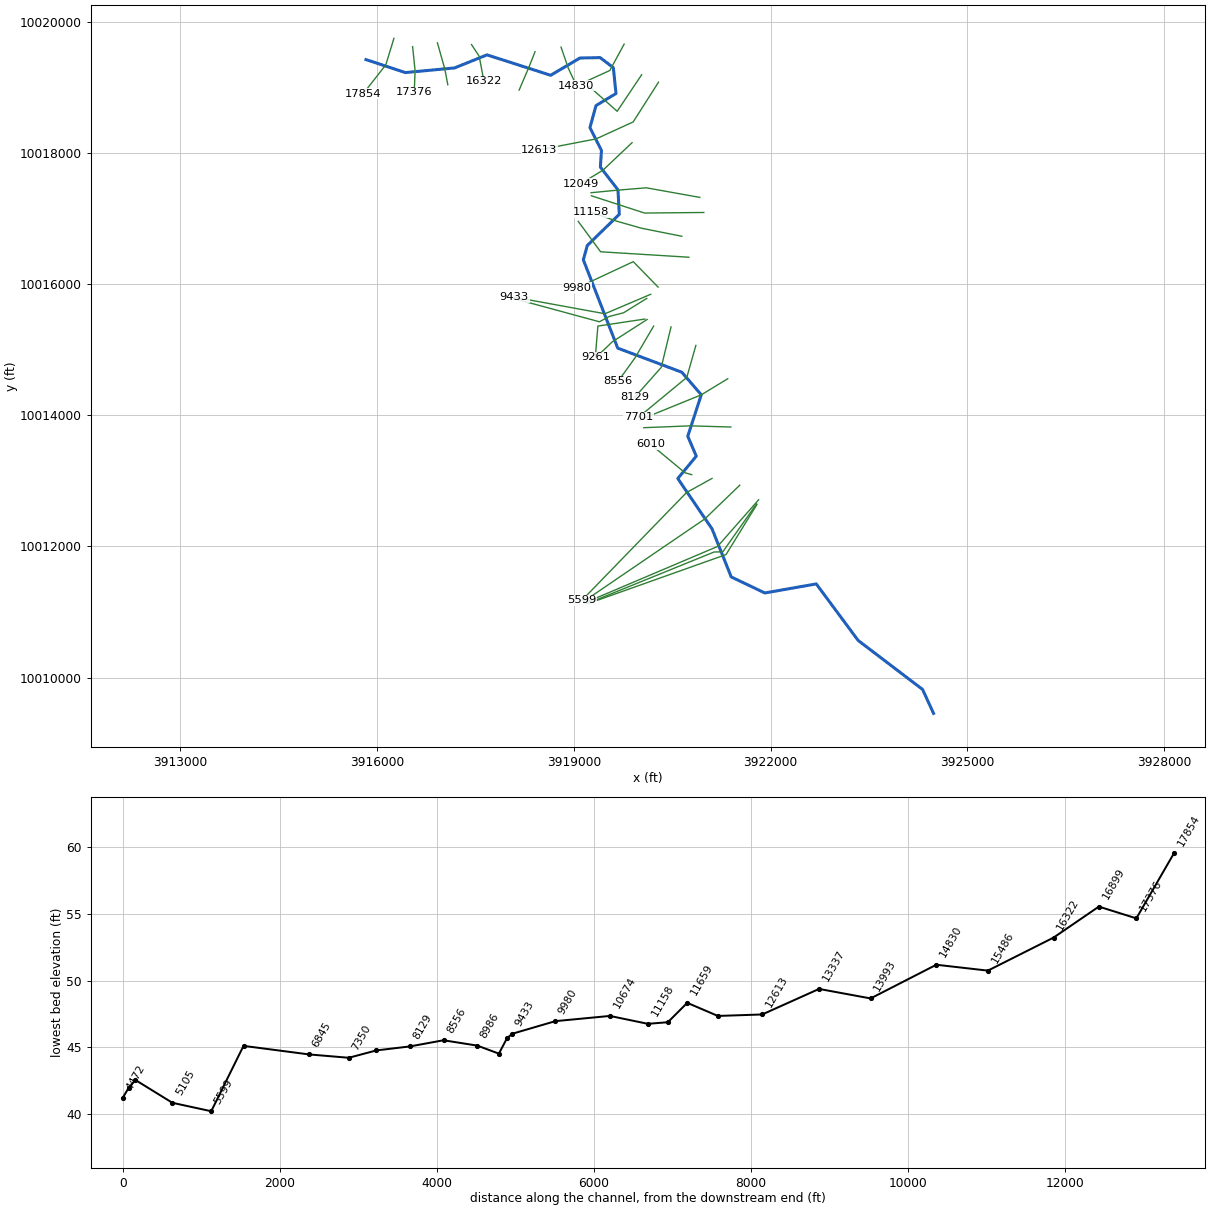
--- G103 36 00.prj (project) ---

Proj Title=G103 36 00 Base Level Engineering
Current Plan=p01
Default Exp/Contr=0.3,0.1
English Units
Geom File=g01
Flow File=f01
Flow File=f02
Plan File=p01
Y Axis Title=Elevation
X Axis Title(PF)=Main Channel Distance
X Axis Title(XS)=Station
BEGIN DESCRIPTION:
G103 36 00
END DESCRIPTION:
DSS Export Rating Curves= 0
DSS Export Rating Curve Sorted= 0
DSS Export Volume Flow Curves= 0
DXF OffsetX= 0
DXF OffsetY= 0
DXF ScaleX= 1
DXF ScaleY= 10

--- G103 36 00.p01 (plan) ---

Plan Title=Multiple Run
Short Identifier=Multiple
Geom File=g01
Flow File=f01
Subcritical Flow
K Sum by GR= 0
Std Step Tol= 0.01
Critical Tol= 0.01
Num of Std Step Trials= 20
Max Error Tol= 0.3
Flow Tol Ratio= 0.001
Split Flow NTrial= 30
Split Flow Tol= 0.02
Split Flow Ratio= 0.02
Log Output Level= 0
Friction Slope Method= 1
Unsteady Friction Slope Method= 2
Unsteady Bridges Friction Slope Method= 1
Parabolic Critical Depth
Global Vel Dist=  1 , 1 , 1
Global Log Level= 0
CheckData=True
Encroach Param= -1, 0, 0, 0
BEGIN DESCRIPTION:
Multiple Run
END DESCRIPTION:

--- G103 36 00.f01 (steady flow) ---

Flow Title=Multiple
Program Version=4.10
Number of Profiles= 7
Profile Names=10-year,25-year,50-year,1pct_min,100-year,1pct_plu,500-year
River Rch & RM=G103 36 00,Reach-1         ,17854
     530     684     895     385    1162    3509    2021
River Rch & RM=G103 36 00,Reach-1         ,14830
     911    1209    1609     703    2123    6411    3813
River Rch & RM=G103 36 00,Reach-1         ,9433
    1168    1562    2091     917    2769    8362    5017
River Rch & RM=G103 36 00,Reach-1         ,4633
    1211    1621    2171     952    2876    8685    5215
Boundary for River Rch & Prof#=G103 36 00,Reach-1         , 1
Up Type= 0
Dn Type= 3
Dn Slope=0.00102
Boundary for River Rch & Prof#=G103 36 00,Reach-1         , 2
Up Type= 0
Dn Type= 3
Dn Slope=0.00102
Boundary for River Rch & Prof#=G103 36 00,Reach-1         , 3
Up Type= 0
Dn Type= 3
Dn Slope=0.00102
Boundary for River Rch & Prof#=G103 36 00,Reach-1         , 4
Up Type= 0
Dn Type= 3
Dn Slope=0.00102
Boundary for River Rch & Prof#=G103 36 00,Reach-1         , 5
Up Type= 0
Dn Type= 3
Dn Slope=0.00102
Boundary for River Rch & Prof#=G103 36 00,Reach-1         , 6
Up Type= 0
Dn Type= 3
Dn Slope=0.00102
Boundary for River Rch & Prof#=G103 36 00,Reach-1         , 7
Up Type= 0
Dn Type= 3
Dn Slope=0.00102
DSS Import GetInterval= 0
DSS Import GetPeak= 0
DSS Import FillOption= 0

--- G103 36 00.f02 (steady flow) ---

Flow Title=Orig_BLE_Flows
Program Version=4.10
Number of Profiles= 7
Profile Names=10-year,25-year,50-year,1pct_min,100-year,1pct_plu,500-year
River Rch & RM=G103 36 00,Reach-1         ,17854
     530     671     778     296     894    2699    1175
River Rch & RM=G103 36 00,Reach-1         ,14830
     911    1185    1399     541    1633    4930    2217
River Rch & RM=G103 36 00,Reach-1         ,9433
    1168    1531    1818     705    2130    6432    2917
River Rch & RM=G103 36 00,Reach-1         ,4633
    1211    1589    1888     733    2212    6681    3032
Boundary for River Rch & Prof#=G103 36 00,Reach-1         , 1
Up Type= 0
Dn Type= 3
Dn Slope=0.00102
Boundary for River Rch & Prof#=G103 36 00,Reach-1         , 2
Up Type= 0
Dn Type= 3
Dn Slope=0.00102
Boundary for River Rch & Prof#=G103 36 00,Reach-1         , 3
Up Type= 0
Dn Type= 3
Dn Slope=0.00102
Boundary for River Rch & Prof#=G103 36 00,Reach-1         , 4
Up Type= 0
Dn Type= 3
Dn Slope=0.00102
Boundary for River Rch & Prof#=G103 36 00,Reach-1         , 5
Up Type= 0
Dn Type= 3
Dn Slope=0.00102
Boundary for River Rch & Prof#=G103 36 00,Reach-1         , 6
Up Type= 0
Dn Type= 3
Dn Slope=0.00102
Boundary for River Rch & Prof#=G103 36 00,Reach-1         , 7
Up Type= 0
Dn Type= 3
Dn Slope=0.00102
DSS Import GetInterval= 0
DSS Import GetPeak= 0
DSS Import FillOption= 0

--- G103 36 00.g01 (geometry) ---

Geom Title=Existing Conditions
Program Version=4.10

River Reach=G103 36 00      ,Reach-1
Reach XY= 30
      3915832.95     10019425.36      3916433.21     10019227.45
      3917182.78     10019298.19      3917677.57     10019497.41
      3918647.62     10019186.22      3919094.24     10019449.24
      3919401.53     10019455.75      3919603.35      10019302.1
      3919643.72     10018907.57      3919339.03     10018723.98
      3919246.58     10018388.04      3919422.36     10018039.08
      3919405.43     10017785.17      3919673.66     10017439.25
       3919694.5     10017065.99      3919206.65      10016590.3
      3919145.89     10016371.55      3919670.19     10015024.32
      3920647.62     10014656.27      3920943.63     10014312.08
      3920737.47     10013680.57      3920867.67     10013376.75
      3920585.56     10013036.04      3921108.56     10012265.64
      3921399.36     10011534.74      3921912.38     10011289.95
      3922696.23     10011427.97      3923334.25     10010565.99
      3924316.02     10009818.59      3924483.67     10009453.37

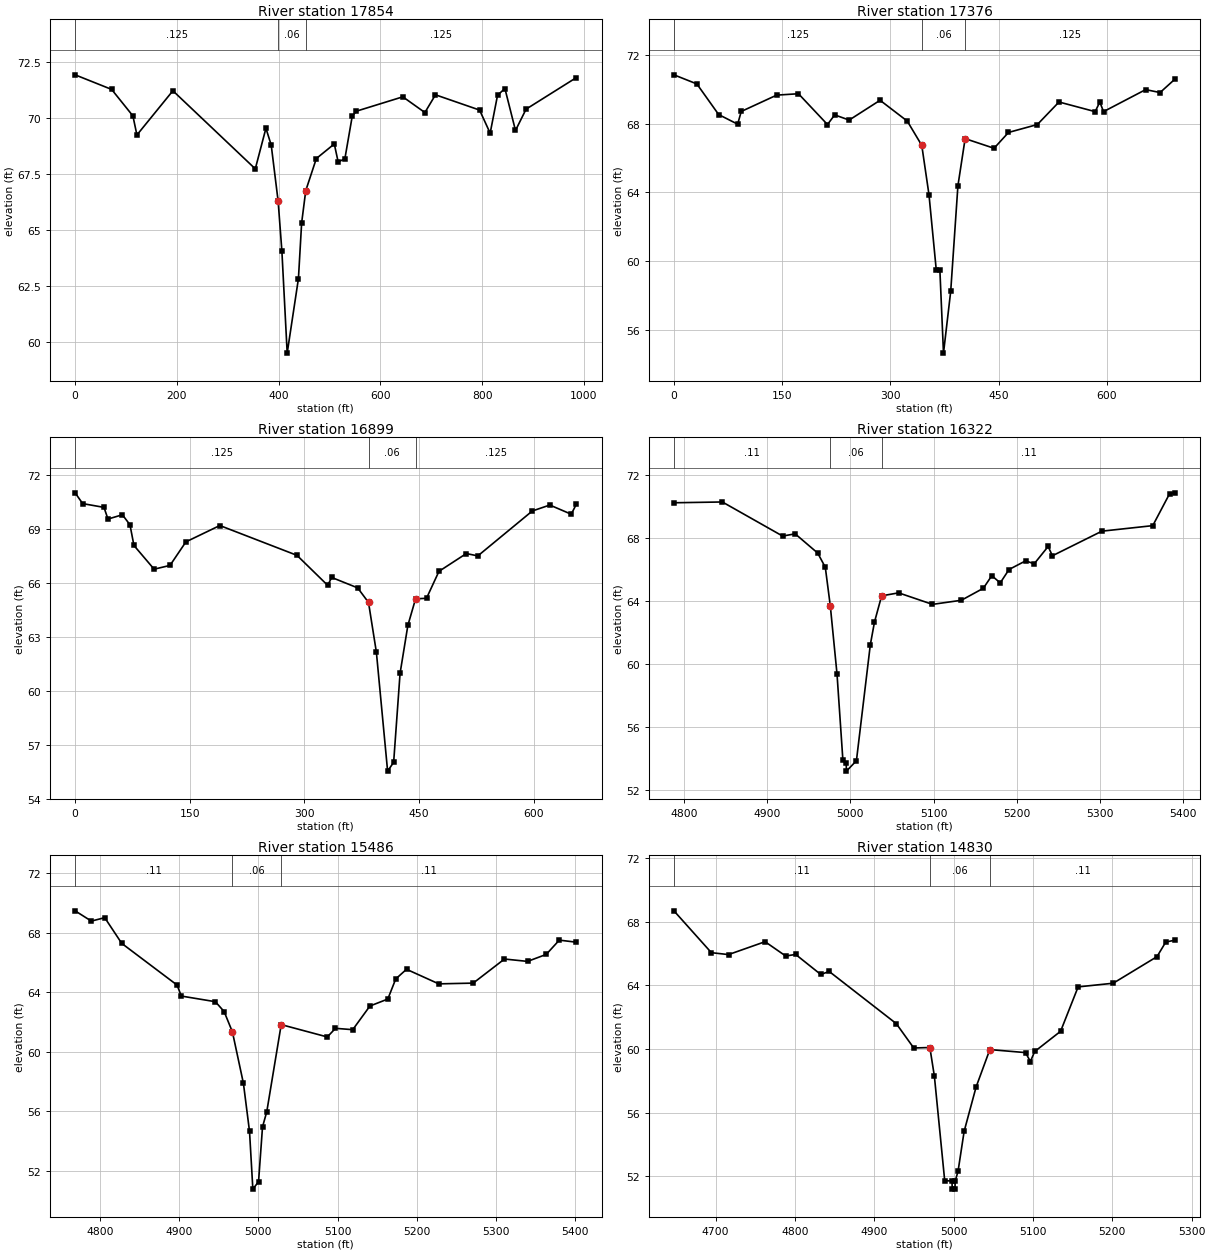
Type RM Length L Ch R = 1 ,17854   ,478,478,478
BEGIN DESCRIPTION:
G 103 36 00 30.0
END DESCRIPTION:
XS GIS Cut Line= 3
      3916259.24     10019749.67      3916135.04     10019344.64
      3915788.24     10018902.49
#Sta/Elev= 30
       0   71.92    71.8   71.27   113.6   70.09   121.5   69.24   192.2   71.21
   354.2   67.73   375.1   69.54   385.5   68.79   399.1   66.29   406.5   64.06
   416.9   59.52     439   62.84   445.3   65.32   453.4   66.76   474.2   68.19
   509.5   68.84   517.1   68.04   530.3   68.18   544.8   70.08   552.9    70.3
   644.2   70.94   687.6   70.24   708.4   71.03   795.1   70.35   815.9   69.32
   830.4   71.01   844.9   71.31   865.7   69.44   886.5   70.39   985.6    71.8
#Mann= 3 , 0 , 0
       0    .125       0   399.1     .06       0   453.4    .125       0
Bank Sta=399.1,453.4
XS Rating Curve= 0 ,0
Exp/Cntr=0.3,0.1

Type RM Length L Ch R = 1 ,17376   ,477,477,477
BEGIN DESCRIPTION:
G 103 36 00 29.0
END DESCRIPTION:
XS GIS Cut Line= 3
      3916543.62     10019622.72      3916581.65     10019256.09
      3916568.79     10018930.01
#Sta/Elev= 30
       0   70.84    31.8   70.31      62   68.53    88.3   67.97    93.3   68.71
   142.4   69.66   172.6   69.74   212.8   67.95   222.8   68.51   242.9   68.21
   285.7   69.36   323.4   68.15   343.5   66.74   353.5   63.87   363.6   59.49
   368.6   59.49   373.6   54.66   383.6   58.25   393.6   64.39   403.6   67.13
   443.7   66.57   463.7   67.49   503.7   67.95   533.7   69.26   583.8    68.7
   590.3   69.26   595.4    68.7   653.8   69.98   673.8   69.81   694.9   70.61
#Mann= 3 , 0 , 0
       0    .125       0   343.5     .06       0   403.6    .125       0
Bank Sta=343.5,403.6
XS Rating Curve= 0 ,0
Exp/Cntr=0.3,0.1

Type RM Length L Ch R = 1 ,16899   ,577,577,577
BEGIN DESCRIPTION:
G 103 36 00 28.0
END DESCRIPTION:
XS GIS Cut Line= 3
      3916922.09     10019680.62      3917034.34     10019282.57
      3917080.24     10019042.39
#Sta/Elev= 30
       0   71.03     9.9   70.43    37.8   70.22      43   69.57    61.9   69.81
    71.8   69.25      77    68.1   103.4   66.78   124.2   66.99     145    68.3
   189.4   69.21   290.4   67.55   330.6   65.88   335.8   66.32   369.8   65.74
     384   64.93   394.3   62.16     409   55.54   416.9   56.03   425.3   60.98
   435.5   63.65   445.6   65.13   459.9   65.16   476.2   66.66     512   67.65
   527.1   67.52   598.4   70.02   621.3   70.35   649.3   69.84   656.2   70.41
#Mann= 3 , 0 , 0
       0    .125       0     384     .06       0   445.6    .125       0
Bank Sta=384,445.6
XS Rating Curve= 0 ,0
Exp/Cntr=0.3,0.1

Type RM Length L Ch R = 1 ,16322   ,836,836,836
BEGIN DESCRIPTION:
G 103 36 00 27.0
END DESCRIPTION:
XS GIS Cut Line= 3
      3917441.35     10019655.23      3917558.54     10019475.55
      3917631.14     10019094.42
#Sta/Elev= 30
    4788   70.23  4846.2   70.28  4918.6   68.12  4933.7   68.26  4960.8   67.04
  4969.9   66.14  4975.9    63.7    4984   59.36    4991   53.94    4995   53.72
  4995.3   53.22  5007.3   53.88    5024   61.23    5029   62.67  5037.6   64.33
    5058   64.52  5098.7   63.79  5133.4   64.05  5159.8   64.81    5170   65.61
  5180.1   65.15  5190.7      66  5210.7   66.55  5220.9   66.36  5237.7   67.46
  5242.8   66.87  5302.3   68.43  5363.4   68.78  5383.7   70.81  5390.5   70.86
#Mann= 3 , 0 , 0
    4788     .11       0  4975.9     .06       0  5037.6     .11       0
Bank Sta=4975.9,5037.6
XS Rating Curve= 0 ,0
Exp/Cntr=0.3,0.1

Type RM Length L Ch R = 1 ,15486   ,656,656,656
BEGIN DESCRIPTION:
G 103 36 00 26.0
END DESCRIPTION:
XS GIS Cut Line= 3
      3918410.09     10019545.82      3918326.77     10019334.92
      3918167.85     10018961.06
#Sta/Elev= 30
  4768.7   69.46  4789.2   68.77  4806.1      69  4827.6   67.27  4897.4   64.47
  4902.8   63.73  4945.8   63.35  4956.8   62.69  4967.3   61.32  4981.2   57.86
  4988.9   54.63  4993.1   50.75  5000.3   51.25  5005.3   54.93  5010.7   55.96
  5028.9   61.81  5087.1   60.98  5097.4   61.56  5119.2   61.47  5140.9   63.06
  5163.5   63.53  5173.5   64.88  5187.1   65.53  5227.8   64.55  5271.3    64.6
  5310.8   66.22  5339.9   66.06  5363.5   66.53    5380   67.49  5401.7   67.35
#Mann= 3 , 0 , 0
  4768.7     .11       0  4967.3     .06       0  5028.9     .11       0
Bank Sta=4967.3,5028.9
XS Rating Curve= 0 ,0
Exp/Cntr=0.3,0.1

Type RM Length L Ch R = 1 ,14830   ,837,837,837
BEGIN DESCRIPTION:
Mapping XS aa3fada7
END DESCRIPTION:
XS GIS Cut Line= 3
      3918805.95     10019616.14      3918917.92     10019290.65
      3919040.33     10019030.19
#Sta/Elev= 30
  4647.4   68.68  4694.6   66.05  4716.2   65.93  4762.3   66.74  4788.3   65.84
  4800.8   65.94  4832.5   64.68  4843.1   64.87  4927.7   61.59  4949.7   60.06
    4970   60.09  4975.7   58.29  4988.7   51.73  4997.9   51.69  4998.2   51.19
  5001.7   51.19  5001.9   51.69  5005.5    52.3  5013.2   54.82  5028.3   57.61
  5045.6   59.96  5090.6   59.77  5096.7   59.21  5102.2   59.84  5134.8   61.11
  5156.9    63.9  5201.1   64.13  5256.3    65.8  5267.4   66.72  5279.4   66.84
#Mann= 3 , 0 , 0
  4647.4     .11       0    4970     .06       0  5045.6     .11       0
Bank Sta=4970,5045.6
XS Rating Curve= 0 ,0
Exp/Cntr=0.3,0.1

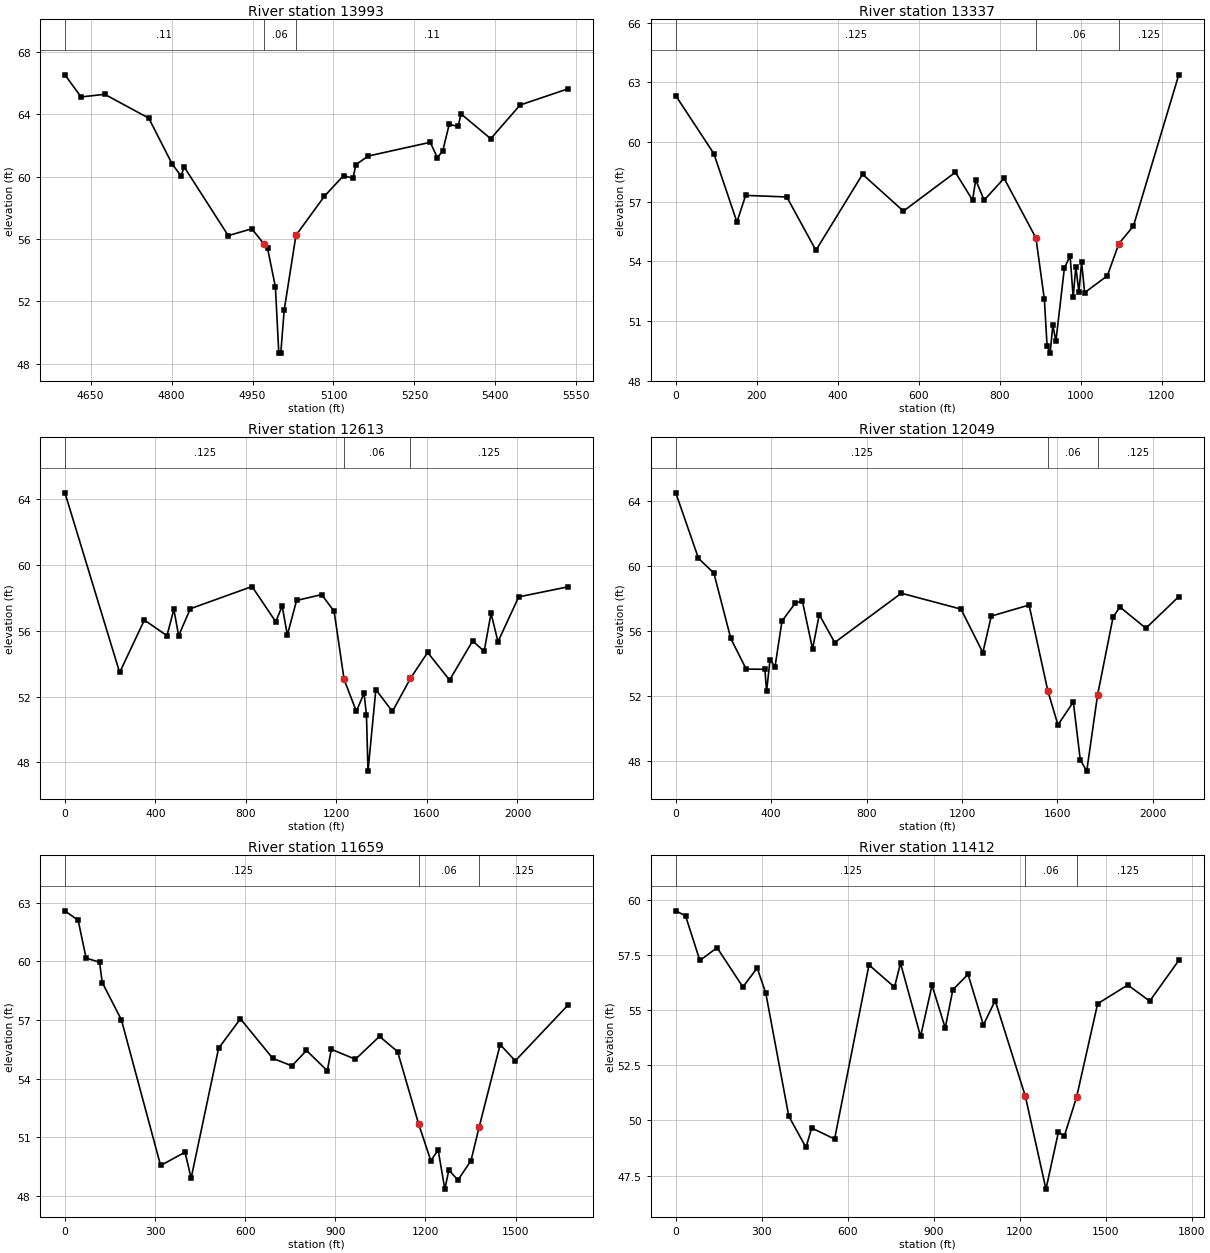
Type RM Length L Ch R = 1 ,13993   ,656,656,656
BEGIN DESCRIPTION:
G 103 36 00 25.0
END DESCRIPTION:
XS GIS Cut Line= 3
      3919767.85     10019661.07      3919549.86     10019259.62
      3919117.82     10019061.06
#Sta/Elev= 30
  4602.3   66.53  4632.2   65.11    4676   65.28  4757.7   63.75  4801.4   60.78
  4817.6   60.05  4823.3   60.62    4905   56.21  4948.7   56.65  4970.6    55.7
  4977.8   55.41  4992.4   52.92  4998.7   48.67  5002.4   48.67  5008.6   51.41
  5030.5   56.23  5083.3   58.74  5118.7   60.06  5136.2   59.89  5141.7   60.77
  5164.6   61.32  5279.5    62.2  5292.4   61.22  5302.5   61.63  5314.5   63.35
    5331   63.22  5336.5   64.02  5391.5   62.43  5445.9   64.59  5534.6   65.63
#Mann= 3 , 0 , 0
  4602.3     .11       0  4970.6     .06       0  5030.5     .11       0
Bank Sta=4970.6,5030.5
XS Rating Curve= 0 ,0
Exp/Cntr=0.3,0.1

Type RM Length L Ch R = 1 ,13337   ,724,724,724
BEGIN DESCRIPTION:
Mapping XS f13f10dd
END DESCRIPTION:
XS GIS Cut Line= 3
      3920034.94      10019194.5      3919661.68     10018636.78
      3919234.16     10019016.55
#Sta/Elev= 30
       0   62.32      94   59.41   151.1   55.97   172.6   57.31   274.2   57.23
   346.2   54.55   461.4   58.37   562.4   56.52   690.7   58.47   733.3   57.07
   740.9   58.09   761.8   57.07   811.1   58.17   889.7   55.17   910.6   52.08
   917.3   49.74   924.8   49.38   931.5   50.78   939.1   49.98     960   53.65
   974.2   54.27   981.7    52.2   988.4   53.71   995.9   52.45  1002.6   53.95
  1010.1   52.42  1066.2   53.27  1094.6   54.88  1130.6   55.77  1242.6   63.37
#Mann= 3 , 0 , 0
       0    .125       0   889.7     .06       0  1094.6    .125       0
Bank Sta=889.7,1094.6
XS Rating Curve= 0 ,0
Exp/Cntr=0.3,0.1

Type RM Length L Ch R = 1 ,12613   ,564,564,564
BEGIN DESCRIPTION:
G 103 36 00 24.0
END DESCRIPTION:
XS GIS Cut Line= 4
      3920291.88      10019081.3       3919905.6     10018474.47
      3919338.92     10018215.35      3918474.34     10018048.68
#Sta/Elev= 30
       0    64.4   241.8   53.47     351   56.66   450.9   55.71   481.4   57.31
   502.5   55.71   554.2   57.35   826.8    58.7   931.6   56.56   960.1   57.51
   983.1   55.75  1023.7   57.85  1134.7   58.21  1189.7   57.19  1233.7   53.05
  1287.9   51.11  1321.9   52.21  1332.6   50.89  1339.4   47.47  1374.1   52.43
  1447.4    51.1  1526.9   53.11    1603   54.69    1700   53.01  1801.8   55.39
  1852.7   54.76  1883.3   57.07  1913.9   55.34  2005.5   58.07    2223   58.68
#Mann= 3 , 0 , 0
       0    .125       0  1233.7     .06       0  1526.9    .125       0
Bank Sta=1233.7,1526.9
XS Rating Curve= 0 ,0
Exp/Cntr=0.3,0.1

Type RM Length L Ch R = 1 ,12049   ,390,390,390
BEGIN DESCRIPTION:
G 103 36 00 23.0
END DESCRIPTION:
XS GIS Cut Line= 3
      3919888.41     10018158.07      3919446.23      10017739.6
      3919107.18     10017533.07
#Sta/Elev= 30
       0   64.52    95.1   60.48   159.7   59.57   230.6   55.54   295.2   53.65
   373.6   53.64   380.6   52.27   395.2   54.23     416   53.79   445.2   56.61
   501.5   57.73   530.7   57.85   573.4   54.89   601.5   57.01   666.2   55.29
   945.5   58.33  1195.6   57.35  1287.3   54.67  1322.7   56.92  1481.1    57.6
  1559.7   52.31    1602   50.21  1666.6   51.62  1695.8   48.05  1722.8   47.36
  1768.2   52.05  1833.2   56.85  1861.9   57.48  1970.7   56.17  2108.6   58.12
#Mann= 3 , 0 , 0
       0    .125       0  1559.7     .06       0  1768.2    .125       0
Bank Sta=1559.7,1768.2
XS Rating Curve= 0 ,0
Exp/Cntr=0.3,0.1

Type RM Length L Ch R = 1 ,11659   ,247,247,247
BEGIN DESCRIPTION:
G 103 36 00 22.0
END DESCRIPTION:
XS GIS Cut Line= 4
      3920921.22     10017323.48       3920105.7     10017469.87
      3919669.65      10017434.1       3919263.4     10017395.03
#Sta/Elev= 30
       0   62.59    44.1    62.1    70.4   60.17   115.2   59.96   124.1   58.92
   187.9   57.01   318.4   49.55   399.7   50.23     420    48.9   511.4   55.55
   584.1   57.06   691.5   55.04   755.4   54.65     804   55.44   873.3    54.4
   886.6    55.5   966.9   54.99  1047.1   56.16  1107.3   55.38  1177.6   51.66
  1217.7    49.8  1242.3   50.34  1264.5   48.34  1277.9   49.32  1308.1    48.8
  1351.6    49.8  1378.4    51.5  1448.7   55.74  1498.9   54.91  1674.2   57.76
#Mann= 3 , 0 , 0
       0    .125       0  1177.6     .06       0  1378.4    .125       0
Bank Sta=1177.6,1378.4
XS Rating Curve= 0 ,0
Exp/Cntr=0.3,0.1

Type RM Length L Ch R = 1 ,11412   ,254,254,254
BEGIN DESCRIPTION:
Mapping XS fbc80ef4
END DESCRIPTION:
XS GIS Cut Line= 3
      3920981.99     10017093.45      3920079.21     10017084.77
      3919268.61     10017348.16
#Sta/Elev= 30
       0    59.5    34.1   59.27    84.1   57.25   144.1   57.83   234.1   56.05
   284.1   56.91   314.2   55.76   394.2    50.2   454.2   48.78   474.2   49.66
   554.2   49.16   674.2   57.05   763.2   56.04   784.2   57.13   854.2   53.81
   894.2   56.13   940.2   54.19   966.9   55.93  1019.9   56.62  1073.3   54.33
  1114.5   55.43  1219.7    51.1  1291.7   46.89  1335.3   49.48  1355.6   49.29
  1398.4   51.05    1472   55.29  1577.2   56.14  1653.7   55.41  1755.1   57.25
#Mann= 3 , 0 , 0
       0    .125       0  1219.7     .06       0  1398.4    .125       0
Bank Sta=1219.7,1398.4
XS Rating Curve= 0 ,0
Exp/Cntr=0.3,0.1

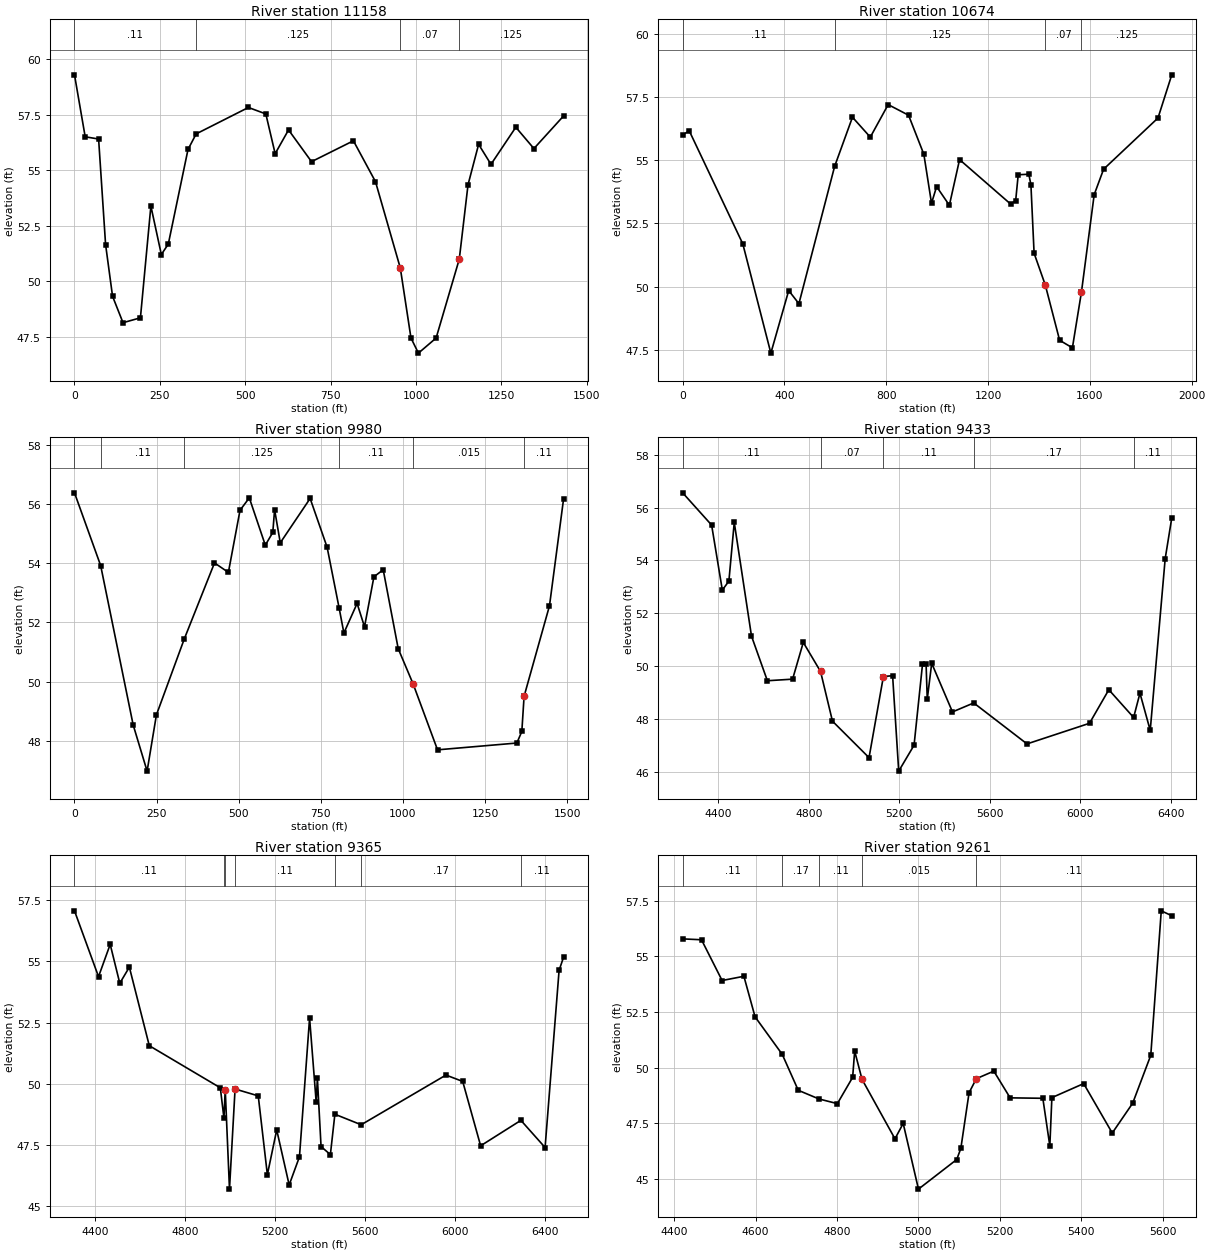
Type RM Length L Ch R = 1 ,11158   ,484,484,484
BEGIN DESCRIPTION:
G 103 36 00 21.0
END DESCRIPTION:
XS GIS Cut Line= 4
      3920647.09     10016730.64      3920032.34     10016853.46
      3919656.63     10016960.14      3919266.01     10017098.16
#Sta/Elev= 30
       0    59.3    31.3   56.51    70.6   56.41      91   51.66   111.4   49.33
     142   48.14     193   48.36   223.6   53.39   254.2   51.21   274.6   51.68
   332.3   55.94   356.1   56.64   509.1   57.83   560.1   57.54   587.4   55.75
   626.6   56.82   693.9   55.39   816.5   56.33   881.1   54.49   953.8    50.6
     985   47.45  1006.8   46.77  1058.6   47.45  1126.4      51    1152   54.35
    1183   56.17  1219.2   55.27  1291.9   56.94  1344.9   55.98  1431.8   57.45
#Mann= 4 ,-1 , 0
       0     .11       0   356.1    .125       0   953.8     .07       0
  1126.4    .125       0
Bank Sta=953.8,1126.4
XS Rating Curve= 0 ,0
Exp/Cntr=0.3,0.1

Type RM Length L Ch R = 1 ,10674   ,694,694,694
BEGIN DESCRIPTION:
Mapping XS b57e5e8d
END DESCRIPTION:
XS GIS Cut Line= 3
      3920753.69     10016411.16      3919409.23     10016493.99
      3919068.09     10016957.53
#Sta/Elev= 30
       0   56.01    25.9   56.17   236.3   51.69   346.5   47.36   416.6   49.84
   456.7   49.32     597   54.76   667.1   56.71   737.2   55.92   807.4   57.21
   887.5   56.79   947.6   55.24   977.7    53.3   997.7   53.96  1047.8   53.22
  1087.9   55.03  1288.3   53.27  1308.3    53.4  1318.3   54.43  1359.9   54.45
  1368.2   54.04  1380.7   51.32  1424.7   50.06    1481   47.87  1531.2   47.57
  1566.9   49.79  1616.8   53.64  1653.8   54.65  1867.5   56.68  1921.6   58.39
#Mann= 4 ,-1 , 0
       0     .11       0     597    .125       0  1424.7     .07       0
  1566.9    .125       0
Bank Sta=1424.7,1566.9
XS Rating Curve= 0 ,0
Exp/Cntr=0.3,0.1

Type RM Length L Ch R = 1 ,9980    ,547,547,547
BEGIN DESCRIPTION:
G 103 36 00 20.0
END DESCRIPTION:
XS GIS Cut Line= 3
      3920284.94     10015955.43      3919907.33     10016343.45
      3919048.91     10015941.56
#Sta/Elev= 30
       0   56.38    79.7   53.92   178.7   48.53   221.1   46.97   249.4   48.87
   334.3   51.44   426.3   54.01   468.6   53.69     504   55.79   532.3   56.21
     581   54.61   603.8   55.04   609.3   55.81   626.6   54.69   717.5   56.19
   769.2   54.54   805.9   52.48   820.3   51.64   860.5   52.64   883.1   51.85
   911.7   53.54     940   53.78   985.7   51.11  1031.4   49.91  1105.4   47.69
  1346.9   47.92  1362.1   48.31    1369    49.5  1446.3   52.56  1489.3   56.18
#Mann= 6 ,-1 , 0
       0    .125       0    79.7     .11       0   334.3    .125       0
   805.9     .11       0  1031.4    .015       0    1369     .11       0
Bank Sta=1031.4,1369
XS Rating Curve= 0 ,0
Exp/Cntr=0.3,0.1

Type RM Length L Ch R = 1 ,9433    ,68,68,68
BEGIN DESCRIPTION:
G 103 36 00 19.0
END DESCRIPTION:
XS GIS Cut Line= 3
      3920172.29     10015845.57      3919475.75     10015548.63
      3918094.16     10015801.28
#Sta/Elev= 30
  4242.8   56.56  4370.8   55.34  4418.1   52.88  4447.1   53.22  4470.8   55.44
    4547   51.14  4617.2   49.45  4728.7   49.51  4775.9    50.9  4852.2    49.8
  4904.9   47.92  5066.5   46.54    5130   49.61  5170.7   49.64  5197.7   46.03
  5265.5   47.01  5302.8   50.07  5318.7   50.07  5323.8   48.75  5343.5   50.11
  5435.3   48.27  5529.3   48.61  5764.7   47.06  6040.9   47.84  6126.3   49.11
  6235.9   48.06  6263.9   48.98  6309.3   47.57  6375.4   54.07  6404.5   55.61
#Mann= 5 ,-1 , 0
  4242.8     .11       0  4852.2     .07       0    5130     .11       0
  5529.3     .17       0  6235.9     .11       0
Bank Sta=4852.2,5130
XS Rating Curve= 0 ,0
Exp/Cntr=0.3,0.1

Type RM Length L Ch R = 1 ,9365    ,104,104,104
BEGIN DESCRIPTION:
Mapping XS 16f9687a
END DESCRIPTION:
XS GIS Cut Line= 5
      3920112.39     10015783.07       3919760.8      10015564.3
      3919539.44     10015507.01      3919391.01     10015426.28
      3918078.55     10015783.04
#Sta/Elev= 30
  4309.3   57.07    4416   54.38  4467.8    55.7  4510.4   54.11  4552.9   54.77
  4641.4   51.56  4956.8   49.84  4972.9    48.6  4978.6   49.77  4997.5    45.7
  5022.3   49.79  5125.2   49.51  5165.7   46.29  5207.2   48.12  5262.5   45.87
  5308.2   47.02  5353.2   52.69  5382.6   49.24  5387.8   50.23  5404.1   47.44
  5445.5   47.11  5465.5   48.76  5582.3   48.33  5958.7   50.36  6033.1    50.1
  6112.7   47.47  6291.5   48.51  6398.9    47.4  6461.1   54.64  6481.1   55.18
#Mann= 7 ,-1 , 0
  4309.3     .11       0  4972.9     .11       0  4978.6     .07       0
  5022.3     .11       0  5465.5     .15       0  5582.3     .17       0
  6291.5     .11       0
Bank Sta=4978.6,5022.3
XS Rating Curve= 0 ,0
Exp/Cntr=0.3,0.1

Type RM Length L Ch R = 1 ,9261    ,275,275,275
BEGIN DESCRIPTION:
Mapping XS a686de86
END DESCRIPTION:
XS GIS Cut Line= 3
      3920083.67     10015467.94      3919367.57     10015361.18
      3919328.57     10014885.39
#Sta/Elev= 30
    4421   55.78  4467.3   55.74  4517.9   53.91  4571.4    54.1  4598.8   52.28
  4665.7   50.59  4704.9   48.98  4755.8   48.59    4801   48.38  4838.5   49.56
  4843.5   50.74  4861.6   49.47  4942.5    46.8  4962.7   47.49  5000.2   44.54
  5094.2   45.87  5104.3   46.37  5124.5   48.87  5142.3    49.5  5185.3   49.84
  5225.4   48.64  5305.7   48.62  5322.9   46.48  5327.9   48.65    5406   49.28
  5476.2   47.06  5526.4    48.4  5570.8   50.55  5596.6   57.04  5622.4   56.82
#Mann= 5 ,-1 , 0
    4421     .11       0  4665.7     .17       0  4755.8     .11       0
  4861.6    .015       0  5142.3     .11       0
Bank Sta=4861.6,5142.3
XS Rating Curve= 0 ,0
Exp/Cntr=0.3,0.1

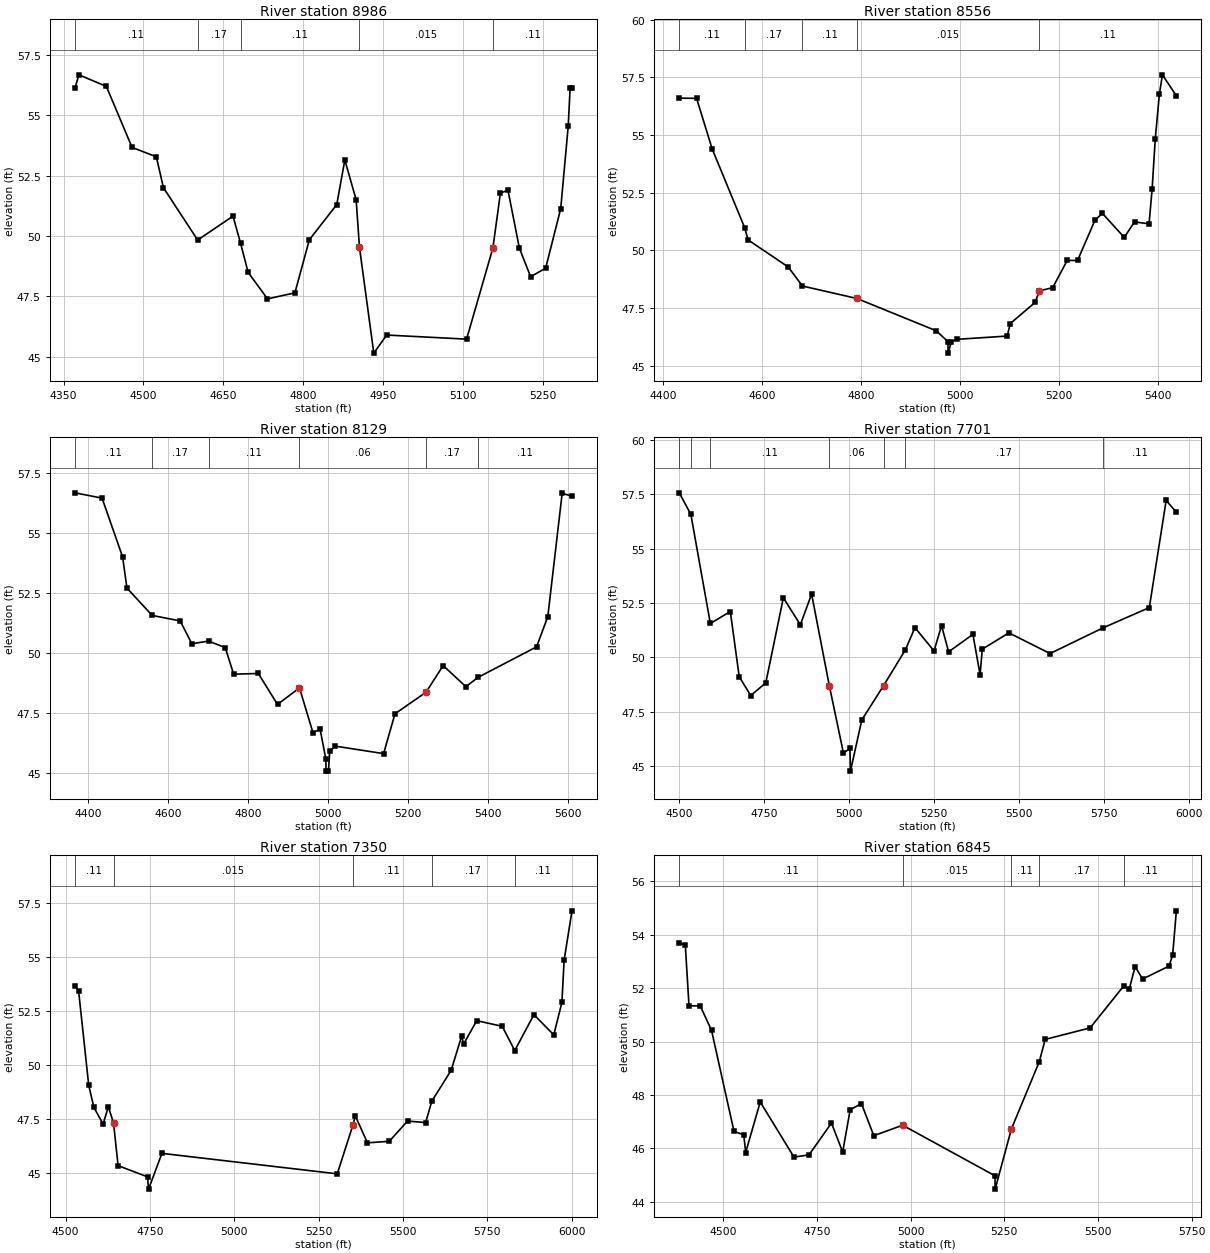
Type RM Length L Ch R = 1 ,8986    ,430,430,430
BEGIN DESCRIPTION:
G 103 36 00 18.0
END DESCRIPTION:
XS GIS Cut Line= 3
      3920117.85     10015461.07      3919588.59     10015121.55
      3919367.85     10014911.07
#Sta/Elev= 30
  4371.2   56.13  4378.8   56.68  4430.3    56.2  4478.6   53.67  4524.2   53.28
  4537.5      52  4601.8   49.83  4668.2   50.82  4682.5   49.69  4696.6   48.49
    4733   47.39  4784.5   47.64  4811.6   49.84  4863.1    51.3  4878.3   53.15
  4899.5    51.5  4905.8   49.52  4932.7   45.14  4956.9   45.89    5107   45.72
  5156.4    49.5  5170.5   51.77  5184.7    51.9  5206.1    49.5  5227.2   48.31
  5255.5   48.66  5283.8   51.13  5297.9   54.55  5301.5   56.14    5305   56.14
#Mann= 5 ,-1 , 0
  4371.2     .11       0  4601.8     .17       0  4682.5     .11       0
  4905.8    .015       0  5156.4     .11       0
Bank Sta=4905.8,5156.4
XS Rating Curve= 0 ,0
Exp/Cntr=0.3,0.1

Type RM Length L Ch R = 1 ,8556    ,427,427,427
BEGIN DESCRIPTION:
G 103 36 00 17.0
END DESCRIPTION:
XS GIS Cut Line= 3
      3920217.86     10015361.09      3919930.61     10014871.55
      3919674.04     10014516.43
#Sta/Elev= 30
  4432.4    56.6  4467.5   56.59  4498.9    54.4  4564.9   50.97  4571.6   50.45
  4652.7   49.28  4681.6   48.45  4791.8   47.91  4952.2   46.51  4975.9   46.04
  4976.4   45.54    4983   46.04  4995.2   46.14  5095.9   46.28    5102   46.82
  5152.3   47.74  5160.9   48.24  5187.9   48.38  5217.3   49.56  5238.2   49.56
  5273.8   51.32  5288.5    51.6  5332.6   50.56  5353.5   51.23  5382.9   51.15
  5389.1   52.67  5395.4   54.83  5403.8   56.78  5409.9   57.61  5438.1    56.7
#Mann= 5 ,-1 , 0
  4432.4     .11       0  4564.9     .17       0  4681.6     .11       0
  4791.8    .015       0  5160.9     .11       0
Bank Sta=4791.8,5160.9
XS Rating Curve= 0 ,0
Exp/Cntr=0.3,0.1

Type RM Length L Ch R = 1 ,8129    ,428,428,428
BEGIN DESCRIPTION:
G 103 36 00 16.0
END DESCRIPTION:
XS GIS Cut Line= 3
      3920482.37     10015347.06      3920333.39     10014730.92
      3919929.16     10014274.75
#Sta/Elev= 30
  4366.1   56.68    4434   56.46  4485.4   54.01  4496.3   52.71  4559.4   51.57
  4629.5   51.34  4658.5   50.39  4700.4    50.5  4742.2   50.23  4763.2   49.12
  4824.9   49.15  4872.9   47.86  4927.8   48.55  4961.8   46.67  4979.3   46.84
  4993.8   45.58  4994.3   45.08  5000.4   45.08  5003.6   45.92  5017.9   46.12
  5138.3   45.81  5166.7   47.47  5244.5   48.37  5287.2   49.48  5344.1    48.6
  5374.7   48.99  5520.9   50.26    5549   51.52  5584.9   56.66  5609.5   56.54
#Mann= 6 ,-1 , 0
  4366.1     .11       0  4559.4     .17       0  4700.4     .11       0
  4927.8     .06       0  5244.5     .17       0  5374.7     .11       0
Bank Sta=4927.8,5244.5
XS Rating Curve= 0 ,0
Exp/Cntr=0.3,0.1

Type RM Length L Ch R = 1 ,7701    ,351,351,351
BEGIN DESCRIPTION:
G 103 36 00 15.0
END DESCRIPTION:
XS GIS Cut Line= 3
      3920861.12     10015065.45      3920722.24     10014577.22
      3919986.54     10013969.56
#Sta/Elev= 30
  4500.2   57.56  4534.3   56.57  4591.6   51.56  4650.3   52.11  4676.5   49.12
  4710.3   48.25  4754.6   48.83  4806.3   52.74  4856.2    51.5  4889.4   52.91
  4941.4   48.71    4983   45.61  5002.1   45.82  5003.6   44.78    5037   47.13
  5100.8    48.7  5165.1   50.35  5193.3   51.37  5249.3    50.3  5271.5   51.46
  5292.3   50.26  5363.7   51.06  5384.8   49.21  5391.3   50.38  5469.5   51.13
  5590.6   50.18  5746.5   51.36  5882.5   52.29    5932   57.21    5962   56.67
#Mann= 7 ,-1 , 0
  4500.2     .11       0  4534.3     .17       0  4591.6     .11       0
  4941.4     .06       0  5100.8     .11       0  5165.1     .17       0
  5746.5     .11       0
Bank Sta=4941.4,5100.8
XS Rating Curve= 0 ,0
Exp/Cntr=0.3,0.1

Type RM Length L Ch R = 1 ,7350    ,505,505,505
BEGIN DESCRIPTION:
G 103 36 00 14.0
END DESCRIPTION:
XS GIS Cut Line= 3
      3921347.27     10014557.71      3920943.63     10014312.08
       3920016.2     10013934.35
#Sta/Elev= 30
  4527.5   53.66  4538.5   53.43  4568.5   49.05  4583.9   48.02  4611.1   47.25
  4626.6   48.05    4642   47.31  4655.6   45.32  4742.8    44.8  4745.9   44.23
  4785.5   45.89  5305.4   44.94  5351.8    47.2  5358.9   47.63    5395   46.38
  5459.7   46.45  5513.7   47.39  5567.5   47.32  5585.7   48.31  5643.3   49.75
  5674.5   51.35  5679.9   50.96  5718.9   52.05  5794.5   51.79  5831.6   50.66
  5888.5   52.33  5947.4   51.39  5971.5    52.9    5978   54.85  6001.4   57.15
#Mann= 5 ,-1 , 0
  4527.5     .11       0    4642    .015       0  5351.8     .11       0
  5585.7     .17       0  5831.6     .11       0
Bank Sta=4642,5351.8
XS Rating Curve= 0 ,0
Exp/Cntr=0.3,0.1

Type RM Length L Ch R = 1 ,6845    ,835,835,835
BEGIN DESCRIPTION:
G 103 36 00 13.0
END DESCRIPTION:
XS GIS Cut Line= 3
      3921393.87     10013821.03      3920776.53     10013838.99
      3920067.88     10013811.07
#Sta/Elev= 30
  4382.4   53.67  4398.4   53.63  4408.4   51.34  4438.4   51.33  4468.5   50.42
  4528.5   46.64  4554.6   46.51  4559.6   45.85  4598.5   47.74  4688.5   45.68
  4728.6   45.76  4788.6   46.95  4818.6   45.87  4838.6   47.45  4868.6   47.68
  4901.6   46.48  4978.7   46.87    5225   44.98  5225.5   44.48  5268.9   46.73
  5343.4   49.25    5359   50.08    5479   50.51  5568.7   52.08  5583.2   51.95
  5599.1    52.8  5619.2   52.34  5689.2   52.82  5699.2   53.22  5709.2   54.89
#Mann= 5 ,-1 , 0
  4382.4     .11       0  4978.7    .015       0  5268.9     .11       0
  5343.4     .17       0  5568.7     .11       0
Bank Sta=4978.7,5268.9
XS Rating Curve= 0 ,0
Exp/Cntr=0.3,0.1

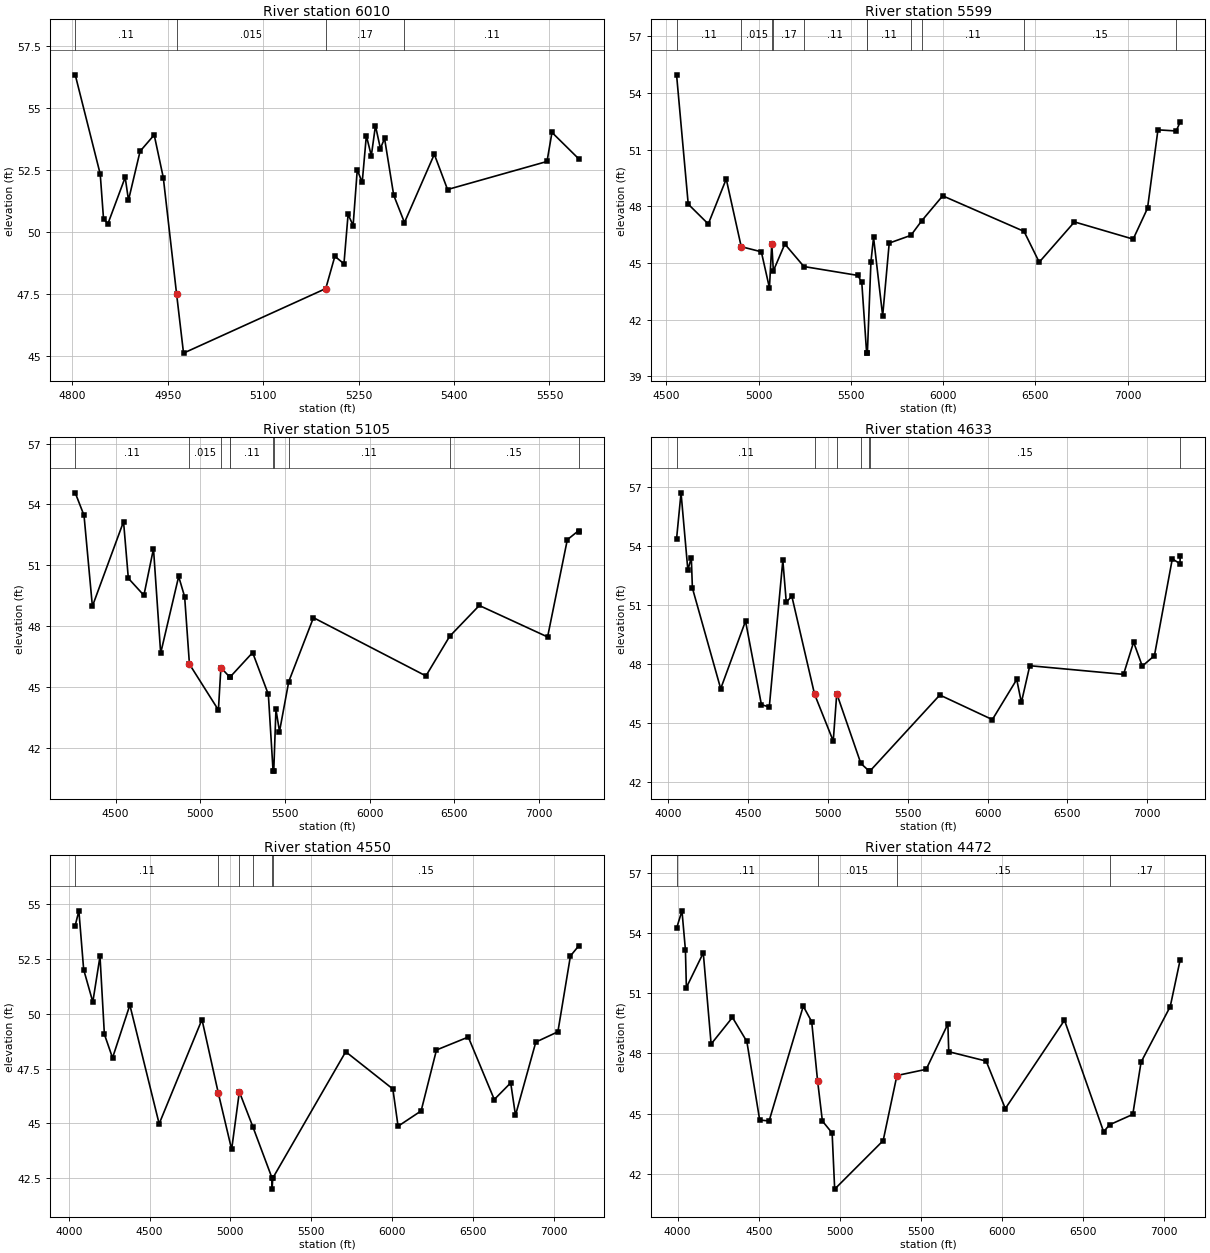
Type RM Length L Ch R = 1 ,6010    ,411,411,411
BEGIN DESCRIPTION:
G 103 36 00 11.0
END DESCRIPTION:
XS GIS Cut Line= 3
      3920797.43     10013094.48      3920695.91     10013123.11
      3920167.87     10013561.06
#Sta/Elev= 30
  4804.7   56.33    4844   52.33  4849.2   50.52  4856.2   50.34  4883.2    52.2
  4888.4   51.28  4906.6   53.25  4928.8   53.91  4943.1   52.19    4964    47.5
  4974.9   45.12  5198.4   47.72  5212.7   49.02    5227   48.72  5233.5   50.71
  5241.4   50.26  5247.9    52.5  5255.7      52  5262.2   53.88    5270   53.07
  5276.5   54.28  5284.3   53.36  5290.8   53.77  5305.2   51.48  5322.1   50.38
    5369   53.13  5389.8   51.71  5546.1   52.84  5553.9   54.01  5596.2   52.94
#Mann= 4 ,-1 , 0
  4804.7     .11       0    4964    .015       0  5198.4     .17       0
  5322.1     .11       0
Bank Sta=4964,5198.4
XS Rating Curve= 0 ,0
Exp/Cntr=0.3,0.1

Type RM Length L Ch R = 1 ,5599    ,494,494,494
BEGIN DESCRIPTION:
G 103 36 00 10.0
END DESCRIPTION:
XS GIS Cut Line= 3
      3921107.36     10013037.17      3920717.93      10012821.2
       3919127.3     10011180.88
#Sta/Elev= 30
  4554.7   54.95  4617.9   48.11  4726.6   47.06  4823.9   49.44  4905.2   45.86
  5014.2   45.59  5058.1   43.68  5070.8      46  5079.4   44.58  5141.5      46
  5244.9   44.81  5537.6   44.34  5558.7   43.97    5585   40.23    5589   40.23
  5608.4   45.07  5622.5   46.35  5671.9    42.2  5707.4   46.05    5825   46.46
  5882.8   47.22  5997.3   48.55  6438.2   46.67  6520.5   45.04  6711.6   47.17
  7029.8   46.26  7107.5   47.89  7164.1   52.04  7262.9   51.98  7284.9   52.46
#Mann= 11 ,-1 , 0
  4554.7     .11       0  4905.2    .015       0  5070.8     .11       0
  5079.4     .17       0  5244.9     .11       0    5585     .08       0
    5589     .11       0    5825     .15       0  5882.8     .11       0
  6438.2     .15       0  7262.9     .17       0
Bank Sta=4905.2,5070.8
XS Rating Curve= 0 ,0
Exp/Cntr=0.3,0.1

Type RM Length L Ch R = 1 ,5105    ,472,472,472
BEGIN DESCRIPTION:
G 103 36 00 9.0
END DESCRIPTION:
XS GIS Cut Line= 3
      3921529.25     10012933.02      3920997.88     10012419.72
      3919152.24     10011160.48
#Sta/Elev= 30
  4261.2   54.57  4313.1   53.46  4362.5   48.98  4546.4   53.15  4574.7   50.36
  4666.6   49.52  4723.2   51.82  4765.6   46.67  4871.8   50.45  4907.1   49.45
  4935.4   46.13  5106.4   43.87  5121.1   45.96  5172.5    45.5  5173.7   45.48
  5308.4    46.7  5401.2   44.64  5429.1   40.86  5433.1   40.86    5446    43.9
    5467   42.81  5521.6   45.27  5667.4   48.42  6331.4   45.55  6471.4    47.5
  6646.4   49.02  7049.5   47.47    7166   52.26  7233.1   52.71  7234.3   52.65
#Mann= 10 ,-1 , 0
  4261.2     .11       0  4935.4    .015       0  5121.1     .11       0
  5172.5     .17       0  5173.7     .11       0  5429.1     .08       0
  5433.1     .11       0  5521.6     .11       0  6471.4     .15       0
  7233.1     .17       0
Bank Sta=4935.4,5121.1
XS Rating Curve= 0 ,0
Exp/Cntr=0.3,0.1

Type RM Length L Ch R = 1 ,4633    ,83,83,83
BEGIN DESCRIPTION:
G 103 36 00 8.0
END DESCRIPTION:
XS GIS Cut Line= 3
      3921817.87     10012711.09      3921191.02     10011998.72
      3919158.92     10011135.89
#Sta/Elev= 30
  4051.1   54.38  4079.1   56.72  4121.8    52.8  4143.6   53.42  4150.3   51.88
  4327.7   46.76  4483.3    50.2  4582.9   45.95  4632.2   45.83  4717.1   53.29
  4738.5   51.17  4773.6   51.46  4915.9   46.48    5033    44.1  5055.1   46.51
  5206.2   42.96  5258.7   42.57  5262.7   42.57  5700.9   46.44  6030.2   45.19
    6183   47.23  6212.1   46.06  6264.8   47.93  6852.4   47.49  6915.5   49.13
  6969.8   47.91  7045.9   48.44    7158   53.36  7205.9   53.12  7207.7   53.52
#Mann= 7 ,-1 , 0
  4051.1     .11       0  4915.9     .06       0  5055.1     .17       0
  5206.2     .15       0  5258.7     .08       0  5262.7     .15       0
  7205.9     .17       0
Bank Sta=4915.9,5055.1
XS Rating Curve= 0 ,0
Exp/Cntr=0.3,0.1

Type RM Length L Ch R = 1 ,4550    ,78,78,78
BEGIN DESCRIPTION:
Mapping XS 5591a7bc
END DESCRIPTION:
XS GIS Cut Line= 4
      3921784.44     10012646.53      3921271.43     10011917.39
      3921138.62     10011914.78      3919201.93     10011127.39
#Sta/Elev= 30
  4040.1   54.03  4062.7    54.7  4092.3   52.02  4148.9   50.54  4193.3   52.62
  4220.4   49.07  4270.9   47.99    4378    50.4  4559.2   44.98    4824   49.74
  4925.1   46.38  5007.5   43.81  5055.2   46.44  5138.5   44.85  5257.6    42.5
  5257.9      42  5261.6    42.5    5713   48.27  6004.5   46.57  6036.8   44.87
  6179.4   45.57  6274.3   48.35  6471.1   48.94  6631.8   46.09  6733.4   46.85
  6762.9   45.37  6888.7   48.71  7025.2   49.18  7102.8   52.64  7155.1   53.11
#Mann= 6 ,-1 , 0
  4040.1     .11       0  4925.1     .06       0  5055.2     .17       0
  5138.5     .15       0  5257.6     .08       0  5261.6     .15       0
Bank Sta=4925.1,5055.2
XS Rating Curve= 0 ,0
Exp/Cntr=0.3,0.1

Type RM Length L Ch R = 1 ,4472    ,225,225,225
BEGIN DESCRIPTION:
Mapping XS 2a2738e5
END DESCRIPTION:
XS GIS Cut Line= 3
      3921792.26     10012641.34      3921320.91     10011875.72
      3919241.95     10011136.37
#Sta/Elev= 30
  3993.4   54.25  4026.7   55.12    4048   53.17  4053.9   51.29  4158.1   53.02
  4206.5   48.47  4337.9    49.8  4426.7    48.6  4505.9   44.68  4563.9   44.63
  4774.5   50.36  4826.6   49.59  4862.7   46.65  4892.5   44.63  4952.6   44.03
  4968.3   41.23  5267.2   43.65  5352.1    46.9  5532.5   47.21  5666.3   49.47
  5671.6   48.09  5902.4   47.62  6020.5   45.25  6385.3   49.66  6626.7   44.09
  6662.9   44.44  6806.5   44.96  6857.5   47.57  7037.3   50.34    7099   52.69
#Mann= 4 ,-1 , 0
  3993.4     .11       0  4862.7    .015       0  5352.1     .15       0
  6662.9     .17       0
Bank Sta=4862.7,5352.1
XS Rating Curve= 0 ,0
Exp/Cntr=0.3,0.1