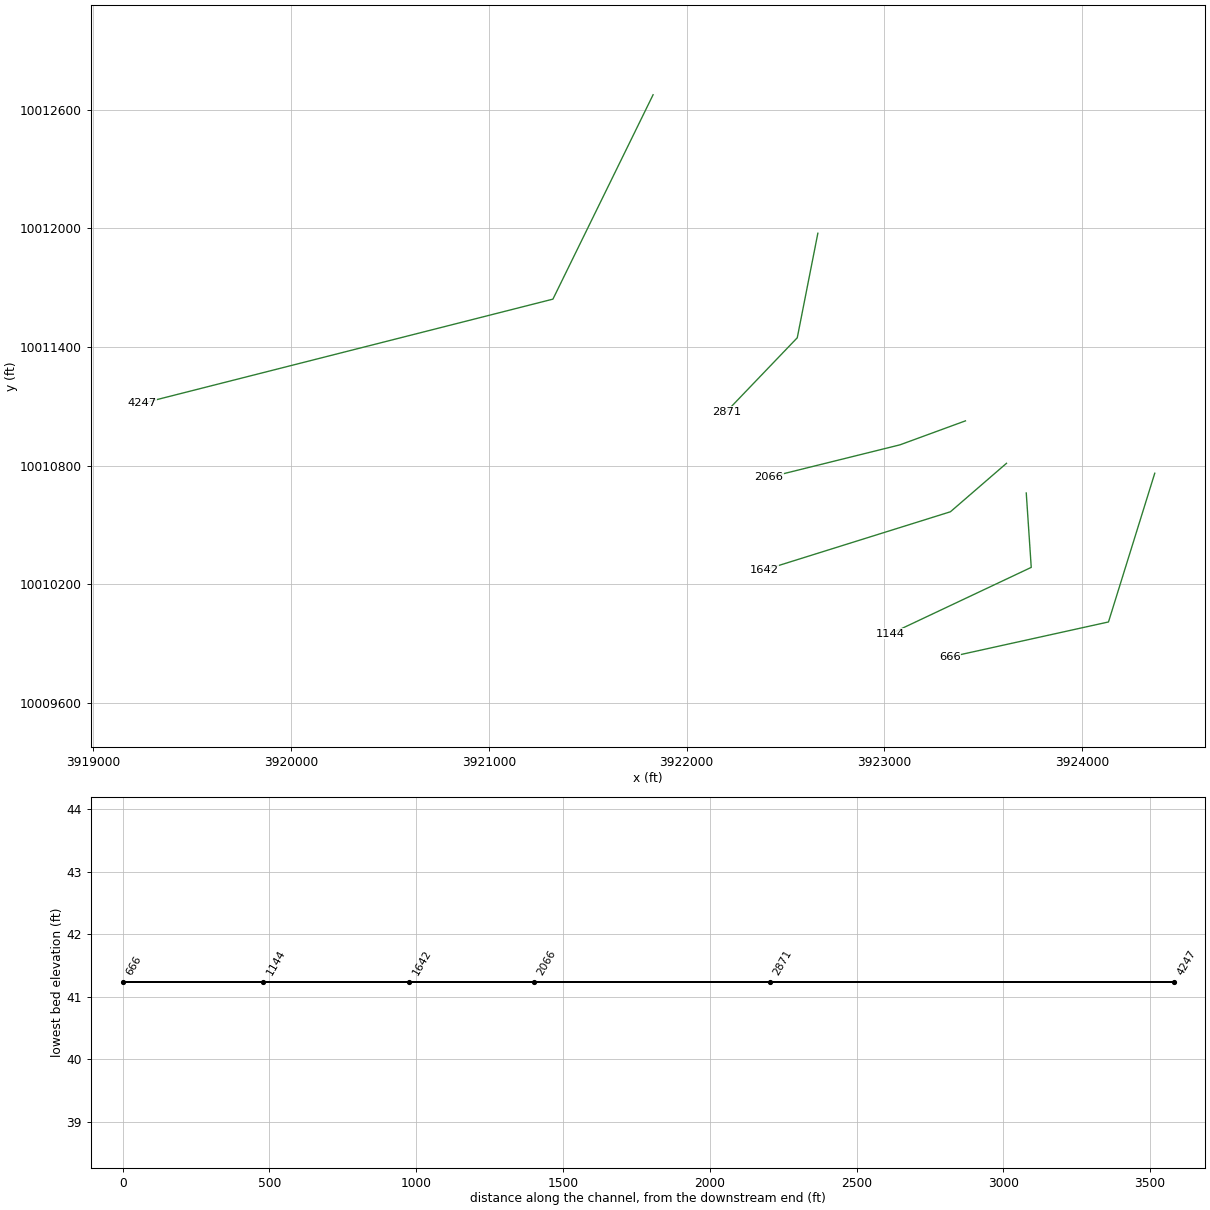
HEC-RAS study G103 36 00.prj: G103 36 00 Base Level Engineering

--- G103 36 00.g01 (geometry) --- (continued)

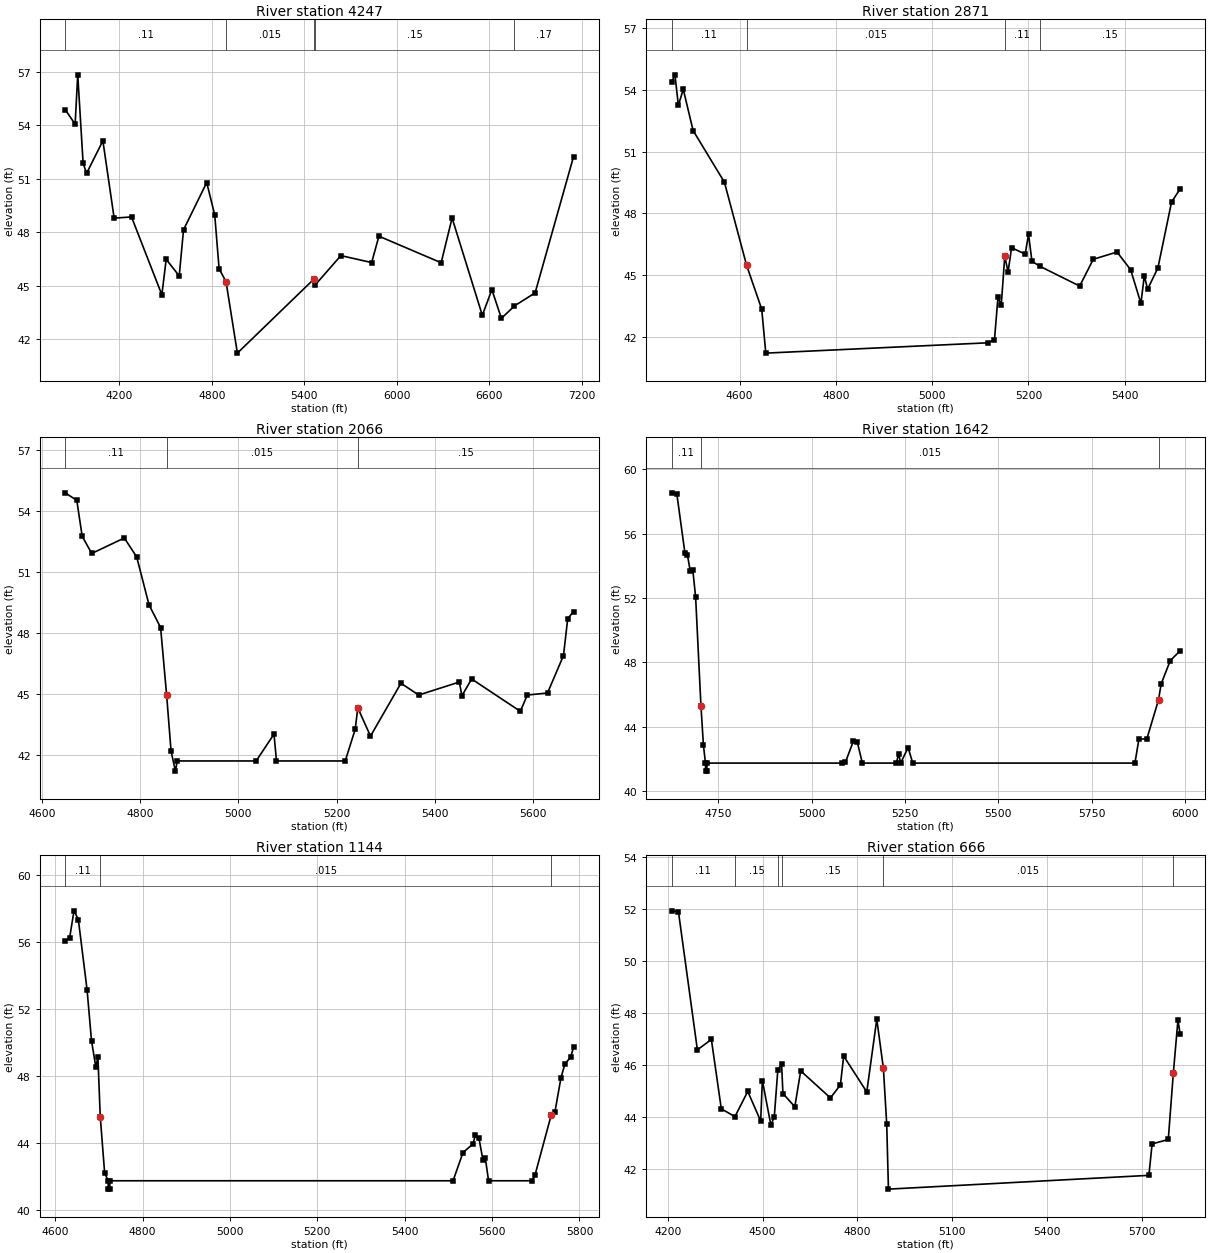
Type RM Length L Ch R = 1 ,4247    ,1376,1376,1376
BEGIN DESCRIPTION:
G 103 36 00 7.0
END DESCRIPTION:
XS GIS Cut Line= 3
      3921830.48     10012675.23      3921323.84     10011641.51
       3919244.5     10011114.03
#Sta/Elev= 30
  3848.8   54.89  3913.1   54.07  3930.1   56.84  3964.8    51.9  3987.1   51.31
  4093.1   53.14  4166.2    48.8  4278.7   48.87  4475.6    44.5  4503.6   46.49
  4588.1   45.56  4616.1   48.15  4766.6    50.8  4818.6   48.97  4846.7   45.96
  4891.7   45.24  4965.3   41.23  5460.1   45.37  5467.4   45.03  5636.4    46.7
  5836.1   46.31  5883.1   47.79  6286.7    46.3  6357.7   48.81  6553.7   43.35
  6615.6   44.79  6677.5   43.18  6762.3   43.88  6896.1   44.61  7145.2   52.25
#Mann= 5 ,-1 , 0
  3848.8     .11       0  4891.7    .015       0  5460.1     .12       0
  5467.4     .15       0  6762.3     .17       0
Bank Sta=4891.7,5460.1
XS Rating Curve= 0 ,0
Exp/Cntr=0.3,0.1

Type RM Length L Ch R = 1 ,2871    ,805,805,805
BEGIN DESCRIPTION:
G 103 36 00 5.0
END DESCRIPTION:
XS GIS Cut Line= 3
      3922663.79     10011974.69      3922559.63     10011446.03
      3922201.58     10011072.42
#Sta/Elev= 30
  4458.7   54.38  4465.5   54.72  4472.6   53.24  4482.8   54.02  4503.2   52.02
  4568.2   49.52  4614.5   45.48  4645.8   43.36  4654.3   41.23  5115.3   41.73
  5129.5   41.88  5136.7   43.93  5143.6   43.57  5150.8   45.92  5157.8   45.17
    5165   46.34  5193.3   46.03  5200.2   46.99  5207.4   45.68  5223.9   45.44
  5306.5   44.48  5334.8   45.78  5384.2   46.13  5412.5   45.27  5433.8   43.64
  5440.8   44.98  5447.7   44.33  5469.1   45.36  5497.4   48.55    5515   49.18
#Mann= 4 ,-1 , 0
  4458.7     .11       0  4614.5    .015       0  5150.8     .11       0
  5223.9     .15       0
Bank Sta=4614.5,5150.8
XS Rating Curve= 0 ,0
Exp/Cntr=0.3,0.1

Type RM Length L Ch R = 1 ,2066    ,424,424,424
BEGIN DESCRIPTION:
G 103 36 00 4.0
END DESCRIPTION:
XS GIS Cut Line= 3
      3923410.32     10011025.89      3923079.05     10010904.53
      3922416.39      10010740.3
#Sta/Elev= 30
  4647.2   54.91  4670.8   54.54  4681.8   52.77  4701.3   51.93  4767.6   52.69
  4792.8   51.76    4818    49.4  4841.5   48.29  4853.8   44.97  4862.8   42.22
  4871.7   41.23  4875.5   41.73  5036.2   41.73  5072.5   43.05  5077.6   41.73
  5217.6   41.73    5238   43.29  5243.2   44.34  5269.1   42.95  5331.1   45.55
  5367.3   44.97  5450.1   45.61  5455.3   44.93  5475.1   45.76  5574.3   44.17
  5588.5   44.97  5629.7   45.07  5662.2   46.91  5670.9   48.73  5682.7   49.07
#Mann= 3 , 0 , 0
  4647.2     .11       0  4853.8    .015       0  5243.2     .15       0
Bank Sta=4853.8,5243.2
XS Rating Curve= 0 ,0
Exp/Cntr=0.3,0.1

Type RM Length L Ch R = 1 ,1642    ,498,498,498
BEGIN DESCRIPTION:
G 103 36 00 3.0
END DESCRIPTION:
XS GIS Cut Line= 3
      3923617.83     10010811.06      3923334.25     10010565.99
      3922392.93     10010271.54
#Sta/Elev= 30
  4625.2   58.53  4638.9   58.48  4660.8   54.77  4667.4   54.66  4675.1   53.65
  4681.7   53.75  4689.3   52.06  4703.6   45.28  4710.2   42.84  4715.7   41.73
  4715.9   41.23  4719.4   41.23  4719.7   41.73  5080.1   41.73  5090.5   41.79
  5111.5   43.08    5122   43.06  5135.7   41.73  5226.7   41.73  5233.1    42.3
  5238.3   41.73  5258.2   42.69  5270.8   41.73  5865.6   41.73  5876.4   43.24
  5897.3   43.22  5928.8   45.66  5935.8   46.65  5960.2    48.1  5986.3    48.7
#Mann= 3 , 0 , 0
  4625.2     .11       0  4703.6    .015       0  5928.8     .15       0
Bank Sta=4703.6,5928.8
XS Rating Curve= 0 ,0
Exp/Cntr=0.3,0.1

Type RM Length L Ch R = 1 ,1144    ,478,478,478
BEGIN DESCRIPTION:
G 103 36 00 2.0
END DESCRIPTION:
XS GIS Cut Line= 3
      3923717.85     10010661.09      3923743.11     10010284.74
      3923031.94     10009949.09
#Sta/Elev= 30
  4622.8   56.09  4632.8   56.24  4642.9   57.88  4652.9   57.36  4672.9   53.14
    4683   50.11  4692.7   48.56  4697.7   49.11    4703   45.57    4713   42.22
    4721   41.73  4721.3   41.23  4724.8   41.23    4725   41.73  5510.6   41.73
  5533.4   43.42  5556.2   43.93  5561.7   44.46  5569.8   44.29  5578.9   42.99
  5584.5   43.08  5591.9   41.73  5691.4   41.73  5698.3   42.08  5735.6   45.69
  5743.9   45.86  5757.7    47.9  5766.7   48.72  5779.9   49.13  5786.4   49.72
#Mann= 3 , 0 , 0
  4622.8     .11       0    4703    .015       0  5735.6     .15       0
Bank Sta=4703,5735.6
XS Rating Curve= 0 ,0
Exp/Cntr=0.3,0.1

Type RM Length L Ch R = 1 ,666     ,0,0,0
BEGIN DESCRIPTION:
G 103 36 00 1.0
END DESCRIPTION:
XS GIS Cut Line= 3
      3924367.86     10010761.11      3924133.73      10010008.7
      3923331.63     10009831.71
#Sta/Elev= 30
    4212   51.94  4233.5    51.9  4293.4   46.59  4337.7   46.99  4369.1   44.32
  4412.3   44.02  4452.9   44.99  4493.8   43.85  4499.1   45.41  4526.2   43.69
  4536.9   44.02  4548.1   45.82  4560.1   46.03  4564.2   44.91  4601.9    44.4
  4620.5   45.78  4714.7   44.74  4746.2   45.24  4756.6   46.35  4829.7   44.97
  4861.4   47.77  4882.3   45.88  4892.8   43.74  4898.3   41.23  5722.9   41.76
  5733.1   42.97  5784.3   43.14  5800.4   45.71    5815   47.75  5821.4   47.21
#Mann= 6 ,-1 , 0
    4212     .11       0  4412.3     .15       0  4548.1     .17       0
  4560.1     .15       0  4882.3    .015       0  5800.4     .15       0
Bank Sta=4882.3,5800.4
XS Rating Curve= 0 ,0
Exp/Cntr=0.3,0.1

Chan Stop Cuts=-1
Use User Specified Reach Order=0
Composite Channel Slope=5