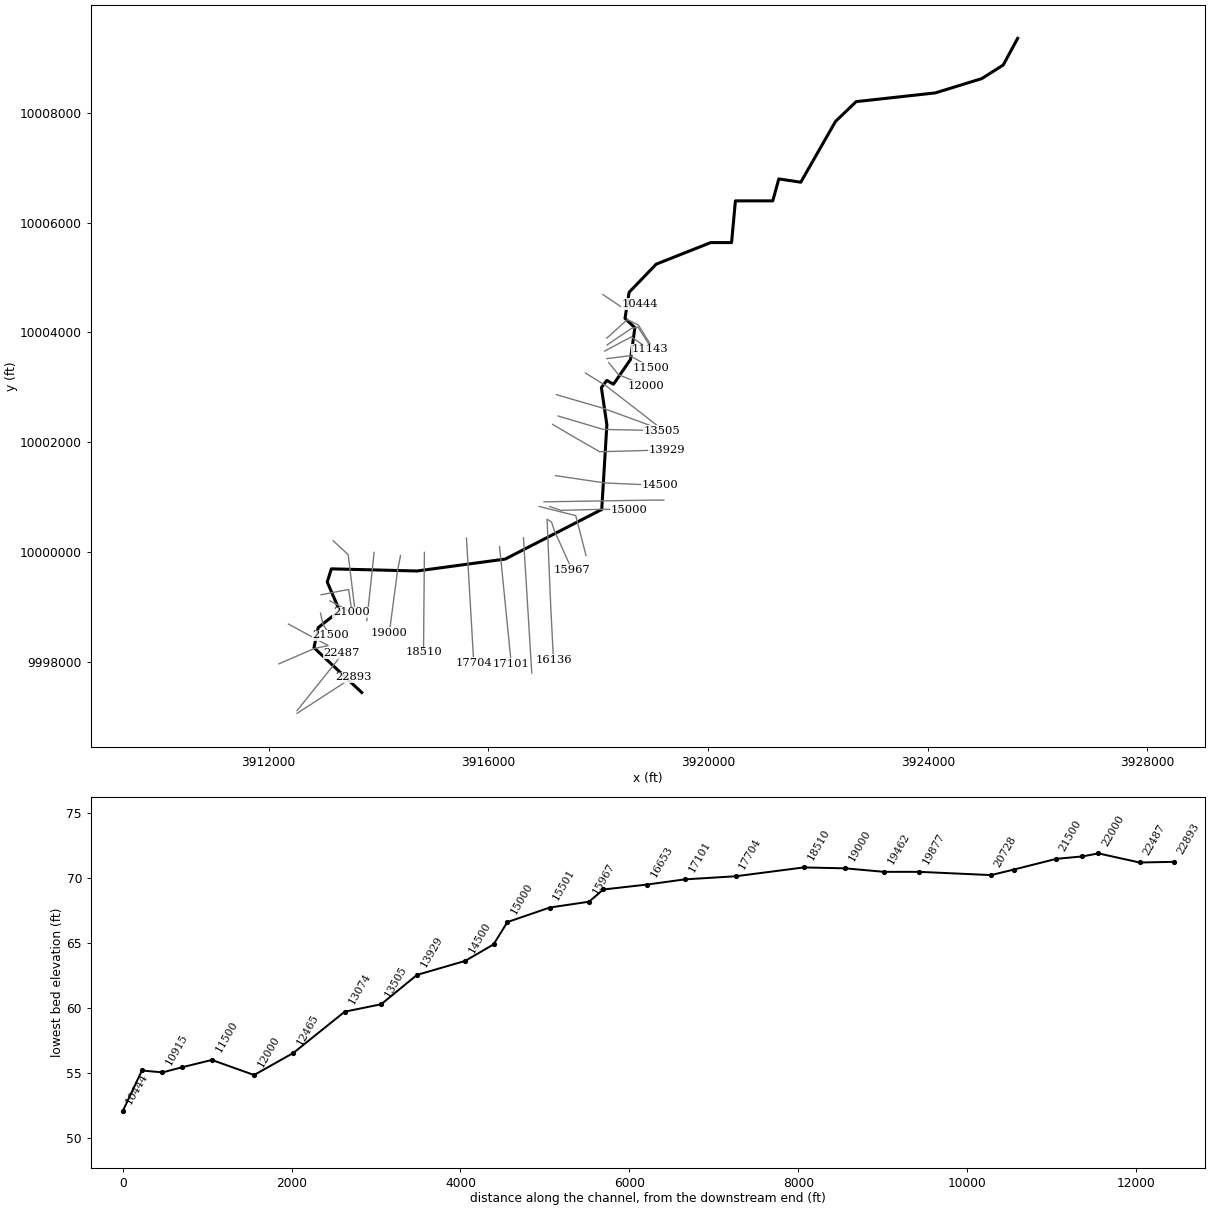
--- G103 37 00.prj (project) ---

Proj Title=G103 37 00 Base Level Engineering
Current Plan=p01
Default Exp/Contr=0.3,0.1
English Units
Geom File=g01
Flow File=f01
Flow File=f02
Plan File=p01
Y Axis Title=Elevation
X Axis Title(PF)=Main Channel Distance
X Axis Title(XS)=Station
BEGIN DESCRIPTION:
G103 37 00
END DESCRIPTION:
DSS Export Rating Curves= 0
DSS Export Rating Curve Sorted= 0
DSS Export Volume Flow Curves= 0
DXF OffsetX= 0
DXF OffsetY= 0
DXF ScaleX= 1
DXF ScaleY= 10

--- G103 37 00.p01 (plan) ---

Plan Title=Multiple Run
Short Identifier=Multiple
Geom File=g01
Flow File=f01
Subcritical Flow
K Sum by GR= 0
Std Step Tol= 0.01
Critical Tol= 0.01
Num of Std Step Trials= 20
Max Error Tol= 0.3
Flow Tol Ratio= 0.001
Split Flow NTrial= 30
Split Flow Tol= 0.02
Split Flow Ratio= 0.02
Log Output Level= 0
Friction Slope Method= 1
Unsteady Friction Slope Method= 2
Unsteady Bridges Friction Slope Method= 1
Parabolic Critical Depth
Global Vel Dist=  1 , 1 , 1
Global Log Level= 0
CheckData=True
Encroach Param= -1, 0, 0, 0
BEGIN DESCRIPTION:
Multiple Run
END DESCRIPTION:

--- G103 37 00.f01 (steady flow) ---

Flow Title=Multiple
Program Version=4.10
Number of Profiles= 7
Profile Names=10-year,25-year,50-year,1pct_min,100-year,1pct_plu,500-year
River Rch & RM=G103 37 00,Reach-1         ,22893
     185     221     275     112     339    1024     538
River Rch & RM=G103 37 00,Reach-1         ,15501
     460     572     730     305     921    2781    1513
River Rch & RM=G103 37 00,Reach-1         ,7409
    1160    1538    2047     891    2691    8127    4811
Boundary for River Rch & Prof#=G103 37 00,Reach-1         , 1
Up Type= 0
Dn Type= 3
Dn Slope=0.0005
Boundary for River Rch & Prof#=G103 37 00,Reach-1         , 2
Up Type= 0
Dn Type= 3
Dn Slope=0.0005
Boundary for River Rch & Prof#=G103 37 00,Reach-1         , 3
Up Type= 0
Dn Type= 3
Dn Slope=0.0005
Boundary for River Rch & Prof#=G103 37 00,Reach-1         , 4
Up Type= 0
Dn Type= 3
Dn Slope=0.0005
Boundary for River Rch & Prof#=G103 37 00,Reach-1         , 5
Up Type= 0
Dn Type= 3
Dn Slope=0.0005
Boundary for River Rch & Prof#=G103 37 00,Reach-1         , 6
Up Type= 0
Dn Type= 3
Dn Slope=0.0005
Boundary for River Rch & Prof#=G103 37 00,Reach-1         , 7
Up Type= 0
Dn Type= 3
Dn Slope=0.0005
DSS Import GetInterval= 0
DSS Import GetPeak= 0
DSS Import FillOption= 0

--- G103 37 00.f02 (steady flow) ---

Flow Title=Orig_BLE_Flows
Program Version=4.10
Number of Profiles= 7
Profile Names=10-year,25-year,50-year,1pct_min,100-year,1pct_plu,500-year
River Rch & RM=G103 37 00,Reach-1         ,22893
     185     217     239      87     261     789     313
River Rch & RM=G103 37 00,Reach-1         ,15502
     555     691     792     297     897    2709    1147
River Rch & RM=G103 37 00,Reach-1         ,7409
    1160    1508    1780     686    2070    6253    2797
Boundary for River Rch & Prof#=G103 37 00,Reach-1         , 1
Up Type= 0
Dn Type= 3
Dn Slope=0.0005
Boundary for River Rch & Prof#=G103 37 00,Reach-1         , 2
Up Type= 0
Dn Type= 3
Dn Slope=0.0005
Boundary for River Rch & Prof#=G103 37 00,Reach-1         , 3
Up Type= 0
Dn Type= 3
Dn Slope=0.0005
Boundary for River Rch & Prof#=G103 37 00,Reach-1         , 4
Up Type= 0
Dn Type= 3
Dn Slope=0.0005
Boundary for River Rch & Prof#=G103 37 00,Reach-1         , 5
Up Type= 0
Dn Type= 3
Dn Slope=0.0005
Boundary for River Rch & Prof#=G103 37 00,Reach-1         , 6
Up Type= 0
Dn Type= 3
Dn Slope=0.0005
Boundary for River Rch & Prof#=G103 37 00,Reach-1         , 7
Up Type= 0
Dn Type= 3
Dn Slope=0.0005
DSS Import GetInterval= 0
DSS Import GetPeak= 0
DSS Import FillOption= 0

--- G103 37 00.g01 (geometry) ---

Geom Title=Existing Conditions
Program Version=4.10

River Reach=G103 37 00      ,Reach-1
Reach XY= 30
      3913695.26      9997441.67      3912826.32      9998257.41
      3912902.14      9998622.16      3913292.76      9998932.06
       3913067.5      9999452.64      3913141.98      9999693.82
      3914702.52      9999654.81      3916308.39      9999872.16
      3918064.79     10000775.56      3918158.23     10002316.84
      3918058.23     10002996.84      3918158.23     10003126.84
      3918278.23     10003056.84      3918588.23     10003506.84
      3918668.23     10004086.84      3918488.23     10004256.84
      3918563.73     10004732.36      3919055.79     10005243.58
      3920048.23     10005636.84      3920428.23     10005636.84
      3920498.23     10006396.84      3921178.23     10006396.84
      3921288.23     10006796.84      3921688.23     10006736.84
      3922321.31     10007845.24      3922696.31     10008204.61
      3924136.42     10008363.47      3924982.77     10008623.88
      3925373.39     10008871.28      3925636.44     10009357.71

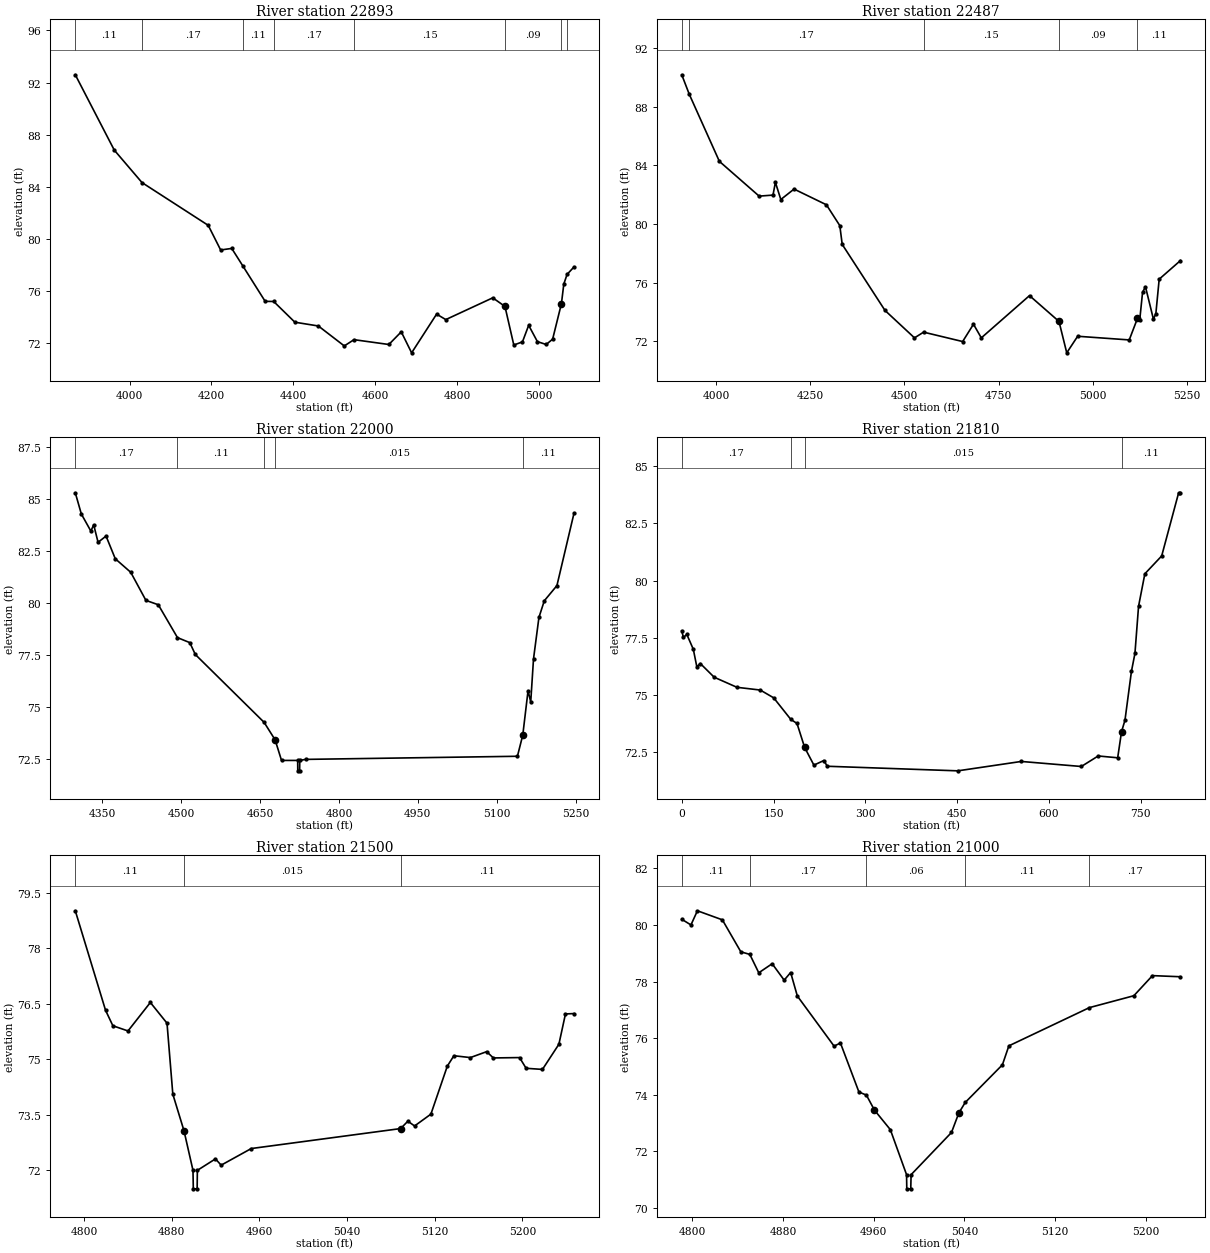
Type RM Length L Ch R = 1 ,22893   ,406,406,406
BEGIN DESCRIPTION:
G103-37-00 46.0
END DESCRIPTION:
XS GIS Cut Line= 3
      3912517.89      9997061.09      3913459.82      9997672.47
       3913541.7      9997720.15
#Sta/Elev= 30
  3867.5    92.6  3962.7   86.82  4030.4   84.33  4192.1   81.05  4222.4   79.16
  4249.5   79.28  4277.1   77.91  4331.1   75.22  4351.9   75.21  4403.6   73.62
    4461   73.33  4524.3    71.8    4548   72.28  4633.1   71.91  4663.4   72.88
  4688.7   71.27  4749.7   74.24  4772.1   73.82  4886.8   75.49  4916.6   74.83
  4938.2   71.87  4959.3   72.11  4974.5   73.38  4995.8   72.13  5017.3   71.91
    5033   72.32  5054.5   75.05  5060.3   76.55  5068.3   77.29  5085.2   77.86
#Mann= 8 ,-1 , 0
  3867.5     .11       0  4030.4     .17       0  4277.1     .11       0
  4351.9     .17       0    4548     .15       0  4916.6     .09       0
  5054.5     .15       0  5068.3     .11       0
Bank Sta=4916.6,5054.5
XS Rating Curve= 0 ,0
Exp/Cntr=0.3,0.1

Type RM Length L Ch R = 1 ,22487   ,487,487,487
BEGIN DESCRIPTION:
G103-37-00 45.0
END DESCRIPTION:
XS GIS Cut Line= 3
      3912517.84      9997111.06      3913242.81      9998015.35
       3913331.4      9998156.43
#Sta/Elev= 30
    3908   90.17    3928   88.84    4008   84.27  4113.7    81.9  4150.5   81.97
  4156.9   82.84  4171.3   81.67  4206.5   82.38  4292.5   81.31  4328.1   79.89
  4334.5   78.61  4448.2   74.11  4526.6   72.24  4550.8   72.63  4654.6   71.99
  4683.4   73.17  4704.2   72.24  4832.3   75.12  4910.7   73.36  4931.3   71.22
  4960.3   72.35  5097.4    72.1  5119.3   73.57  5125.2   73.44  5132.8   75.34
  5140.5   75.73  5161.7   73.51  5168.2    73.9    5177   76.24  5233.6   77.51
#Mann= 5 ,-1 , 0
    3908     .11       0    3928     .17       0  4550.8     .15       0
  4910.7     .09       0  5119.3     .11       0
Bank Sta=4910.7,5119.3
XS Rating Curve= 0 ,0
Exp/Cntr=0.3,0.1

Type RM Length L Ch R = 1 ,22000   ,190,190,190
BEGIN DESCRIPTION:
G103-37-00 44.0
END DESCRIPTION:
XS GIS Cut Line= 3
      3912188.13      9997963.27      3912831.53       9998242.3
      3913073.16      9998293.05
#Sta/Elev= 30
  4298.7   85.28  4310.2   84.26  4328.3   83.44  4333.7   83.74    4342    82.9
  4357.2    83.2  4374.7   82.11  4404.1   81.46    4433   80.11  4456.5    79.9
    4493   78.32  4516.4   78.08  4526.9   77.51  4657.7   74.25  4678.6   73.41
  4690.8   72.42  4721.5   72.42  4721.7   71.92  4725.2   71.92  4725.5   72.42
  4736.4   72.47  5139.3   72.62  5149.5   73.64  5159.5   75.77  5164.6   75.23
  5169.9    77.3  5180.2   79.29  5190.4   80.09  5214.4   80.82  5246.9    84.3
#Mann= 5 ,-1 , 0
  4298.7     .17       0    4493     .11       0  4657.7     .17       0
  4678.6    .015       0  5149.5     .11       0
Bank Sta=4678.6,5149.5
XS Rating Curve= 0 ,0
Exp/Cntr=0.3,0.1

Type RM Length L Ch R = 1 ,21810   ,310,310,310
BEGIN DESCRIPTION:
G103-37-00 44.0
END DESCRIPTION:
XS GIS Cut Line= 2
      3912361.18       9998687.7      3913078.18      9998300.56
#Sta/Elev= 30
       0   77.81     2.7   77.52     8.3   77.65    18.9      77    24.6   76.24
    30.3   76.38      53   75.78    90.2   75.34   128.3   75.22   150.2   74.88
   178.1   73.94   188.3   73.76   200.8   72.71   215.9   71.94   232.1   72.14
   237.8   71.89     451   71.69   554.7    72.1   652.8   71.88   680.4   72.34
   712.2   72.26   718.5    73.4   724.1    73.9   734.7   76.04   740.4   76.82
   746.3   78.88   756.6    80.3   784.1   81.08   811.8   83.84   814.8   83.84
#Mann= 4 ,-1 , 0
       0     .17       0   178.1     .11       0   200.8    .015       0
   718.5     .11       0
Bank Sta=200.8,718.5
XS Rating Curve= 0 ,0
Exp/Cntr=0.3,0.1

Type RM Length L Ch R = 1 ,21500   ,500,500,500
BEGIN DESCRIPTION:
G103-37-00 43.0
END DESCRIPTION:
XS GIS Cut Line= 3
      3912945.34      9998888.06      3912988.98      9998684.69
      3913127.47      9998480.04
#Sta/Elev= 30
    4792   79.02  4819.6   76.33  4826.3   75.91  4840.1   75.77  4860.5   76.54
  4875.7   75.98    4881   74.06  4891.2   73.07  4899.4      72  4899.7    71.5
  4903.2    71.5  4903.4      72  4919.9   72.31  4925.1   72.14  4952.6   72.59
  5088.9   73.13  5095.5   73.33  5101.6    73.2  5116.5   73.52  5131.5   74.82
  5137.5    75.1  5152.5   75.05  5167.4   75.21  5173.5   75.04  5197.4   75.05
  5203.4   74.76  5218.3   74.73  5233.3   75.41  5239.3   76.23  5247.1   76.24
#Mann= 3 , 0 , 0
    4792     .11       0  4891.2    .015       0  5088.9     .11       0
Bank Sta=4891.2,5088.9
XS Rating Curve= 0 ,0
Exp/Cntr=0.3,0.1

Type RM Length L Ch R = 1 ,21000   ,272,272,272
BEGIN DESCRIPTION:
G103-37-00 42.0
END DESCRIPTION:
XS GIS Cut Line= 3
      3913117.88      9999111.06      3913302.54      9999012.75
      3913506.63       9998905.6
#Sta/Elev= 30
  4790.8    80.2  4798.9      80  4804.6    80.5  4826.6   80.18  4842.9   79.05
  4850.8   78.96  4858.7   78.31  4870.5   78.63  4881.1   78.05  4886.8   78.32
  4892.7   77.49  4925.1   75.72  4930.7   75.83    4947    74.1  4953.6   73.99
  4960.7   73.46  4974.7   72.77    4989   71.18  4989.2   70.68  4992.7   70.68
    4993   71.18  5028.6   72.67  5035.1   73.36  5040.7   73.73  5073.5   75.06
  5079.2   75.73  5150.2   77.08  5189.4    77.5  5205.8   78.21  5230.5   78.17
#Mann= 5 ,-1 , 0
  4790.8     .11       0  4850.8     .17       0  4953.6     .06       0
  5040.7     .11       0  5150.2     .17       0
Bank Sta=4960.7,5035.1
XS Rating Curve= 0 ,0
Exp/Cntr=0.3,0.1

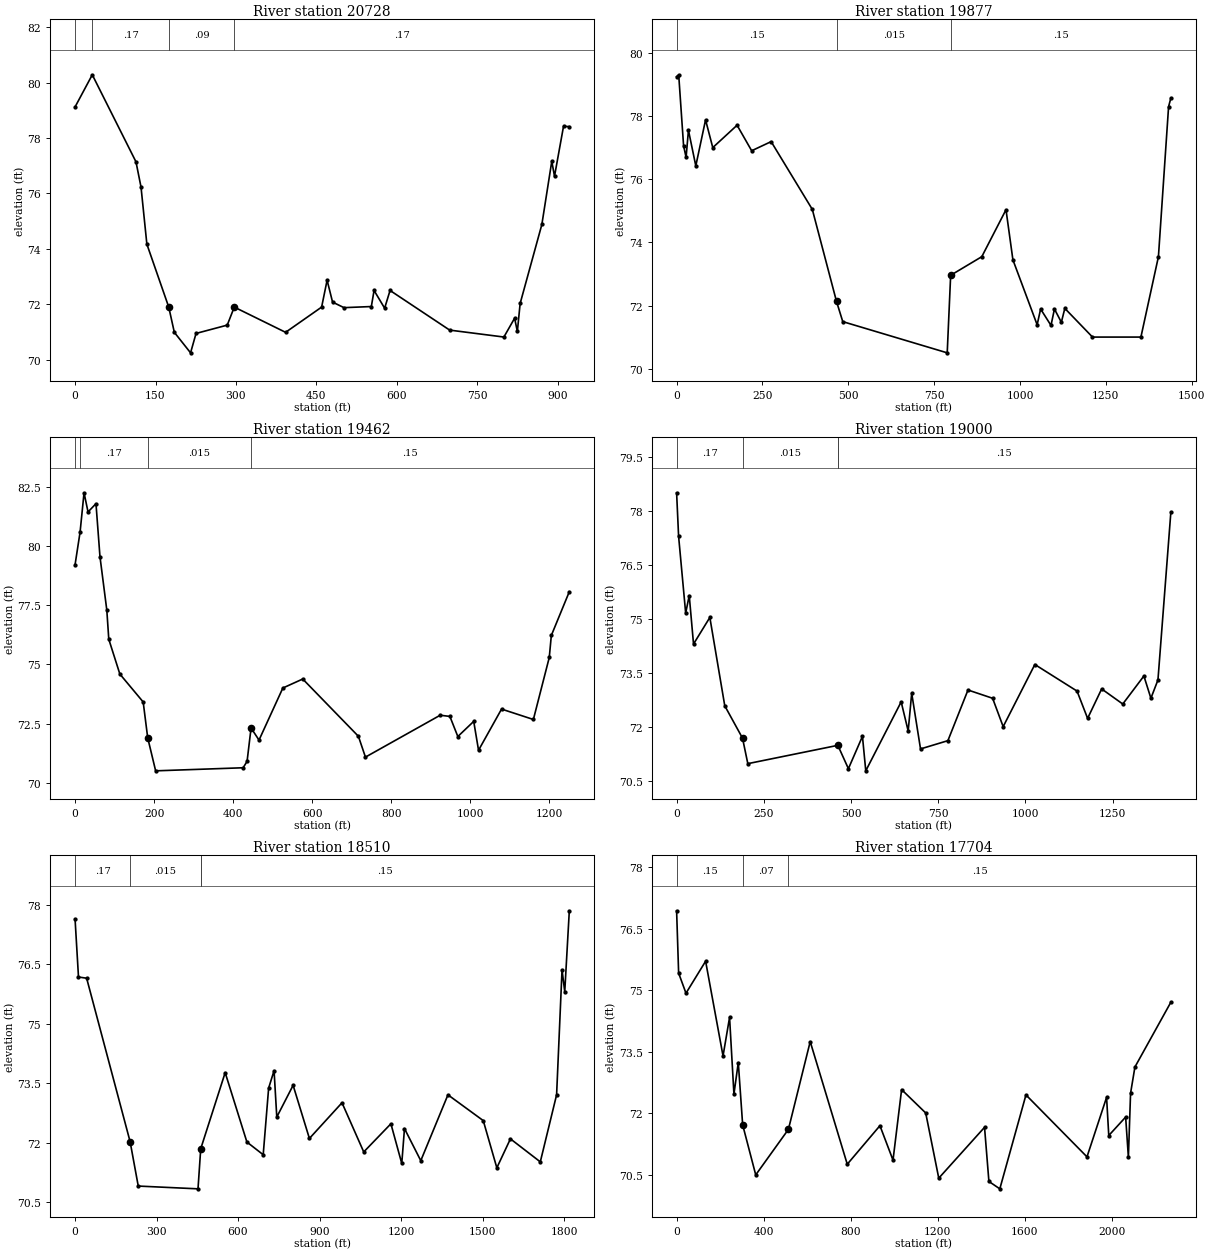
Type RM Length L Ch R = 1 ,20728   ,851,851,851
BEGIN DESCRIPTION:
Mapping XS 08834ba2
END DESCRIPTION:
XS GIS Cut Line= 3
      3912956.35      9999221.95       3913456.4      9999318.34
      3913517.17      9998910.36
#Sta/Elev= 30
       0   79.12    32.1   80.28   113.6   77.14     123   76.23   133.9   74.17
   174.7    71.9   185.1   70.99   215.4   70.25   225.6   70.95   283.8   71.25
   296.9    71.9   392.6   70.99   459.8    71.9     470   72.87   480.2   72.08
   501.5   71.88   552.5   71.92   557.6    72.5   577.3   71.86   587.4    72.5
   698.6   71.07   799.7   70.82   819.7    71.5   824.8   71.02     830   72.03
   870.5   74.88     889   77.16   894.1   76.62   910.9   78.42   921.7   78.41
#Mann= 4 ,-1 , 0
       0     .11       0    32.1     .17       0   174.7     .09       0
   296.9     .17       0
Bank Sta=174.7,296.9
XS Rating Curve= 0 ,0
Exp/Cntr=0.3,0.1

Type RM Length L Ch R = 1 ,19877   ,415,415,415
BEGIN DESCRIPTION:
Mapping XS e3348aba
END DESCRIPTION:
XS GIS Cut Line= 3
      3913175.15     10000207.23      3913449.46      9999950.29
      3913577.93        9998893.
#Sta/Elev= 30
       0   79.26     6.1   79.32    20.3   77.07    27.6    76.7    34.5   77.56
    55.9   76.43    84.3   77.89   105.3   77.01   176.1   77.72   218.6   76.91
   275.3    77.2   395.2   75.05   465.7   72.13   483.9   71.49   788.1    70.5
   798.1   72.96   888.8   73.55   959.3   75.04   979.4   73.45    1050   71.39
  1060.1   71.89  1090.3   71.37  1100.4   71.89  1120.5   71.47  1130.6   71.91
  1211.2      71  1352.2      71  1403.2   73.55  1432.8   78.31  1439.4   78.58
#Mann= 3 , 0 , 0
       0     .15       0   465.7    .015       0   798.1     .15       0
Bank Sta=465.7,798.1
XS Rating Curve= 0 ,0
Exp/Cntr=0.3,0.1

Type RM Length L Ch R = 1 ,19462   ,462,462,462
BEGIN DESCRIPTION:
G103-37-00 39.0
END DESCRIPTION:
XS GIS Cut Line= 2
      3913921.68      9999993.69        3913788.      9998750.63
#Sta/Elev= 30
       0   79.21    12.7   80.59    22.7   82.25    32.8   81.44    52.9   81.79
      63   79.55    80.3   77.29    85.3   76.06   113.3   74.59   172.3   73.41
   183.7    71.9   203.8    70.5   425.1   70.63   435.1    70.9   445.2   72.31
   465.3    71.8   525.6      74   575.9   74.38   716.7   71.96   734.5   71.08
   923.6   72.85   948.1    72.8   968.2   71.95  1008.4   72.59  1020.6   71.37
  1078.8   73.11  1159.3   72.67  1199.5   75.29  1204.7   76.22  1250.2   78.07
#Mann= 4 ,-1 , 0
       0     .11       0    12.7     .17       0   183.7    .015       0
   445.2     .15       0
Bank Sta=183.7,445.2
XS Rating Curve= 0 ,0
Exp/Cntr=0.3,0.1

Type RM Length L Ch R = 1 ,19000   ,490,490,490
BEGIN DESCRIPTION:
G103-37-00 38.0
END DESCRIPTION:
XS GIS Cut Line= 3
      3914401.45      9999936.64      3914346.28       9999650.2
      3914198.59      9998532.75
#Sta/Elev= 30
       0   78.51     5.7    77.3      26   75.16    36.2   75.65    48.5    74.3
    95.3   75.04   138.1   72.58     189   71.68   204.2   70.97   462.3   71.48
   492.6   70.83   532.9   71.73   542.4   70.77   643.9   72.69     664   71.88
   674.1   72.93   699.4   71.38   777.9   71.61   835.5   73.02   906.1   72.79
   936.4      72  1027.2   73.73  1148.2   72.99  1178.5   72.23  1218.8   73.05
  1279.3   72.63  1339.9   73.41    1360   72.79  1380.2    73.3  1417.2   77.97
#Mann= 4 ,-1 , 0
       0     .17       0     189    .015       0   462.3     .15       0
   462.3     .15       0
Bank Sta=189,462.3
XS Rating Curve= 0 ,0
Exp/Cntr=0.3,0.1

Type RM Length L Ch R = 1 ,18510   ,806,806,806
BEGIN DESCRIPTION:
Mapping XS 830e8a3e
END DESCRIPTION:
XS GIS Cut Line= 2
      3914836.61      9999993.69      3914820.12      9998172.51
#Sta/Elev= 30
       0   77.64    12.6   76.18    42.6   76.15   202.6   72.03   232.6   70.91
   452.6   70.84   462.6   71.85   552.6   73.77   632.6   72.02   692.6    71.7
   712.6   73.38   732.6   73.82   742.6   72.65   802.7   73.45   862.7   72.11
   982.7   73.01  1062.7   71.77  1162.7   72.48  1202.7   71.48  1212.7   72.36
  1272.7   71.55  1372.7   73.21  1502.7   72.56  1552.7   71.37  1602.7    72.1
  1712.7   71.52  1772.7   73.21  1792.7   76.36  1802.7   75.81  1819.5   77.85
#Mann= 4 ,-1 , 0
       0     .17       0   202.6    .015       0   462.6     .12       0
   462.6     .15       0
Bank Sta=202.6,462.6
XS Rating Curve= 0 ,0
Exp/Cntr=0.3,0.1

Type RM Length L Ch R = 1 ,17704   ,603,603,603
BEGIN DESCRIPTION:
Mapping XS 6eb5319a
END DESCRIPTION:
XS GIS Cut Line= 2
      3915602.24     10000254.11      3915734.83      9997986.13
#Sta/Elev= 30
       0   76.94     9.3   75.42    43.1   74.93   133.3   75.71   213.4    73.4
   243.4   74.34   263.5   72.47   283.5   73.24   303.6   71.72   363.7    70.5
   513.9   71.61   614.1   73.75   784.4   70.76   934.6    71.7   994.7   70.86
  1034.2   72.58    1145   72.01    1205   70.42  1415.4   71.66  1435.5   70.34
  1485.6   70.16  1605.8   72.45  1886.3   70.94  1976.4   72.39  1986.4   71.46
    2064   71.91  2076.6   70.93  2086.6   72.49  2106.6   73.13  2271.8   74.71
#Mann= 3 , 0 , 0
       0     .15       0   303.6     .07       0   513.9     .15       0
Bank Sta=303.6,513.9
XS Rating Curve= 0 ,0
Exp/Cntr=0.3,0.1

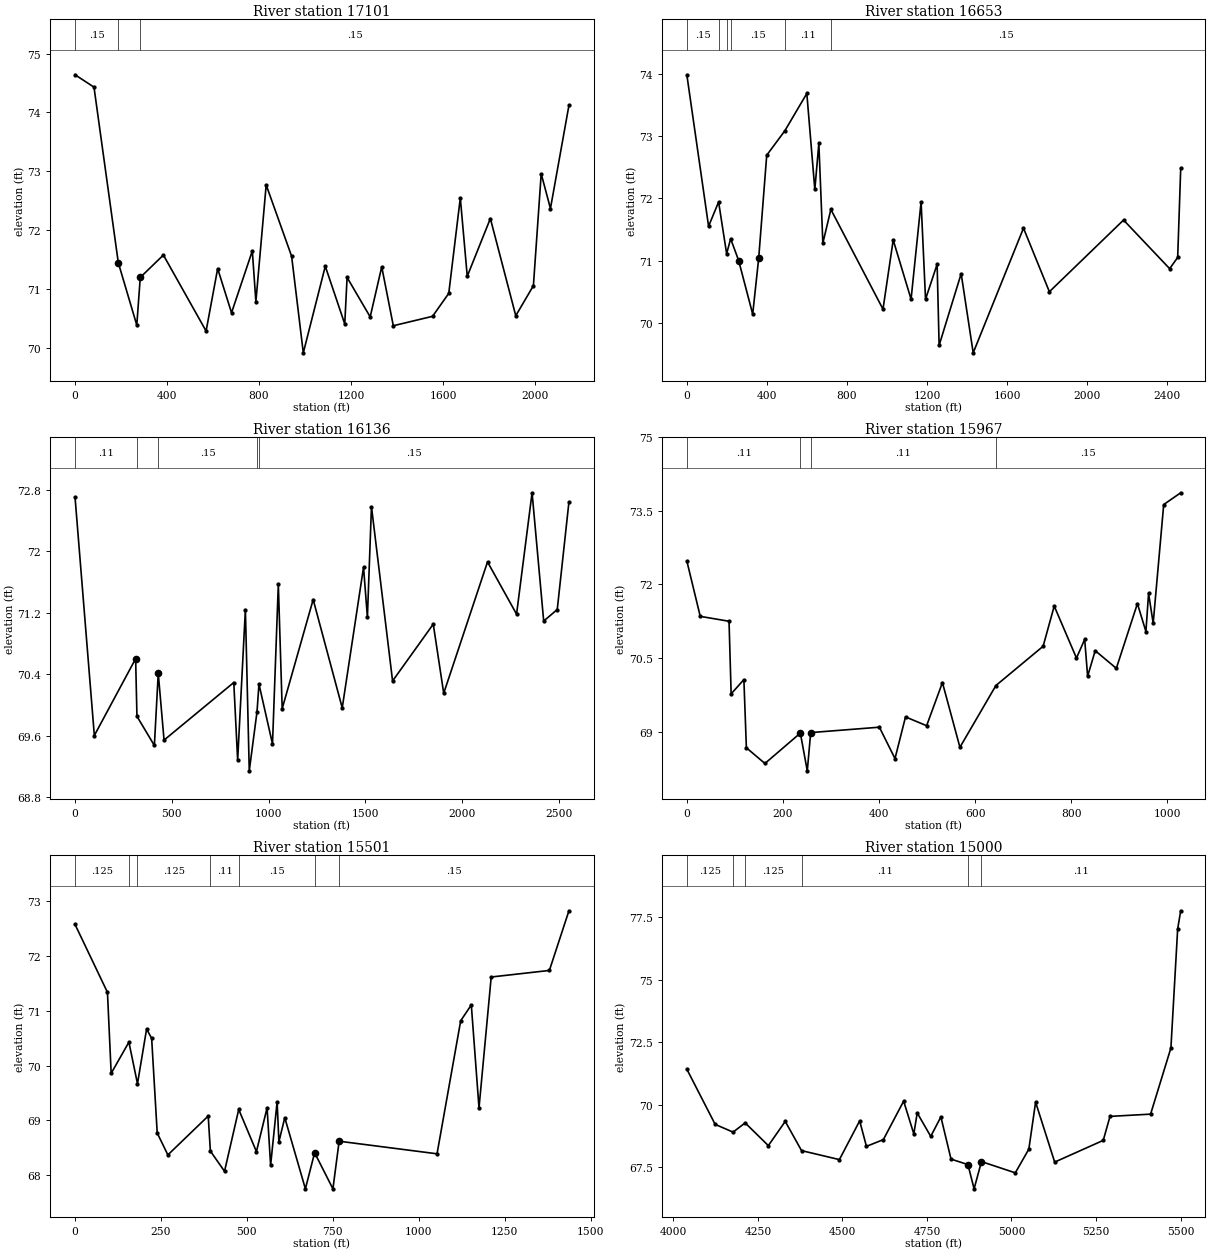
Type RM Length L Ch R = 1 ,17101   ,448,448,448
BEGIN DESCRIPTION:
Mapping XS 5b3e15a0
END DESCRIPTION:
XS GIS Cut Line= 2
      3916204.67      10000098.2      3916418.06      9997961.05
#Sta/Elev= 30
       0   74.64    82.4   74.43   188.1   71.45   268.5   70.39   283.6    71.2
   384.2   71.58   569.9   70.29   620.2   71.35   680.5    70.6   770.9   71.65
   786.4   70.79   831.2   72.77   941.8   71.56   992.6   69.92  1088.2   71.39
  1172.9   70.41    1183    71.2  1283.5   70.53  1333.7   71.38    1384   70.38
  1554.8   70.54  1625.2   70.93  1675.4   72.55  1705.6   71.22  1806.1    72.2
  1916.6   70.55  1993.3   71.06  2027.2   72.96  2067.4   72.37  2147.8   74.12
#Mann= 3 , 0 , 0
       0     .15       0   188.1     .07       0   283.6     .15       0
Bank Sta=188.1,283.6
XS Rating Curve= 0 ,0
Exp/Cntr=0.3,0.1

Type RM Length L Ch R = 1 ,16653   ,517,517,517
BEGIN DESCRIPTION:
Mapping XS 383cd33f
END DESCRIPTION:
XS GIS Cut Line= 2
      3916639.75     10000259.61      3916791.38      9997795.71
#Sta/Elev= 30
       0   73.98   108.7   71.55   158.8   71.94   198.9   71.11     219   71.35
     259      71   329.2   70.14   359.2   71.04   399.3   72.69   489.5   73.08
   599.7   73.68   639.7   72.14   659.8   72.88   679.8   71.28   719.9   71.82
   980.4   70.22  1031.4   71.33  1120.7   70.38  1170.8   71.94    1193   70.38
  1250.9   70.94  1260.9   69.64  1371.1   70.79  1431.2   69.52  1682.6   71.52
    1812    70.5  2182.7   71.65  2413.1   70.87  2453.2   71.05  2468.4   72.48
#Mann= 6 ,-1 , 0
       0     .15       0   158.8     .07       0   198.9     .11       0
     219     .15       0   489.5     .11       0   719.9     .15       0
Bank Sta=259,359.2
XS Rating Curve= 0 ,0
Exp/Cntr=0.3,0.1

Type RM Length L Ch R = 1 ,16136   ,169,169,169
BEGIN DESCRIPTION:
Mapping XS 45e5ce07
END DESCRIPTION:
XS GIS Cut Line= 3
       3917069.8     10000590.72      3917133.86      9999064.09
      3917185.56      9998040.78
#Sta/Elev= 30
       0    72.7    99.7    69.6   313.1    70.6   319.9   69.85     410   69.47
     430   70.41     460   69.54   820.4   70.29   840.4   69.28   880.4   71.24
   900.4   69.14   940.5   69.91   950.5   70.27  1020.5   69.49  1050.6   71.57
  1070.6   69.95  1230.7   71.37  1380.9   69.96    1491   71.79    1511   71.14
    1532   72.58  1641.1   70.31  1851.4   71.05  1905.4   70.15  2131.8   71.86
  2281.9   71.18  2362.1   72.76  2422.1   71.09  2492.2   71.24  2552.6   72.64
#Mann= 5 ,-1 , 0
       0     .11       0   319.9     .06       0     430     .15       0
   940.5     .09       0   950.5     .15       0
Bank Sta=313.1,430
XS Rating Curve= 0 ,0
Exp/Cntr=0.3,0.1

Type RM Length L Ch R = 1 ,15967   ,466,466,466
BEGIN DESCRIPTION:
G103-37-00 32.0
END DESCRIPTION:
XS GIS Cut Line= 4
      3917080.93     10000592.59      3917151.24     10000544.41
      3917202.02     10000390.76      3917522.02      9999678.78
#Sta/Elev= 30
       0   72.48    27.9   71.35    87.8   71.25    92.2   69.77   118.7   70.06
   123.9   68.67   162.5   68.35   236.2   68.97   250.6    68.2   257.7   68.98
   400.6   69.09   433.1   68.45     455    69.3   498.9   69.12   531.8      70
   568.2   68.68   643.1   69.94   741.3   70.74   764.4   71.56   810.7    70.5
   827.8   70.88   833.9   70.13   849.7   70.65   893.6   70.29   937.5   71.61
   955.2   71.04   960.7   71.82   970.3   71.21   992.2   73.63  1027.6   73.87
#Mann= 4 ,-1 , 0
       0     .11       0   236.2     .07       0   257.7     .11       0
   643.1     .15       0
Bank Sta=236.2,257.7
XS Rating Curve= 0 ,0
Exp/Cntr=0.3,0.1

Type RM Length L Ch R = 1 ,15501   ,501,501,501
BEGIN DESCRIPTION:
G103-37-00 31.0
END DESCRIPTION:
XS GIS Cut Line= 3
      3916925.92     10000830.19      3917591.76     10000662.92
      3917779.03      9999935.93
#Sta/Elev= 30
       0   72.58    94.3   71.34   105.1   69.86   156.7   70.43   181.7   69.67
   208.2   70.67   222.9    70.5   239.1   68.77   270.1   68.37   387.5   69.08
   393.8   68.44     435   68.07   476.3    69.2   527.8   68.43   558.8   69.23
   569.1   68.18     588   69.34   593.2   68.61   610.3   69.05   670.3   67.75
  697.14   68.41   750.4   67.75   768.5   68.62  1053.4   68.39  1122.2   70.82
  1153.1   71.11  1175.5   69.23    1211   71.62  1380.3   71.74  1437.2   72.83
#Mann= 7 ,-1 , 0
       0    .125       0   156.7     .11       0   181.7    .125       0
   393.8     .11       0   476.3     .15       0  697.14     .09       0
   768.5     .15       0
Bank Sta=697.14,768.5
XS Rating Curve= 0 ,0
Exp/Cntr=0.3,0.1

Type RM Length L Ch R = 1 ,15000   ,164,164,164
BEGIN DESCRIPTION:
G103-37-00 30.0
END DESCRIPTION:
XS GIS Cut Line= 4
      3917118.51     10000829.33      3917325.05     10000758.98
       3918066.5     10000778.69      3918566.89     10000768.55
#Sta/Elev= 30
  4040.1   71.42  4123.9   69.21  4176.8    68.9  4212.6   69.27  4281.1   68.36
  4331.1   69.33  4379.3   68.16  4491.2    67.8  4551.2   69.35  4571.2   68.33
  4621.2    68.6  4681.2   70.14  4711.3   68.83  4721.3   69.67  4761.3   68.73
  4791.3   69.51  4821.3   67.82  4871.3    67.6  4889.5   66.63  4911.3   67.72
  5011.4   67.27  5051.4   68.22  5071.4    70.1  5127.8    67.7  5271.4   68.57
  5291.4   69.53  5411.4   69.62  5471.5   72.27  5491.5   77.04  5500.5   77.76
#Mann= 6 ,-1 , 0
  4040.1    .125       0  4176.8     .11       0  4212.6    .125       0
  4379.3     .11       0  4871.3     .07       0  4911.3     .11       0
Bank Sta=4871.3,4911.3
XS Rating Curve= 0 ,0
Exp/Cntr=0.3,0.1

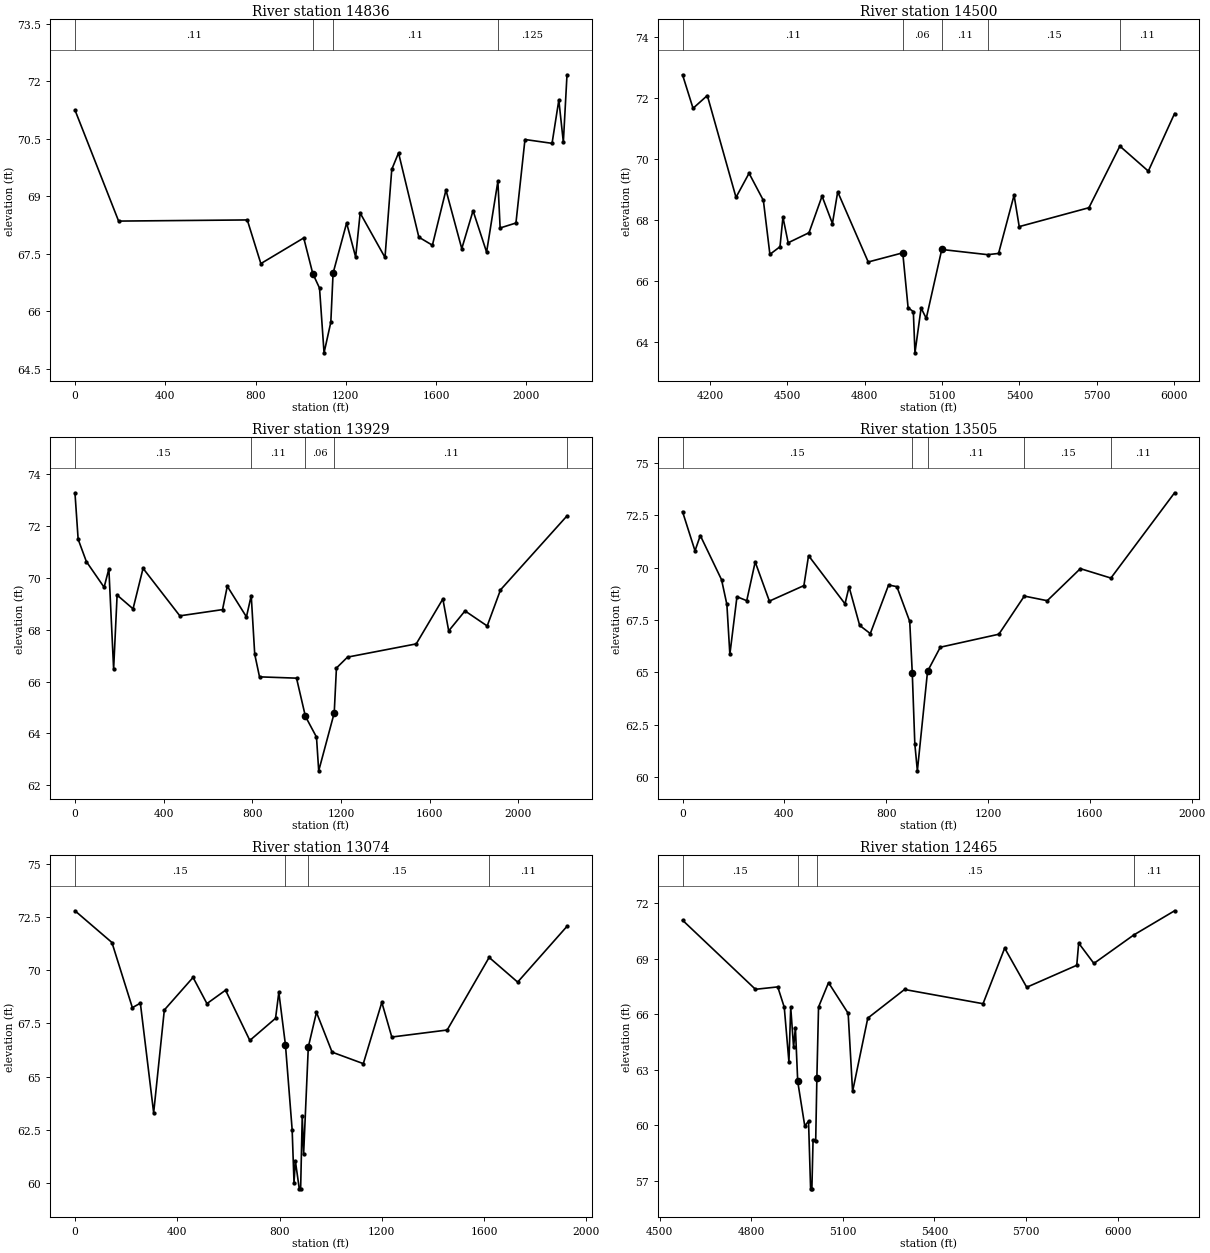
Type RM Length L Ch R = 1 ,14836   ,336,336,336
BEGIN DESCRIPTION:
Mapping XS 777b5285
END DESCRIPTION:
XS GIS Cut Line= 3
      3917014.51     10000914.66       3919020.4     10000946.79
      3919195.16     10000945.23
#Sta/Elev= 30
       0   71.25   193.4   68.35   763.4   68.38   823.5   67.24  1013.5   67.91
  1053.5   66.98  1083.5    66.6  1103.5   64.91  1133.5   65.71  1143.5   66.99
  1203.5    68.3  1243.5   67.41  1263.5   68.56  1373.5    67.4  1403.5    69.7
  1433.5   70.13  1523.5   67.93  1583.5   67.72  1643.6   69.16  1713.6   67.63
  1763.6   68.62  1823.6   67.54  1873.6   69.39  1883.6   68.17  1953.6    68.3
  1993.6   70.48  2113.6   70.38  2143.6   71.51  2163.6   70.41  2179.8   72.17
#Mann= 4 ,-1 , 0
       0     .11       0  1053.5     .07       0  1143.5     .11       0
  1873.6    .125       0
Bank Sta=1053.5,1143.5
XS Rating Curve= 0 ,0
Exp/Cntr=0.3,0.1

Type RM Length L Ch R = 1 ,14500   ,571,571,571
BEGIN DESCRIPTION:
G103-37-00 29.0
END DESCRIPTION:
XS GIS Cut Line= 3
       3917222.8     10001392.09      3918119.17     10001259.03
      3919119.57     10001214.13
#Sta/Elev= 30
  4093.8   72.76  4134.6   71.66  4189.9   72.08  4301.1   68.74  4351.7   69.53
  4407.2   68.64  4432.5   66.87  4471.6   67.12  4483.1   68.09  4503.3   67.25
  4584.2   67.58  4634.7   68.78  4674.9   67.88  4695.4   68.92  4813.7   66.62
  4947.6   66.92  4968.3   65.12  4988.6   64.99  4994.9   63.64  5018.7   65.11
  5038.7   64.77  5098.8   67.03  5276.5   66.86    5319    66.9  5379.1   68.81
  5399.1   67.78  5669.4    68.4  5789.3   70.42  5899.6    69.6  6001.4   71.49
#Mann= 5 ,-1 , 0
  4093.8     .11       0  4947.6     .06       0  5098.8     .11       0
  5276.5     .15       0  5789.3     .11       0
Bank Sta=4947.6,5098.8
XS Rating Curve= 0 ,0
Exp/Cntr=0.3,0.1

Type RM Length L Ch R = 1 ,13929   ,424,424,424
BEGIN DESCRIPTION:
G103-37-00 28.0
END DESCRIPTION:
XS GIS Cut Line= 4
      3917171.96     10002324.27      3917593.48     10002076.27
      3918028.73     10001826.88       3919257.9     10001860.73
#Sta/Elev= 30
       0   73.27    14.4   71.48    51.5   70.62   131.6   69.63     153   70.34
   174.5   66.48   190.2   69.33   262.1    68.8   307.3   70.36   473.2   68.53
   665.9   68.77   687.4   69.67   773.8   68.49   795.4   69.31   811.2   67.05
   832.8   66.18   999.8   66.13  1039.8   64.66  1089.9   63.86  1099.9   62.56
  1169.9   64.79  1179.9   66.52  1229.9   66.94    1540   67.45  1660.1   69.18
  1686.5   67.95  1760.1   68.72  1860.2   68.14  1920.2   69.53  2220.3   72.38
#Mann= 5 ,-1 , 0
       0     .15       0   795.4     .11       0  1039.8     .06       0
  1169.9     .11       0  2220.3     .11       0
Bank Sta=1039.8,1169.9
XS Rating Curve= 0 ,0
Exp/Cntr=0.3,0.1

Type RM Length L Ch R = 1 ,13505   ,431,431,431
BEGIN DESCRIPTION:
G103-37-00 27.0
END DESCRIPTION:
XS GIS Cut Line= 3
      3917270.92     10002477.92       3918090.9      10002234.1
      3919167.85     10002211.07
#Sta/Elev= 30
       0   72.67      49    70.8    69.8   71.53   153.3   69.42   174.2   68.24
   185.9   65.86   213.8   68.61   252.2   68.42   285.4   70.27   341.1    68.4
   476.7   69.14     495   70.57   638.2   68.27   654.1   69.08   695.8   67.24
   737.5   66.85   809.4   69.17   841.9   69.09   892.4   67.43   902.4   64.97
   912.4   61.59   922.4    60.3   962.4   65.05  1012.5    66.2  1242.5   66.82
  1342.5   68.64  1432.5   68.42  1562.6   69.95  1682.6    69.5  1932.7   73.57
#Mann= 5 ,-1 , 0
       0     .15       0   902.4     .09       0   962.4     .11       0
  1342.5     .15       0  1682.6     .11       0
Bank Sta=902.4,962.4
XS Rating Curve= 0 ,0
Exp/Cntr=0.3,0.1

Type RM Length L Ch R = 1 ,13074   ,609,609,609
BEGIN DESCRIPTION:
G103-37-00 26.0
END DESCRIPTION:
XS GIS Cut Line= 3
      3917242.27     10002865.94      3918086.56     10002620.39
      3919067.85     10002261.07
#Sta/Elev= 30
       0   72.79   144.6    71.3   224.5   68.24   255.8   68.45   307.8    63.3
   349.5   68.13   461.9   69.66   516.1   68.43     589   69.06   683.9    66.7
   784.5   67.74   797.3   68.96   823.2   66.49   849.4   62.51   856.7   60.02
     862   61.04   877.3   59.73   882.6   59.73   888.9   63.17   894.2   61.35
   912.6   66.39   944.5   68.02  1005.6   66.15  1127.7   65.61  1200.1   68.49
  1239.1   66.86  1455.7   67.19  1619.8    70.6  1731.3   69.44  1924.3   72.06
#Mann= 4 ,-1 , 0
       0     .15       0   823.2     .09       0   912.6     .15       0
  1619.8     .11       0
Bank Sta=823.2,912.6
XS Rating Curve= 0 ,0
Exp/Cntr=0.3,0.1

Type RM Length L Ch R = 1 ,12465   ,465,465,465
BEGIN DESCRIPTION:
G103-37-00 25.0
END DESCRIPTION:
XS GIS Cut Line= 3
      3917767.86     10003261.07      3918147.32     10003024.03
      3919067.81      10002311.1
#Sta/Elev= 30
  4575.1   71.09  4813.9   67.35    4887   67.48  4908.3   66.38  4923.6   63.42
  4929.5   66.37  4938.9   64.21  4944.8   65.28  4952.4   62.36  4975.5   59.95
  4987.8   60.22  4994.6   56.55  4998.8   56.55  5002.6   59.17  5011.3   59.16
 5015.1762.56683  5020.6   66.39  5053.3   67.71  5117.6   66.05  5132.1   61.82
  5181.9   65.79  5302.3   67.34  5559.4   66.57  5630.3   69.58  5702.5   67.46
  5866.4   68.65  5872.7   69.85  5922.5   68.75  6053.1   70.29  6186.8    71.6
#Mann= 4 ,-1 , 0
  4575.1     .15       0  4952.4     .09       0 5015.17     .15       0
  6053.1     .11       0
Bank Sta=4952.4,5015.17
XS Rating Curve= 0 ,0
Exp/Cntr=0.3,0.1

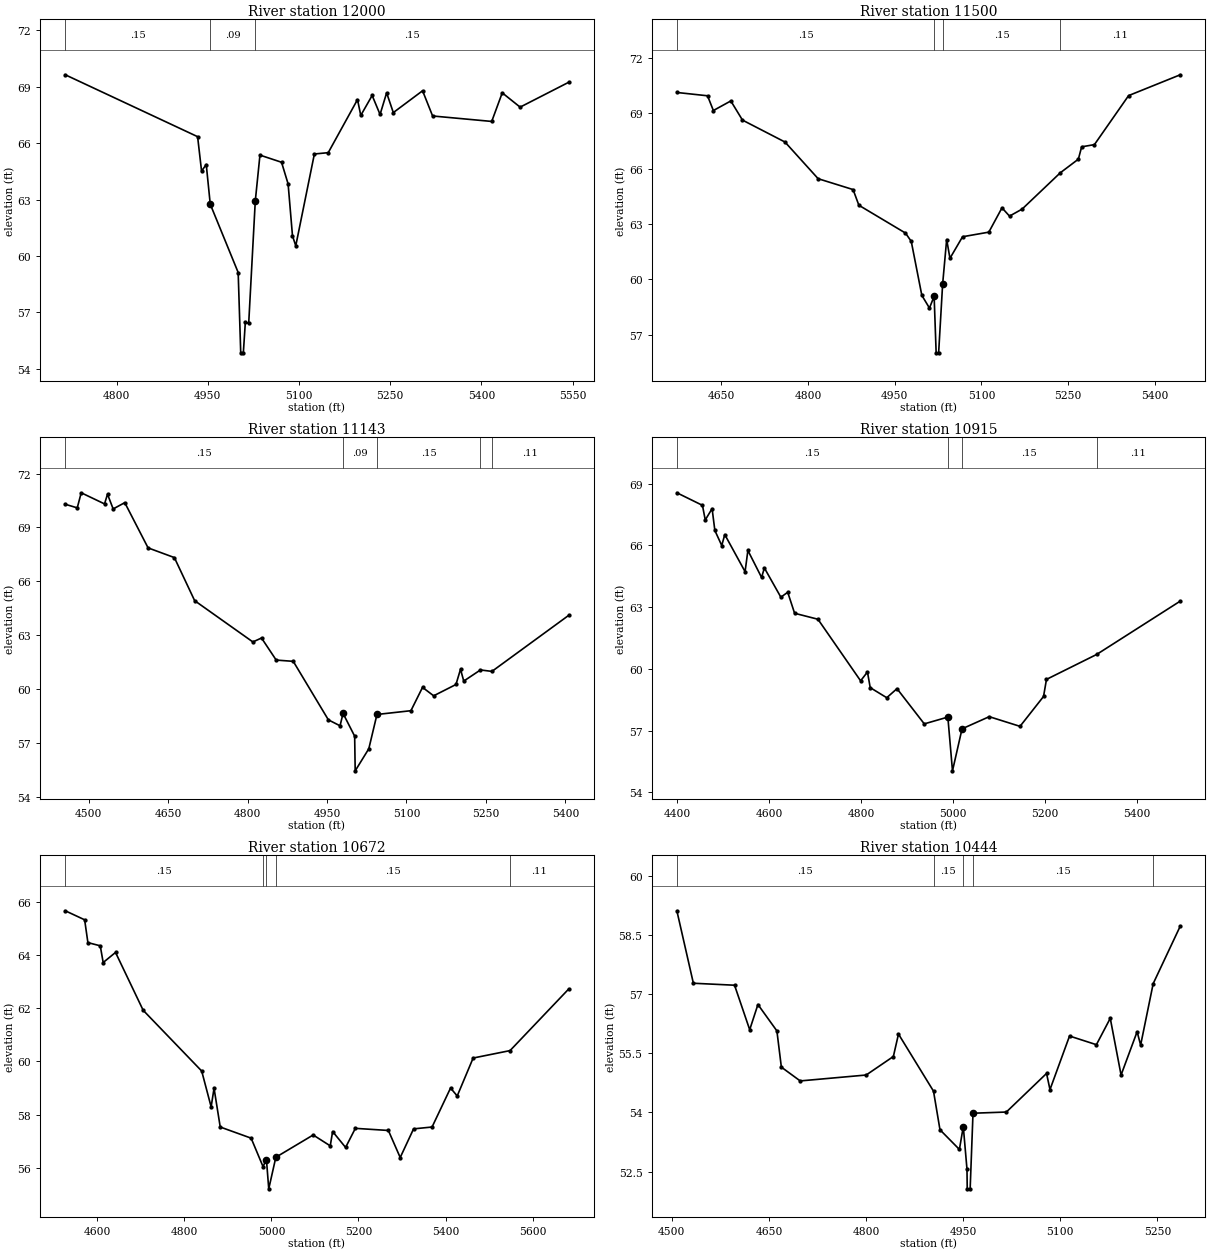
Type RM Length L Ch R = 1 ,12000   ,500,500,500
BEGIN DESCRIPTION:
G103-37-00 24.0
END DESCRIPTION:
XS GIS Cut Line= 3
      3918191.56     10003450.28      3918371.84     10003230.46
      3918874.99     10003025.21
#Sta/Elev= 30
  4715.7   69.63  4933.3   66.34  4939.8   64.51  4947.5   64.86  4954.1   62.75
    5000   59.12  5004.2   54.85  5008.5   54.85  5011.8   56.49  5017.3   56.41
  5028.1   62.91  5035.8   65.36  5071.3   64.98  5082.1   63.83  5089.3   61.07
  5094.7   60.54  5125.3   65.42  5148.1   65.49  5196.2   68.31  5201.6   67.47
  5220.3   68.53  5233.3   67.52  5244.1   68.67  5255.1   67.62  5303.2   68.78
  5319.7   67.44  5416.9   67.15  5434.2   68.67  5463.6   67.91  5543.4   69.23
#Mann= 3 , 0 , 0
  4715.7     .15       0  4954.1     .09       0  5028.1     .15       0
Bank Sta=4954.1,5028.1
XS Rating Curve= 0 ,0
Exp/Cntr=0.3,0.1

Type RM Length L Ch R = 1 ,11500   ,357,357,357
BEGIN DESCRIPTION:
G103-37-00 23.0
END DESCRIPTION:
XS GIS Cut Line= 3
      3918155.14     10003523.16      3918579.05     10003576.02
      3918967.89     10003361.05
#Sta/Elev= 30
  4572.8   70.14  4625.9   69.96    4636   69.16  4666.2   69.68  4686.4   68.64
    4760   67.45  4817.4   65.46  4877.9   64.87  4887.9   64.02  4968.6   62.51
  4978.6   62.06  4996.9   59.13  5010.1   58.44  5018.2   59.08  5021.7   56.01
    5026   56.01  5032.9   59.73  5039.9   62.16  5045.6   61.14  5067.4   62.31
  5112.9   62.56  5135.7   63.88  5148.7   63.43  5170.5   63.81  5236.6   65.78
  5267.9   66.52  5273.6   67.19  5295.7   67.31  5354.9   69.97  5444.3    71.1
#Mann= 4 ,-1 , 0
  4572.8     .15       0  5018.2     .09       0  5032.9     .15       0
  5236.6     .11       0
Bank Sta=5018.2,5032.9
XS Rating Curve= 0 ,0
Exp/Cntr=0.3,0.1

Type RM Length L Ch R = 1 ,11143   ,228,228,228
BEGIN DESCRIPTION:
G103-37-00 22.0
END DESCRIPTION:
XS GIS Cut Line= 3
      3918117.88     10003661.09      3918603.05       10003919.
      3918932.99     10003691.73
#Sta/Elev= 30
    4456   70.29  4478.6   70.09  4486.1   70.93  4530.1   70.31  4535.7   70.85
  4546.4   70.03  4568.3   70.38  4612.3   67.86  4661.9   67.32  4700.2   64.92
  4810.1   62.62  4826.4   62.84  4854.1   61.61  4886.3   61.54  4952.6   58.28
  4974.6   57.95  4980.3   58.64  5002.2   57.37  5003.2   55.44  5028.9   56.67
  5044.3   58.58  5108.4   58.79  5130.3   60.09  5151.3   59.62  5193.4   60.25
    5202    61.1  5208.1   60.44  5239.6   61.06  5261.3   60.98  5406.1    64.1
#Mann= 5 ,-1 , 0
    4456     .15       0  4980.3     .09       0  5044.3     .15       0
  5239.6     .15       0  5261.3     .11       0
Bank Sta=4980.3,5044.3
XS Rating Curve= 0 ,0
Exp/Cntr=0.3,0.1

Type RM Length L Ch R = 1 ,10915   ,243,243,243
BEGIN DESCRIPTION:
Mapping XS 51cdb4ad
END DESCRIPTION:
XS GIS Cut Line= 4
      3918161.65     10003771.43      3918601.72     10004070.88
      3918724.12     10004099.53      3918958.49     10003729.74
#Sta/Elev= 30
  4399.4   68.55  4455.1   67.94  4461.2   67.23  4476.1   67.78  4482.1   66.72
  4497.1   65.99  4503.7   66.52  4547.9   64.72    4554   65.75  4583.8   64.44
  4589.9    64.9  4625.8   63.48  4640.7   63.72  4655.7    62.7  4706.5   62.41
  4799.4   59.42  4814.3   59.85  4820.3   59.09  4856.3    58.6  4878.6   59.04
    4938   57.33  4989.3   57.66  4999.4   55.05  5020.2   57.09  5079.4   57.68
  5146.4   57.21  5197.6   58.66    5204   59.49  5313.2    60.7  5495.2   63.29
#Mann= 4 ,-1 , 0
  4399.4     .15       0  4989.3     .09       0  5020.2     .15       0
  5313.2     .11       0
Bank Sta=4989.3,5020.2
XS Rating Curve= 0 ,0
Exp/Cntr=0.3,0.1

Type RM Length L Ch R = 1 ,10672   ,228,228,228
BEGIN DESCRIPTION:
Mapping XS e24559f0
END DESCRIPTION:
XS GIS Cut Line= 4
      3918158.17     10003897.73      3918531.84     10004234.95
      3918732.36     10004134.69      3918958.94     10003770.08
#Sta/Elev= 30
  4526.2   65.68  4570.7   65.34  4578.2   64.48  4606.6   64.36  4613.3   63.73
  4641.7   64.11  4705.2   61.93  4839.7   59.64  4861.4   58.29  4868.1   58.99
  4882.3   57.53  4953.3   57.11  4980.6   56.04  4988.5    56.3  4993.8    55.2
  5010.1   56.39  5095.9   57.23  5135.1   56.82  5140.6   57.36  5170.4   56.76
  5192.8   57.48  5268.7    57.4  5295.9   56.38  5326.6   57.46  5369.1   57.53
  5411.6      59  5426.9    58.7  5463.5   60.13  5548.3   60.41    5683   62.73
#Mann= 5 ,-1 , 0
  4526.2     .15       0  4980.6     .15       0  4988.5     .09       0
  5010.1     .15       0  5548.3     .11       0
Bank Sta=4988.5,5010.1
XS Rating Curve= 0 ,0
Exp/Cntr=0.3,0.1

Type RM Length L Ch R = 1 ,10444   ,446,446,446
BEGIN DESCRIPTION:
G103-37-00 21.0
END DESCRIPTION:
XS GIS Cut Line= 3
      3918083.97     10004691.88      3918492.22     10004416.94
      3918758.92     10004518.27
#Sta/Elev= 30
  4507.8   59.12  4533.3   57.28  4596.9   57.23  4620.3    56.1    4633   56.74
  4662.3   56.07  4669.2   55.15  4698.3    54.8  4800.2   54.95  4842.2   55.42
  4850.1   55.99  4904.2   54.54  4914.2   53.56  4944.2   53.06  4950.2   53.64
  4955.9   52.56  4956.3   52.06  4960.8   52.06  4965.2   53.98  5016.7   54.01
  5078.8   54.99  5084.1   54.58  5114.3   55.94  5155.8   55.72  5177.2   56.39
  5193.9   54.95  5218.7   56.05  5224.1   55.71  5243.5   57.27  5285.3   58.73
#Mann= 5 ,-1 , 0
  4507.8     .15       0  4904.2     .15       0  4950.2     .09       0
  4965.2     .15       0  5243.5     .15       0
Bank Sta=4950.2,4965.2
XS Rating Curve= 0 ,0
Exp/Cntr=0.3,0.1