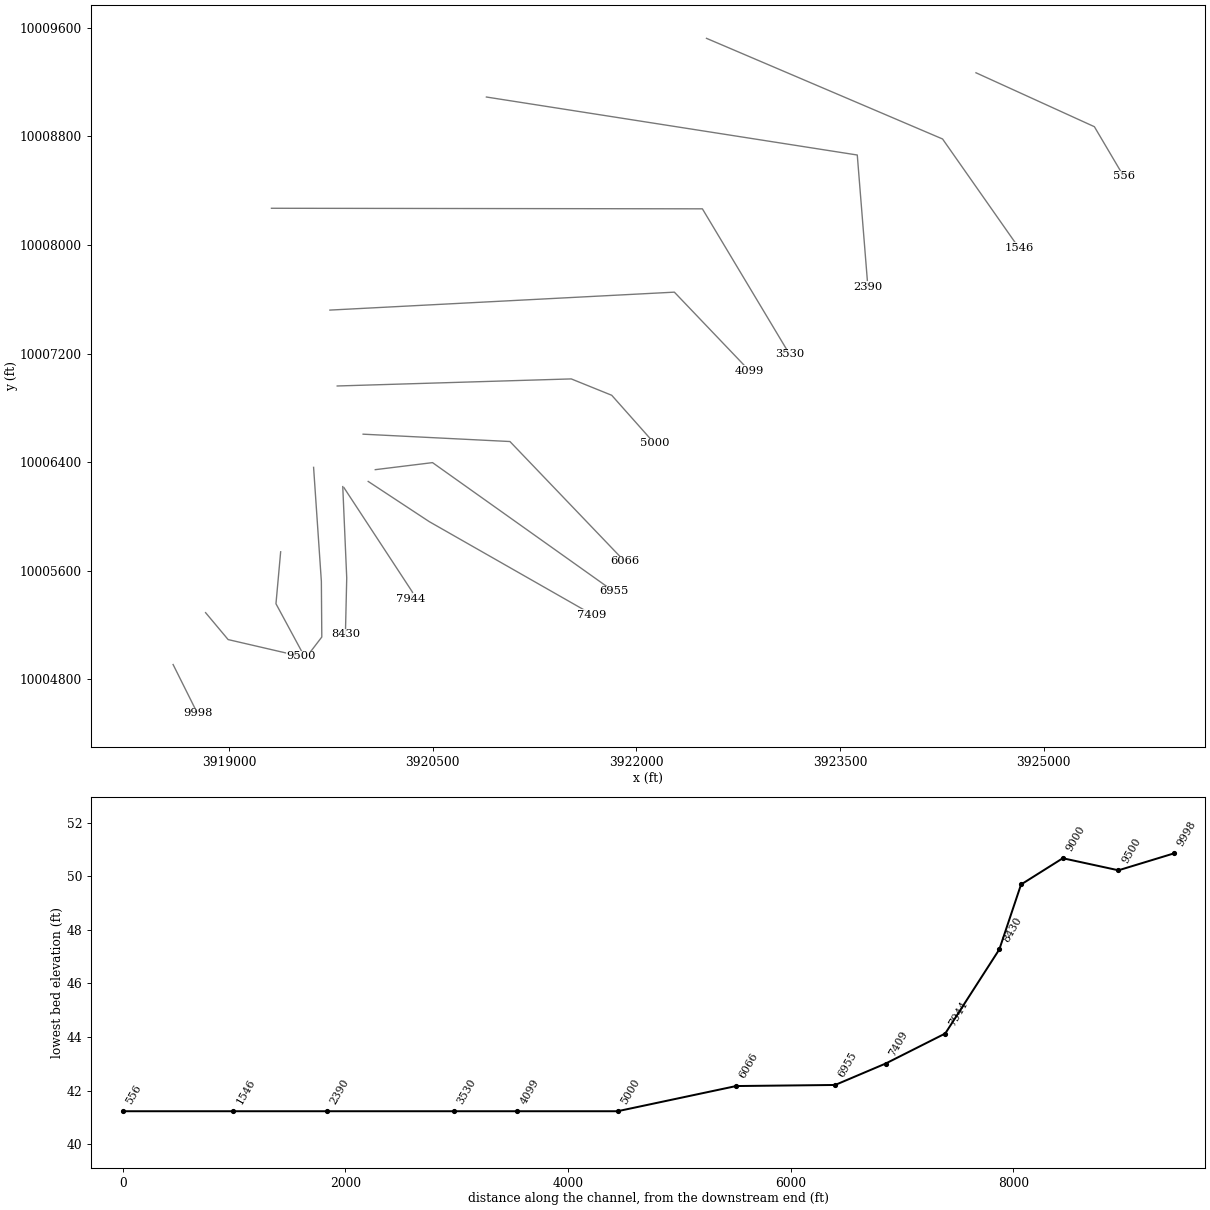
HEC-RAS study G103 37 00.prj: G103 37 00 Base Level Engineering

--- G103 37 00.g01 (geometry) --- (continued)

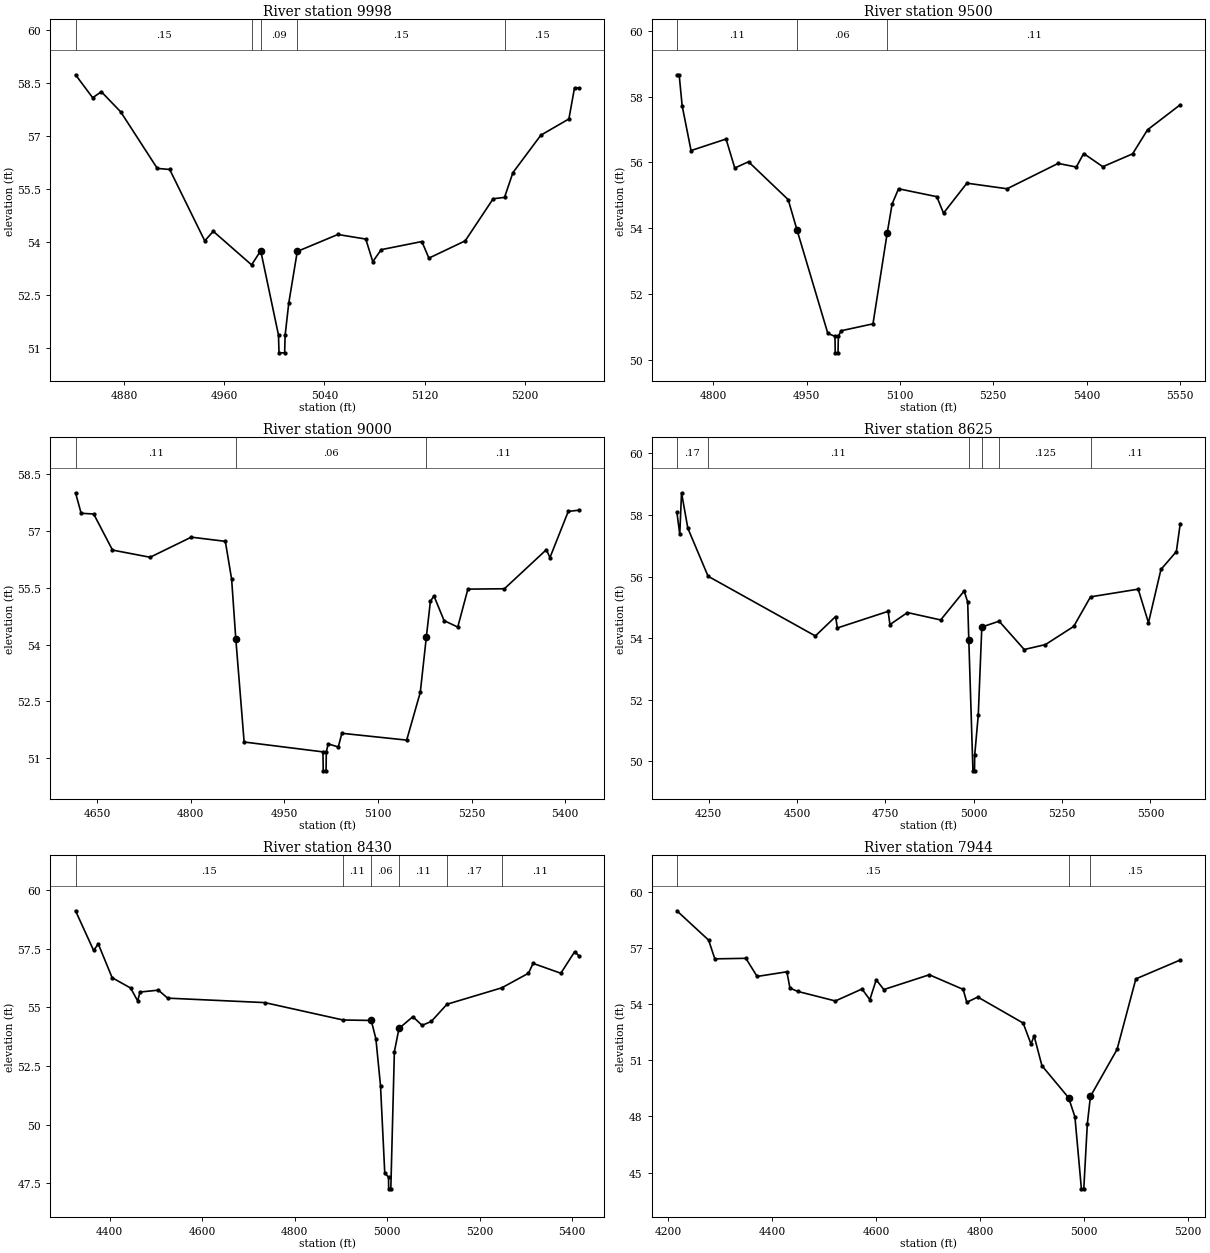
Type RM Length L Ch R = 1 ,9998    ,498,498,498
BEGIN DESCRIPTION:
G103-37-00 20.0
END DESCRIPTION:
XS GIS Cut Line= 2
       3918587.3     10004909.48      3918766.87     10004549.82
#Sta/Elev= 30
  4841.3   58.72    4855   58.07  4861.9   58.24  4877.4   57.67  4906.6   56.07
  4916.5   56.04  4944.5   54.02  4951.3   54.29  4981.9   53.34  4989.2   53.74
  5003.4   51.35  5003.8   50.85  5008.3   50.85  5008.7   51.35  5011.6   52.26
  5018.4   53.72  5050.8    54.2  5073.1   54.07  5078.7   53.43  5085.4   53.77
  5117.9      54  5123.5   53.53  5152.5   54.02  5174.8   55.21  5183.9   55.25
  5190.6   55.95  5212.9   57.01  5235.3   57.47  5239.8   58.35  5243.3   58.35
#Mann= 5 ,-1 , 0
  4841.3     .15       0  4981.9     .15       0  4989.2     .09       0
  5018.4     .15       0  5183.9     .15       0
Bank Sta=4989.2,5018.4
XS Rating Curve= 0 ,0
Exp/Cntr=0.3,0.1

Type RM Length L Ch R = 1 ,9500    ,500,500,500
BEGIN DESCRIPTION:
G103-37-00 19.0
END DESCRIPTION:
XS GIS Cut Line= 3
      3918826.62      10005291.7      3918992.62     10005093.41
      3919529.12     10004969.16
#Sta/Elev= 30
  4741.4   58.66  4745.1   58.66  4749.9   57.72  4764.2   56.36  4820.5   56.71
  4834.5   55.83  4856.6   56.02  4920.4   54.87  4934.7   53.94  4984.1   50.81
  4995.6   50.72    4996   50.22  5000.5   50.22    5001   50.72  5005.4   50.89
  5056.7    51.1  5079.6   53.86  5087.5   54.74  5097.8    55.2  5159.3   54.96
  5170.1   54.46  5207.7   55.37  5272.3    55.2  5354.4   55.97  5383.6   55.86
  5395.4   56.27  5426.2   55.87  5474.1   56.26  5498.1   56.99  5550.7   57.75
#Mann= 3 , 0 , 0
  4741.4     .11       0  4934.7     .06       0  5079.6     .11       0
Bank Sta=4934.7,5079.6
XS Rating Curve= 0 ,0
Exp/Cntr=0.3,0.1

Type RM Length L Ch R = 1 ,9000    ,375,375,375
BEGIN DESCRIPTION:
G103-37-00 18.0
END DESCRIPTION:
XS GIS Cut Line= 3
      3919379.59     10005740.02      3919345.02     10005357.28
       3919545.4     10004986.12
#Sta/Elev= 30
  4615.7      58  4624.7   57.46  4644.8   57.44  4674.9   56.49  4735.1    56.3
  4801.1   56.83  4855.6   56.72  4865.7   55.72 4872.3254.15777  4885.7   51.43
  5011.9   51.17  5012.4   50.67  5016.9   50.67  5017.3   51.17  5020.3   51.38
  5036.5    51.3  5042.2   51.66    5146   51.48  5167.8   52.74  5177.5    54.2
    5184   55.14  5189.7   55.28  5205.9   54.63  5227.8   54.46    5244   55.46
  5302.5   55.47  5369.7    56.5  5375.4   56.29  5404.8   57.51  5421.8   57.54
#Mann= 3 , 0 , 0
  4615.7     .11       0 4872.32     .06       0  5177.5     .11       0
Bank Sta=4872.32,5177.5
XS Rating Curve= 0 ,0
Exp/Cntr=0.3,0.1

Type RM Length L Ch R = 1 ,8625    ,195,195,195
BEGIN DESCRIPTION:
G103-37-00 15.0
END DESCRIPTION:
XS GIS Cut Line= 4
      3919622.14     10006361.96      3919679.44     10005521.86
       3919682.6     10005112.21      3919577.73     10004975.26
#Sta/Elev= 30
  4160.1    58.1  4168.3   57.37  4173.3   58.72  4191.1   57.57  4248.4   56.01
  4551.9   54.07  4609.2    54.7  4614.2   54.33  4757.9   54.87  4762.9   54.44
  4812.5   54.83  4906.5   54.59  4972.9   55.53  4982.9   55.17 4986.0953.94187
  4997.8   49.69  5002.3   49.69  5002.7   50.19  5012.9   51.51  5022.9   54.36
  5071.8   54.55  5142.9   53.63  5202.9   53.79  5282.9   54.38  5330.4   55.34
  5465.3   55.59  5494.4    54.5  5529.7   56.23  5573.3   56.81  5584.3   57.72
#Mann= 6 ,-1 , 0
  4160.1     .17       0  4248.4     .11       0 4986.09     .06       0
  5022.9     .11       0  5071.8    .125       0  5330.4     .11       0
Bank Sta=4986.09,5022.9
XS Rating Curve= 0 ,0
Exp/Cntr=0.3,0.1

Type RM Length L Ch R = 1 ,8430    ,486,486,486
BEGIN DESCRIPTION:
G103-37-00 14.0
END DESCRIPTION:
XS GIS Cut Line= 3
        3919837.     10006220.21      3919866.25     10005547.68
      3919856.53     10005131.96
#Sta/Elev= 30
    4326   59.11  4365.2   57.42  4375.2    57.7  4405.2   56.26  4445.2   55.82
  4460.5   55.27  4465.5   55.65  4505.3   55.73  4525.3   55.39  4735.5    55.2
  4904.6   54.46  4965.7   54.44  4975.8   53.66  4985.8   51.66    4995   47.94
  5003.1   47.77  5003.5   47.27  5008.1   47.27  5015.8   53.11  5025.8    54.1
  5055.8    54.6  5075.8   54.23  5095.8    54.4  5129.6   55.13  5248.2   55.83
  5305.9   56.45  5315.9   56.87  5375.9   56.45  5405.9   57.37    5415   57.19
#Mann= 6 ,-1 , 0
    4326     .15       0  4904.6     .11       0  4965.7     .06       0
  5025.8     .11       0  5129.6     .17       0  5248.2     .11       0
Bank Sta=4965.7,5025.8
XS Rating Curve= 0 ,0
Exp/Cntr=0.3,0.1

Type RM Length L Ch R = 1 ,7944    ,535,535,535
BEGIN DESCRIPTION:
G103-37-00 13.0
END DESCRIPTION:
XS GIS Cut Line= 3
      3919846.02     10006212.24      3920351.65     10005441.04
      3920339.26     10005395.26
#Sta/Elev= 30
  4216.3   58.99  4277.5   57.42  4289.4   56.42  4349.2   56.45  4370.9   55.48
  4428.2   55.73  4434.1   54.86  4449.2   54.68  4521.6   54.17  4572.9   54.81
    4588   54.24  4600.3    55.3    4615   54.78  4702.5   55.57  4767.7   54.79
  4774.8    54.1  4795.9   54.38  4883.3   52.99  4898.4   51.87  4904.4    52.3
  4919.5   50.71  4970.8      49    4983   47.98  4995.5   44.13  5000.1   44.13
  5006.9   47.59  5012.9   49.07  5064.2   51.58  5100.4   55.35  5185.9   56.36
#Mann= 3 , 0 , 0
  4216.3     .15       0  4970.8     .09       0  5012.9     .15       0
Bank Sta=4970.8,5012.9
XS Rating Curve= 0 ,0
Exp/Cntr=0.3,0.1

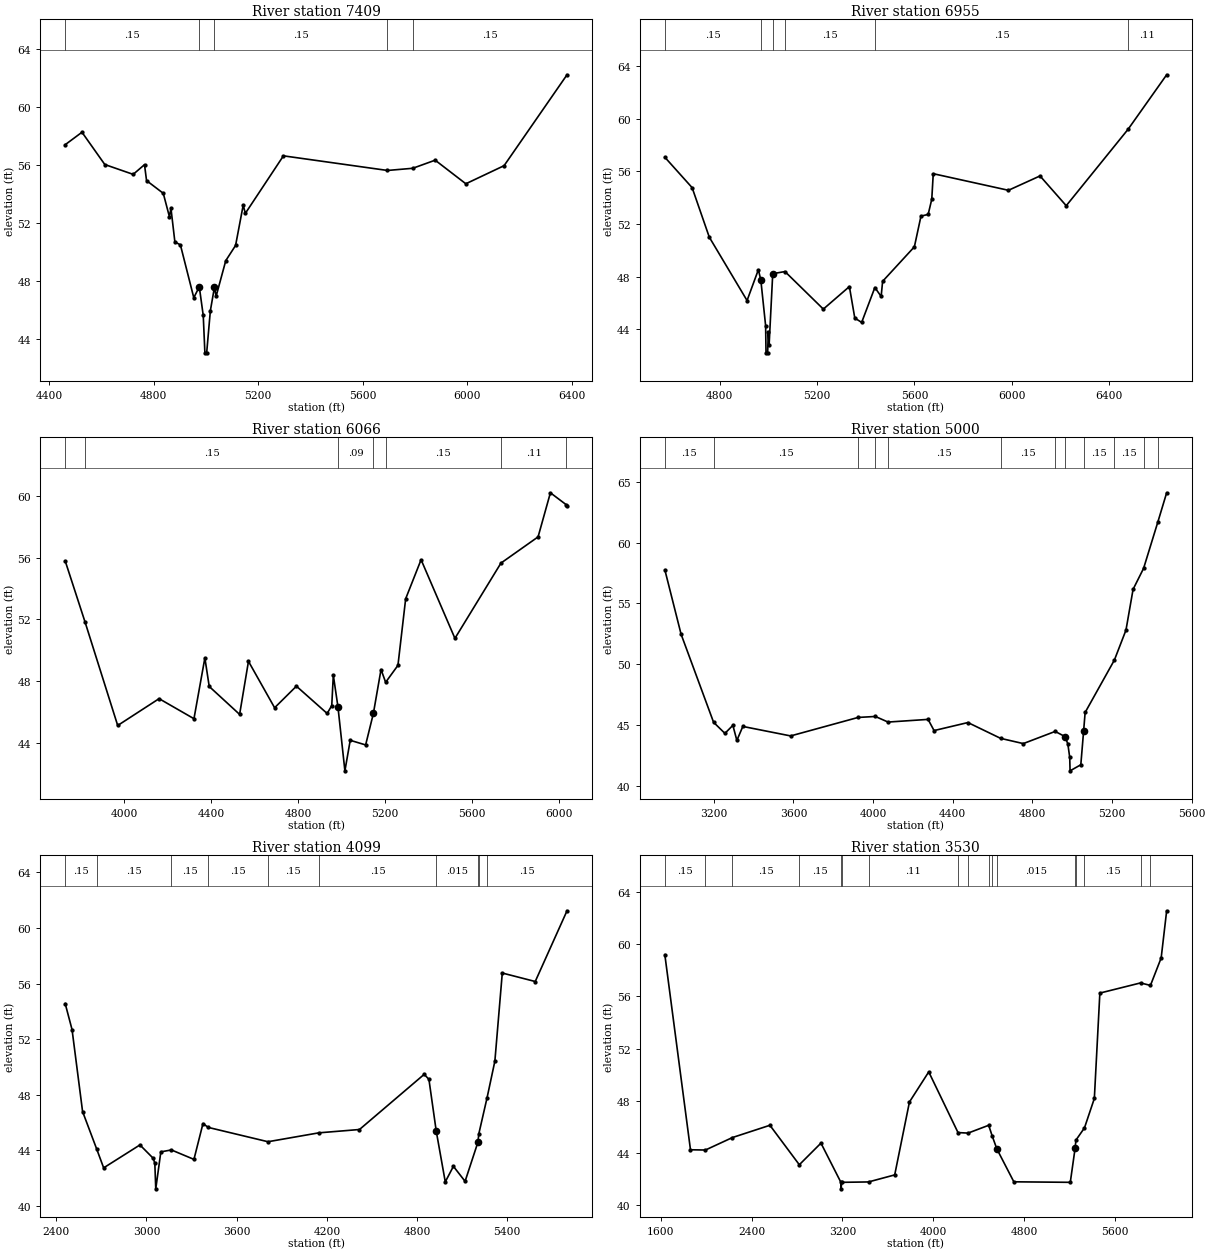
Type RM Length L Ch R = 1 ,7409    ,454,454,454
BEGIN DESCRIPTION:
G103-37-00 12.0
END DESCRIPTION:
XS GIS Cut Line= 3
      3920024.46     10006258.21      3920474.41     10005961.98
      3921674.17     10005278.07
#Sta/Elev= 30
  4461.3   57.39  4525.5   58.25  4612.8   56.02  4721.3   55.34  4764.7   56.01
  4772.5   54.91  4836.5   54.03  4859.9   52.42  4865.9   52.99  4880.9   50.67
    4902   50.47  4953.2   46.82  4974.3   47.57  4989.4   45.59  4995.7   43.01
  5002.5   43.01  5016.6   45.92  5032.4   47.56  5038.5   46.91  5075.6   49.38
  5113.1   50.43  5142.1    53.2  5150.6   52.65  5296.1   56.62  5694.2   55.61
  5790.8   55.76  5876.6   56.32  5993.9   54.69  6140.2   55.94    6381   62.22
#Mann= 5 ,-1 , 0
  4461.3     .15       0  4974.3     .09       0  5032.4     .15       0
  5694.2     .11       0  5790.8     .15       0
Bank Sta=4974.3,5032.4
XS Rating Curve= 0 ,0
Exp/Cntr=0.3,0.1

Type RM Length L Ch R = 1 ,6955    ,889,889,889
BEGIN DESCRIPTION:
G103-37-00 11.0
END DESCRIPTION:
XS GIS Cut Line= 3
      3920076.61       10006345.      3920498.23     10006396.84
      3921831.79     10005449.16
#Sta/Elev= 30
  4575.2   57.06  4687.3   54.75  4757.8   50.99  4912.9   46.18  4959.3   48.52
  4969.4   47.74  4989.1   44.27  4990.7   42.21  4997.5   42.21    5000   43.82
  5003.5   42.82  5018.3   48.22  5068.6   48.38  5226.1   45.53  5333.1   47.24
  5355.3   44.85  5383.5   44.52  5437.7   47.17  5463.5   46.49  5469.6   47.64
    5600   50.26  5627.1   52.59  5656.6   52.72  5671.4   53.87  5677.5   55.81
  5986.2   54.55  6115.9   55.64  6223.6   53.38  6477.9   59.19    6636   63.32
#Mann= 6 ,-1 , 0
  4575.2     .15       0  4969.4     .09       0  5018.3     .15       0
  5068.6     .15       0  5437.7     .15       0  6477.9     .11       0
Bank Sta=4969.4,5018.3
XS Rating Curve= 0 ,0
Exp/Cntr=0.3,0.1

Type RM Length L Ch R = 1 ,6066    ,1066,1066,1066
BEGIN DESCRIPTION:
G103-37-00 10.5
END DESCRIPTION:
XS GIS Cut Line= 3
      3919986.95     10006606.36       3921068.5     10006552.21
      3921913.98     10005669.09
#Sta/Elev= 30
  3729.6   55.78  3820.8   51.82  3970.8   45.11    4161   46.85  4321.2   45.55
  4371.3   49.49  4391.3   47.64  4530.9   45.83  4571.6   49.27  4691.7   46.26
  4791.8   47.66  4933.1   45.89  4954.2    46.4  4961.4   48.37  4982.5   46.34
  5014.6   42.17  5039.1   44.15  5109.9   43.85  5145.4   45.89  5180.6   48.74
  5201.8   47.91  5258.3   49.01  5293.8   53.33  5364.6   55.86  5520.1   50.76
  5731.5   55.64  5902.1   57.34  5958.7    60.2    6032   59.42  6035.1   59.32
#Mann= 7 ,-1 , 0
  3729.6     .17       0  3820.8     .15       0  4982.5     .09       0
  5145.4     .15       0  5201.8     .15       0  5731.5     .11       0
    6032    .125       0
Bank Sta=4982.5,5145.4
XS Rating Curve= 0 ,0
Exp/Cntr=0.3,0.1

Type RM Length L Ch R = 1 ,5000    ,901,901,901
BEGIN DESCRIPTION:
G103-37-00 10.0
END DESCRIPTION:
XS GIS Cut Line= 4
      3919796.18     10006961.39      3921520.11     10007013.48
      3921818.23     10006892.89      3922133.35     10006538.27
#Sta/Elev= 30
  2953.7   57.76  3035.4   52.46  3198.6   45.22  3255.5   44.31  3295.5   44.97
  3315.5   43.73  3345.5   44.88  3585.7    44.1  3924.5   45.62  4011.2    45.7
  4074.8   45.24    4276   45.46    4306   44.54  4476.1    45.2  4640.5    43.9
  4754.2   43.47  4914.4   44.47  4963.3   44.05    4978   43.45  4987.5   42.33
  4989.2   41.23  5043.2   41.73  5057.4   44.53  5064.9   46.03  5211.9   50.34
    5270    52.8  5305.7   56.15  5358.6   57.88    5430   61.68  5474.4   64.09
#Mann= 12 ,-1 , 0
  2953.7     .15       0  3198.6     .15       0  3924.5     .15       0
  4011.2     .15       0  4074.8     .15       0  4640.5     .15       0
  4914.4     .15       0  4963.3    .015       0  5057.4     .15       0
  5211.9     .15       0  5358.6     .11       0    5430     .15       0
Bank Sta=4963.3,5057.4
XS Rating Curve= 0 ,0
Exp/Cntr=0.3,0.1

Type RM Length L Ch R = 1 ,4099    ,569,569,569
BEGIN DESCRIPTION:
G103-37-00 9.0
END DESCRIPTION:
XS GIS Cut Line= 3
      3919742.28     10007520.42      3922279.64     10007652.53
      3922830.88      10007075.1
#Sta/Elev= 30
  2459.2   54.56  2504.8   52.69  2574.9   46.79  2668.9   44.09  2715.1   42.74
  2956.5   44.39  3045.6   43.42  3055.6   43.06  3061.8   41.23  3095.6   43.89
  3165.7   44.03  3315.9   43.35    3376   45.93  3411.1   45.65  3808.6   44.62
  4146.9   45.26  4417.4    45.5    4848   49.47  4879.4   49.11  4928.1   45.38
  4988.2   41.73  5042.3   42.85    5120   41.77  5204.9   44.57  5211.8   45.21
    5266   47.77  5318.2   50.42  5367.5   56.76  5586.8   56.15  5798.3   61.24
#Mann= 10 ,-1 , 0
  2459.2     .15       0  2668.9     .15       0  3165.7     .15       0
  3411.1     .15       0  3808.6     .15       0  4146.9     .15       0
  4928.1    .015       0  5204.9     .12       0  5211.8     .15       0
    5266     .15       0
Bank Sta=4928.1,5204.9
XS Rating Curve= 0 ,0
Exp/Cntr=0.3,0.1

Type RM Length L Ch R = 1 ,3530    ,1140,1140,1140
BEGIN DESCRIPTION:
G103-37-00 7.0
END DESCRIPTION:
XS GIS Cut Line= 3
       3919311.8     10008270.42      3922486.06     10008266.29
      3923127.98     10007195.06
#Sta/Elev= 30
  1634.4   59.21  1860.5   44.23  1992.2   44.21  2230.6   45.17  2560.5   46.11
  2819.8   43.08  3010.5   44.74  3186.2   41.73  3186.7   41.23  3194.7   41.73
  3429.6   41.76  3660.5    42.3  3790.5    47.9  3960.5   50.21  4218.5   45.55
    4307   45.51  4488.9   46.11  4520.5   45.27  4560.5    44.3  4710.5   41.77
  5208.1   41.73  5250.9   44.37  5257.7   44.97  5333.1   45.91  5420.1   48.17
  5468.7   56.26    5827   57.04  5914.7   56.85  6009.1   58.96  6057.5   62.58
#Mann= 17 ,-1 , 0
  1634.4     .15       0  1992.2     .15       0  2230.6     .15       0
  2819.8     .15       0  3186.2     .08       0  3194.7     .15       0
  3429.6     .11       0  4218.5     .15       0    4307     .15       0
  4488.9     .15       0  4520.5     .11       0  4560.5    .015       0
  5250.9     .11       0  5257.7     .15       0  5333.1     .15       0
    5827     .11       0  5914.7     .15       0
Bank Sta=4560.5,5250.9
XS Rating Curve= 0 ,0
Exp/Cntr=0.3,0.1

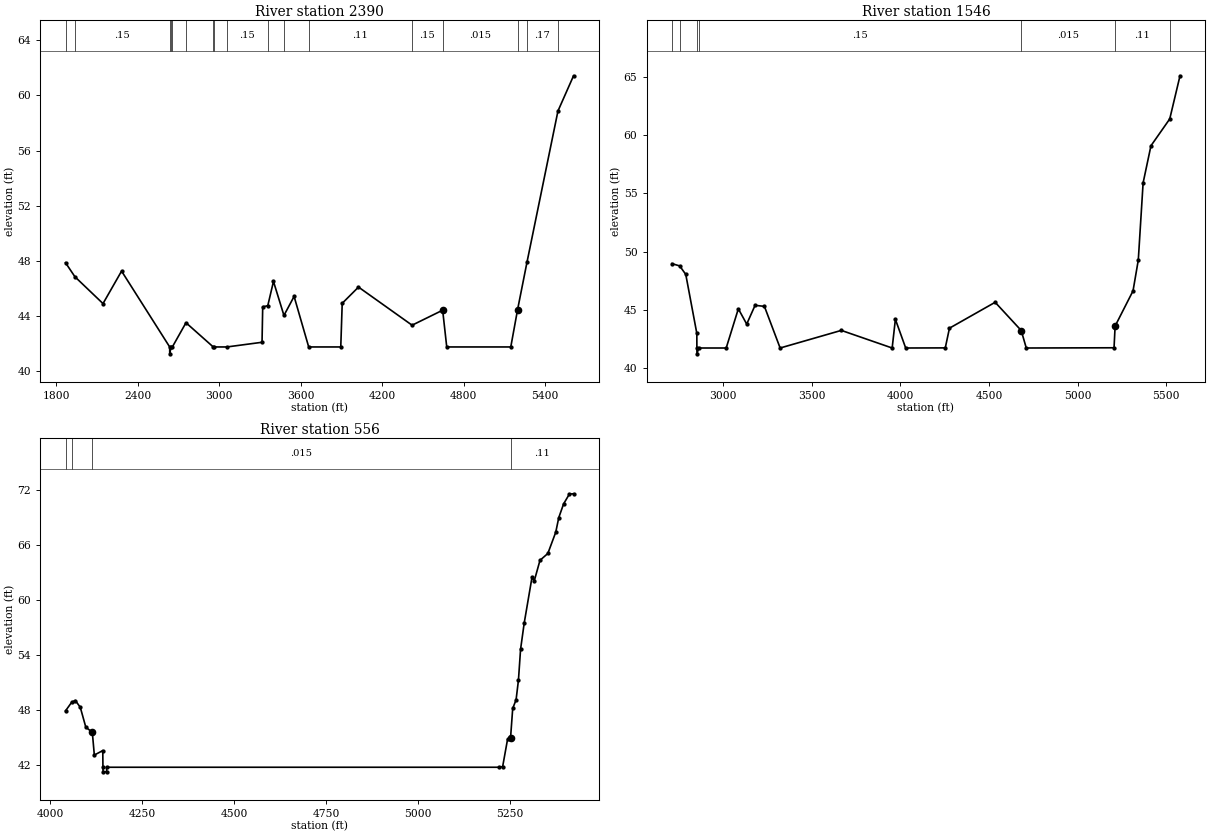
Type RM Length L Ch R = 1 ,2390    ,844,844,844
BEGIN DESCRIPTION:
G103-37-00 5.0
END DESCRIPTION:
XS GIS Cut Line= 3
       3920895.1     10009089.87      3923626.92      10008662.7
      3923705.05     10007690.46
#Sta/Elev= 30
  1869.2   47.85  1938.5   46.83  2145.3   44.88    2282   47.24  2636.2   41.73
  2636.7   41.23  2646.2   41.73  2655.8   41.73  2756.2   43.49    2957   41.73
  2964.4   41.73  3057.4   41.73  3316.1   42.07  3321.1   44.64  3358.5   44.73
  3400.3   46.49  3477.4   44.02  3552.2    45.4  3659.7   41.73  3895.8   41.73
  3906.4    44.9  4026.3   46.08  4420.8   43.31  4645.9    44.4    4676   41.73
  5147.5   41.73  5197.7   44.45  5267.1    47.9  5494.8   58.87  5609.6   61.43
#Mann= 17 ,-1 , 0
  1869.2     .11       0  1938.5     .15       0  2636.2     .08       0
  2646.2     .17       0  2655.8     .15       0  2756.2     .11       0
    2957     .15       0  2964.4     .11       0  3057.4     .15       0
  3358.5     .11       0  3477.4     .15       0  3659.7     .11       0
  4420.8     .15       0  4645.9    .015       0  5197.7     .15       0
  5267.1     .17       0  5494.8     .11       0
Bank Sta=4645.9,5197.7
XS Rating Curve= 0 ,0
Exp/Cntr=0.3,0.1

Type RM Length L Ch R = 1 ,1546    ,990,990,990
BEGIN DESCRIPTION:
G103-37-00 3.0
END DESCRIPTION:
XS GIS Cut Line= 3
      3922516.23     10009522.14      3924255.19     10008780.77
      3924816.11     10007980.46
#Sta/Elev= 30
  2710.5   48.96  2753.9   48.77  2788.4   48.04  2850.8   42.98  2851.1   41.73
  2851.6   41.23  2861.3   41.73  3016.6   41.73  3085.1   45.09  3132.4   43.78
  3179.6   45.39  3232.3    45.3    3321   41.73  3666.4   43.24  3953.4   41.73
  3971.6   44.19  4029.7   41.73  4253.2   41.74  4276.8   43.43  4534.8   45.65
  4681.9   43.23  4710.4   41.73  5205.8   41.75  5211.9   43.61    5313   46.63
  5342.7   49.27  5369.9   55.89  5414.2   59.07  5520.2   61.37  5578.2   65.07
#Mann= 7 ,-1 , 0
  2710.5     .11       0  2753.9     .15       0  2851.1     .08       0
  2861.3     .15       0  4681.9    .015       0  5211.9     .11       0
  5520.2    .125       0
Bank Sta=4681.9,5211.9
XS Rating Curve= 0 ,0
Exp/Cntr=0.3,0.1

Type RM Length L Ch R = 1 ,556     ,0,0,0
BEGIN DESCRIPTION:
G103-37-00 1.0
END DESCRIPTION:
XS GIS Cut Line= 3
      3924501.27     10009268.45      3925373.39     10008871.28
      3925588.71     10008506.48
#Sta/Elev= 30
  4041.7   47.88  4058.7   48.83  4068.5   49.01  4081.9   48.27    4097   46.09
  4114.6   45.55  4120.1   43.06  4143.1   43.55  4143.5   41.73    4144   41.23
  4153.3   41.23  4153.8   41.73    5221   41.73  5230.8   41.81  5244.1   44.78
  5252.3   44.96  5258.1   48.14  5267.3   49.09  5273.7   51.22  5279.5    54.6
  5289.4   57.46  5310.8    62.5  5316.6   62.04  5332.3    64.3  5353.7   65.05
  5375.2   67.37  5383.4   68.96  5396.6   70.46  5412.3   71.53  5423.6   71.56
#Mann= 4 ,-1 , 0
  4041.7     .11       0  4058.7     .15       0  4114.6    .015       0
  5252.3     .11       0
Bank Sta=4114.6,5252.3
XS Rating Curve= 0 ,0
Exp/Cntr=0.3,0.1

Chan Stop Cuts=-1
Use User Specified Reach Order=0
Composite Channel Slope=5