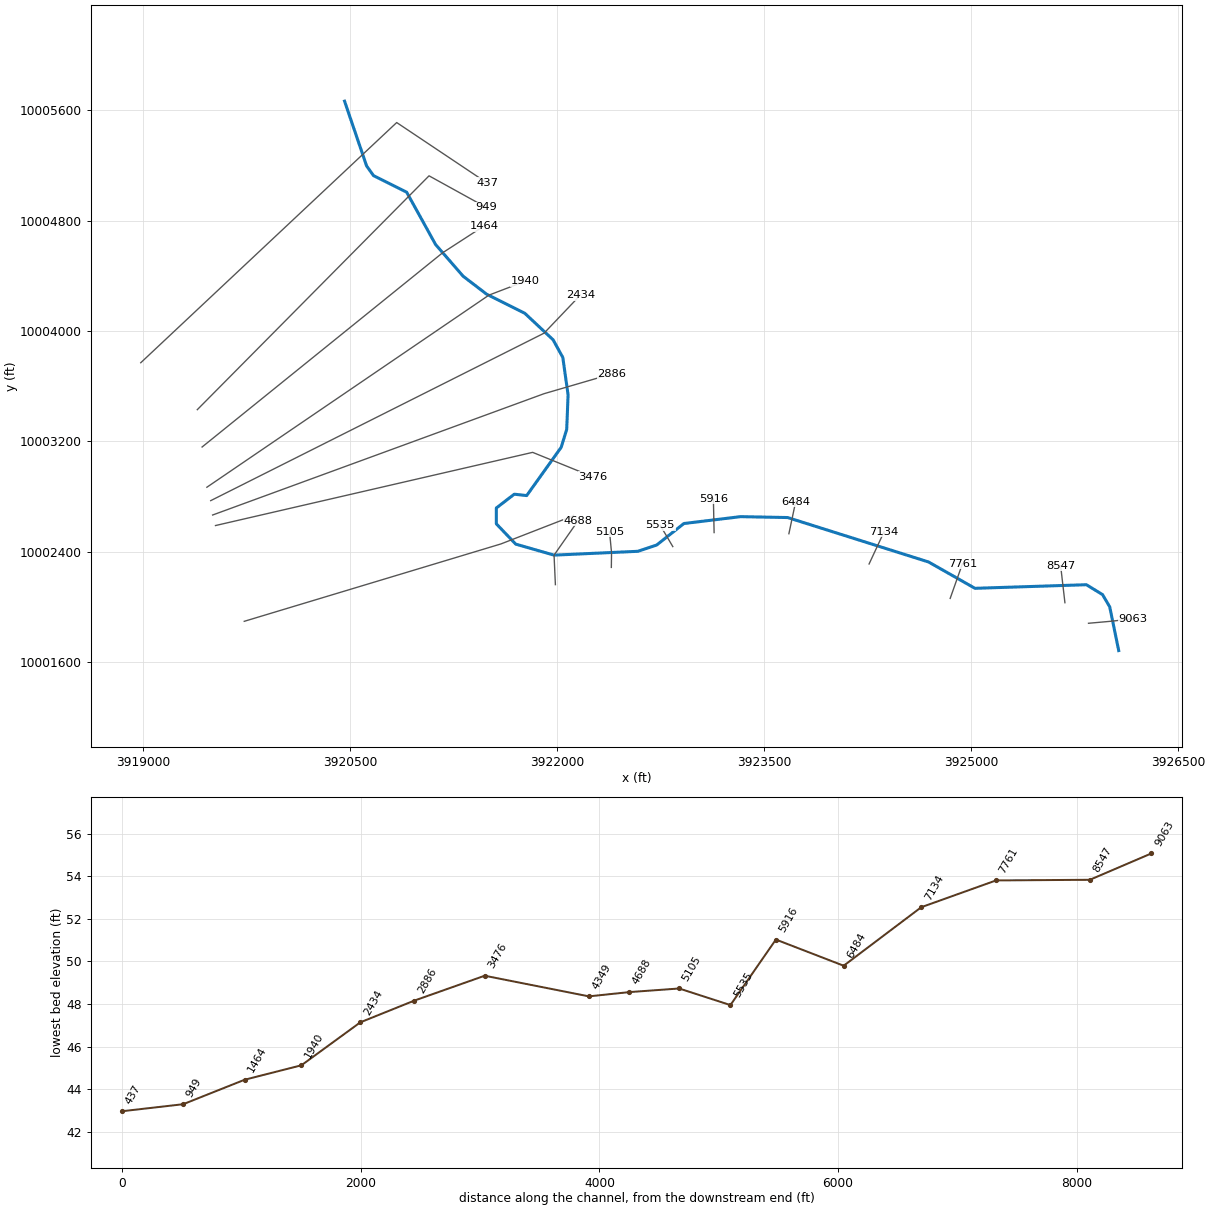
--- G103 37 02.prj (project) ---

Proj Title=G103 37 02 Base Level Engineering
Current Plan=p01
Default Exp/Contr=0.3,0.1
English Units
Geom File=g01
Flow File=f01
Flow File=f02
Plan File=p01
Y Axis Title=Elevation
X Axis Title(PF)=Main Channel Distance
X Axis Title(XS)=Station
BEGIN DESCRIPTION:
G103 37 02
END DESCRIPTION:
DSS Export Rating Curves= 0
DSS Export Rating Curve Sorted= 0
DSS Export Volume Flow Curves= 0
DXF OffsetX= 0
DXF OffsetY= 0
DXF ScaleX= 1
DXF ScaleY= 10

--- G103 37 02.p01 (plan) ---

Plan Title=Multiple Run
Program Version=4.10
Short Identifier=Multiple
Geom File=g01
Flow File=f01
Subcritical Flow
K Sum by GR= 0
Std Step Tol= 0.01
Critical Tol= 0.01
Num of Std Step Trials= 20
Max Error Tol= 0.3
Flow Tol Ratio= 0.001
Split Flow NTrial= 30
Split Flow Tol= 0.02
Split Flow Ratio= 0.02
Log Output Level= 0
Friction Slope Method= 1
Unsteady Friction Slope Method= 2
Unsteady Bridges Friction Slope Method= 1
Parabolic Critical Depth
Global Vel Dist= 1 , 1 , 1
Global Log Level= 0
CheckData=True
Encroach Param=-1 ,0,0, 0
BEGIN DESCRIPTION:
Multiple Run
END DESCRIPTION:
Computation Interval=1HOUR
Output Interval=1HOUR
Run HTab= 0
Run UNet= 0
Run PostProcess= 0
Run WQNet= 0
UNET Theta= 1
UNET Theta Warmup= 1
UNET ZTol= 0.02
UNET ZSATol= 0.05
UNET MxIter= 20
UNET MaxInSteps= 0
UNET DtIC= 0
UNET DtMin= 0
UNET MaxCRTS= 20
UNET WFStab= 2
UNET SFStab= 1
UNET WFX= 1
UNET SFX= 1
UNET DSS MLevel= 4
UNET DZMax Abort= 100
UNET Convert EG Bridges= 0
UNET Use Existing IB Tables=-1
UNET Froude Reduction=False
UNET Froude Limit= 1
UNET Froude Power= 10
UNET Time Slicing=0,0, 5
UNET Junction Losses=0
Instantaneous Interval=1HOUR
Write IC File= 0
Write IC File at Sim End=0
Echo Input=False
Echo Parameters=False
Echo Output=False
Write Detailed= 0
WQ AD Non Conservative
WQ ULTIMATE=-1
WQ Max Comp Step=1HOUR
WQ Output Interval=15MIN
WQ Output Selected Increments= 0
WQ Output face flow=0
WQ Output face velocity=0
WQ Output face area=0
WQ Output face dispersion=0
WQ Output cell volume=0
WQ Output cell surface area=0
WQ Output cell continuity=0
WQ Output cumulative cell continuity=0
WQ Output face conc=0
WQ Output face dconc_dx=0
WQ Output face courant=0
WQ Output face peclet=0
WQ Output face adv mass=0
WQ Output face disp mass=0
WQ Output cell mass=0
WQ Output cell source sink temp=0
WQ Output cell source sink nsm=0
WQ Output MaxMinRange=-1
WQ Daily Max Min Mean=-1
WQ Daily Range=0
WQ Daily Time=0
WQ Create Restart=0
WQ Fixed Restart=0
WQ System Summary=0
WQ Use Fixed Temperature=0
Sorting and Armoring Iterations= 10
XS Update Threshold= 0.02
Hydraulics Update Threshold= 0.02
Energy Slope Method= 1
Volume Change Method= 0
XS Weighting Method= 0
Number of US Weighted Cross Sections= 1
Number of DS Weighted Cross Sections= 1
Upstream XS Weight=0.25
Main XS Weight=0.5
Downstream XS Weight=0.25
Number of DS XS's Weighted with US Boundary= 1
Upstream Boundary Weight= 1
Weight of XSs Associated with US Boundary= 0
Number of US XS's Weighted with DS Boundary= 1
Downstream Boundary Weight= 0.5
Weight of XSs Associated with DS Boundary= 0.5
Sediment Output Level= 4
Mass or Volume Output= 0
Output Increment Type= 1
Profile and TS Output Increment= 10
XS Output Flag= 0
XS Output Increment= 10
Disregard all LS=0
Disregard all Conn=0
Disregard all Breaches=0
Disregard all Pumps=0

--- G103 37 02.f01 (steady flow) ---

Flow Title=Multiple
Program Version=4.10
Number of Profiles= 7
Profile Names=10-year,25-year,50-year,1pct_min,100-year,1pct_plu,500-year
River Rch & RM=G103 37 02,Reach-1         ,9063
     666     869    1144     495    1494    4512    2628
Boundary for River Rch & Prof#=G103 37 02,Reach-1         , 1
Up Type= 0
Dn Type= 3
Dn Slope=0.005
Boundary for River Rch & Prof#=G103 37 02,Reach-1         , 2
Up Type= 0
Dn Type= 3
Dn Slope=0.005
Boundary for River Rch & Prof#=G103 37 02,Reach-1         , 3
Up Type= 0
Dn Type= 3
Dn Slope=0.005
Boundary for River Rch & Prof#=G103 37 02,Reach-1         , 4
Up Type= 0
Dn Type= 3
Dn Slope=0.005
Boundary for River Rch & Prof#=G103 37 02,Reach-1         , 5
Up Type= 0
Dn Type= 3
Dn Slope=0.005
Boundary for River Rch & Prof#=G103 37 02,Reach-1         , 6
Up Type= 0
Dn Type= 3
Dn Slope=0.005
Boundary for River Rch & Prof#=G103 37 02,Reach-1         , 7
Up Type= 0
Dn Type= 3
Dn Slope=0.005
DSS Import GetInterval= 0
DSS Import GetPeak= 0
DSS Import FillOption= 0

--- G103 37 02.f02 (steady flow) ---

Flow Title=Orig_BLE_Flows
Program Version=4.10
Number of Profiles= 7
Profile Names=10-year,25-year,50-year,1pct_min,100-year,1pct_plu,500-year
River Rch & RM=G103 37 02,Reach-1         ,9063
     666     852     995     380    1149    3469    1528
Boundary for River Rch & Prof#=G103 37 02,Reach-1         , 1
Up Type= 0
Dn Type= 3
Dn Slope=0.005
Boundary for River Rch & Prof#=G103 37 02,Reach-1         , 2
Up Type= 0
Dn Type= 3
Dn Slope=0.005
Boundary for River Rch & Prof#=G103 37 02,Reach-1         , 3
Up Type= 0
Dn Type= 3
Dn Slope=0.005
Boundary for River Rch & Prof#=G103 37 02,Reach-1         , 4
Up Type= 0
Dn Type= 3
Dn Slope=0.005
Boundary for River Rch & Prof#=G103 37 02,Reach-1         , 5
Up Type= 0
Dn Type= 3
Dn Slope=0.005
Boundary for River Rch & Prof#=G103 37 02,Reach-1         , 6
Up Type= 0
Dn Type= 3
Dn Slope=0.005
Boundary for River Rch & Prof#=G103 37 02,Reach-1         , 7
Up Type= 0
Dn Type= 3
Dn Slope=0.005
DSS Import GetInterval= 0
DSS Import GetPeak= 0
DSS Import FillOption= 0

--- G103 37 02.g01 (geometry) ---

Geom Title=Existing Conditions
Program Version=4.10

River Reach=G103 37 02      ,Reach-1
Reach XY= 30
      3926068.66     10001683.03      3926003.56     10001999.87
      3925951.48     10002088.84      3925834.29     10002160.46
        3925027.     10002134.41      3924690.62     10002325.39
      3923669.25     10002647.56      3923328.54     10002654.07
      3922917.51     10002604.16       3922719.6     10002447.91
      3922584.18     10002402.77      3921976.54     10002374.99
      3921698.76     10002454.85      3921558.23     10002601.84
      3921558.23     10002716.84      3921688.23     10002816.84
      3921778.23     10002806.84      3922028.23     10003156.84
      3922068.23     10003286.84      3922078.23     10003536.84
      3922039.92     10003808.49      3921969.76     10003936.15
      3921765.04     10004128.22      3921488.23     10004266.84
      3921318.23     10004396.84      3921118.23     10004626.84
      3920908.23     10005006.84      3920668.23     10005126.84
      3920618.23     10005196.84      3920458.23     10005666.84

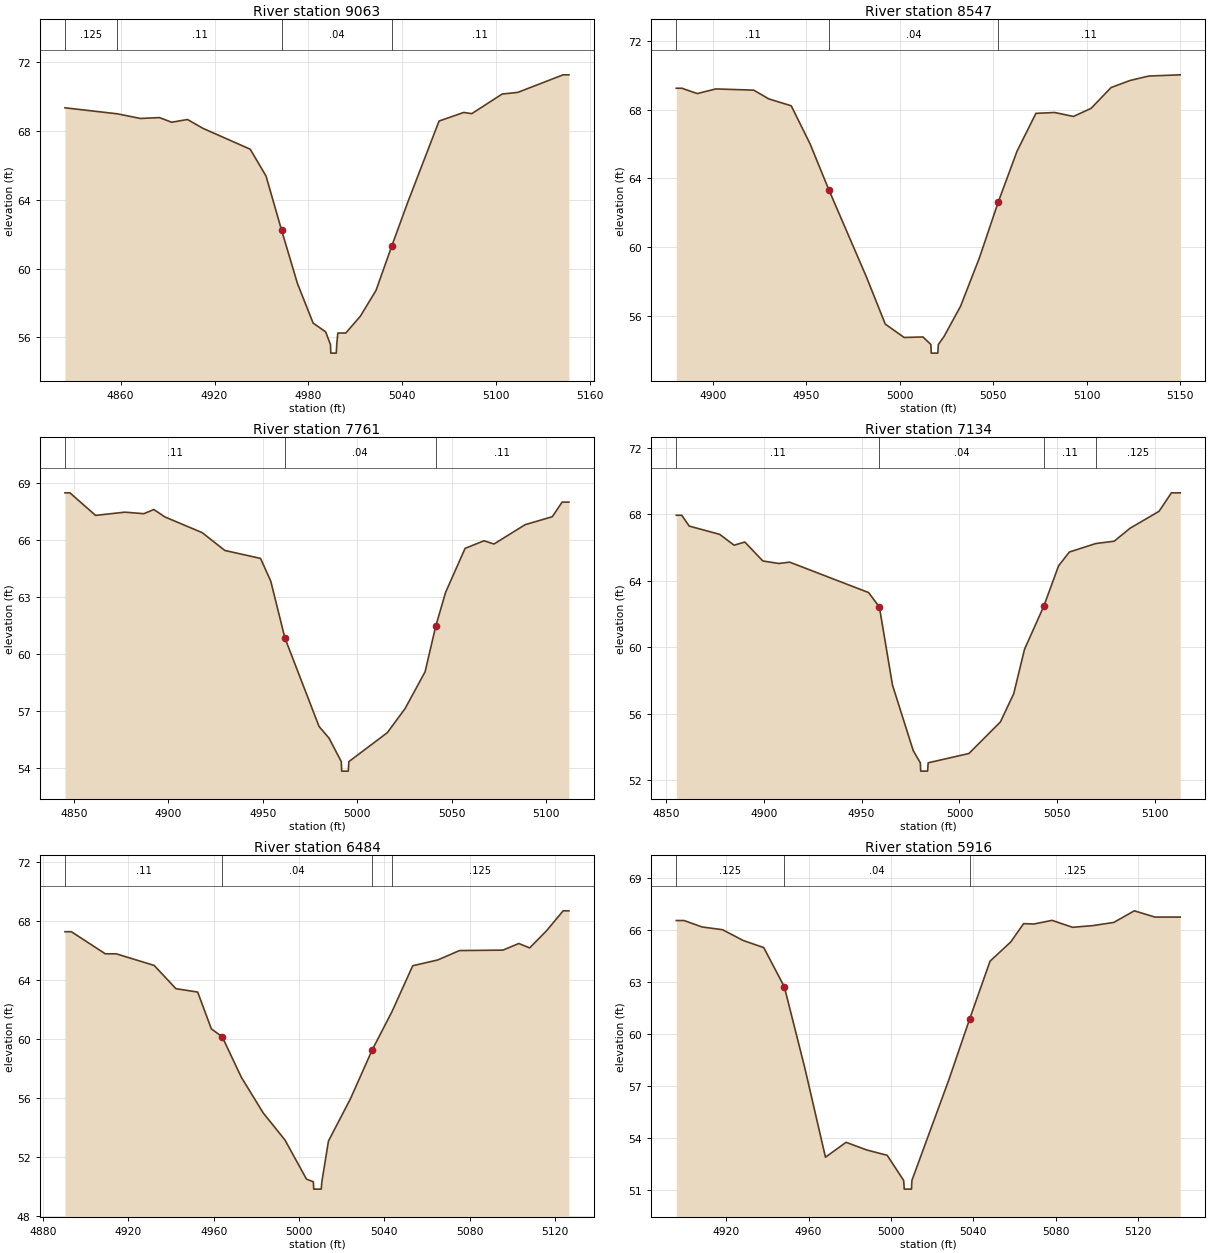
Type RM Length L Ch R = 1 ,9063    ,516,516,516
BEGIN DESCRIPTION:
G103-37-02 10.0
END DESCRIPTION:
XS GIS Cut Line= 3
      3925849.88     10001880.94      3926024.39     10001896.57
      3926170.25     10001913.93
#Sta/Elev= 30
  4824.4   69.36  4857.9   69.01  4872.6   68.74  4884.8   68.79  4892.6   68.52
  4902.7   68.68  4912.7   68.16  4942.8   66.95  4952.9   65.39  4962.9   62.22
    4973   59.13    4983   56.83    4991   56.32  4994.1   55.58  4994.3   55.08
  4997.8   55.08  4998.1   55.58  4998.8   56.25  5003.9   56.25  5013.2   57.23
  5023.2   58.73  5033.3   61.32  5043.4   63.84  5063.5   68.59  5079.3   69.09
  5084.4   69.02  5103.8   70.16  5113.9   70.26  5142.8   71.28  5146.5   71.28
#Mann= 4 ,-1 , 0
  4824.4    .125       0  4857.9     .11       0  4962.9     .04       0
  5033.3     .11       0
Bank Sta=4962.9,5033.3
XS Rating Curve= 0 ,0
Exp/Cntr=0.3,0.1

Type RM Length L Ch R = 1 ,8547    ,786,786,786
BEGIN DESCRIPTION:
Mapping XS 8648c615
END DESCRIPTION:
XS GIS Cut Line= 2
       3925678.9     10002029.99      3925647.85     10002297.79
#Sta/Elev= 30
  4880.4   69.24  4883.4   69.24  4891.6   68.93  4901.6    69.2  4921.8   69.13
  4929.9   68.62  4941.9   68.22    4952      66    4962   63.34  4982.2   58.25
  4992.2   55.53  5002.3   54.75  5012.4   54.78  5016.6   54.34  5016.8   53.84
  5020.3   53.84  5020.6   54.34  5023.6    54.8  5032.5   56.57  5042.6   59.39
  5052.6   62.61  5062.7   65.58  5072.8   67.78  5082.8   67.83  5092.9    67.6
  5102.3   68.07    5113   69.28  5123.1   69.69  5133.2   69.95    5150   70.02
#Mann= 3 , 0 , 0
  4880.4     .11       0    4962     .04       0  5052.6     .11       0
Bank Sta=4962,5052.6
XS Rating Curve= 0 ,0
Exp/Cntr=0.3,0.1

Type RM Length L Ch R = 1 ,7761    ,627,627,627
BEGIN DESCRIPTION:
Mapping XS 78c228c9
END DESCRIPTION:
XS GIS Cut Line= 2
       3924847.3     10002061.19      3924936.28     10002312.93
#Sta/Elev= 30
  4845.2   68.49  4847.8   68.49  4861.4    67.3  4876.9   67.47    4887   67.39
  4892.3   67.61  4898.1   67.22  4917.9   66.39  4929.9   65.45  4948.8   65.03
  4954.2   63.84  4961.7   60.84  4979.8   56.17  4985.1   55.55  4991.6   54.31
  4991.8   53.81  4995.3   53.81  4995.6   54.31    5016   55.84  5025.4   57.11
    5036   59.05  5041.6   61.44  5046.9   63.25  5057.2   65.56  5067.2   65.96
  5072.5   65.79    5089   66.81  5103.4   67.23  5108.6      68  5112.2      68
#Mann= 3 , 0 , 0
  4845.2     .11       0  4961.7     .04       0  5041.6     .11       0
Bank Sta=4961.7,5041.6
XS Rating Curve= 0 ,0
Exp/Cntr=0.3,0.1

Type RM Length L Ch R = 1 ,7134    ,650,650,650
BEGIN DESCRIPTION:
Mapping XS c68c77b8
END DESCRIPTION:
XS GIS Cut Line= 2
      3924259.63     10002310.99      3924368.14     10002544.29
#Sta/Elev= 30
  4855.4   67.94  4858.2   67.94    4862   67.29  4877.6   66.79  4884.9   66.14
  4890.4   66.33  4899.6   65.19  4907.8   65.04  4913.3   65.12  4953.6   63.29
  4959.1   62.42  4965.8   57.72  4976.4   53.78    4980   53.05  4980.2   52.55
  4983.7   52.55    4984   53.05  5004.8   53.61  5020.9   55.51  5027.7   57.21
  5033.2   59.88    5043   62.46  5050.6    64.9  5056.1   65.73  5069.6   66.24
    5079   66.38  5087.1   67.16  5101.9   68.18  5108.2   69.29  5112.7   69.29
#Mann= 4 ,-1 , 0
  4855.4     .11       0  4959.1     .04       0    5043     .11       0
  5069.6    .125       0
Bank Sta=4959.1,5043
XS Rating Curve= 0 ,0
Exp/Cntr=0.3,0.1

Type RM Length L Ch R = 1 ,6484    ,568,568,568
BEGIN DESCRIPTION:
Mapping XS 5c76d46b
END DESCRIPTION:
XS GIS Cut Line= 2
       3923678.4     10002530.19      3923727.23     10002761.29
#Sta/Elev= 30
  4890.3   67.29  4893.3   67.29  4909.2   65.79  4914.3   65.79  4932.1      65
  4942.3   63.42  4952.5   63.19  4958.9   60.69    4964   60.15    4973   57.39
  4983.2   54.98  4993.4   53.14  5003.5   50.48  5006.7    50.3  5006.9    49.8
  5010.4    49.8  5010.7    50.3  5013.8   53.07  5024.1   55.94  5034.3   59.26
  5043.5   61.84  5053.3   64.98    5065   65.37  5075.2   66.01  5095.6   66.04
    5103   66.49  5108.1   66.19  5116.1   67.37  5123.8   68.71  5126.5   68.71
#Mann= 4 ,-1 , 0
  4890.3     .11       0    4964     .04       0  5034.3     .11       0
  5043.5    .125       0
Bank Sta=4964,5034.3
XS Rating Curve= 0 ,0
Exp/Cntr=0.3,0.1

Type RM Length L Ch R = 1 ,5916    ,381,381,381
BEGIN DESCRIPTION:
Mapping XS cdaab46a
END DESCRIPTION:
XS GIS Cut Line= 2
      3923136.47     10002538.56      3923131.26     10002783.41
#Sta/Elev= 29
  4895.7   66.52  4899.5   66.52  4908.2   66.15  4918.2   65.99  4928.2   65.37
  4938.2   64.96  4948.2    62.7  4958.2      58  4968.2   52.87  4978.2   53.73
  4988.2   53.29  4998.2   52.98  5006.2   51.53  5006.5   51.03    5010   51.03
  5010.2   51.53  5028.2   57.35  5038.2   60.82  5048.2   64.18  5058.2   65.28
  5064.5   66.34  5069.5   66.32  5078.3   66.53  5088.3   66.13  5098.3   66.23
  5108.3   66.41  5118.3   67.08  5128.3   66.72  5140.6   66.72
#Mann= 3 , 0 , 0
  4895.7    .125       0  4948.2     .04       0  5038.2    .125       0
Bank Sta=4948.2,5038.2
XS Rating Curve= 0 ,0
Exp/Cntr=0.3,0.1

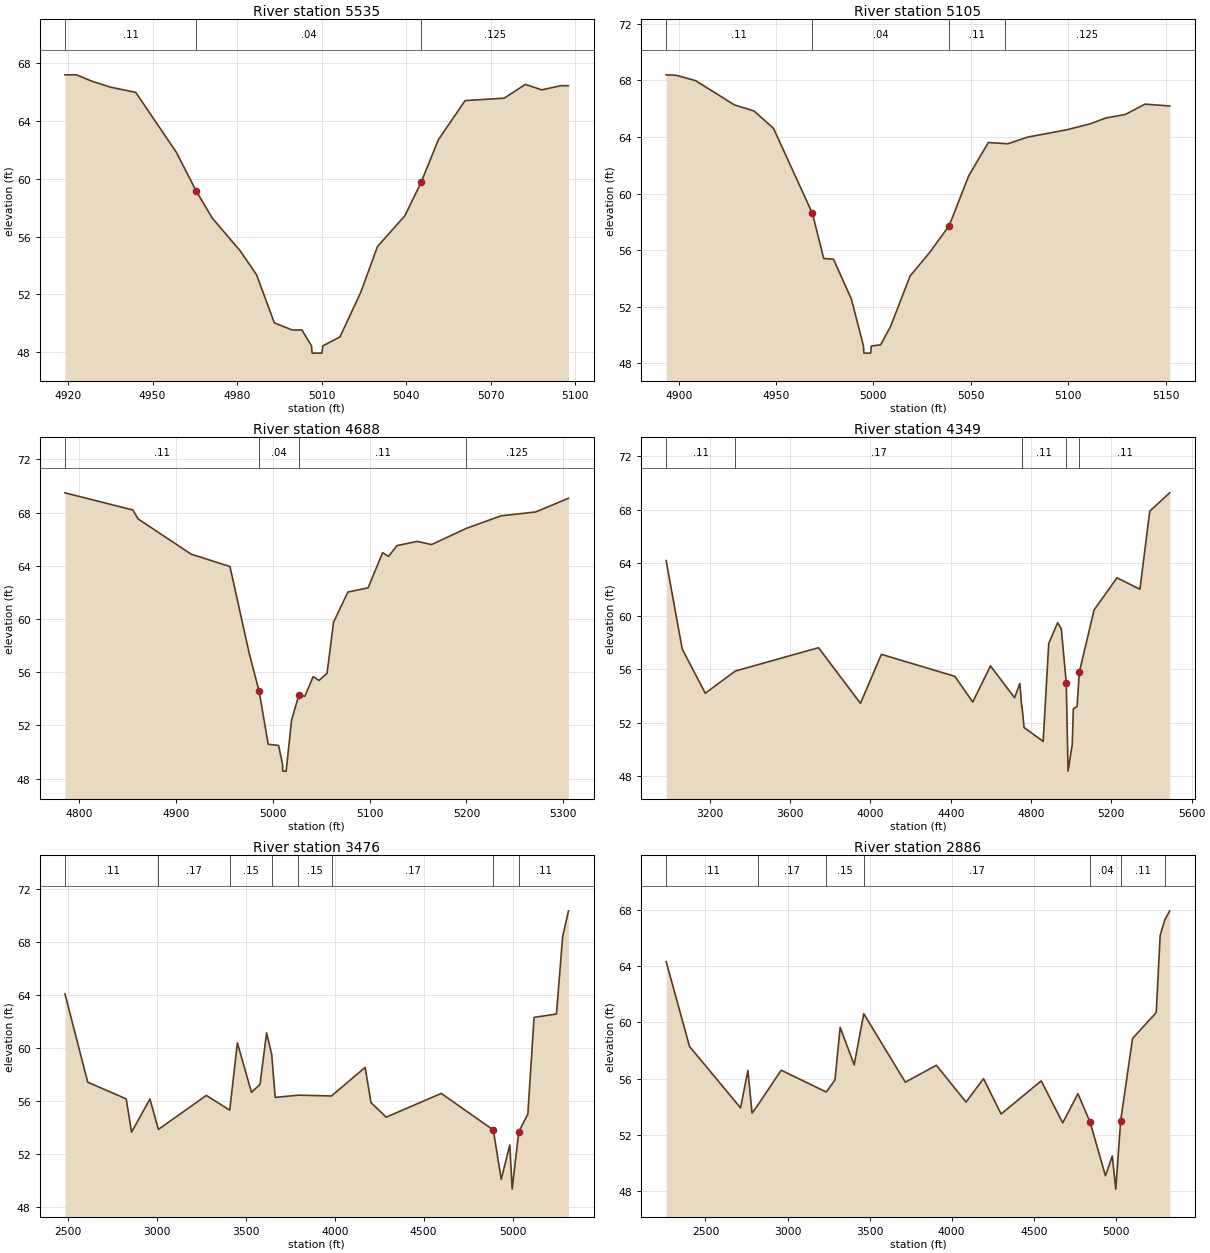
Type RM Length L Ch R = 1 ,5535    ,430,430,430
BEGIN DESCRIPTION:
G103-37-02 8.0
END DESCRIPTION:
XS GIS Cut Line= 3
      3922837.01     10002436.98      3922795.98     10002506.94
      3922745.84     10002590.67
#Sta/Elev= 29
  4918.9   67.17    4923   67.17  4928.3   66.74  4935.2   66.31    4944   65.96
  4958.4   61.83  4965.4   59.17  4971.2   57.27  4981.1   55.01  4986.9   53.36
  4993.2   50.04  4999.5   49.55    5003   49.55  5006.4   48.45  5006.6   47.95
  5010.1   47.95  5010.4   48.45  5016.5   49.07  5023.9   52.16  5029.8   55.31
  5039.5   57.43  5045.3   59.74  5051.4   62.68  5060.9   65.39  5074.8   65.56
  5082.3   66.51  5088.1   66.13  5094.9   66.42  5097.6   66.42
#Mann= 3 , 0 , 0
  4918.9     .11       0  4965.4     .04       0  5045.3    .125       0
Bank Sta=4965.4,5045.3
XS Rating Curve= 0 ,0
Exp/Cntr=0.3,0.1

Type RM Length L Ch R = 1 ,5105    ,417,417,417
BEGIN DESCRIPTION:
G103-37-02 7.0
END DESCRIPTION:
XS GIS Cut Line= 3
      3922391.68     10002285.96      3922393.21     10002392.35
      3922378.66     10002543.76
#Sta/Elev= 30
  4893.6   68.38  4898.7   68.35  4908.7   67.97  4928.7   66.25  4938.7   65.83
  4948.7    64.6  4968.7   58.59  4974.5   55.41  4979.5   55.36  4988.7   52.54
  4994.9   49.23  4995.1   48.73  4998.6   48.73  4998.9   49.23  5003.7   49.32
  5008.8   50.61  5018.8   54.17  5028.9   55.84  5038.9   57.73  5048.9   61.24
    5059    63.6  5067.3   63.53    5069   63.51  5079.1   63.98  5099.2    64.5
  5111.3   64.92  5119.3   65.33  5129.3   65.58  5139.4   66.31  5152.1   66.18
#Mann= 4 ,-1 , 0
  4893.6     .11       0  4968.7     .04       0  5038.9     .11       0
  5067.3    .125       0
Bank Sta=4968.7,5038.9
XS Rating Curve= 0 ,0
Exp/Cntr=0.3,0.1

Type RM Length L Ch R = 1 ,4688    ,339,339,339
BEGIN DESCRIPTION:
G103-37-02 6.0
END DESCRIPTION:
XS GIS Cut Line= 3
      3921986.29     10002161.01      3921976.54     10002374.99
      3922151.23     10002625.38
#Sta/Elev= 30
  4785.8   69.48  4855.9   68.19  4861.2   67.52    4916   64.87    4956   63.94
  4976.1   57.35  4986.1   54.56  4995.5   50.58  5006.2   50.49  5010.3   49.06
  5010.5   48.56    5014   48.56  5019.6    52.4  5027.1   54.28  5033.2   54.18
  5041.9   55.66    5048   55.38  5056.2   55.92  5062.9   59.76  5077.7   62.02
  5098.6   62.34  5113.5   64.98  5119.6    64.7  5128.3   65.51  5149.2   65.83
  5164.1   65.59  5199.6    66.8  5235.6   67.75  5271.4   68.04  5305.3   69.07
#Mann= 4 ,-1 , 0
  4785.8     .11       0  4986.1     .04       0  5027.1     .11       0
  5199.6    .125       0
Bank Sta=4986.1,5027.1
XS Rating Curve= 0 ,0
Exp/Cntr=0.5,0.3

Type RM Length L Ch R = 1 ,4349    ,873,873,873
BEGIN DESCRIPTION:
G103-37-02 5.0
END DESCRIPTION:
XS GIS Cut Line= 3
      3919731.38      10001895.1      3921591.33     10002456.11
      3922117.82     10002661.06
#Sta/Elev= 30
  2982.9   64.17  3062.8   57.53  3177.7   54.21    3328   55.88  3741.7   57.63
  3950.6   53.45  4054.8   57.13  4420.6   55.48  4509.7   53.55  4598.2   56.26
    4718   53.87  4744.4   54.95  4753.7   53.18    4755   53.21  4765.3   51.64
  4860.4   50.59  4888.2   57.95  4932.6   59.51  4950.9   59.03  4975.4   55.01
  4984.5   48.36  5005.3   50.36  5010.7   53.04  5029.2   53.21  5040.5   55.78
  5114.1   60.47  5228.2   62.88  5342.4   62.02  5391.4   67.89  5490.6   69.26
#Mann= 6 ,-1 , 0
  2982.9     .11       0    3328     .17       0  4753.7     .15       0
    4755     .11       0  4975.4     .04       0  5040.5     .11       0
Bank Sta=4975.4,5040.5
XS Rating Curve= 0 ,0
Exp/Cntr=0.3,0.1

Type RM Length L Ch R = 1 ,3476    ,590,590,590
BEGIN DESCRIPTION:
Mapping XS 8419ff7f
END DESCRIPTION:
XS GIS Cut Line= 3
      3919523.03     10002589.54      3921821.36     10003120.17
      3922259.73     10002942.22
#Sta/Elev= 30
  2482.7   64.08  2610.8   57.41  2827.2   56.15  2857.1   53.63  2960.6   56.14
    3008   53.84  3277.9   56.41  3409.3    55.3  3452.4   60.38  3531.7   56.64
  3579.6   57.24  3616.6   61.14  3645.3   59.52  3665.1   56.26  3794.7   56.43
  3981.7   56.37  4170.8   58.53  4203.8   55.87  4289.3   54.77  4598.9   56.56
  4891.7    53.8  4936.2   50.07  4984.4   52.67  4997.8   49.33 5034.7653.65568
  5085.9      55    5121   62.31  5246.8   62.56  5281.7   68.41  5314.6   70.36
#Mann= 8 ,-1 , 0
  2482.7     .11       0    3008     .17       0  3409.3     .15       0
  3645.3     .17       0  3794.7     .15       0  3981.7     .17       0
  4891.7     .04       0 5034.76     .11       0
Bank Sta=4891.7,5034.76
XS Rating Curve= 0 ,0
Exp/Cntr=0.3,0.1

Type RM Length L Ch R = 1 ,2886    ,452,452,452
BEGIN DESCRIPTION:
Mapping XS 9f9abbce
END DESCRIPTION:
XS GIS Cut Line= 3
      3919502.22     10002665.93      3921903.83     10003545.52
      3922393.56     10003688.53
#Sta/Elev= 30
  2260.7   64.31  2403.2   58.28    2714   53.93  2758.7   56.58  2783.9   53.55
  2821.9   54.17  2961.6    56.6  3236.2   55.05  3289.1   55.91    3321   59.64
  3406.2   56.98  3464.5   60.61  3717.7   55.75  3906.7   56.95  4087.7   54.34
  4194.3      56  4301.3   53.49  4545.7   55.84  4676.7   52.86  4769.4   54.93
  4843.3   52.92  4937.1   49.11  4978.8   50.51    5000   48.16    5030   53.03
  5102.1   58.85  5246.4   60.69  5270.5   66.18  5298.5   67.26  5328.5   67.91
#Mann= 7 ,-1 , 0
  2260.7     .11       0  2821.9     .17       0  3236.2     .15       0
  3464.5     .17       0  4843.3     .04       0    5030     .11       0
  5298.5    .125       0
Bank Sta=4843.3,5030
XS Rating Curve= 0 ,0
Exp/Cntr=0.3,0.1

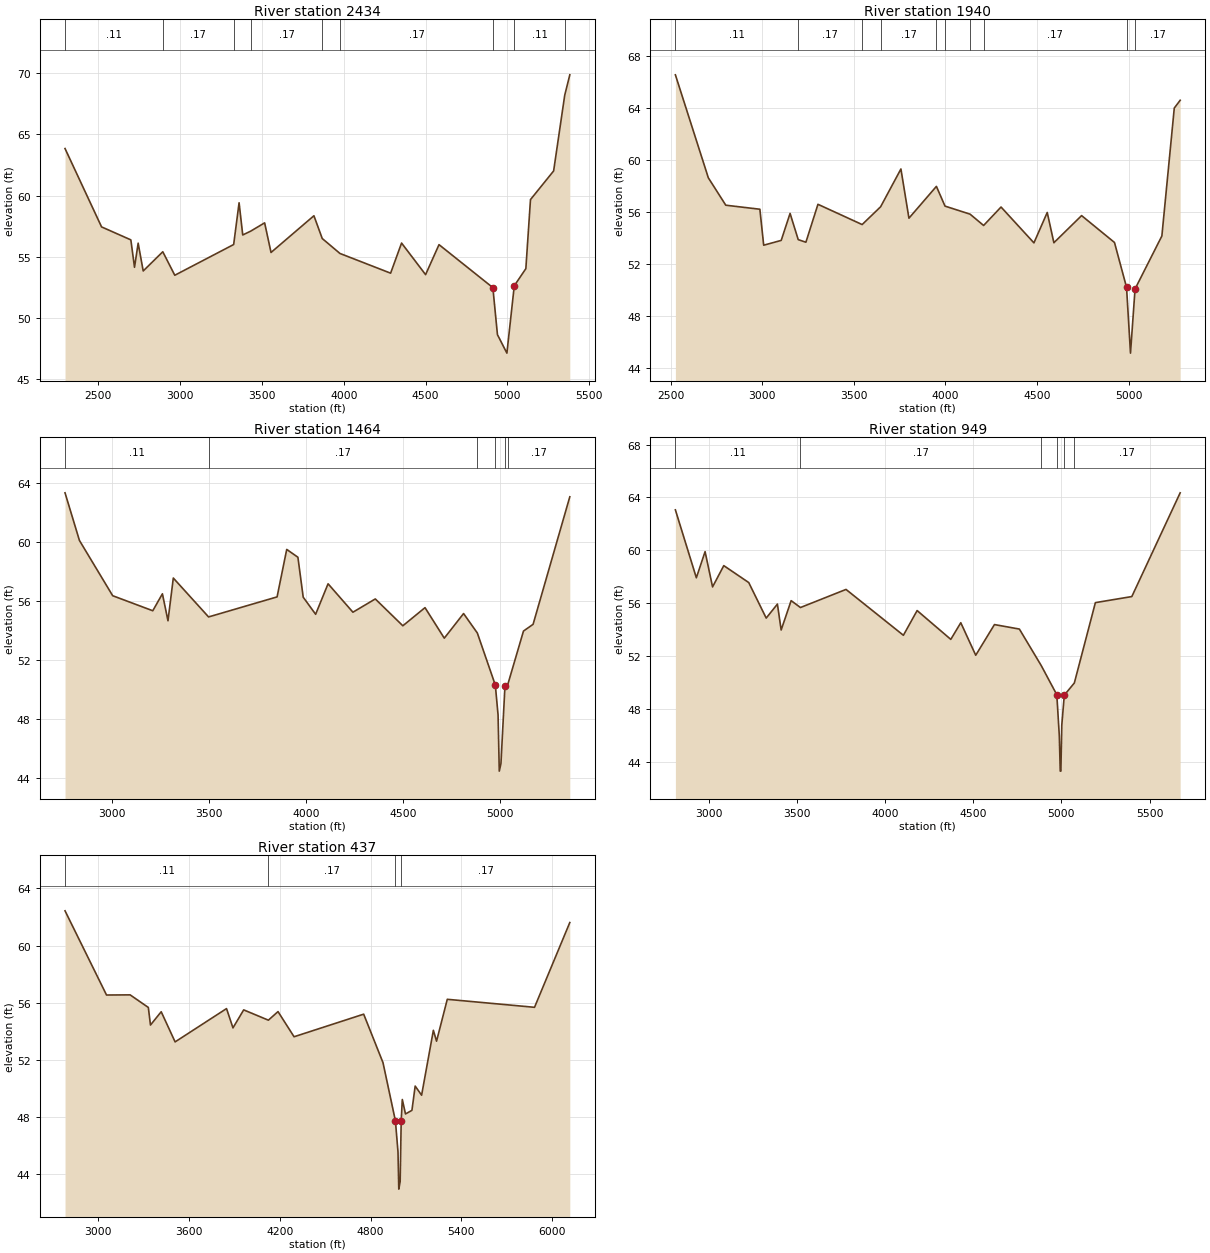
Type RM Length L Ch R = 1 ,2434    ,494,494,494
BEGIN DESCRIPTION:
G103-37-02 4.0
END DESCRIPTION:
XS GIS Cut Line= 3
      3919488.34      10002770.1       3921904.2     10003984.46
      3922167.83     10004261.05
#Sta/Elev= 30
  2296.1   63.85  2519.4   57.45  2698.5   56.39  2720.9   54.15  2743.2   56.12
  2774.1   53.85  2893.8   55.42  2967.1    53.5  3327.1   56.01  3360.2   59.42
  3382.5   56.79  3430.8    57.1  3516.4   57.78  3555.5   55.36  3817.7   58.36
  3868.6    56.5  3976.9   55.28  4286.6   53.67  4353.6   56.13  4500.4   53.55
  4582.5      56  4911.7   52.49  4939.7   48.65  4997.5   47.14  5042.6   52.64
  5113.4   54.04  5141.7   59.68  5283.2   62.02  5351.1   68.21  5382.1   69.87
#Mann= 9 ,-1 , 0
  2296.1     .11       0  2893.8     .17       0  3327.1     .15       0
  3430.8     .17       0  3868.6     .11       0  3976.9     .17       0
  4911.7     .04       0  5042.6     .11       0  5351.1    .125       0
Bank Sta=4911.7,5042.6
XS Rating Curve= 0 ,0
Exp/Cntr=0.3,0.1

Type RM Length L Ch R = 1 ,1940    ,476,476,476
BEGIN DESCRIPTION:
G103-37-02 3.0
END DESCRIPTION:
XS GIS Cut Line= 3
      3919460.55     10002867.31      3921504.71     10004260.36
       3921767.9     10004361.09
#Sta/Elev= 30
  2526.3   66.55  2706.1   58.62  2801.4   56.51  2987.4    56.2  3008.3   53.43
  3103.9    53.8  3152.3   55.88  3196.8   53.86  3238.7   53.66  3304.5   56.58
  3545.8   55.02  3646.6   56.39  3757.4    59.3  3801.2   55.51  3951.1   57.96
  3998.1   56.44    4135   55.82  4208.8   54.95  4303.9   56.37  4483.5   53.61
  4556.1   55.95  4592.4   53.62  4743.7   55.71  4923.2   53.64    4989   50.19
  5010.6   45.12  5035.5   50.06  5181.9   54.14  5249.6   63.99  5281.8   64.59
#Mann= 10 ,-1 , 0
  2526.3     .11       0  3196.8     .17       0  3545.8     .15       0
  3646.6     .17       0  3951.1     .11       0  3998.1     .17       0
    4135     .11       0  4208.8     .17       0    4989     .09       0
  5035.5     .17       0
Bank Sta=4989,5035.5
XS Rating Curve= 0 ,0
Exp/Cntr=0.3,0.1

Type RM Length L Ch R = 1 ,1464    ,515,515,515
BEGIN DESCRIPTION:
G103-37-02 2.0
END DESCRIPTION:
XS GIS Cut Line= 3
      3919425.83     10003158.98      3921168.23     10004566.84
      3921467.88     10004761.09
#Sta/Elev= 30
  2759.9   63.32    2834   60.09  3005.1   56.34  3211.4   55.32    3261   56.47
  3289.6   54.64    3317   57.54  3498.5    54.9    3851   56.26  3900.6   59.48
  3958.1   58.95  3985.4   56.24  4049.3   55.08  4113.3   57.15  4241.2   55.22
  4356.3   56.12  4498.1    54.3  4612.1   55.53  4711.3   53.46  4810.5   55.13
  4881.3   53.81  4973.8   50.28    4988   48.25  4994.2   44.44  5002.8   44.95
  5023.4    50.2  5037.6    50.3  5118.7   53.94  5168.2    54.4  5357.1   63.05
#Mann= 6 ,-1 , 0
  2759.9     .11       0  3498.5     .17       0  4881.3     .15       0
  4973.8     .09       0  5023.4     .15       0  5037.6     .17       0
Bank Sta=4973.8,5023.4
XS Rating Curve= 0 ,0
Exp/Cntr=0.3,0.1

Type RM Length L Ch R = 1 ,949     ,512,512,512
BEGIN DESCRIPTION:
Mapping XS b4dccbf6
END DESCRIPTION:
XS GIS Cut Line= 3
      3919391.13     10003429.83       3921070.5     10005125.38
      3921486.55     10004895.68
#Sta/Elev= 30
  2812.1   63.06  2930.9   57.92  2980.4    59.9  3022.8   57.23  3086.4   58.84
  3227.9   57.56  3326.9   54.87  3390.5   55.93  3411.7   53.97  3468.3   56.19
  3521.1   55.67  3779.4   57.04  4104.7   53.57  4182.5   55.44  4373.4   53.26
    4430   54.52  4514.8   52.06  4620.9   54.38  4762.3   54.04  4886.9   51.26
  4974.4   49.07  4988.6   45.97  4993.9   43.29  4997.4   43.29  5002.7   46.78
  5016.9   49.04  5073.8   49.96  5193.1   56.04  5399.7    56.5  5673.8   64.35
#Mann= 6 ,-1 , 0
  2812.1     .11       0  3521.1     .17       0  4886.9     .15       0
  4974.4     .09       0  5016.9     .15       0  5073.8     .17       0
Bank Sta=4974.4,5016.9
XS Rating Curve= 0 ,0
Exp/Cntr=0.3,0.1

Type RM Length L Ch R = 1 ,437     ,0,0,0
BEGIN DESCRIPTION:
G103-37-02 1.0
END DESCRIPTION:
XS GIS Cut Line= 3
      3918981.38     10003770.08      3920836.12     10005511.66
      3921491.49     10005073.31
#Sta/Elev= 30
  2783.1   62.43  3057.1   56.54  3212.9   56.55  3333.1   55.67  3347.3   54.44
  3418.1   55.37  3509.9   53.26  3849.4   55.59  3891.9   54.24  3962.7    55.5
  4125.7   54.78  4189.3   55.38  4295.3   53.62  4754.9    55.2  4882.4   51.81
 4964.3847.73993  4981.5   45.56  4986.7   42.96  4995.7   43.48  5002.6   47.75
  5009.9   49.23  5030.9   48.22  5073.4   48.47  5094.9   50.17  5137.3   49.53
    5215   54.07    5236   53.31  5306.9   56.24  5882.9   55.68  6115.8   61.61
#Mann= 4 ,-1 , 0
  2783.1     .11       0  4125.7     .17       0 4964.38     .09       0
  5002.6     .17       0
Bank Sta=4964.38,5002.6
XS Rating Curve= 0 ,0
Exp/Cntr=0.3,0.1

Chan Stop Cuts=-1
Use User Specified Reach Order=0
Composite Channel Slope=5