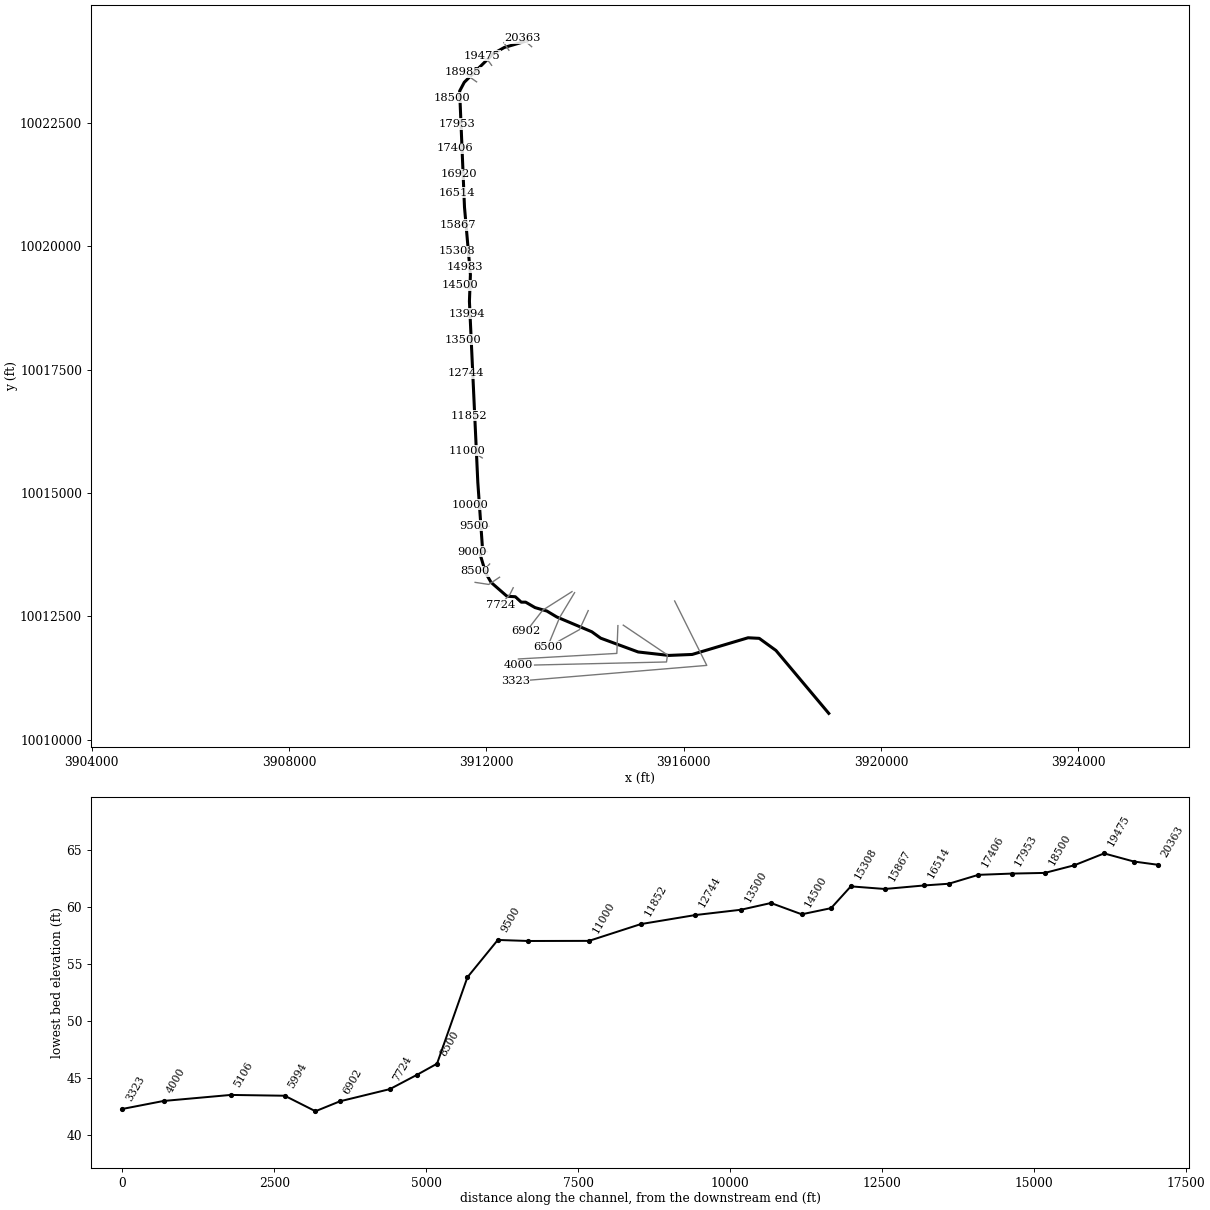
--- G103 38 00.prj (project) ---

Proj Title=G103 38 00 Base Level Engineering
Current Plan=p01
Default Exp/Contr=0.3,0.1
English Units
Geom File=g01
Flow File=f01
Flow File=f02
Plan File=p01
Y Axis Title=Elevation
X Axis Title(PF)=Main Channel Distance
X Axis Title(XS)=Station
BEGIN DESCRIPTION:
G103 38 00
END DESCRIPTION:
DSS Export Rating Curves= 0
DSS Export Rating Curve Sorted= 0
DSS Export Volume Flow Curves= 0
DXF OffsetX= 0
DXF OffsetY= 0
DXF ScaleX= 1
DXF ScaleY= 10

--- G103 38 00.p01 (plan) ---

Plan Title=Multiple Run
Program Version=4.10
Short Identifier=Multiple
Geom File=g01
Flow File=f01
Subcritical Flow
K Sum by GR= 0
Std Step Tol= 0.01
Critical Tol= 0.01
Num of Std Step Trials= 20
Max Error Tol= 0.3
Flow Tol Ratio= 0.001
Split Flow NTrial= 30
Split Flow Tol= 0.02
Split Flow Ratio= 0.02
Log Output Level= 0
Friction Slope Method= 1
Unsteady Friction Slope Method= 2
Unsteady Bridges Friction Slope Method= 1
Parabolic Critical Depth
Global Vel Dist= 1 , 1 , 1
Global Log Level= 0
CheckData=True
Encroach Param=-1 ,0,0, 0
BEGIN DESCRIPTION:
Multiple Run
END DESCRIPTION:
Computation Interval=1HOUR
Output Interval=1HOUR
Run HTab= 0
Run UNet= 0
Run PostProcess= 0
Run WQNet= 0
UNET Theta= 1
UNET Theta Warmup= 1
UNET ZTol= 0.02
UNET ZSATol= 0.05
UNET MxIter= 20
UNET MaxInSteps= 0
UNET DtIC= 0
UNET DtMin= 0
UNET MaxCRTS= 20
UNET WFStab= 2
UNET SFStab= 1
UNET WFX= 1
UNET SFX= 1
UNET DSS MLevel= 4
UNET DZMax Abort= 100
UNET Convert EG Bridges= 0
UNET Use Existing IB Tables=-1
UNET Froude Reduction=False
UNET Froude Limit= 1
UNET Froude Power= 10
UNET Time Slicing=0,0, 5
UNET Junction Losses=0
Instantaneous Interval=1HOUR
Write IC File= 0
Write IC File at Sim End=0
Echo Input=False
Echo Parameters=False
Echo Output=False
Write Detailed= 0
WQ AD Non Conservative
WQ ULTIMATE=-1
WQ Max Comp Step=1HOUR
WQ Output Interval=15MIN
WQ Output Selected Increments= 0
WQ Output face flow=0
WQ Output face velocity=0
WQ Output face area=0
WQ Output face dispersion=0
WQ Output cell volume=0
WQ Output cell surface area=0
WQ Output cell continuity=0
WQ Output cumulative cell continuity=0
WQ Output face conc=0
WQ Output face dconc_dx=0
WQ Output face courant=0
WQ Output face peclet=0
WQ Output face adv mass=0
WQ Output face disp mass=0
WQ Output cell mass=0
WQ Output cell source sink temp=0
WQ Output cell source sink nsm=0
WQ Output MaxMinRange=-1
WQ Daily Max Min Mean=-1
WQ Daily Range=0
WQ Daily Time=0
WQ Create Restart=0
WQ Fixed Restart=0
WQ System Summary=0
WQ Use Fixed Temperature=0
Sorting and Armoring Iterations= 10
XS Update Threshold= 0.02
Hydraulics Update Threshold= 0.02
Energy Slope Method= 1
Volume Change Method= 0
XS Weighting Method= 0
Number of US Weighted Cross Sections= 1
Number of DS Weighted Cross Sections= 1
Upstream XS Weight=0.25
Main XS Weight=0.5
Downstream XS Weight=0.25
Number of DS XS's Weighted with US Boundary= 1
Upstream Boundary Weight= 1
Weight of XSs Associated with US Boundary= 0
Number of US XS's Weighted with DS Boundary= 1
Downstream Boundary Weight= 0.5
Weight of XSs Associated with DS Boundary= 0.5
Sediment Output Level= 4
Mass or Volume Output= 0
Output Increment Type= 1
Profile and TS Output Increment= 10
XS Output Flag= 0
XS Output Increment= 10
Disregard all LS=0
Disregard all Conn=0
Disregard all Breaches=0
Disregard all Pumps=0

--- G103 38 00.f01 (steady flow) ---

Flow Title=Multiple
Program Version=4.10
Number of Profiles= 7
Profile Names=10-year,25-year,50-year,1pct_min,100-year,1pct_plu,500-year
River Rch & RM=G103 38 00,Reach-1         ,20363
      27      27      28      10      30      91      34
River Rch & RM=G103 38 00,Reach-1         ,18500
     289     350     437     179     541    1634     857
River Rch & RM=G103 38 00,Reach-1         ,14983
    1124    1497    1998     874    2638    7967    4750
River Rch & RM=G103 38 00,Reach-1         ,2005
    1162    1547    2065     902    2724    8226    4902
Boundary for River Rch & Prof#=G103 38 00,Reach-1         , 1
Up Type= 0
Dn Type= 3
Dn Slope=0.00047
Boundary for River Rch & Prof#=G103 38 00,Reach-1         , 2
Up Type= 0
Dn Type= 3
Dn Slope=0.00047
Boundary for River Rch & Prof#=G103 38 00,Reach-1         , 3
Up Type= 0
Dn Type= 3
Dn Slope=0.00047
Boundary for River Rch & Prof#=G103 38 00,Reach-1         , 4
Up Type= 0
Dn Type= 3
Dn Slope=0.00047
Boundary for River Rch & Prof#=G103 38 00,Reach-1         , 5
Up Type= 0
Dn Type= 3
Dn Slope=0.00047
Boundary for River Rch & Prof#=G103 38 00,Reach-1         , 6
Up Type= 0
Dn Type= 3
Dn Slope=0.00047
Boundary for River Rch & Prof#=G103 38 00,Reach-1         , 7
Up Type= 0
Dn Type= 3
Dn Slope=0.00047
DSS Import GetInterval= 0
DSS Import GetPeak= 0
DSS Import FillOption= 0

--- G103 38 00.f02 (steady flow) ---

Flow Title=Orig_BLE_Flows
Program Version=4.10
Number of Profiles= 7
Profile Names=10-year,25-year,50-year,1pct_min,100-year,1pct_plu,500-year
River Rch & RM=G103 38 00,Reach-1         ,20363
      27      26      24       8      23      69      20
River Rch & RM=G103 38 00,Reach-1         ,18500
     289     343     380     138     416    1258     498
River Rch & RM=G103 38 00,Reach-1         ,15000
    1141    1492    1768     684    2067    6242    2820
River Rch & RM=G103 38 00,Reach-1         ,2005
    1181    1545    1831     709    2140    6463    2918
Boundary for River Rch & Prof#=G103 38 00,Reach-1         , 1
Up Type= 0
Dn Type= 3
Dn Slope=0.00047
Boundary for River Rch & Prof#=G103 38 00,Reach-1         , 2
Up Type= 0
Dn Type= 3
Dn Slope=0.00047
Boundary for River Rch & Prof#=G103 38 00,Reach-1         , 3
Up Type= 0
Dn Type= 3
Dn Slope=0.00047
Boundary for River Rch & Prof#=G103 38 00,Reach-1         , 4
Up Type= 0
Dn Type= 3
Dn Slope=0.00047
Boundary for River Rch & Prof#=G103 38 00,Reach-1         , 5
Up Type= 0
Dn Type= 3
Dn Slope=0.00047
Boundary for River Rch & Prof#=G103 38 00,Reach-1         , 6
Up Type= 0
Dn Type= 3
Dn Slope=0.00047
Boundary for River Rch & Prof#=G103 38 00,Reach-1         , 7
Up Type= 0
Dn Type= 3
Dn Slope=0.00047
DSS Import GetInterval= 0
DSS Import GetPeak= 0
DSS Import FillOption= 0

--- G103 38 00.g01 (geometry) ---

Geom Title=Existing Conditions
Program Version=4.10

River Reach=G103 38 00      ,Reach-1
Reach XY= 30
      3912822.19     10024167.49      3912367.49     10024034.82
       3912145.1     10023911.07       3911553.9     10023328.02
       3911459.8     10023149.58      3911558.23     10020796.84
      3911678.23     10019426.84      3911658.23     10018886.84
      3911828.23     10015216.84      3911918.23     10013946.84
      3911918.23     10013826.84      3911878.23     10013746.84
      3911988.23     10013376.84      3912098.23     10013186.84
      3912418.23     10012906.84      3912588.23     10012896.84
      3912708.23     10012786.84      3912798.23     10012786.84
      3912988.23     10012676.84      3913228.23     10012606.84
      3913428.23     10012486.84      3914138.23     10012186.84
      3914318.23     10012056.84      3915078.23     10011776.84
      3915698.23     10011706.84      3916172.97      10011726.6
      3917305.78     10012064.89      3917531.98     10012053.24
      3917871.48     10011807.04      3918941.53     10010531.83

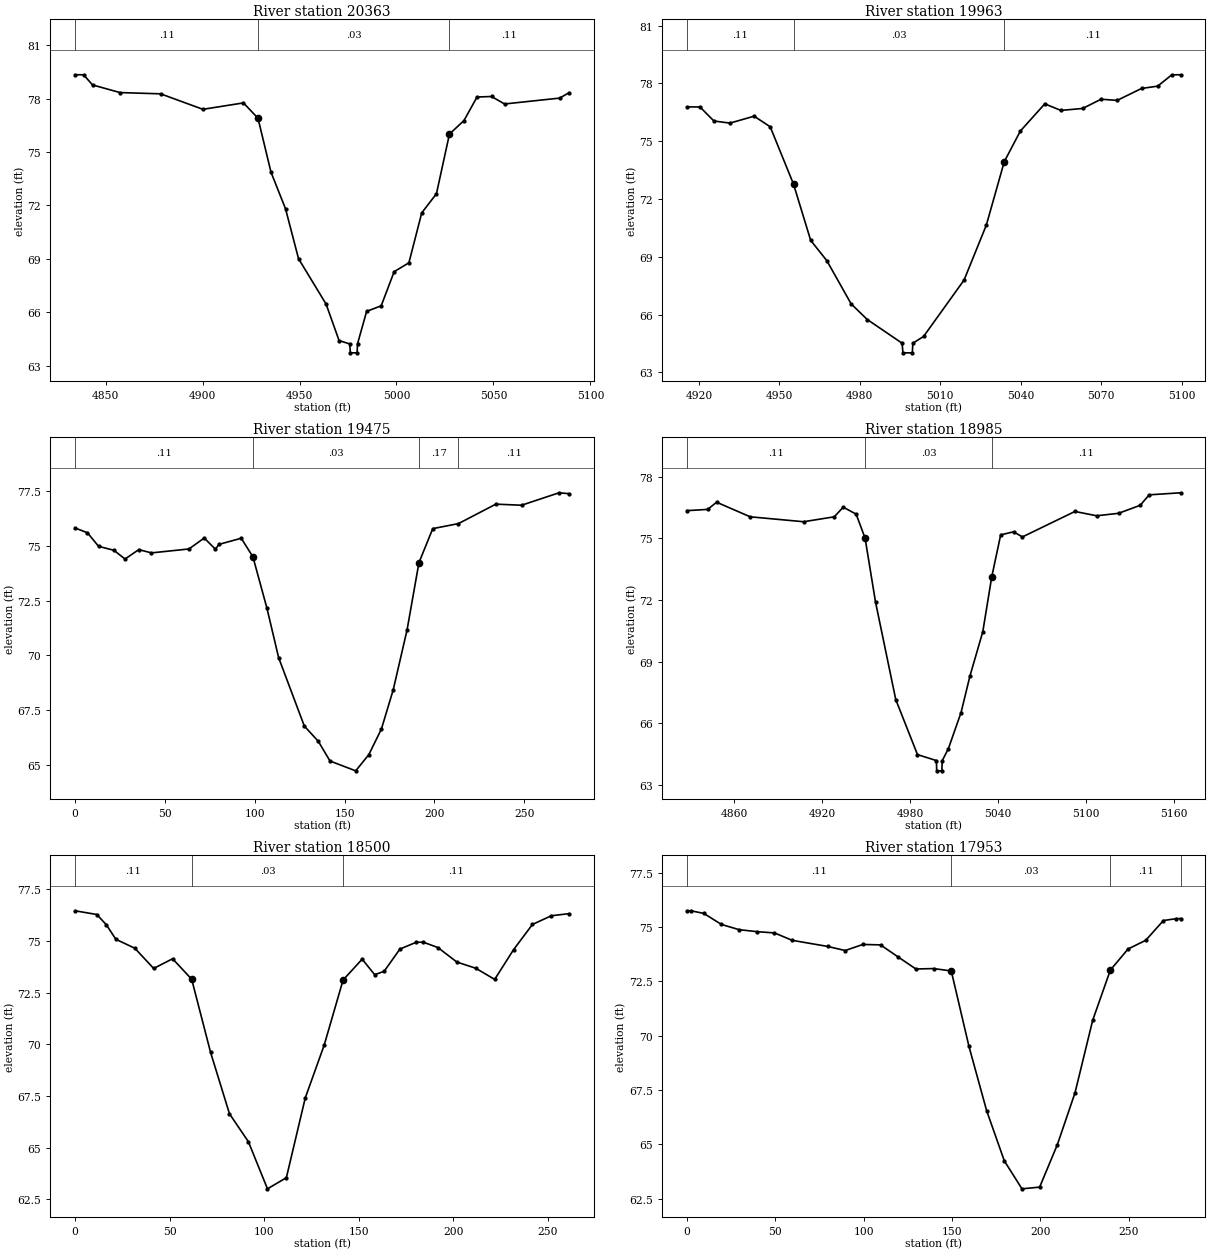
Type RM Length L Ch R = 1 ,20363   ,400,400,400
BEGIN DESCRIPTION:
Mapping XS 1081cedf
END DESCRIPTION:
XS GIS Cut Line= 2
      3912919.42     10024049.94      3912729.27     10024219.25
#Sta/Elev= 30
  4834.3   79.34  4838.7   79.34  4843.3   78.77  4857.5   78.34  4878.4   78.27
  4900.2    77.4  4921.1   77.76  4928.6    76.9  4935.3   73.87  4942.8   71.81
  4949.5   69.01  4963.7   66.46  4970.4   64.41  4975.9   64.22  4976.2   63.72
  4979.7   63.72  4979.9   64.22  4984.6   66.05  4992.1   66.36  4998.8   68.28
  5006.4   68.78    5013   71.58  5020.6   72.66  5027.3   76.01  5034.8   76.77
  5041.5   78.09    5049   78.12  5055.7    77.7  5084.1   78.03  5088.9   78.33
#Mann= 3 , 0 , 0
  4834.3     .11       0  4928.6     .03       0  5027.3     .11       0
Bank Sta=4928.6,5027.3
XS Rating Curve= 0 ,0
Exp/Cntr=0.3,0.1

Type RM Length L Ch R = 1 ,19963   ,488,488,488
BEGIN DESCRIPTION:
Mapping XS 4be0a44e
END DESCRIPTION:
XS GIS Cut Line= 2
      3912458.57      10023977.9        3912357.     10024131.56
#Sta/Elev= 29
  4915.5   76.78  4920.4   76.78  4925.6   76.05  4931.6   75.94  4940.6    76.3
  4946.6   75.75  4955.3   72.77  4961.7   69.85  4967.7    68.8  4976.8   66.55
  4982.8   65.74  4995.8   64.51  4996.1   64.01  4999.6   64.01  4999.8   64.51
  5003.8   64.86  5018.9   67.79  5027.2   70.64  5033.9   73.94  5039.9   75.53
    5049   76.94    5055    76.6  5063.1    76.7    5070   77.18    5076   77.12
  5085.1   77.74  5091.1   77.86  5096.4   78.45  5099.7   78.45
#Mann= 3 , 0 , 0
  4915.5     .11       0  4955.3     .03       0  5033.9     .11       0
Bank Sta=4955.3,5033.9
XS Rating Curve= 0 ,0
Exp/Cntr=0.3,0.1

Type RM Length L Ch R = 1 ,19475   ,490,490,490
BEGIN DESCRIPTION:
Mapping XS 0d932309
END DESCRIPTION:
XS GIS Cut Line= 3
      3912108.23     10023672.29      3912060.47     10023738.45
      3911912.66     10023863.15
#Sta/Elev= 30
       0   75.83     6.9   75.61    13.1   74.99    21.6   74.81    27.8   74.41
    35.5   74.84    42.5   74.69    63.4   74.87    71.9   75.37    78.1   74.86
    80.1   75.08    92.5   75.36      99   74.51   106.8   72.16   113.3    69.9
   127.6   66.77   135.4   66.07   141.9   65.17   156.2   64.72   163.5   65.46
   170.5   66.63   177.1   68.43   184.8   71.17   191.4   74.24   199.1    75.8
   213.4   76.03   234.2   76.92   248.5   76.87   269.4   77.44   274.9    77.4
#Mann= 4 ,-1 , 0
       0     .11       0      99     .03       0   191.4     .17       0
   213.4     .11       0
Bank Sta=99,191.4
XS Rating Curve= 0 ,0
Exp/Cntr=0.3,0.1

Type RM Length L Ch R = 1 ,18985   ,485,485,485
BEGIN DESCRIPTION:
Mapping XS 6d3da4ed
END DESCRIPTION:
XS GIS Cut Line= 2
      3911803.27     10023337.12      3911527.27      10023529.8
#Sta/Elev= 30
  4827.8   76.35    4842   76.41  4848.1   76.76    4871   76.05  4907.4   75.81
  4928.3   76.05  4934.4   76.52  4943.2   76.18  4949.3   75.01  4956.4    71.9
  4970.2   67.15    4985   64.47  4997.9   64.18  4998.1   63.68  5001.6   63.68
  5001.9   64.18    5006   64.75  5014.7   66.52  5020.8   68.31  5029.5   70.45
  5035.6   73.12  5041.7   75.17  5050.5   75.32  5056.5   75.07  5092.3   76.31
  5107.1    76.1    5122   76.22  5136.8   76.61  5142.9   77.12  5164.4   77.22
#Mann= 3 , 0 , 0
  4827.8     .11       0  4949.3     .03       0  5035.6     .11       0
Bank Sta=4949.3,5035.6
XS Rating Curve= 0 ,0
Exp/Cntr=0.3,0.1

Type RM Length L Ch R = 1 ,18500   ,547,547,547
BEGIN DESCRIPTION:
Mapping XS 49739639
END DESCRIPTION:
XS GIS Cut Line= 3
      3911559.36     10023027.21      3911375.46     10023014.38
      3911298.51     10023011.78
#Sta/Elev= 30
       0   76.46    11.5   76.28    16.5   75.79    21.6   75.08    31.6   74.65
    41.6   73.67    51.6   74.14    61.7   73.15    71.7   69.61    81.7   66.64
    91.7   65.29   101.8   63.01   111.8   63.55   121.8   67.41   131.8   69.96
   141.8   73.11   151.9   74.12   158.5   73.37   163.5   73.53   171.9   74.61
   180.6   74.94   184.3   74.94     192   74.68     202   73.98     212   73.68
     222   73.14     232   74.58     242    75.8     252   76.22   261.3   76.32
#Mann= 3 , 0 , 0
       0     .11       0    61.7     .03       0   141.8     .11       0
Bank Sta=61.7,141.8
XS Rating Curve= 0 ,0
Exp/Cntr=0.3,0.1

Type RM Length L Ch R = 1 ,17953   ,547,547,547
BEGIN DESCRIPTION:
Mapping XS 951523de
END DESCRIPTION:
XS GIS Cut Line= 2
      3911677.41     10022481.38      3911398.05     10022481.38
#Sta/Elev= 30
       0   75.75     2.3   75.75     9.6   75.63    19.6   75.12    29.6   74.88
    39.6   74.79    49.6   74.73    59.6   74.39    79.6   74.11    89.6   73.92
    99.6    74.2   109.6   74.18   119.6   73.62   129.6   73.07   139.6   73.09
   149.6   72.98   159.6   69.51   169.6   66.55   179.6   64.24   189.6   62.95
   199.6   63.03   209.6   64.98   219.6   67.37   229.6   70.71   239.6   73.02
   249.6   73.99   259.6   74.39   269.6    75.3     277   75.39   279.4   75.39
#Mann= 4 ,-1 , 0
       0     .11       0   149.6     .03       0   239.6     .11       0
   279.4    .125       0
Bank Sta=149.6,239.6
XS Rating Curve= 0 ,0
Exp/Cntr=0.3,0.1

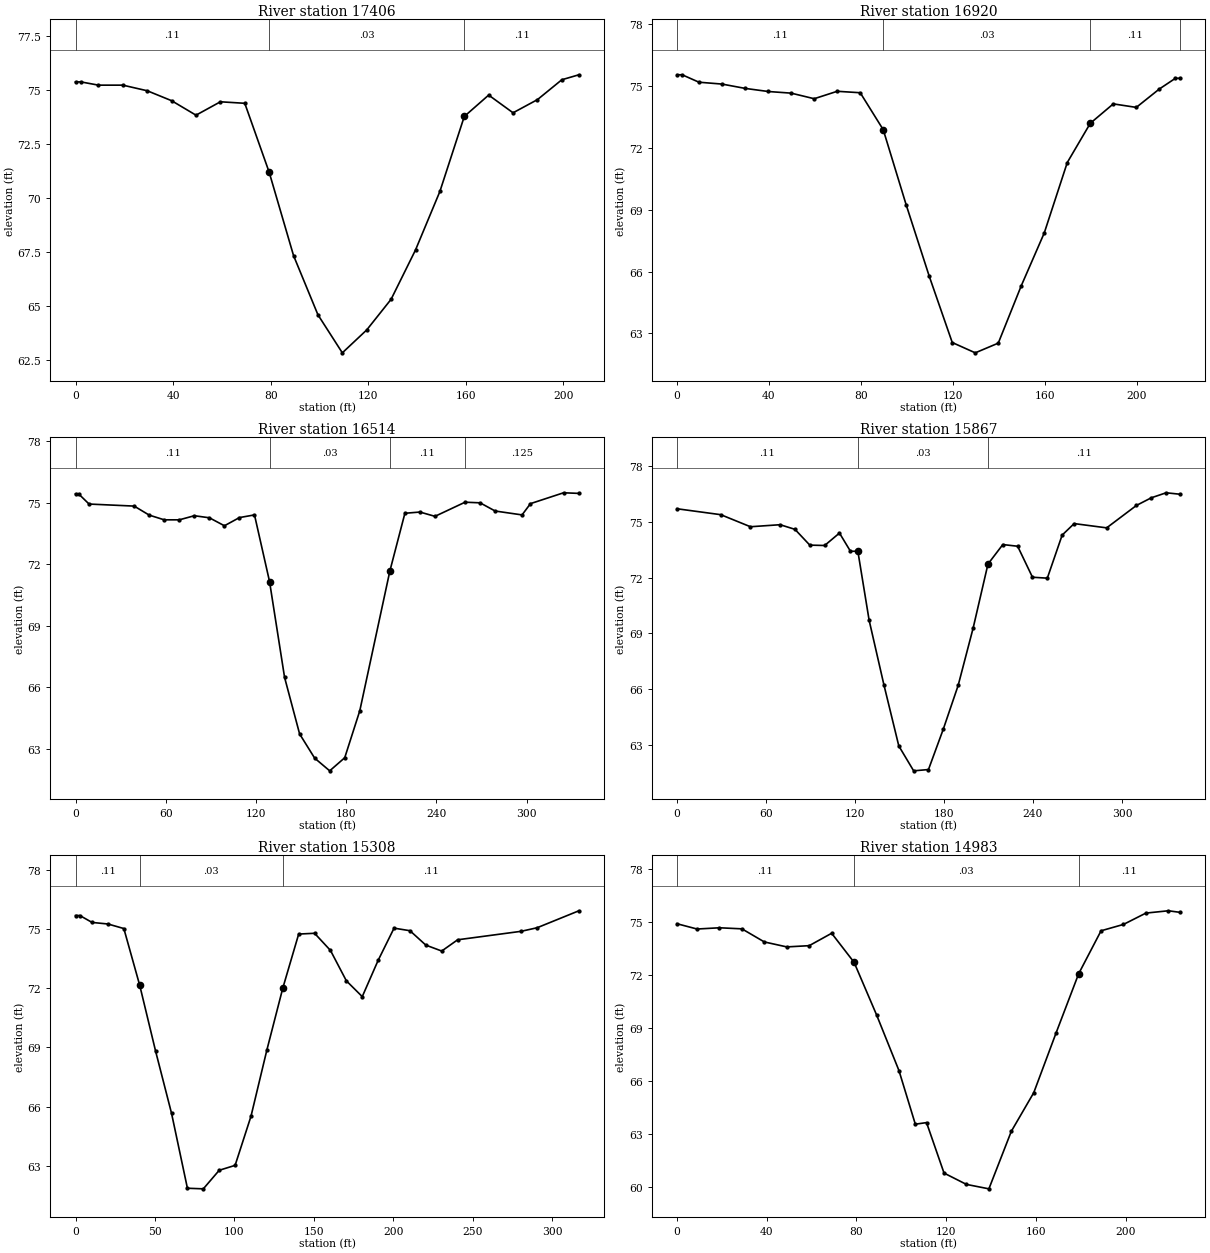
Type RM Length L Ch R = 1 ,17406   ,486,486,486
BEGIN DESCRIPTION:
Mapping XS beeea0fe
END DESCRIPTION:
XS GIS Cut Line= 2
      3911642.68     10022006.38      3911357.92     10021992.49
#Sta/Elev= 23
       0   75.38     2.2   75.38     9.4   75.23    19.4   75.23    29.4   74.97
    39.4   74.51    49.4   73.84    59.4   74.46    69.4   74.39    79.4    71.2
    89.4   67.34    99.4    64.6   109.4   62.84   119.4    63.9   129.4   65.32
   139.4    67.6   149.4   70.31   159.4   73.78   169.4   74.77   179.4   73.95
   189.4   74.56   199.4   75.48   206.4   75.71
#Mann= 3 , 0 , 0
       0     .11       0    79.4     .03       0   159.4     .11       0
Bank Sta=79.4,159.4
XS Rating Curve= 0 ,0
Exp/Cntr=0.3,0.1

Type RM Length L Ch R = 1 ,16920   ,406,406,406
BEGIN DESCRIPTION:
Mapping XS fd546173
END DESCRIPTION:
XS GIS Cut Line= 2
       3911667.5     10021471.07      3911448.75     10021466.91
#Sta/Elev= 25
       0   75.53     2.3   75.53     9.6   75.17    19.6   75.08    29.7   74.87
    39.7   74.72    49.7   74.64    59.7   74.37    69.7   74.73    79.7   74.66
    89.7   72.87    99.7   69.22   109.7   65.77   119.7   62.56   129.7   62.06
   139.7   62.53   149.7   65.31   159.7   67.87   169.7   71.28   179.7   73.18
   189.7   74.12   199.7   73.95   209.7   74.84   216.7   75.36   218.8   75.36
#Mann= 4 ,-1 , 0
       0     .11       0    89.7     .03       0   179.7     .11       0
   218.8    .125       0
Bank Sta=89.7,179.7
XS Rating Curve= 0 ,0
Exp/Cntr=0.3,0.1

Type RM Length L Ch R = 1 ,16514   ,647,647,647
BEGIN DESCRIPTION:
Mapping XS e5d15467
END DESCRIPTION:
XS GIS Cut Line= 3
      3911726.87     10021070.73      3911439.37     10021070.73
      3911397.71     10021092.95
#Sta/Elev= 30
       0   75.43       2   75.43       9   74.93      39   74.83      49   74.39
      59   74.16      69   74.16      79   74.36      89   74.26      99   73.87
     109   74.27     119    74.4     129   71.15     139   66.47     149   63.71
     159   62.53     169   61.91     179   62.55     189   64.84     209   71.66
     219   74.48     229   74.54     239   74.33     259   75.02     269   74.99
     279   74.59   296.9    74.4   302.5   74.95   324.5   75.48   334.7   75.45
#Mann= 4 ,-1 , 0
       0     .11       0     129     .03       0     209     .11       0
     259    .125       0
Bank Sta=129,209
XS Rating Curve= 0 ,0
Exp/Cntr=0.3,0.1

Type RM Length L Ch R = 1 ,15867   ,559,559,559
BEGIN DESCRIPTION:
Mapping XS b546a394
END DESCRIPTION:
XS GIS Cut Line= 3
      3911757.43     10020442.95      3911638.02      10020442.8
       3911418.3     10020433.03
#Sta/Elev= 30
       0   75.72    29.6    75.4    49.6   74.75    69.6   74.86    79.6   74.61
    89.6   73.76    99.6   73.74   109.6   74.41     117   73.43     122   73.43
   129.6   69.71   139.6   66.22   149.6   62.94   159.6    61.6   169.6   61.67
   179.6   63.85   189.6    66.2   199.7   69.29   209.7   72.74   219.7   73.79
   229.7    73.7   239.7   72.03   249.7   71.98   259.7    74.3   267.8   74.92
   289.7   74.69   309.8    75.9   319.8   76.31   329.8   76.58   339.3    76.5
#Mann= 3 , 0 , 0
       0     .11       0     122     .03       0   209.7     .11       0
Bank Sta=122,209.7
XS Rating Curve= 0 ,0
Exp/Cntr=0.3,0.1

Type RM Length L Ch R = 1 ,15308   ,325,325,325
BEGIN DESCRIPTION:
Mapping XS 512d2a0d
END DESCRIPTION:
XS GIS Cut Line= 2
      3911718.21     10019901.91      3911400.22     10019904.19
#Sta/Elev= 29
       0   75.68     2.7   75.68    10.4   75.33    20.4   75.25    30.4   75.02
    40.4   72.14    50.4    68.8    60.4   65.66    70.4   61.86    80.4   61.83
    90.4   62.77   100.4   63.02   110.4   65.51   120.4   68.87   130.4      72
   140.4   74.74   150.4   74.78   160.4   73.91   170.4   72.37   180.4   71.57
   190.4   73.41   200.4   75.04   210.4   74.91   220.4   74.18   230.4   73.88
   240.4   74.45   280.4   74.88   290.4   75.06   316.7   75.92
#Mann= 3 , 0 , 0
       0     .11       0    40.4     .03       0   130.4     .11       0
Bank Sta=40.4,130.4
XS Rating Curve= 0 ,0
Exp/Cntr=0.3,0.1

Type RM Length L Ch R = 1 ,14983   ,483,483,483
BEGIN DESCRIPTION:
G103-38-00 30.0
END DESCRIPTION:
XS GIS Cut Line= 2
      3911786.83     10019589.94      3911562.36     10019581.94
#Sta/Elev= 25
       0   74.89       9   74.59      19   74.66      29    74.6      39   73.86
      49   73.58      59   73.65      69   74.35      79   72.71      89   69.75
      99    66.6   106.3   63.57   111.3   63.66   119.1   60.81   129.1   60.17
   139.1   59.92   149.1   63.17   159.1   65.35   169.1   68.74   179.1   72.06
   189.1   74.49   199.1   74.85   209.1   75.49   219.1   75.62   224.4   75.53
#Mann= 3 , 0 , 0
       0     .11       0      79     .03       0   179.1     .11       0
Bank Sta=79,179.1
XS Rating Curve= 0 ,0
Exp/Cntr=0.3,0.1

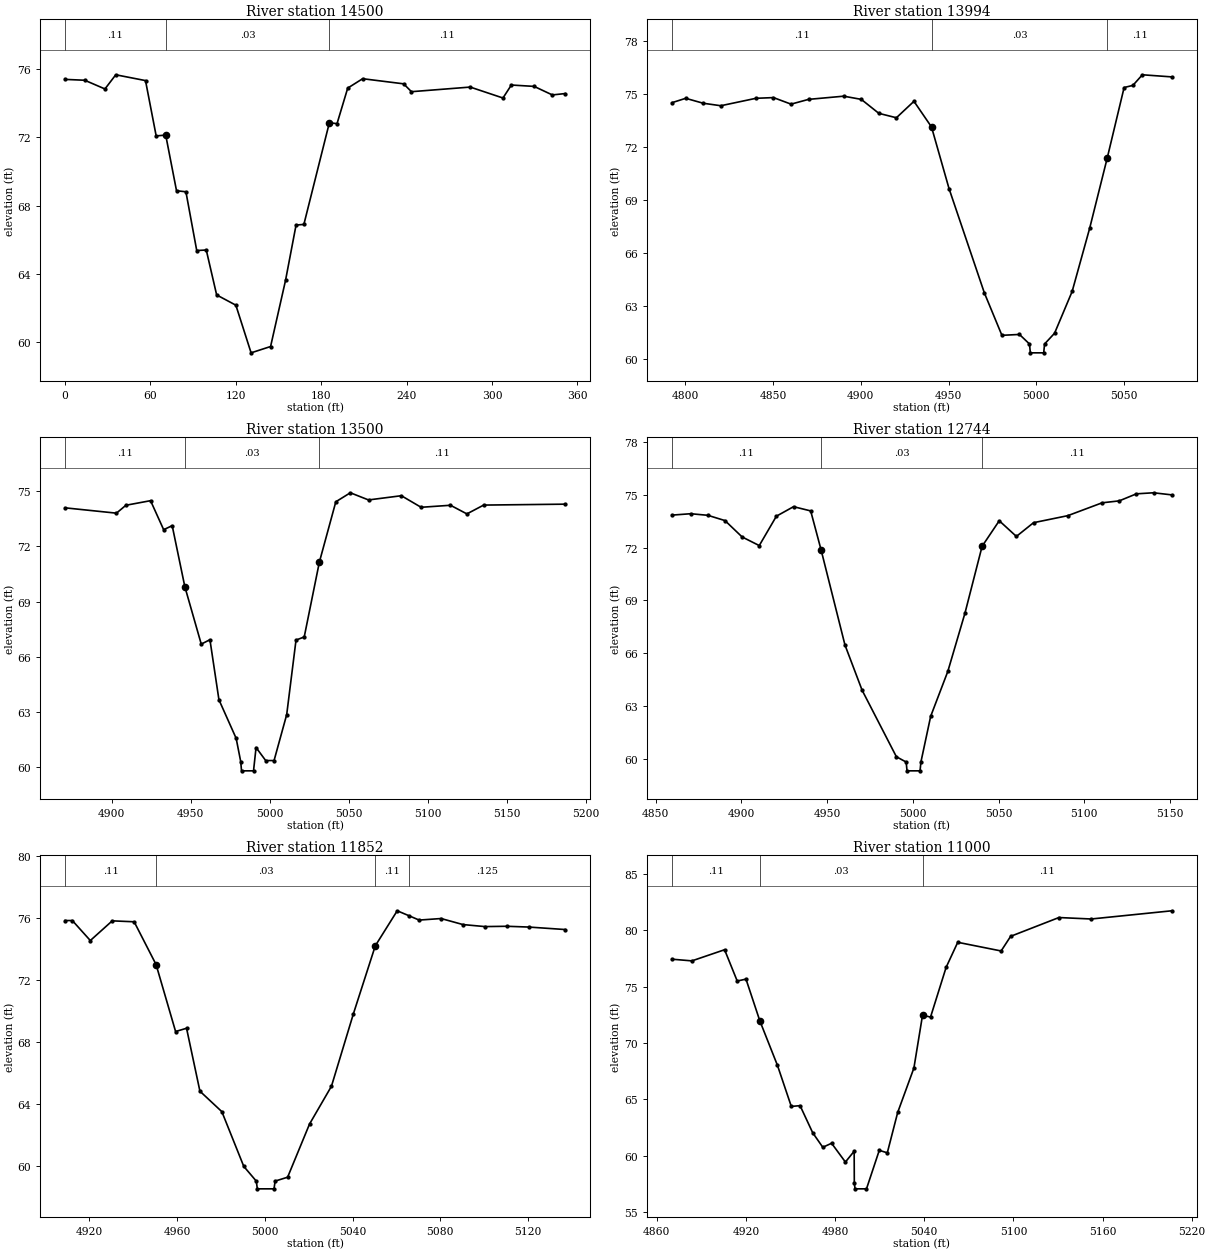
Type RM Length L Ch R = 1 ,14500   ,506,506,506
BEGIN DESCRIPTION:
G103-38-00 29.0
END DESCRIPTION:
XS GIS Cut Line= 3
      3911767.85     10019211.07      3911668.23     10019123.44
      3911467.85     10019211.07
#Sta/Elev= 30
       0   75.39    13.8   75.34      28   74.83    35.6   75.66    56.5   75.32
      64   72.08    70.7   72.13    78.3   68.87    84.9   68.81    92.5   65.37
    99.2    65.4   106.5   62.77     120   62.17   130.7   59.38   144.4   59.75
   154.9   63.62   162.3   66.86   167.8    66.9   185.7   72.85   191.1    72.8
   198.6   74.88   209.1   75.43   237.9   75.13   243.4   74.67   284.7   74.94
   307.7    74.3   313.6   75.06   329.6   74.98   342.4   74.48   351.4   74.56
#Mann= 3 , 0 , 0
       0     .11       0    70.7     .03       0   185.7     .11       0
Bank Sta=70.7,185.7
XS Rating Curve= 0 ,0
Exp/Cntr=0.3,0.1

Type RM Length L Ch R = 1 ,13994   ,494,494,494
BEGIN DESCRIPTION:
Mapping XS 697f025d
END DESCRIPTION:
XS GIS Cut Line= 2
       3911885.7     10018645.27      3911601.08     10018635.28
#Sta/Elev= 30
  4792.4   74.51  4800.3   74.76  4810.3   74.48  4820.3   74.34  4840.3   74.76
  4850.3    74.8  4860.3   74.43  4870.3    74.7  4890.3   74.88  4900.3    74.7
  4910.3   73.91  4920.3   73.66  4930.3   74.59  4940.3   73.14  4950.3   69.65
  4970.4   63.76  4980.4   61.36  4990.4   61.41  4996.1   60.87  4996.6   60.37
  5004.2   60.37  5004.7   60.87  5010.4   61.48  5020.4   63.84  5030.4   67.42
  5040.4   71.39    5050   75.37    5055   75.49  5060.4   76.09  5077.2   75.97
#Mann= 3 , 0 , 0
  4792.4     .11       0  4940.3     .03       0  5040.4     .11       0
Bank Sta=4940.3,5040.4
XS Rating Curve= 0 ,0
Exp/Cntr=0.3,0.1

Type RM Length L Ch R = 1 ,13500   ,756,756,756
BEGIN DESCRIPTION:
G103-38-00 27.0
END DESCRIPTION:
XS GIS Cut Line= 3
      3911817.84     10018111.08      3911698.23     10018160.72
      3911517.84     10018111.07
#Sta/Elev= 30
  4870.5    74.1    4903   73.81    4909   74.24  4924.6   74.49  4932.9   72.91
  4938.3   73.13  4946.3   69.81  4956.7   66.68  4962.2   66.92  4967.9   63.65
  4978.8   61.55  4981.7   60.28  4982.2   59.78  4989.8   59.78  4991.4   61.05
  4997.5   60.34  5002.8   60.34  5010.8   62.84  5016.7    66.9  5021.9   67.07
  5031.5   71.15  5041.9   74.43  5051.1   74.92  5062.6   74.53  5083.4   74.76
  5095.9   74.13  5114.5   74.24  5124.9   73.77  5135.5   74.25  5187.1    74.3
#Mann= 3 , 0 , 0
  4870.5     .11       0  4946.3     .03       0  5031.5     .11       0
Bank Sta=4946.3,5031.5
XS Rating Curve= 0 ,0
Exp/Cntr=0.3,0.1

Type RM Length L Ch R = 1 ,12744   ,892,892,892
BEGIN DESCRIPTION:
Mapping XS 793855ad
END DESCRIPTION:
XS GIS Cut Line= 2
      3911878.83     10017429.99      3911587.13     10017429.99
#Sta/Elev= 30
  4859.4   73.84  4870.4   73.92  4880.4   73.83  4890.4   73.53  4900.4    72.6
  4910.4   72.11  4920.4   73.78  4930.4   74.32  4940.4   74.08 4946.48   71.86
  4960.4   66.46  4970.4   63.89  4990.4   60.11  4996.1   59.81  4996.6   59.31
  5004.2   59.31  5004.7   59.81  5010.4   62.41  5020.4   64.96  5030.4   68.27
  5040.4   72.07  5050.4   73.52  5060.4   72.63  5070.4   73.41  5090.4   73.81
  5110.4   74.54  5120.4   74.65  5130.4   75.05  5140.4   75.11  5151.1   74.99
#Mann= 3 , 0 , 0
  4859.4     .11       0 4946.48     .03       0  5040.4     .11       0
Bank Sta=4946.48,5040.4
XS Rating Curve= 0 ,0
Exp/Cntr=0.3,0.1

Type RM Length L Ch R = 1 ,11852   ,852,852,852
BEGIN DESCRIPTION:
Mapping XS bf8bdb99
END DESCRIPTION:
XS GIS Cut Line= 2
      3911879.32      10016565.2      3911651.25     10016568.86
#Sta/Elev= 29
  4908.9   75.83  4912.2   75.83  4920.4   74.54  4930.4   75.81  4940.4   75.75
  4950.4   72.99  4959.3   68.67  4964.3   68.88  4970.4   64.82  4980.4    63.5
  4990.4   59.97  4996.1   59.02  4996.6   58.52  5004.2   58.52  5004.7   59.02
  5010.4   59.27  5020.4    62.7  5030.4   65.14  5040.4   69.81  5050.4    74.2
  5060.4   76.46  5065.6   76.15  5070.4   75.86  5080.4   75.96  5090.4   75.57
  5100.4   75.44  5110.4   75.46  5120.4   75.41    5137   75.25
#Mann= 4 ,-1 , 0
  4908.9     .11       0  4950.4     .03       0  5050.4     .11       0
  5065.6    .125       0
Bank Sta=4950.4,5050.4
XS Rating Curve= 0 ,0
Exp/Cntr=0.3,0.1

Type RM Length L Ch R = 1 ,11000   ,1000,1000,1000
BEGIN DESCRIPTION:
G103-38-00 22.0
END DESCRIPTION:
XS GIS Cut Line= 3
      3911917.82     10015711.09      3911808.23     10015780.84
      3911617.85     10015861.07
#Sta/Elev= 30
  4870.1   77.45  4883.6    77.3  4905.6   78.29  4914.1   75.51    4920   75.68
  4929.3   71.98  4941.2   68.01  4950.5   64.37  4956.4   64.44  4964.9   62.03
  4971.7   60.74  4977.6    61.1  4986.9   59.43  4992.8   60.39  4992.9   57.55
  4993.4   57.05  5001.1   57.05  5009.7   60.47  5015.1   60.25  5022.1   63.84
    5033   67.78  5038.8   72.47  5044.2   72.31  5054.7   76.73  5062.5   78.95
  5091.7   78.18  5098.1   79.48  5130.6   81.15  5152.3   81.02  5206.6   81.75
#Mann= 3 , 0 , 0
  4870.1     .11       0  4929.3     .03       0  5038.8     .11       0
Bank Sta=4929.3,5038.8
XS Rating Curve= 0 ,0
Exp/Cntr=0.3,0.1

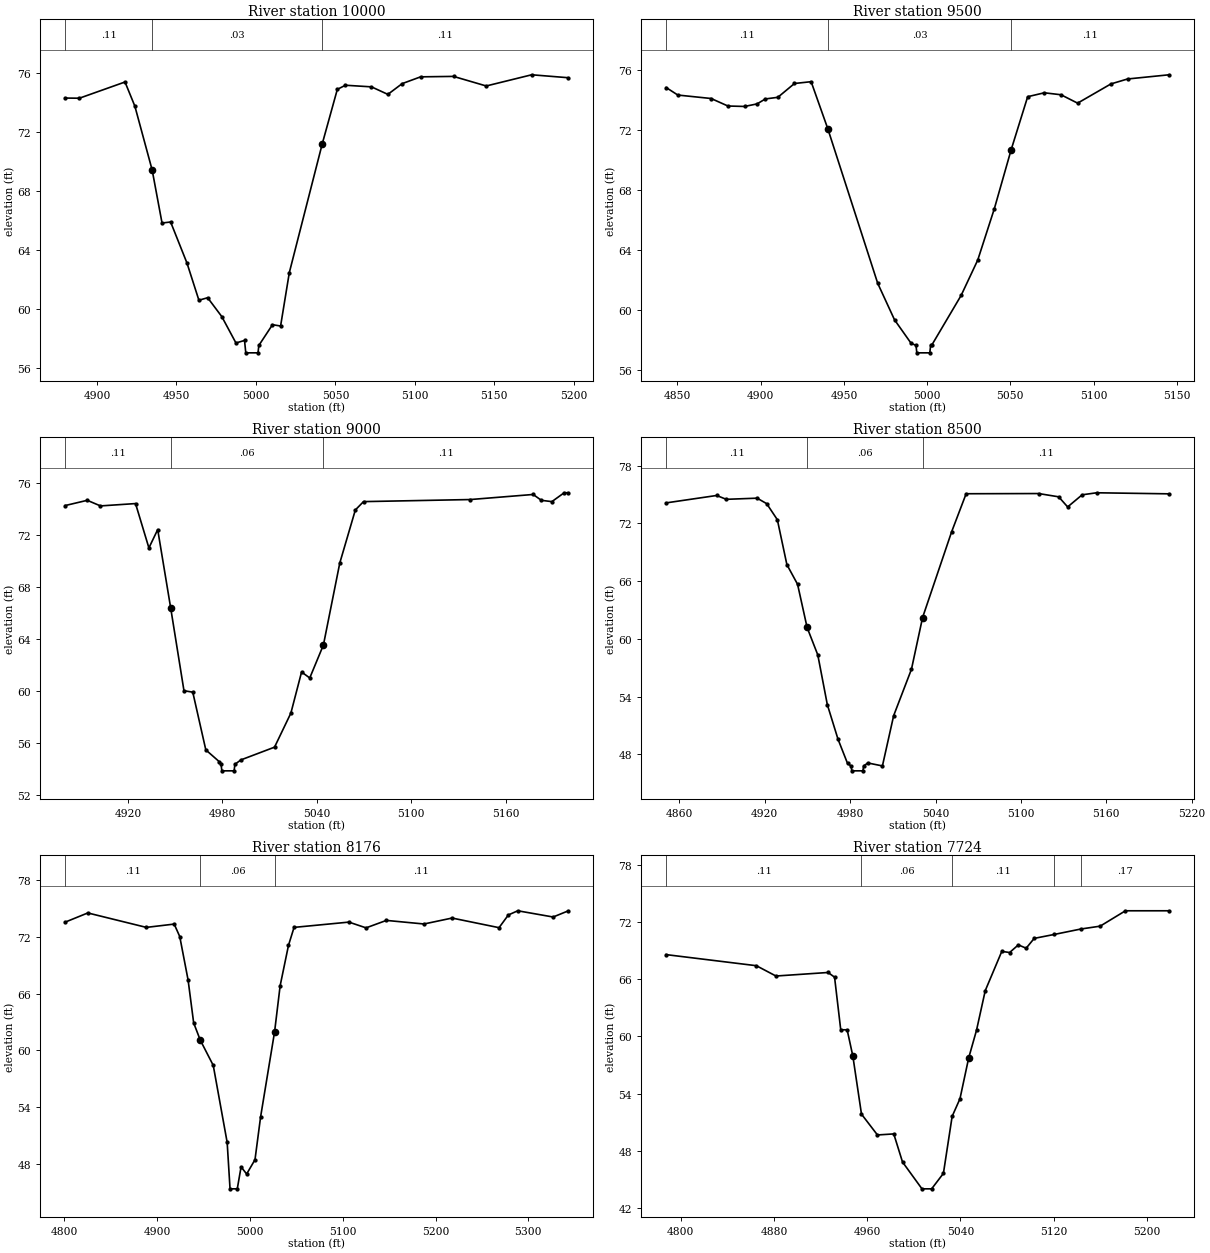
Type RM Length L Ch R = 1 ,10000   ,500,500,500
BEGIN DESCRIPTION:
G103-38-00 20.0
END DESCRIPTION:
XS GIS Cut Line= 3
      3911967.87     10014761.06      3911858.23     10014809.83
      3911667.87     10014761.08
#Sta/Elev= 30
    4880   74.33  4888.9   74.32  4917.6   75.42  4923.8   73.78  4934.7   69.44
  4940.9   65.85  4946.3   65.92  4956.6   63.13  4964.1   60.61  4969.6   60.78
  4978.5    59.5  4987.4   57.71  4992.8   57.88  4993.6   57.04  5001.3   57.04
  5001.8   57.54  5010.4   58.95  5015.5   58.86    5021   62.49  5041.7   71.22
  5051.2   74.92  5056.3    75.2  5072.7   75.09    5083   74.58    5092   75.31
  5103.6   75.77  5124.3    75.8  5144.9   75.15  5173.5   75.91  5196.5   75.71
#Mann= 3 , 0 , 0
    4880     .11       0  4934.7     .03       0  5041.7     .11       0
Bank Sta=4934.7,5041.7
XS Rating Curve= 0 ,0
Exp/Cntr=0.3,0.1

Type RM Length L Ch R = 1 ,9500    ,500,500,500
BEGIN DESCRIPTION:
G103-38-00 19.0
END DESCRIPTION:
XS GIS Cut Line= 3
      3912044.87     10014323.51      3911888.23     10014330.54
      3911742.87     10014333.93
#Sta/Elev= 30
  4843.2    74.8  4850.2    74.3  4870.2   74.07  4880.3   73.57  4890.3   73.54
  4897.8   73.71  4902.8   74.04  4910.3   74.15  4920.3   75.07  4930.3   75.19
  4940.3   72.06  4970.3   61.76  4980.4   59.33  4990.4   57.76  4993.3   57.63
  4993.8   57.13  5001.6   57.13  5002.1   57.63  5002.7   57.63  5020.4   60.95
  5030.4   63.31  5040.4   66.74  5050.4   70.63  5060.4   74.19  5070.4   74.45
  5080.4   74.32  5090.4   73.76  5110.4   75.04  5120.4   75.37  5145.4   75.65
#Mann= 3 , 0 , 0
  4843.2     .11       0  4940.3     .03       0  5050.4     .11       0
Bank Sta=4940.3,5050.4
XS Rating Curve= 0 ,0
Exp/Cntr=0.3,0.1

Type RM Length L Ch R = 1 ,9000    ,500,500,500
BEGIN DESCRIPTION:
G103-38-00 18.0
END DESCRIPTION:
XS GIS Cut Line= 3
      3912017.86     10013811.07      3911910.47     10013864.61
      3911717.87     10013811.08
#Sta/Elev= 30
    4880   74.26    4894   74.66  4902.4   74.23  4924.7   74.41  4933.2      71
  4938.8   72.41  4947.1   66.35  4955.5   60.02  4961.1   59.91  4969.4   55.47
  4977.9   54.57  4979.1   54.36  4979.6   53.86  4987.4   53.86  4987.9   54.36
  4991.7    54.7  5013.1   55.68  5023.5    58.3  5030.3   61.46  5035.5      61
  5044.2   63.54  5054.6   69.84  5064.5   73.92  5069.7   74.56  5137.6   74.72
  5177.6   75.11  5182.8   74.66  5189.5   74.56  5197.3   75.24  5199.9   75.24
#Mann= 3 , 0 , 0
    4880     .11       0  4947.1     .06       0  5044.2     .11       0
Bank Sta=4947.1,5044.2
XS Rating Curve= 0 ,0
Exp/Cntr=0.3,0.1

Type RM Length L Ch R = 1 ,8500    ,324,324,324
BEGIN DESCRIPTION:
G103-38-00 17.0
END DESCRIPTION:
XS GIS Cut Line= 3
      3912067.83     10013561.05      3911968.23     10013449.96
      3911767.87     10013411.07
#Sta/Elev= 30
  4850.8   74.13  4886.3    74.9    4893    74.5  4914.7   74.62  4921.4   74.05
  4928.9   72.38  4935.6   67.71  4943.1   65.67  4949.8   61.18  4957.3   58.33
    4964   53.16  4971.5   49.57  4978.2   47.05  4980.7   46.78  4981.2   46.28
    4989   46.28  4989.5   46.78  4992.4    47.1  5002.7   46.79  5010.6   52.02
  5023.1   56.84  5030.9   62.21  5051.3   71.12  5061.5   75.08  5112.4    75.1
  5126.5   74.76  5132.8   73.71    5143   74.97  5153.2   75.18  5204.1   75.07
#Mann= 3 , 0 , 0
  4850.8     .11       0  4949.8     .06       0  5030.9     .11       0
Bank Sta=4949.8,5030.9
XS Rating Curve= 0 ,0
Exp/Cntr=0.3,0.1

Type RM Length L Ch R = 1 ,8176    ,452,452,452
BEGIN DESCRIPTION:
G103-38-00 16.0
END DESCRIPTION:
XS GIS Cut Line= 3
      3912268.89     10013292.29       3912050.1     10013146.43
      3911774.08     10013188.09
#Sta/Elev= 30
  4800.9   73.58  4825.2   74.55  4888.3   73.02  4918.3   73.37  4924.3   72.05
  4933.3   67.44  4939.3    62.9  4946.4   61.08  4960.4    58.4  4975.4   50.24
  4978.5   45.32  4986.3   45.32  4990.4   47.65  4996.4   46.89  5005.4   48.41
  5011.4   52.92  5026.5   61.95  5032.5   66.84  5041.5   71.12  5047.5   73.02
  5106.6   73.58  5125.1   72.97    5147   73.76  5187.5   73.38  5217.8   74.01
  5268.4   72.99  5278.5   74.34  5288.6   74.78  5326.7   74.12    5343   74.77
#Mann= 3 , 0 , 0
  4800.9     .11       0  4946.4     .06       0  5026.5     .11       0
Bank Sta=4946.4,5026.5
XS Rating Curve= 0 ,0
Exp/Cntr=0.3,0.1

Type RM Length L Ch R = 1 ,7724    ,822,822,822
BEGIN DESCRIPTION:
G103-38-00 15.0
END DESCRIPTION:
XS GIS Cut Line= 3
      3912545.81     10013078.68      3912478.13      10012943.3
      3912290.65       10012735.
#Sta/Elev= 30
  4787.5   68.57  4864.9   67.41  4881.7   66.33  4926.4    66.7    4932   66.21
  4937.3    60.7  4942.8    60.7  4947.7   57.94  4955.1   51.87  4968.8   49.69
  4982.8    49.8  4990.3   46.86    5007   44.05  5015.3   44.05  5025.4   45.67
  5032.9   51.64  5039.6   53.48  5047.1   57.76  5053.8   60.65  5061.3    64.8
  5075.5   68.91  5082.2   68.79  5089.7   69.59  5096.4   69.24  5103.3   70.27
  5120.4   70.68  5143.3   71.25  5159.9   71.55  5181.6   73.16  5219.1   73.16
#Mann= 5 ,-1 , 0
  4787.5     .11       0  4955.1     .06       0  5032.9     .11       0
  5120.4     .11       0  5143.3     .17       0
Bank Sta=4947.7,5047.1
XS Rating Curve= 0 ,0
Exp/Cntr=0.3,0.1

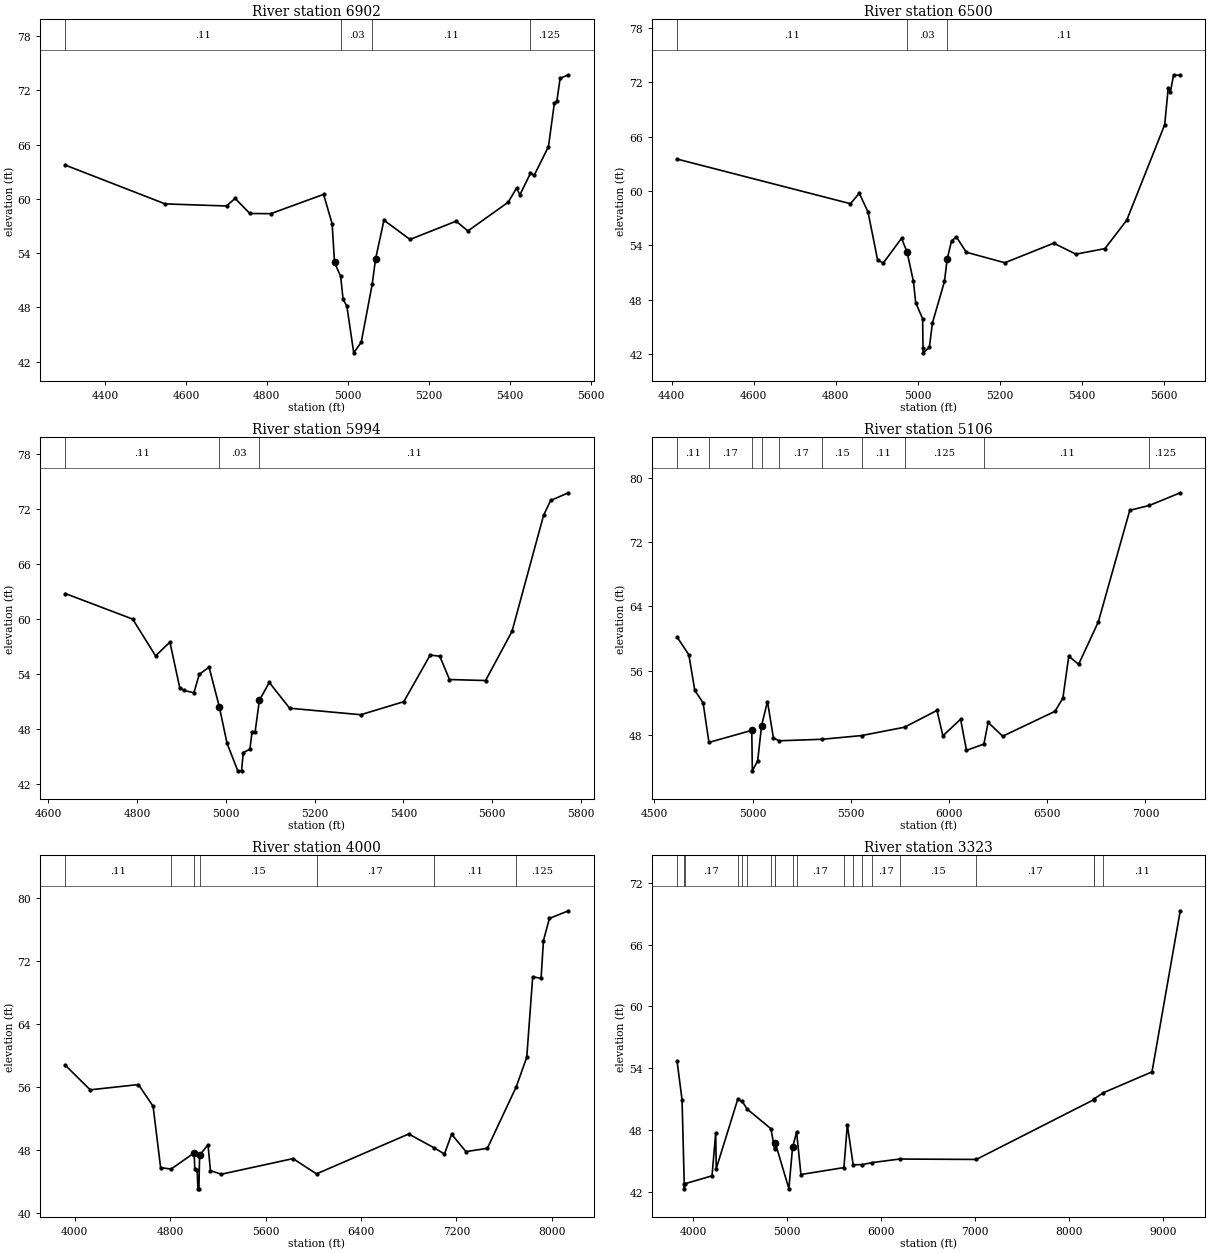
Type RM Length L Ch R = 1 ,6902    ,402,402,402
BEGIN DESCRIPTION:
G103-38-00 14.0
END DESCRIPTION:
XS GIS Cut Line= 3
      3913737.61      10013000.6      3913142.95     10012623.79
       3912812.5     10012197.08
#Sta/Elev= 30
  4301.7   63.73  4548.6   59.44  4700.3   59.21  4721.4   60.05  4757.9   58.38
  4809.6   58.36  4940.1   60.49  4961.3   57.26  4967.2   52.97  4982.4   51.43
  4988.4   48.88  4997.7   48.15  5014.7   42.98  5033.3   44.16  5060.5    50.6
  5068.6   53.34  5089.4   57.64  5153.7   55.51  5267.8   57.53  5296.8   56.45
  5396.4   59.62  5417.2   61.19  5425.4   60.44  5451.5   62.83  5460.7    62.6
    5496   65.76  5510.5   70.55  5516.8   70.82  5524.9   73.32  5545.4   73.71
#Mann= 4 ,-1 , 0
  4301.7     .11       0  4982.4     .03       0  5060.5     .11       0
  5451.5    .125       0
Bank Sta=4967.2,5068.6
XS Rating Curve= 0 ,0
Exp/Cntr=0.3,0.1

Type RM Length L Ch R = 1 ,6500    ,506,506,506
BEGIN DESCRIPTION:
G103-38-00 13.0
END DESCRIPTION:
XS GIS Cut Line= 3
      3913789.69     10012979.78      3913487.18     10012476.84
      3913242.84     10011886.08
#Sta/Elev= 30
  4413.1   63.51  4835.7   58.58    4857   59.74  4878.4   57.67  4901.7   52.39
  4915.3   52.01  4960.1   54.76  4973.6   53.25  4989.1   49.99  4994.6   47.65
  5011.5   45.87  5012.4   42.61  5012.9   42.11  5027.9   42.73  5035.4   45.42
  5064.7   49.99  5071.2   52.44    5082   54.49    5094    54.9  5117.9   53.22
  5211.9   52.06  5330.9   54.22    5385   53.01  5455.7   53.62  5508.9   56.76
  5601.4   67.31    5610   71.36  5615.4   70.94  5623.1   72.82  5639.3   72.75
#Mann= 3 , 0 , 0
  4413.1     .11       0  4973.6     .03       0  5071.2     .11       0
Bank Sta=4973.6,5071.2
XS Rating Curve= 0 ,0
Exp/Cntr=0.3,0.1

Type RM Length L Ch R = 1 ,5994    ,888,888,888
BEGIN DESCRIPTION:
G103-38-00 12.0
END DESCRIPTION:
XS GIS Cut Line= 3
      3914065.71     10012615.15      3913888.64     10012229.76
       3913268.9     10011886.04
#Sta/Elev= 30
  4638.7   62.81  4790.5   60.02    4842   56.01  4874.3   57.51  4896.3   52.56
  4905.4   52.24  4928.4   51.99  4940.3   53.99  4962.4   54.78  4985.4   50.48
  5002.8   46.49  5027.1   43.47  5035.6   43.47  5039.4   45.46  5054.3   45.83
  5059.3   47.71  5066.1   47.71  5075.7   51.16    5098   53.11  5143.8    50.3
  5303.9   49.59  5400.7   51.01  5460.2    56.1  5481.9   55.97  5503.7   53.43
  5584.9   53.32  5644.5   58.69  5715.5   71.34  5731.4   72.96  5771.5    73.8
#Mann= 3 , 0 , 0
  4638.7     .11       0  4985.4     .03       0  5075.7     .11       0
Bank Sta=4985.4,5075.7
XS Rating Curve= 0 ,0
Exp/Cntr=0.3,0.1

Type RM Length L Ch R = 1 ,5106    ,1106,1106,1106
BEGIN DESCRIPTION:
G103-38-00 10.0
END DESCRIPTION:
XS GIS Cut Line= 3
      3914667.85     10012311.06      3914646.15     10011747.77
      3912651.24     10011635.02
#Sta/Elev= 30
  4615.5    60.2  4675.5   57.98  4705.6   53.56    4748   52.01  4777.8   47.08
  4995.8   48.58  4998.7   43.54  5025.8   44.78  5045.8   49.18  5075.8   52.17
  5105.9   47.65  5134.8   47.28  5354.6   47.47  5554.9   47.93  5773.4   48.97
  5938.7   51.06  5968.8    47.9  6058.9   49.96    6089   46.09  6177.6   46.87
  6199.1   49.57  6273.4   47.85  6539.7   50.95  6579.7   52.59  6609.8   57.81
  6659.9    56.8    6760   62.07  6920.3   75.97  7019.8   76.57  7177.3   78.15
#Mann= 10 ,-1 , 0
  4615.5     .11       0  4777.8     .17       0  4995.8     .09       0
  5045.8     .15       0  5134.8     .17       0  5354.6     .15       0
  5554.9     .11       0  5773.4    .125       0  6177.6     .11       0
  7019.8    .125       0
Bank Sta=4995.8,5045.8
XS Rating Curve= 0 ,0
Exp/Cntr=0.3,0.1

Type RM Length L Ch R = 1 ,4000    ,677,677,677
BEGIN DESCRIPTION:
G103-38-00 8.0
END DESCRIPTION:
XS GIS Cut Line= 4
      3914776.36     10012320.69      3915672.38     10011716.84
      3915653.09     10011574.16      3912658.28     10011504.72
#Sta/Elev= 30
  3919.5   58.72  4128.5   55.59  4533.2   56.26  4656.1    53.5  4719.2   45.71
  4806.8   45.52    5000   47.57  5005.8   45.55    5026   45.38  5031.8   43.01
  5040.4   43.01  5046.2   47.28  5116.8   48.61    5137   45.32  5229.2   44.87
  5829.4   46.85  6026.7   44.91  6799.7   49.98  7012.1   48.23  7099.7   47.44
  7159.8   49.95  7279.8   47.74  7459.8   48.16    7702   55.98  7789.9   59.73
  7839.9   69.96    7910   69.75    7930   74.55    7980   77.37  8139.6   78.34
#Mann= 7 ,-1 , 0
  3919.5     .11       0  4806.8     .15       0    5000     .09       0
  5046.2     .15       0  6026.7     .17       0  7012.1     .11       0
    7702    .125       0
Bank Sta=5000,5046.2
XS Rating Curve= 0 ,0
Exp/Cntr=0.3,0.1

Type RM Length L Ch R = 1 ,3323    ,1318,1318,1318
BEGIN DESCRIPTION:
G103-38-00 6.0
END DESCRIPTION:
XS GIS Cut Line= 3
      3915817.87     10012811.04      3916469.06     10011504.72
      3912586.69     10011180.77
#Sta/Elev= 30
  3828.8   54.69  3881.9   50.94    3905   42.81  3905.5   42.31  3914.7   42.81
  4200.8   43.57    4240   47.74  4245.6   44.27  4474.5   50.99    4522   50.79
    4574   50.05  4828.6   48.13  4866.7   46.13 4873.04    46.8  5018.8   42.33
  5057.9   46.32  5100.9   47.81  5147.2    43.7  5604.6   44.37  5640.9   48.52
  5703.2   44.64  5801.8   44.66  5900.5   44.85  6198.5    45.2  7013.4   45.16
  8267.6   50.97  8270.4   51.05  8366.5   51.63  8883.5   53.65  9184.3   69.27
#Mann= 20 ,-1 , 0
  3828.8     .17       0    3905     .12       0  3914.7     .17       0
  4474.5     .15       0    4522     .17       0    4574     .15       0
  4828.6     .17       0  4866.7     .12       0 4873.04     .09       0
  5057.9     .15       0  5100.9     .17       0  5604.6     .15       0
  5703.2     .11       0  5801.8     .15       0  5900.5     .17       0
  6198.5     .15       0  7013.4     .17       0  8267.6     .11       0
  8270.4     .17       0  8366.5     .11       0
#Block Obstruct= 2 , 0
         4430.66   51.35
Bank Sta=4873.04,5057.9
XS Rating Curve= 0 ,0
Exp/Cntr=0.3,0.1