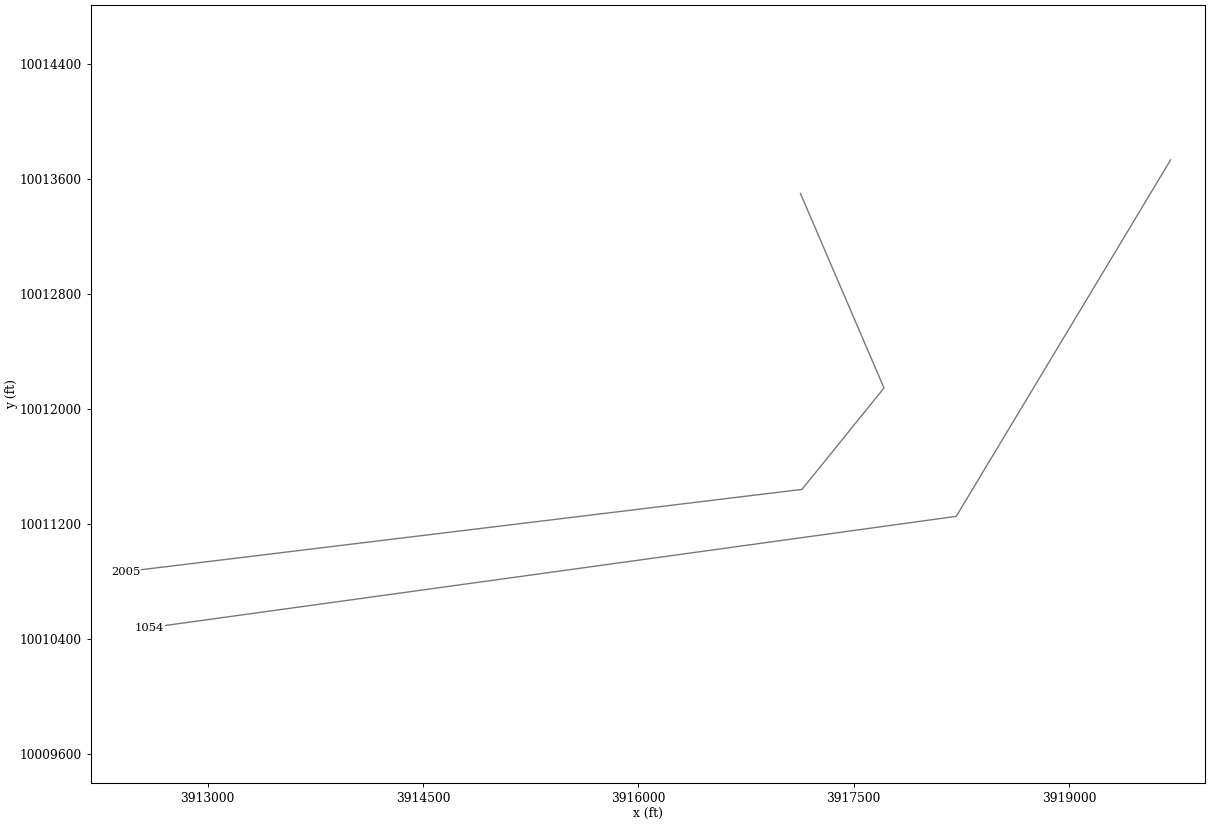
HEC-RAS study G103 38 00.prj: G103 38 00 Base Level Engineering

--- G103 38 00.g01 (geometry) --- (continued)

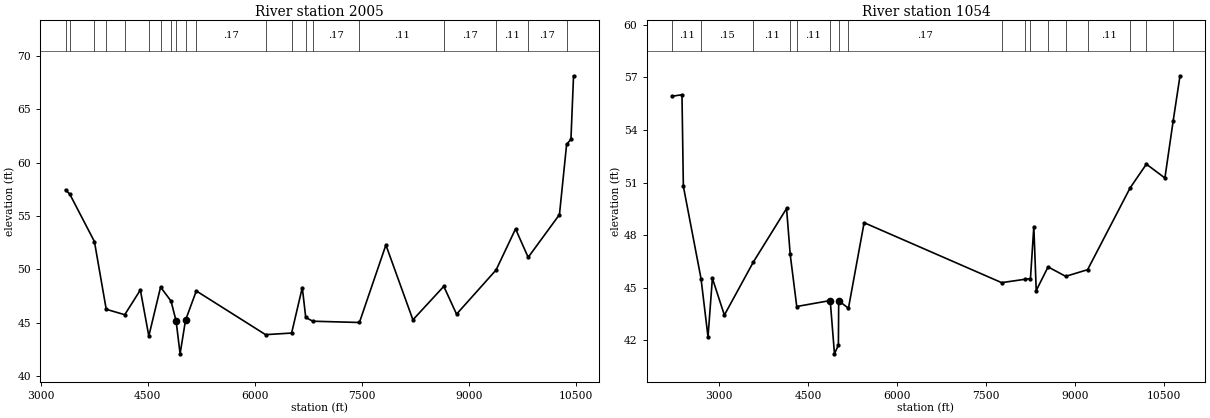
Type RM Length L Ch R = 1 ,2005    ,951,951,951
BEGIN DESCRIPTION:
G103-38-00 4.0
END DESCRIPTION:
XS GIS Cut Line= 4
       3917128.8     10013501.22      3917710.38     10012147.08
      3917139.49     10011440.66      3912431.66     10010868.41
#Sta/Elev= 30
  3345.3   57.45    3405   57.05  3750.8    52.6  3916.2   46.25  4175.9   45.74
  4395.1   48.06  4513.7   43.74  4678.6   48.33  4824.9   47.02  4896.1   45.16
  4952.3   42.07 5028.26   45.22  5179.6   47.97  6150.8   43.87  6516.3   44.02
  6665.8   48.29  6714.1   45.48    6813   45.13  7466.9   45.01  7838.3   52.28
  8217.2   45.26  8650.2    48.4  8829.2   45.79  9383.9   49.94  9656.5   53.79
  9833.5   51.12 10272.2   55.13 10372.7   61.72 10433.3   62.19 10469.8   68.15
#Mann= 20 ,-1 , 0
  3345.3     .11       0    3405    .125       0  3750.8     .11       0
  3916.2     .15       0  4175.9     .17       0  4513.7     .11       0
  4678.6     .15       0  4824.9     .15       0  4896.1     .09       0
 5028.26     .15       0  5179.6     .17       0  6150.8     .11       0
  6516.3     .15       0  6714.1     .11       0    6813     .17       0
  7466.9     .11       0  8650.2     .17       0  9383.9     .11       0
  9833.5     .17       0 10372.7     .11       0
Bank Sta=4896.1,5028.26
XS Rating Curve= 0 ,0
Exp/Cntr=0.3,0.1

Type RM Length L Ch R = 1 ,1054    ,0,0,0
BEGIN DESCRIPTION:
G103-38-00 2.0
END DESCRIPTION:
XS GIS Cut Line= 3
       3919706.9      10013735.6      3918213.86     10011252.98
      3912595.39     10010477.64
#Sta/Elev= 30
  2206.2   55.92    2375   56.01  2398.2   50.79  2696.3   45.52    2814   42.19
  2887.8   45.54  3089.8   43.44  3579.4   46.47  4138.8   49.52  4200.4    46.9
  4310.5   43.93  4875.1   44.27  4946.9   41.23    5013   41.73 5018.2544.25753
  5182.7   43.83  5446.9   48.71    7767   45.29  8153.5   45.48  8252.5   45.52
  8309.3   48.49  8349.7   44.84  8549.6   46.19  8846.7   45.65  9216.3   46.03
  9932.7   50.69 10207.5   52.05   10520   51.26 10658.3   54.49 10774.9   57.09
#Mann= 17 ,-1 , 0
  2206.2     .11       0  2696.3     .15       0  3579.4     .11       0
  4200.4     .17       0  4310.5     .11       0  4875.1     .07       0
 5018.25     .11       0  5182.7     .17       0    7767     .15       0
  8153.5     .11       0  8252.5     .17       0  8549.6     .11       0
  8846.7     .17       0  9216.3     .11       0  9932.7     .17       0
 10207.5     .11       0 10658.3     .17       0
Bank Sta=4875.1,5018.25
XS Rating Curve= 0 ,0
Exp/Cntr=0.3,0.1

Chan Stop Cuts=-1
Use User Specified Reach Order=0
Composite Channel Slope=5