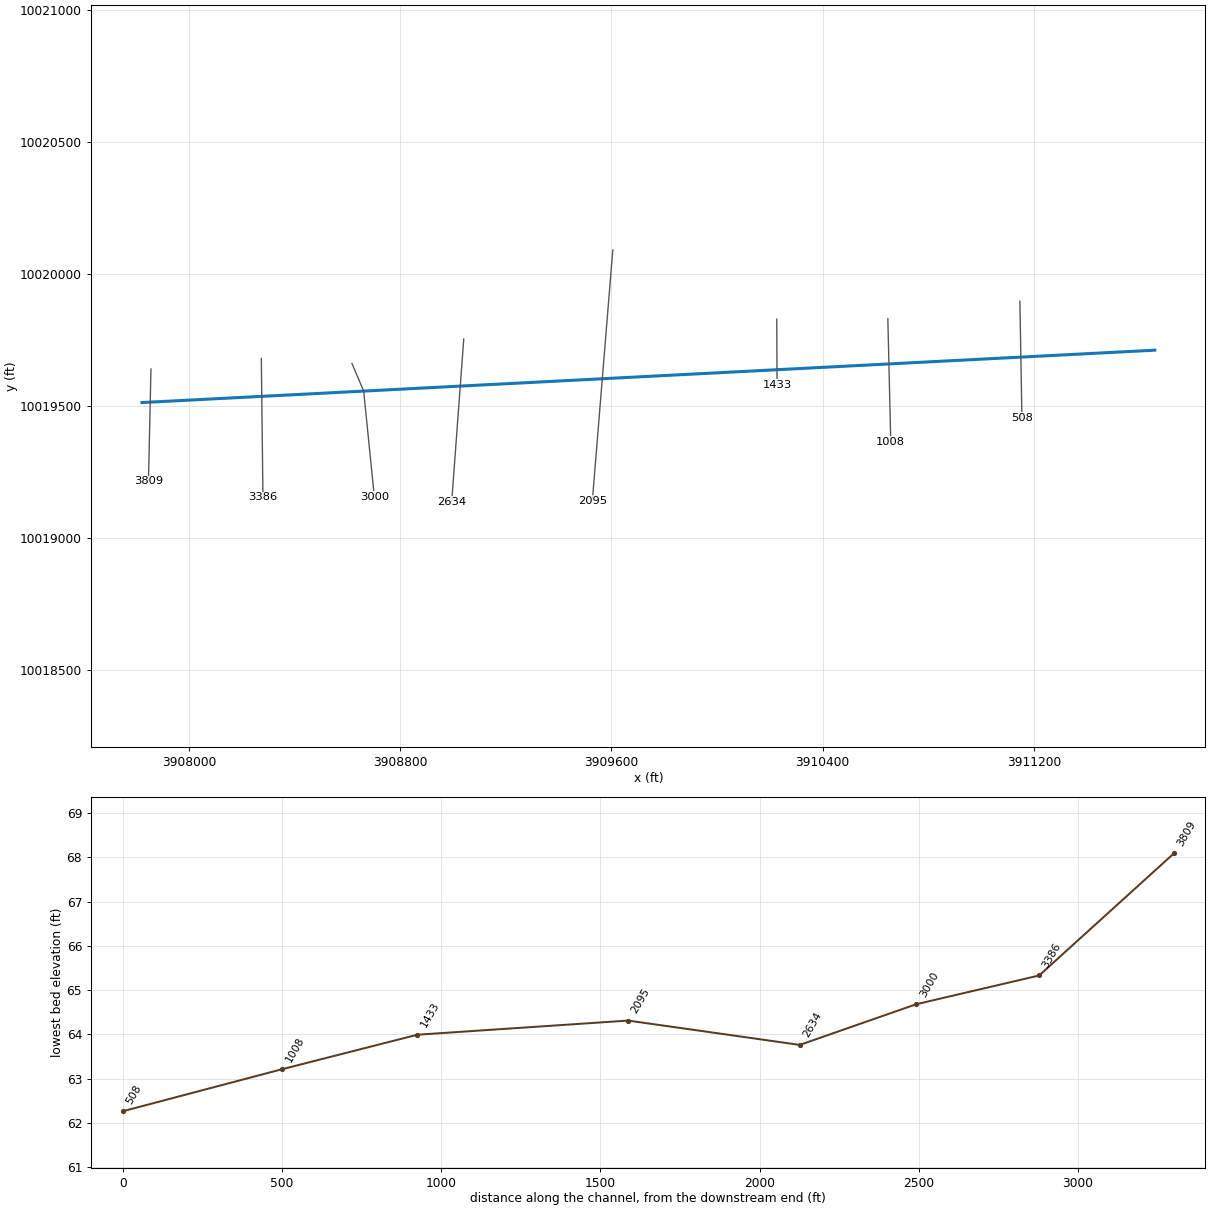
--- G103 38 02.prj (project) ---

Proj Title=G103 38 02 Base Level Engineering
Current Plan=p01
Default Exp/Contr=0.3,0.1
English Units
Geom File=g01
Flow File=f01
Flow File=f02
Plan File=p01
Y Axis Title=Elevation
X Axis Title(PF)=Main Channel Distance
X Axis Title(XS)=Station
BEGIN DESCRIPTION:
G103 38 02
END DESCRIPTION:
DSS Export Rating Curves= 0
DSS Export Rating Curve Sorted= 0
DSS Export Volume Flow Curves= 0
DXF OffsetX= 0
DXF OffsetY= 0
DXF ScaleX= 1
DXF ScaleY= 10

--- G103 38 02.p01 (plan) ---

Plan Title=Multiple Run
Short Identifier=Multiple
Geom File=g01
Flow File=f01
Subcritical Flow
K Sum by GR= 0
Std Step Tol= 0.01
Critical Tol= 0.01
Num of Std Step Trials= 20
Max Error Tol= 0.3
Flow Tol Ratio= 0.001
Split Flow NTrial= 30
Split Flow Tol= 0.02
Split Flow Ratio= 0.02
Log Output Level= 0
Friction Slope Method= 1
Unsteady Friction Slope Method= 2
Unsteady Bridges Friction Slope Method= 1
Parabolic Critical Depth
Global Vel Dist=  1 , 1 , 1
Global Log Level= 0
CheckData=True
Encroach Param= -1, 0, 0, 0
BEGIN DESCRIPTION:
Multiple Run
END DESCRIPTION:

--- G103 38 02.f01 (steady flow) ---

Flow Title=Multiple
Program Version=4.10
Number of Profiles= 7
Profile Names=10-year,25-year,50-year,1pct_min,100-year,1pct_plu,500-year
River Rch & RM=G103 38 02,Reach-1         ,3809
     268     324     406     167     503    1519     800
River Rch & RM=G103 38 02,Reach-1         ,3386
     427     536     687     288     871    2630    1452
Boundary for River Rch & Prof#=G103 38 02,Reach-1         , 1
Up Type= 0
Dn Type= 3
Dn Slope=0.005
Boundary for River Rch & Prof#=G103 38 02,Reach-1         , 2
Up Type= 0
Dn Type= 3
Dn Slope=0.005
Boundary for River Rch & Prof#=G103 38 02,Reach-1         , 3
Up Type= 0
Dn Type= 3
Dn Slope=0.005
Boundary for River Rch & Prof#=G103 38 02,Reach-1         , 4
Up Type= 0
Dn Type= 3
Dn Slope=0.005
Boundary for River Rch & Prof#=G103 38 02,Reach-1         , 5
Up Type= 0
Dn Type= 3
Dn Slope=0.005
Boundary for River Rch & Prof#=G103 38 02,Reach-1         , 6
Up Type= 0
Dn Type= 3
Dn Slope=0.005
Boundary for River Rch & Prof#=G103 38 02,Reach-1         , 7
Up Type= 0
Dn Type= 3
Dn Slope=0.005
DSS Import GetInterval= 0
DSS Import GetPeak= 0
DSS Import FillOption= 0

--- G103 38 02.f02 (steady flow) ---

Flow Title=Orig_BLE_Flows
Program Version=4.10
Number of Profiles= 7
Profile Names=10-year,25-year,50-year,1pct_min,100-year,1pct_plu,500-year
River Rch & RM=G103 38 02,Reach-1         ,3809
     268     318     353     128     387    1169     465
River Rch & RM=G103 38 02,Reach-1         ,3386
     427     525     597     222     670    2024     844
Boundary for River Rch & Prof#=G103 38 02,Reach-1         , 1
Up Type= 0
Dn Type= 3
Dn Slope=0.005
Boundary for River Rch & Prof#=G103 38 02,Reach-1         , 2
Up Type= 0
Dn Type= 3
Dn Slope=0.005
Boundary for River Rch & Prof#=G103 38 02,Reach-1         , 3
Up Type= 0
Dn Type= 3
Dn Slope=0.005
Boundary for River Rch & Prof#=G103 38 02,Reach-1         , 4
Up Type= 0
Dn Type= 3
Dn Slope=0.005
Boundary for River Rch & Prof#=G103 38 02,Reach-1         , 5
Up Type= 0
Dn Type= 3
Dn Slope=0.005
Boundary for River Rch & Prof#=G103 38 02,Reach-1         , 6
Up Type= 0
Dn Type= 3
Dn Slope=0.005
Boundary for River Rch & Prof#=G103 38 02,Reach-1         , 7
Up Type= 0
Dn Type= 3
Dn Slope=0.005
DSS Import GetInterval= 0
DSS Import GetPeak= 0
DSS Import FillOption= 0

--- G103 38 02.g01 (geometry) ---

Geom Title=Existing Conditions
Program Version=4.10

River Reach=G103 38 02      ,Reach-1
Reach XY= 2
       3907822.5      10019513.1      3911658.23     10019711.42

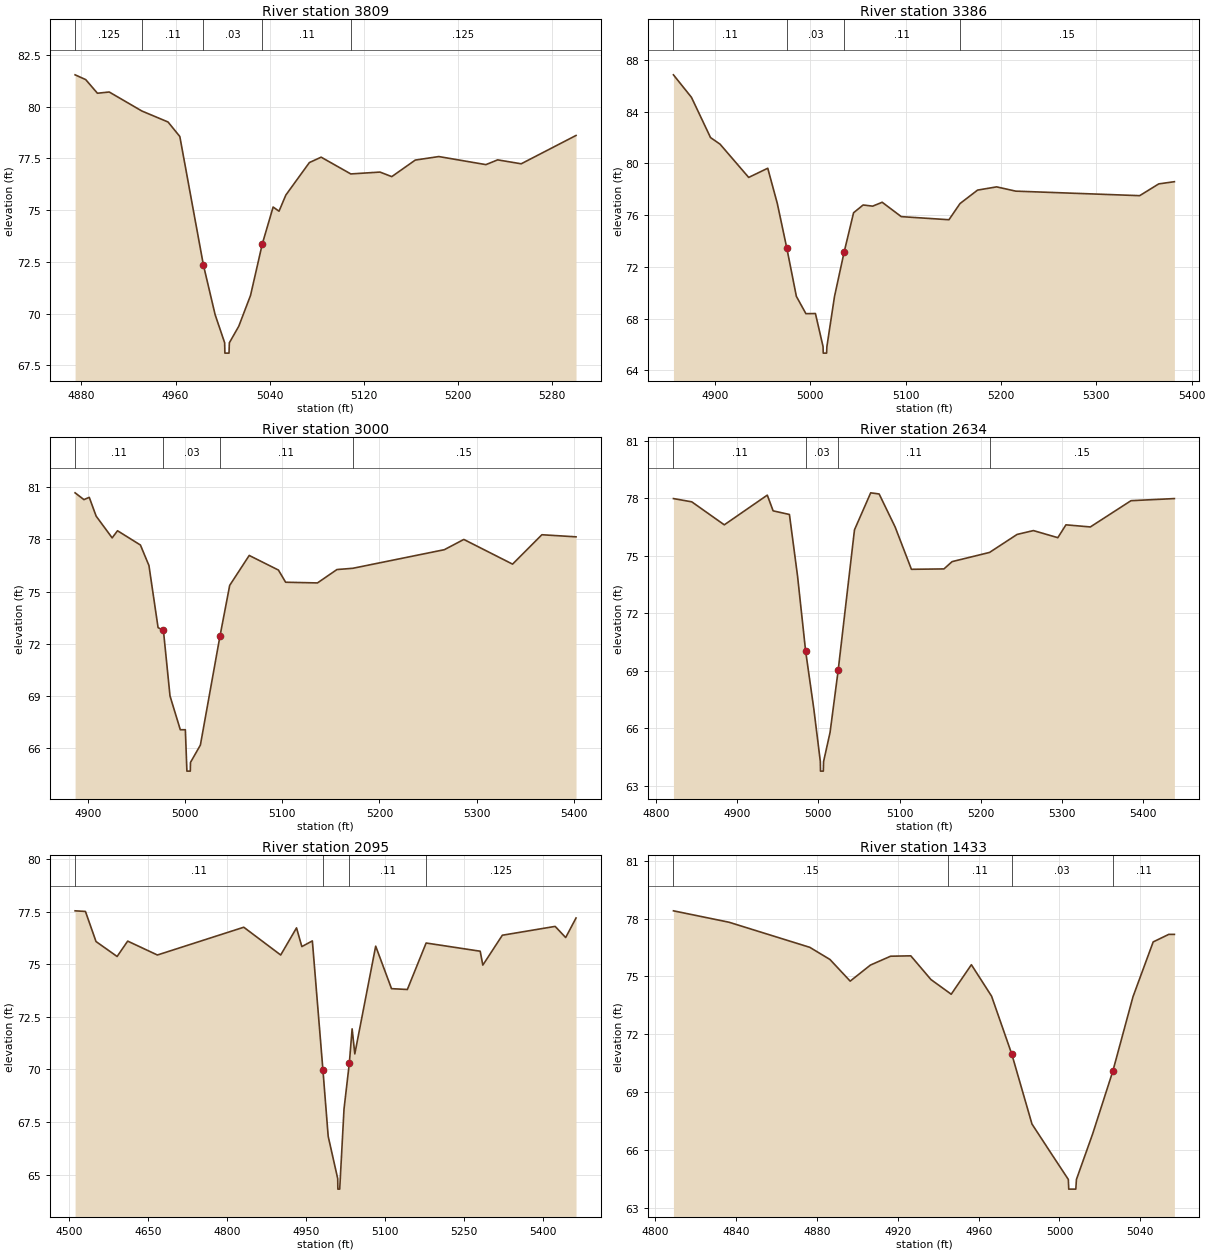
Type RM Length L Ch R = 1 ,3809    ,423,423,423
BEGIN DESCRIPTION:
G103-38-02 3.0
END DESCRIPTION:
XS GIS Cut Line= 2
      3907856.67     10019640.09      3907847.25     10019214.49
#Sta/Elev= 30
  4874.6   81.54  4883.6   81.31  4893.6   80.65  4903.6   80.71  4931.4   79.79
  4953.6   79.26  4963.6   78.56  4983.6   72.36  4993.6   69.95  5001.7   68.59
  5001.9   68.09  5005.4   68.09  5005.7   68.59  5013.7   69.39  5023.7   70.88
  5033.7   73.37  5042.9   75.15  5047.9   74.95  5053.7   75.73  5073.7    77.3
  5083.7   77.56  5108.9   76.75  5133.7   76.84  5143.7   76.62  5163.7   77.42
  5183.7   77.59  5223.7    77.2  5233.7   77.43  5253.7   77.24  5300.3   78.61
#Mann= 5 ,-1 , 0
  4874.6    .125       0  4931.4     .11       0  4983.6     .03       0
  5033.7     .11       0  5108.9    .125       0
Bank Sta=4983.6,5033.7
XS Rating Curve= 0 ,0
Exp/Cntr=0.3,0.1

Type RM Length L Ch R = 1 ,3386    ,386,386,386
BEGIN DESCRIPTION:
Mapping XS 0fe51f84
END DESCRIPTION:
XS GIS Cut Line= 2
      3908274.64     10019679.95       3908280.8     10019154.69
#Sta/Elev= 30
  4856.6   86.84  4875.5    85.1  4895.5   81.99  4905.5   81.48  4935.5   78.91
  4955.5   79.62  4965.5    76.9  4975.5   73.44  4985.5   69.72  4995.5   68.38
  5005.5   68.39  5013.5   65.83  5013.7   65.33  5017.2   65.33  5017.5   65.83
  5025.5   69.71  5035.5   73.11  5045.5   76.18  5055.5   76.78  5065.5   76.69
  5075.5   76.99  5095.5   75.88  5145.5   75.64  5157.1   76.89  5175.5   77.93
  5195.5   78.18  5215.5   77.85  5345.5    77.5  5365.5   78.41  5381.9   78.58
#Mann= 4 ,-1 , 0
  4856.6     .11       0  4975.5     .03       0  5035.5     .11       0
  5157.1     .15       0
Bank Sta=4975.5,5035.5
XS Rating Curve= 0 ,0
Exp/Cntr=0.3,0.1

Type RM Length L Ch R = 1 ,3000    ,366,366,366
BEGIN DESCRIPTION:
G103-38-02 2.0
END DESCRIPTION:
XS GIS Cut Line= 3
      3908617.85     10019661.08      3908662.23     10019556.51
      3908702.68     10019156.05
#Sta/Elev= 30
  4886.4   80.68  4895.5   80.29    4901   80.42  4908.1   79.34  4924.6   78.09
  4930.1    78.5  4953.7   77.68  4962.5    76.5  4971.9   72.93  4977.4   72.77
  4984.2      69  4994.8   67.06    5000   67.06  5001.6   64.68  5005.1   64.68
  5005.3   65.18  5015.5   66.18  5035.6   72.42  5045.7   75.36  5065.8   77.08
  5095.9   76.24  5103.3   75.54  5136.1    75.5  5156.2   76.27  5172.4   76.34
  5266.8   77.41  5286.9      78  5337.1   76.58  5367.3   78.27  5402.5   78.15
#Mann= 4 ,-1 , 0
  4886.4     .11       0  4977.4     .03       0  5035.6     .11       0
  5172.4     .15       0
Bank Sta=4977.4,5035.6
XS Rating Curve= 0 ,0
Exp/Cntr=0.3,0.1

Type RM Length L Ch R = 1 ,2634    ,539,539,539
BEGIN DESCRIPTION:
Mapping XS 033c8194
END DESCRIPTION:
XS GIS Cut Line= 2
      3909041.23     10019753.64      3908995.65     10019137.72
#Sta/Elev= 30
  4821.3   77.98  4843.9   77.81    4884   76.61    4937   78.16  4944.2   77.34
  4964.3   77.15  4974.3   73.94  4984.3   70.01  4994.3   67.03  5002.4   64.26
  5002.6   63.76  5006.1   63.76  5006.4   64.26  5014.4   65.78  5024.4   69.02
  5044.5   76.35  5064.5   78.28  5074.9   78.22  5094.6    76.5  5114.7   74.29
  5154.8   74.31  5164.8   74.69    5211   75.17    5245   76.11  5265.1   76.31
  5295.2   75.94  5305.2   76.61  5335.3    76.5  5385.4   77.87  5438.9   77.98
#Mann= 4 ,-1 , 0
  4821.3     .11       0  4984.3     .03       0  5024.4     .11       0
    5211     .15       0
Bank Sta=4984.3,5024.4
XS Rating Curve= 0 ,0
Exp/Cntr=0.3,0.1

Type RM Length L Ch R = 1 ,2095    ,662,662,662
BEGIN DESCRIPTION:
Mapping XS c15864c3
END DESCRIPTION:
XS GIS Cut Line= 2
      3909605.68     10020090.72      3909528.29     10019141.47
#Sta/Elev= 30
  4510.9   77.54  4530.6   77.51  4550.7   76.08  4590.8   75.37  4610.9    76.1
  4667.4   75.44  4831.6   76.76  4901.8   75.44  4931.9   76.73    4942   75.84
    4962   76.11  4982.1   69.97  4992.1   66.82  5010.2   64.81  5010.5   64.31
    5014   64.31  5022.2   68.12  5032.3    70.3  5037.6   71.93  5042.7   70.74
  5082.4   75.86  5112.5   73.84  5142.6    73.8  5178.3   76.01  5281.1   75.62
  5286.1   74.96  5323.2   76.38  5423.6    76.8  5443.6   76.27  5463.3    77.2
#Mann= 4 ,-1 , 0
  4510.9     .11       0  4982.1     .03       0  5032.3     .11       0
  5178.3    .125       0
Bank Sta=4982.1,5032.3
XS Rating Curve= 0 ,0
Exp/Cntr=0.3,0.1

Type RM Length L Ch R = 1 ,1433    ,425,425,425
BEGIN DESCRIPTION:
Mapping XS 51c7e027
END DESCRIPTION:
XS GIS Cut Line= 2
      3910226.66     10019828.54       3910227.7     10019580.54
#Sta/Elev= 26
  4808.9    78.4  4836.4   77.81  4876.4   76.51  4886.4   75.88  4896.4   74.76
  4906.4   75.59  4916.4   76.05  4926.4   76.07  4936.4   74.84    4945   74.19
  4946.4   74.08  4956.4   75.61  4966.4   73.98  4976.4   70.98  4986.4   67.36
  4996.4   65.76  5004.4   64.49  5004.6   63.99  5008.1   63.99  5008.4   64.49
  5016.4   66.84  5026.4   70.09  5036.4   73.95  5046.4   76.79  5054.1   77.18
  5056.9   77.18
#Mann= 4 ,-1 , 0
  4808.9     .15       0    4945     .11       0  4976.4     .03       0
  5026.4     .11       0
Bank Sta=4976.4,5026.4
XS Rating Curve= 0 ,0
Exp/Cntr=0.3,0.1

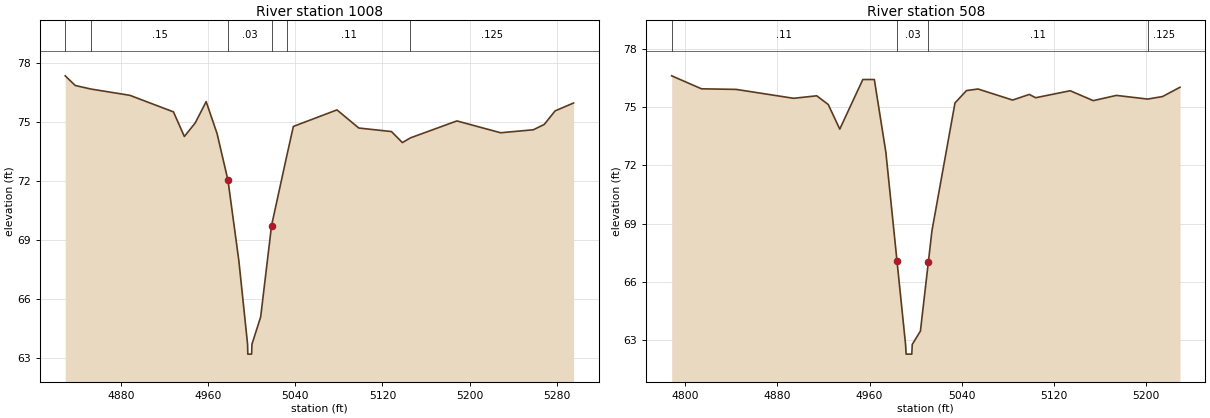
Type RM Length L Ch R = 1 ,1008    ,500,500,500
BEGIN DESCRIPTION:
Mapping XS 525c7106
END DESCRIPTION:
XS GIS Cut Line= 2
      3910647.33     10019830.31       3910658.4     10019364.14
#Sta/Elev= 30
    4829   77.34  4838.2   76.85  4852.5   76.67  4888.3   76.35  4928.3   75.51
  4938.3   74.26  4948.3   74.95  4958.3   76.03  4968.3   74.41  4978.3   72.04
  4988.3   67.95  4996.3   63.71  4996.5   63.21    5000   63.21  5000.3   63.71
  5008.3    65.1  5018.3   69.74  5032.3   73.29  5038.3   74.77  5078.3   75.61
  5098.3   74.69  5128.3   74.51  5138.3   73.95  5145.7   74.19  5188.3   75.05
  5228.4   74.45  5258.4    74.6  5268.4   74.87  5278.4   75.56  5295.3   75.96
#Mann= 6 ,-1 , 0
    4829    .125       0  4852.5     .15       0  4978.3     .03       0
  5018.3     .15       0  5032.3     .11       0  5145.7    .125       0
Bank Sta=4978.3,5018.3
XS Rating Curve= 0 ,0
Exp/Cntr=0.3,0.1

Type RM Length L Ch R = 1 ,508     ,0,0,0
BEGIN DESCRIPTION:
Mapping XS e8b5cd65
END DESCRIPTION:
XS GIS Cut Line= 2
      3911147.37     10019896.96      3911155.18     10019455.83
#Sta/Elev= 30
  4788.2   76.62  4814.1   75.95  4844.1   75.92  4894.1   75.46  4914.1   75.59
  4924.1   75.14  4934.1   73.87  4954.1   76.43  4964.1   76.43  4974.1   72.68
 4983.7867.06468  4991.2   62.76  4991.7   62.26  4996.6   62.26    4997   62.76
  5004.1   63.45 5010.99 67.0122  5014.1   68.62  5034.1   75.22  5044.1   75.86
  5054.1   75.94  5084.1   75.37  5098.6   75.66  5104.1   75.49  5134.1   75.85
  5154.1   75.34  5174.2   75.61  5201.3   75.42  5214.2   75.55  5229.4   76.03
#Mann= 4 ,-1 , 0
  4788.2     .11       0 4983.78     .03       0 5010.99     .11       0
  5201.3    .125       0
Bank Sta=4983.78,5010.99
XS Rating Curve= 0 ,0
Exp/Cntr=0.3,0.1

Chan Stop Cuts=-1
Use User Specified Reach Order=0
Composite Channel Slope=5