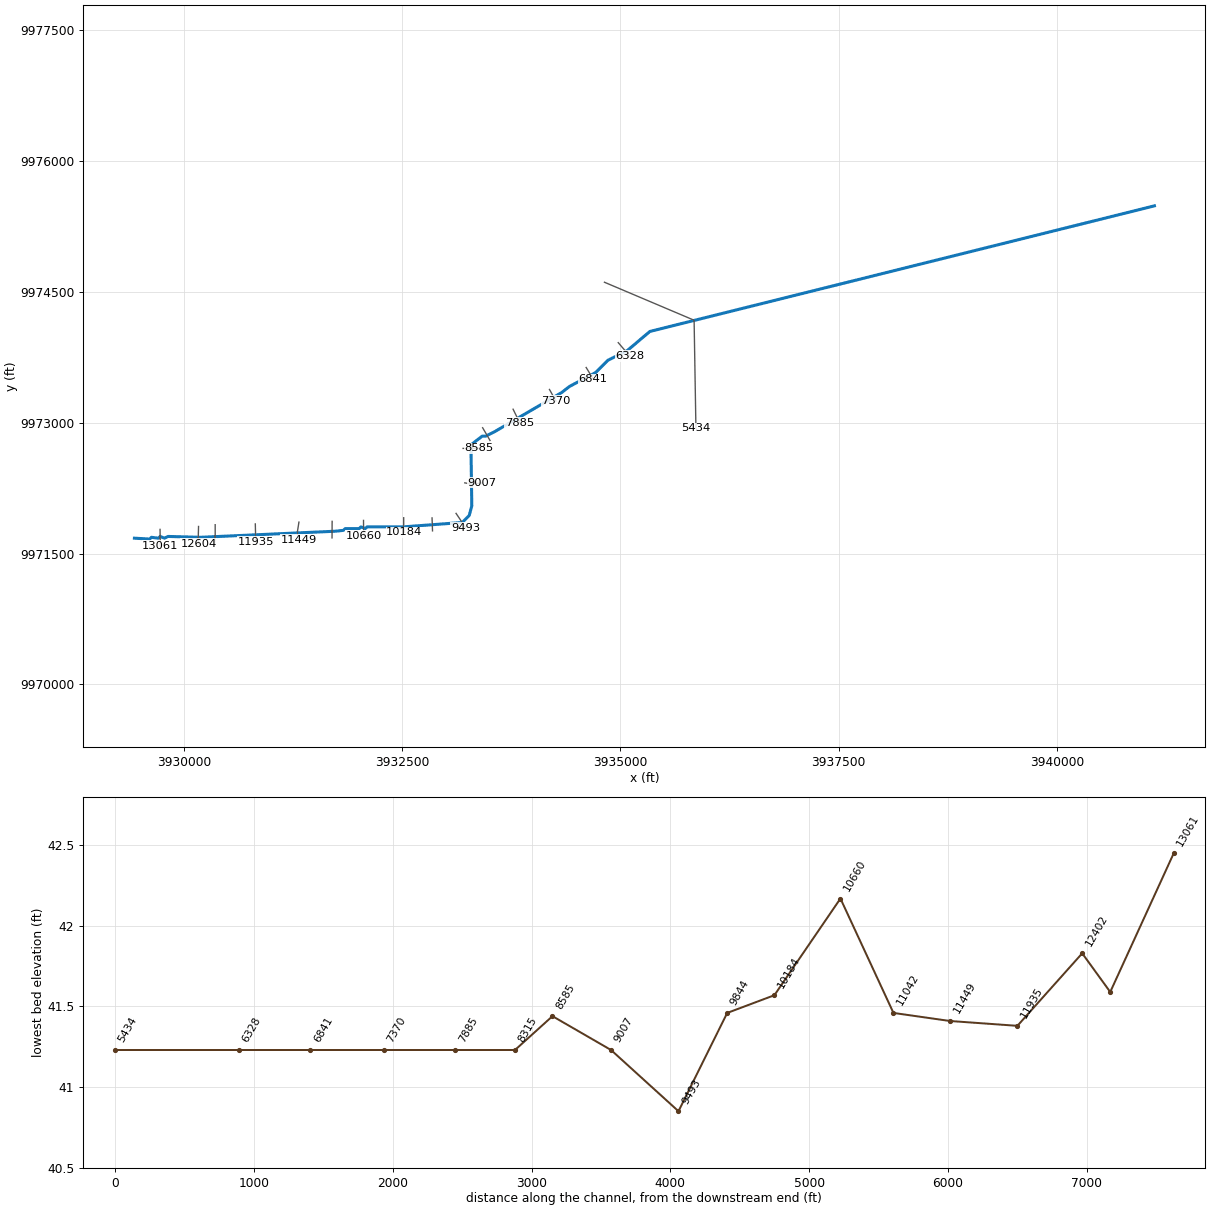
--- G103 52 99.prj (project) ---

Proj Title=G103 52 99 Base Level Engineering
Current Plan=p01
Default Exp/Contr=0.3,0.1
English Units
Geom File=g01
Flow File=f01
Flow File=f02
Plan File=p01
Y Axis Title=Elevation
X Axis Title(PF)=Main Channel Distance
X Axis Title(XS)=Station
BEGIN DESCRIPTION:
G103 52 99
END DESCRIPTION:
DSS Export Rating Curves= 0
DSS Export Rating Curve Sorted= 0
DSS Export Volume Flow Curves= 0
DXF OffsetX= 0
DXF OffsetY= 0
DXF ScaleX= 1
DXF ScaleY= 10

--- G103 52 99.p01 (plan) ---

Plan Title=Multiple Run
Short Identifier=Multiple
Geom File=g01
Flow File=f01
Subcritical Flow
K Sum by GR= 0
Std Step Tol= 0.01
Critical Tol= 0.01
Num of Std Step Trials= 20
Max Error Tol= 0.3
Flow Tol Ratio= 0.001
Split Flow NTrial= 30
Split Flow Tol= 0.02
Split Flow Ratio= 0.02
Log Output Level= 0
Friction Slope Method= 1
Unsteady Friction Slope Method= 2
Unsteady Bridges Friction Slope Method= 1
Parabolic Critical Depth
Global Vel Dist=  1 , 1 , 1
Global Log Level= 0
CheckData=True
Encroach Param= -1, 0, 0, 0
BEGIN DESCRIPTION:
Multiple Run
END DESCRIPTION:

--- G103 52 99.f01 (steady flow) ---

Flow Title=Multiple
Program Version=4.10
Number of Profiles= 7
Profile Names=10-year,25-year,50-year,1pct_min,100-year,1pct_plu,500-year
River Rch & RM=G103 52 99,Reach-1         ,13061
     215     262     330     137     415    1253     678
River Rch & RM=G103 52 99,Reach-1         ,8315
     397     499     642     272     820    2476    1388
Boundary for River Rch & Prof#=G103 52 99,Reach-1         , 1
Up Type= 0
Dn Type= 3
Dn Slope=0.0001
Boundary for River Rch & Prof#=G103 52 99,Reach-1         , 2
Up Type= 0
Dn Type= 3
Dn Slope=0.0001
Boundary for River Rch & Prof#=G103 52 99,Reach-1         , 3
Up Type= 0
Dn Type= 3
Dn Slope=0.0001
Boundary for River Rch & Prof#=G103 52 99,Reach-1         , 4
Up Type= 0
Dn Type= 3
Dn Slope=0.0001
Boundary for River Rch & Prof#=G103 52 99,Reach-1         , 5
Up Type= 0
Dn Type= 3
Dn Slope=0.0001
Boundary for River Rch & Prof#=G103 52 99,Reach-1         , 6
Up Type= 0
Dn Type= 3
Dn Slope=0.0001
Boundary for River Rch & Prof#=G103 52 99,Reach-1         , 7
Up Type= 0
Dn Type= 3
Dn Slope=0.0001
DSS Import GetInterval= 0
DSS Import GetPeak= 0
DSS Import FillOption= 0

--- G103 52 99.f02 (steady flow) ---

Flow Title=Orig_BLE_Flows
Program Version=4.10
Number of Profiles= 7
Profile Names=10-year,25-year,50-year,1pct_min,100-year,1pct_plu,500-year
River Rch & RM=G103 52 99,Reach-1         ,13061
     215     257     287     106     319     964     394
River Rch & RM=G103 52 99,Reach-1         ,8315
     397     489     558     209     631    1904     807
Boundary for River Rch & Prof#=G103 52 99,Reach-1         , 1
Up Type= 0
Dn Type= 3
Dn Slope=0.0001
Boundary for River Rch & Prof#=G103 52 99,Reach-1         , 2
Up Type= 0
Dn Type= 3
Dn Slope=0.0001
Boundary for River Rch & Prof#=G103 52 99,Reach-1         , 3
Up Type= 0
Dn Type= 3
Dn Slope=0.0001
Boundary for River Rch & Prof#=G103 52 99,Reach-1         , 4
Up Type= 0
Dn Type= 3
Dn Slope=0.0001
Boundary for River Rch & Prof#=G103 52 99,Reach-1         , 5
Up Type= 0
Dn Type= 3
Dn Slope=0.0001
Boundary for River Rch & Prof#=G103 52 99,Reach-1         , 6
Up Type= 0
Dn Type= 3
Dn Slope=0.0001
Boundary for River Rch & Prof#=G103 52 99,Reach-1         , 7
Up Type= 0
Dn Type= 3
Dn Slope=0.0001
DSS Import GetInterval= 0
DSS Import GetPeak= 0
DSS Import FillOption= 0

--- G103 52 99.g01 (geometry) ---

Geom Title=Existing Conditions
Program Version=4.10

River Reach=G103 52 99      ,Reach-1
Reach XY= 30
      3929433.23      9971676.84      3929608.23      9971666.84
      3929628.23      9971686.84      3929708.23      9971676.84
      3929728.23      9971696.84      3929778.23      9971676.84
      3929818.23      9971696.84      3930188.23      9971686.84
      3931738.23      9971756.84      3931828.23      9971766.84
      3931848.23      9971786.84      3932008.23      9971786.84
      3932028.23      9971806.84      3932078.23      9971786.84
      3932098.23      9971806.84      3932518.23      9971806.84
      3933188.23      9971856.84      3933268.23      9971936.84
      3933298.23      9972046.84      3933288.23      9972746.84
      3933418.23      9972846.84      3933458.23      9972846.84
      3933558.23      9972896.84      3934328.23      9973346.84
      3934418.23      9973416.84      3934718.23      9973576.84
      3934858.23      9973716.84      3935078.23      9973826.84
      3935338.23      9974046.84      3941118.09      9975486.76

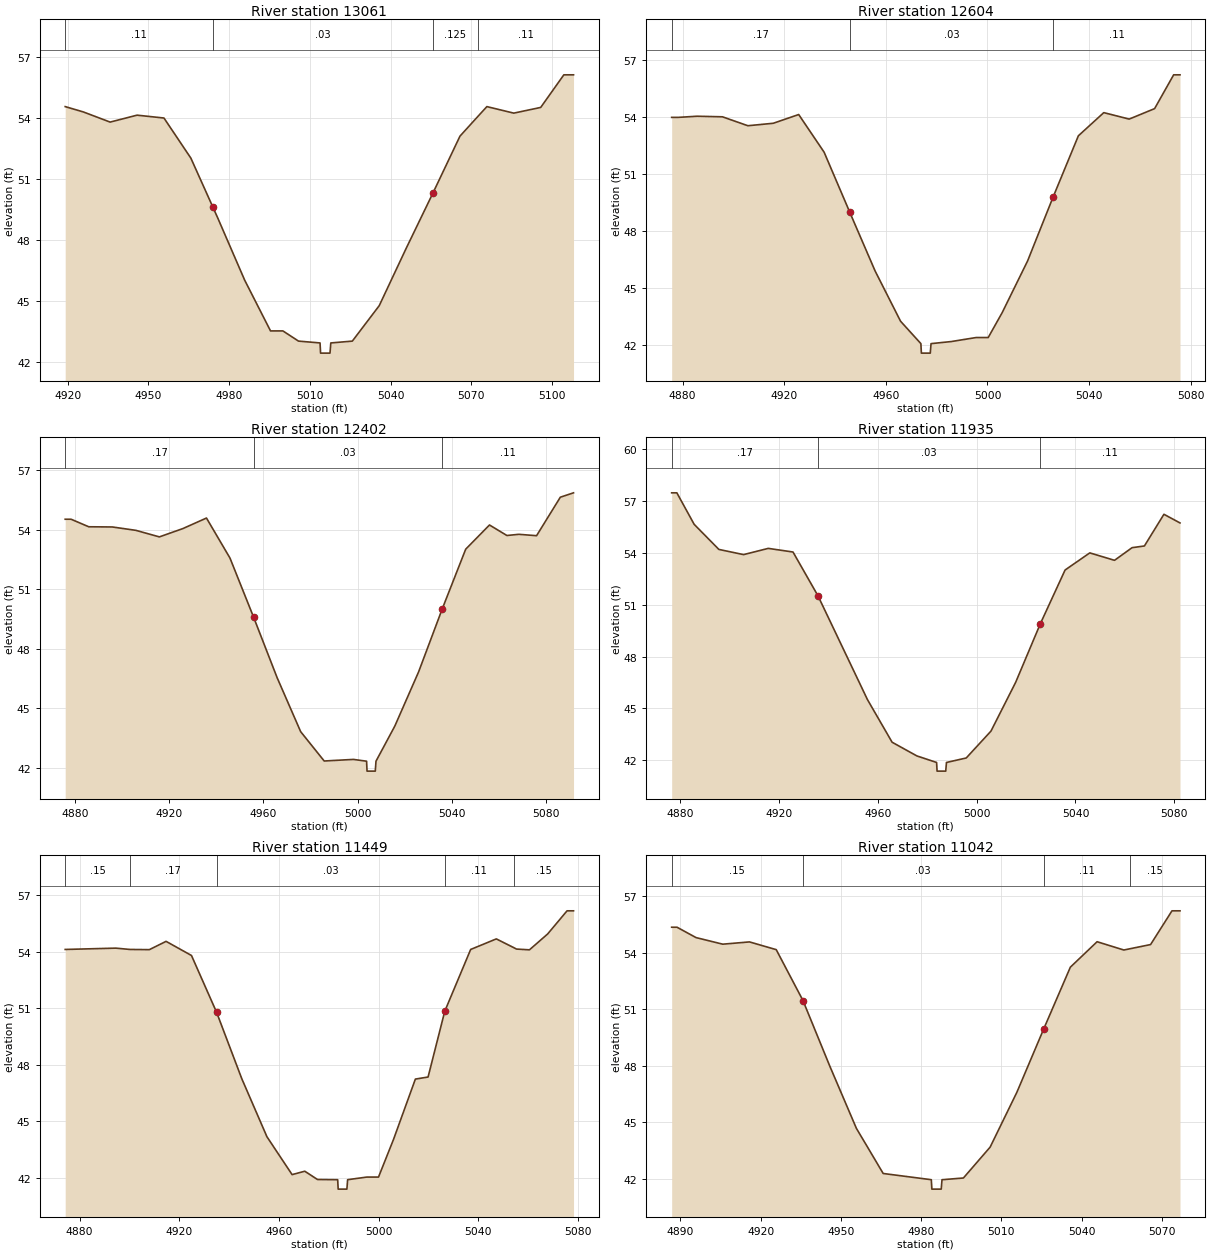
Type RM Length L Ch R = 1 ,13061   ,457,457,457
BEGIN DESCRIPTION:
G103-52-99 17.0
END DESCRIPTION:
XS GIS Cut Line= 3
      3929726.97      9971777.73      3929728.23      9971696.84
      3929729.57      9971588.85
#Sta/Elev= 29
  4919.1   54.55  4925.8   54.29  4935.8   53.79  4945.8   54.13  4955.8   53.99
  4965.8   52.02    4974   49.61  4975.8   49.08  4985.8   46.03 4992.2644.35447
  4995.4   43.54    5000   43.54  5005.8   43.04  5013.8   42.95    5014   42.45
  5017.5   42.45  5017.8   42.95  5025.8   43.04 5032.3244.17448  5035.8   44.78
  5045.8   47.59  5055.8   50.32  5065.8    53.1  5072.4   54.06  5075.8   54.55
  5085.8   54.23  5095.8   54.51  5104.4   56.11    5108   56.11
#Mann= 4 ,-1 , 0
  4919.1     .11       0    4974     .03       0  5055.8    .125       0
  5072.4     .11       0
Bank Sta=4974,5055.8
XS Rating Curve= 0 ,0
Exp/Cntr=0.3,0.1

Type RM Length L Ch R = 1 ,12604   ,202,202,202
BEGIN DESCRIPTION:
G103-52-99 16.0
END DESCRIPTION:
XS GIS Cut Line= 3
      3930167.85       9971811.1      3930164.47      9971686.55
      3930167.85      9971611.12
#Sta/Elev= 28
  4875.7      54  4878.2      54  4885.7   54.06  4895.7   54.03  4905.7   53.56
  4915.7   53.69  4925.7   54.15  4935.7   52.17  4945.8   49.01  4947.5   48.48
  4955.8   45.91  4965.8   43.27  4973.8   42.09    4974   41.59  4977.5   41.59
  4977.8   42.09  4985.8    42.2  4995.5   42.41  5000.3   42.41  5005.8   43.72
  5015.8   46.44  5025.8   49.79  5035.8   53.03  5045.8   54.25  5055.8   53.91
  5065.8   54.46  5073.3   56.24  5075.8   56.24
#Mann= 3 , 0 , 0
  4875.7     .17       0  4945.8     .03       0  5025.8     .11       0
Bank Sta=4945.8,5025.8
XS Rating Curve= 0 ,0
Exp/Cntr=0.3,0.1

Type RM Length L Ch R = 1 ,12402   ,467,467,467
BEGIN DESCRIPTION:
G103-52-99 15.0
END DESCRIPTION:
XS GIS Cut Line= 3
      3930358.48      9971831.04      3930358.48      9971708.68
      3930350.71      9971615.46
#Sta/Elev= 28
  4875.8   54.52  4878.3   54.52  4885.8   54.14  4895.8   54.13  4905.8   53.96
  4915.8   53.63  4925.8   54.05  4935.8   54.58  4945.8   52.56  4955.8   49.59
  4965.8   46.54  4975.8   43.82  4985.8   42.34  4998.2   42.42  5003.8   42.33
    5004   41.83  5007.5   41.83  5007.8   42.33  5015.8    44.1  5025.9   46.83
  5035.9   49.99  5045.9   53.01    5056   54.23  5063.4    53.7  5068.5   53.76
    5076   53.69  5086.1   55.63  5091.7   55.85
#Mann= 3 , 0 , 0
  4875.8     .17       0  4955.8     .03       0  5035.9     .11       0
Bank Sta=4955.8,5035.9
XS Rating Curve= 0 ,0
Exp/Cntr=0.3,0.1

Type RM Length L Ch R = 1 ,11935   ,486,486,486
BEGIN DESCRIPTION:
Mapping XS 5ce38c51
END DESCRIPTION:
XS GIS Cut Line= 2
      3930818.11      9971840.21      3930823.29      9971634.57
#Sta/Elev= 29
  4876.6   57.46  4878.7   57.46  4885.7   55.64  4895.7   54.19  4905.7   53.89
  4915.7   54.25  4925.7   54.04  4935.8   51.51  4952.8   46.42  4955.8   45.52
 4960.5444.34916  4965.8   43.05  4975.8   42.26  4983.8   41.88    4984   41.38
  4987.5   41.38  4987.8   41.88  4995.8   42.14  5005.8   43.69 5008.49 44.4487
  5015.8   46.51  5025.8    49.9  5035.8      53  5045.8   53.99  5055.8   53.56
  5062.9   54.29  5067.9   54.39  5075.8   56.22  5082.3   55.72
#Mann= 3 , 0 , 0
  4876.6     .17       0  4935.8     .03       0  5025.8     .11       0
Bank Sta=4935.8,5025.8
XS Rating Curve= 0 ,0
Exp/Cntr=0.3,0.1

Type RM Length L Ch R = 1 ,11449   ,407,407,407
BEGIN DESCRIPTION:
G103-52-99 13.0
END DESCRIPTION:
XS GIS Cut Line= 3
      3931317.86       9971861.1      3931298.23      9971736.84
      3931317.86      9971661.04
#Sta/Elev= 30
  4874.2   54.13  4894.5    54.2  4900.2   54.13    4908   54.12  4914.7   54.56
  4924.9   53.81    4935   50.79  4945.1   47.27  4955.2   44.19  4965.3   42.18
  4970.4   42.36  4975.5   41.92  4983.6   41.91  4983.8   41.41  4987.3   41.41
  4987.6   41.91  4995.3   42.05    5000   42.05    5006   44.04  5014.8   47.25
  5019.9   47.36  5026.6   50.85    5037   54.13  5047.3   54.69  5054.4   54.22
  5055.4   54.15  5060.6   54.11  5067.9   54.95  5075.7   56.18  5078.3   56.18
#Mann= 5 ,-1 , 0
  4874.2     .15       0  4900.2     .17       0    4935     .03       0
  5026.6     .11       0  5054.4     .15       0
Bank Sta=4935,5026.6
XS Rating Curve= 0 ,0
Exp/Cntr=0.3,0.1

Type RM Length L Ch R = 1 ,11042   ,382,382,382
BEGIN DESCRIPTION:
Mapping XS 87d3d24d
END DESCRIPTION:
XS GIS Cut Line= 2
      3931698.32      9971870.14      3931697.02      9971680.05
#Sta/Elev= 27
  4886.7   55.36  4888.7   55.36  4895.8   54.81  4905.8   54.46  4915.8   54.58
  4925.8   54.17  4935.8   51.47  4945.8      48  4955.8   44.68  4959.7   43.75
  4965.8   42.29  4983.8   41.96    4984   41.46  4987.5   41.46  4987.8   41.96
  4995.8   42.05  5005.8   43.69  5008.744.53401  5015.8    46.6  5025.8   49.95
  5035.8   53.24  5045.8   54.59  5055.8   54.15  5058.2   54.22  5065.8   54.44
  5073.8   56.23  5076.8   56.23
#Mann= 4 ,-1 , 0
  4886.7     .15       0  4935.8     .03       0  5025.8     .11       0
  5058.2     .15       0
Bank Sta=4935.8,5025.8
XS Rating Curve= 0 ,0
Exp/Cntr=0.3,0.1

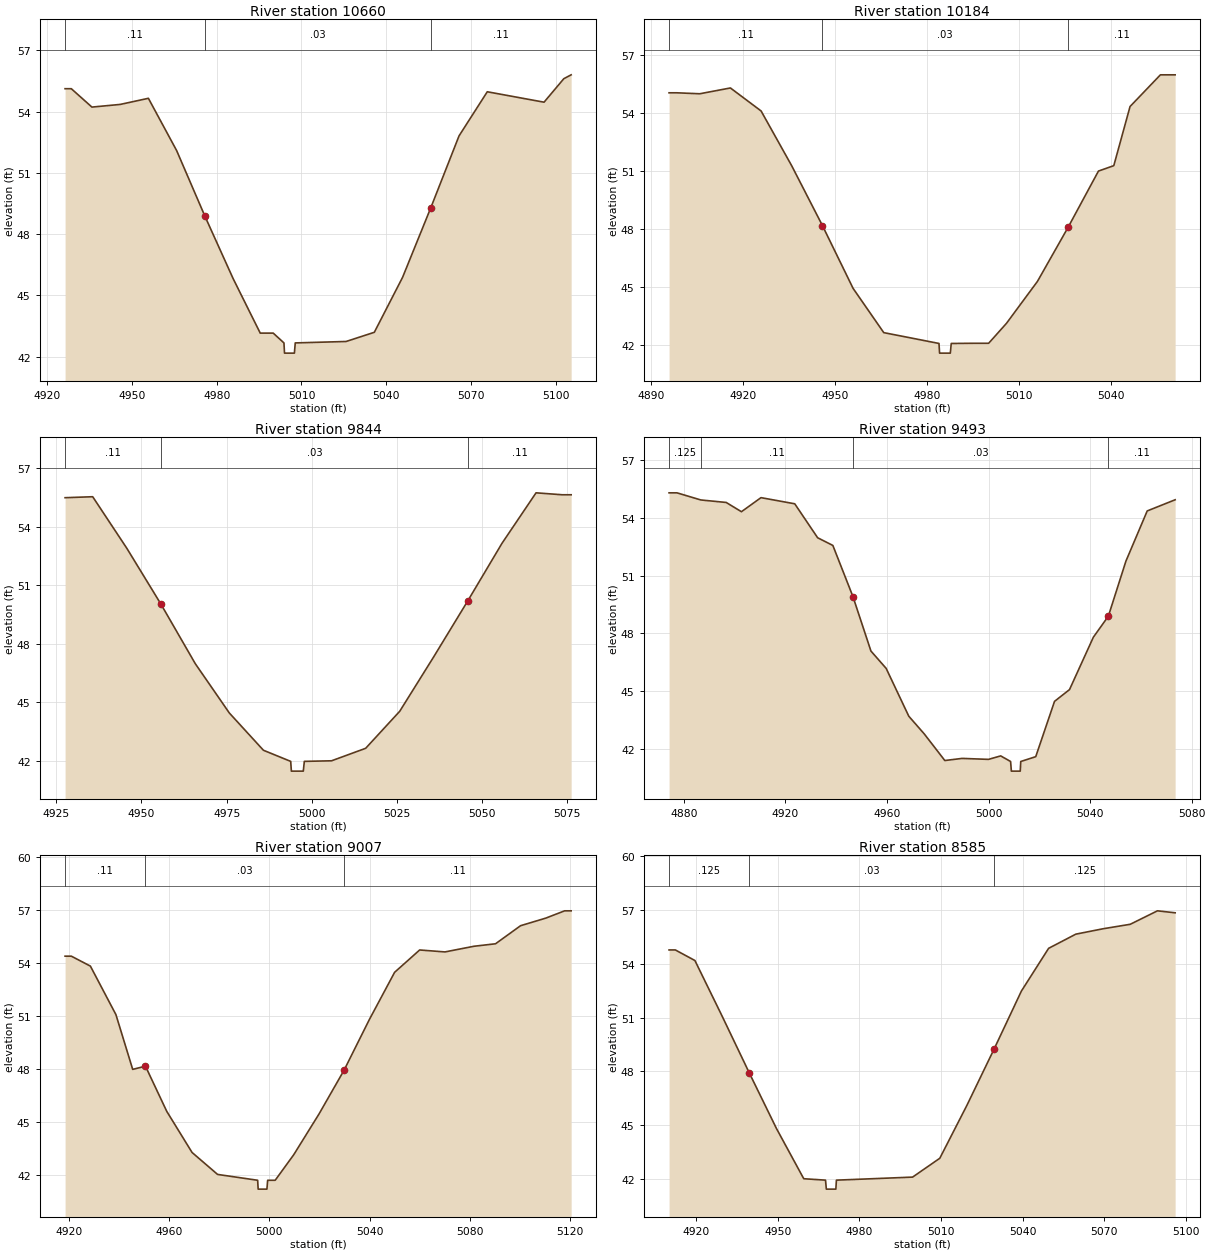
Type RM Length L Ch R = 1 ,10660   ,476,476,476
BEGIN DESCRIPTION:
G103-52-99 11.0
END DESCRIPTION:
XS GIS Cut Line= 3
       3932057.7      9971880.54      3932058.23      9971806.84
      3932062.88      9971701.45
#Sta/Elev= 25
  4926.3   55.12  4928.5   55.12  4935.8   54.22  4945.8   54.35  4955.8   54.65
  4965.8   52.09  4975.8   48.88  4985.8   45.82 4988.8744.96608  4995.4   43.15
    5000   43.15  5003.8   42.67    5004   42.17  5007.5   42.17  5007.8   42.67
  5025.8   42.74  5035.8   43.19  5042.444.96543  5045.8   45.88  5055.8   49.29
  5065.8   52.81  5075.8   54.97  5095.9   54.46  5102.9   55.61  5105.5    55.8
#Mann= 3 , 0 , 0
  4926.3     .11       0  4975.8     .03       0  5055.8     .11       0
Bank Sta=4975.8,5055.8
XS Rating Curve= 0 ,0
Exp/Cntr=0.3,0.1

Type RM Length L Ch R = 1 ,10184   ,340,340,340
BEGIN DESCRIPTION:
G103-52-99 10.0
END DESCRIPTION:
XS GIS Cut Line= 3
      3932517.85      9971911.04      3932518.23      9971806.84
      3932525.14      9971746.44
#Sta/Elev= 26
  4895.8   55.04  4898.3   55.04  4905.8   54.99  4915.8   55.29  4925.8    54.1
  4935.8   51.26  4945.8   48.17  4955.8   44.92 4959.9343.97414  4965.8   42.63
  4975.8   42.32  4983.8   42.07    4984   41.57  4987.5   41.57  4987.8   42.07
  4995.4   42.08    5000   42.08  5005.8   43.11 5010.1744.04892  5015.9   45.28
  5025.9   48.08  5035.8   50.99  5040.8   51.27  5046.1   54.33    5056   55.97
  5060.8   55.97
#Mann= 3 , 0 , 0
  4895.8     .11       0  4945.8     .03       0  5025.9     .11       0
Bank Sta=4945.8,5025.9
XS Rating Curve= 0 ,0
Exp/Cntr=0.3,0.1

Type RM Length L Ch R = 1 ,9844    ,351,351,351
BEGIN DESCRIPTION:
Mapping XS 368a6df5
END DESCRIPTION:
XS GIS Cut Line= 2
      3932842.85       9971909.2      3932848.06      9971760.79
#Sta/Elev= 20
  4927.6   55.48  4935.7   55.53  4945.7   52.89  4955.7   50.03  4965.8   46.97
  4975.8   44.44  4985.8   42.53  4993.8   41.96    4994   41.46  4997.5   41.46
  4997.8   41.96  5005.8   41.99  5015.8   42.63  5025.8   44.53  5035.8   47.33
  5045.8    50.2  5055.8   53.14  5065.8   55.73  5073.5   55.63  5076.1   55.63
#Mann= 3 , 0 , 0
  4927.6     .11       0  4955.7     .03       0  5045.8     .11       0
Bank Sta=4955.7,5045.8
XS Rating Curve= 0 ,0
Exp/Cntr=0.3,0.1

Type RM Length L Ch R = 1 ,9493    ,486,486,486
BEGIN DESCRIPTION:
G103-52-99 8.0
END DESCRIPTION:
XS GIS Cut Line= 3
      3933117.83       9971961.1      3933188.23      9971856.84
      3933227.42      9971794.66
#Sta/Elev= 30
  4874.2   55.29  4877.3   55.29  4886.7   54.92  4896.7   54.79  4902.7   54.31
  4910.4   55.04  4923.7   54.72  4932.7   52.96  4938.7   52.56  4946.6   49.91
  4953.7   47.08  4959.7   46.18  4968.6    43.7  4974.7   42.78  4982.8    41.4
  4989.6   41.51    5000   41.46  5004.8   41.64  5008.7   41.35    5009   40.85
  5012.5   40.85  5012.7   41.35  5018.6    41.6    5026   44.47  5031.9   45.08
  5041.3    47.8  5047.2   48.89  5054.1   51.74  5062.5   54.35  5073.5   54.93
#Mann= 4 ,-1 , 0
  4874.2    .125       0  4886.7     .11       0  4946.6     .03       0
  5047.2     .11       0
Bank Sta=4946.6,5047.2
XS Rating Curve= 0 ,0
Exp/Cntr=0.3,0.1

Type RM Length L Ch R = 1 ,9007    ,422,422,422
BEGIN DESCRIPTION:
G103-52-99 7.0
END DESCRIPTION:
XS GIS Cut Line= 3
      3933217.88      9972311.07      3933298.23      9972296.84
      3933417.89      9972311.08
#Sta/Elev= 27
  4918.4   54.38  4920.9   54.38  4928.5   53.82  4938.7   51.08  4945.4   47.99
  4950.5   48.17    4959   45.62  4969.1    43.3  4979.3   42.06  4995.3   41.73
  4995.5   41.23    4999   41.23  4999.3   41.73  5002.3   41.73  5009.7   43.17
  5019.8   45.47  5029.8   47.94  5039.9    50.8    5050   53.47    5060   54.73
  5070.1   54.62  5081.7   54.94  5090.3   55.08  5100.3    56.1  5110.4   56.53
  5117.9   56.94  5120.5   56.94
#Mann= 3 , 0 , 0
  4918.4     .11       0  4950.5     .03       0  5029.8     .11       0
Bank Sta=4950.5,5029.8
XS Rating Curve= 0 ,0
Exp/Cntr=0.3,0.1

Type RM Length L Ch R = 1 ,8585    ,270,270,270
BEGIN DESCRIPTION:
Mapping XS b68f5219
END DESCRIPTION:
XS GIS Cut Line= 2
      3933198.33      9972706.08      3933384.33      9972707.37
#Sta/Elev= 24
  4910.1   54.77  4912.4   54.77  4919.6   54.18  4929.6   51.08  4939.6   47.91
  4949.6   44.81 4952.7143.94235  4959.6   42.02  4967.6   41.94  4967.9   41.44
  4971.4   41.44  4971.6   41.94  4999.6   42.11  5009.6   43.16 5012.7544.09237
  5019.6   46.12  5029.6   49.26  5039.6   52.48  5049.6   54.86  5059.6   55.65
  5069.6   55.95  5079.6    56.2  5089.6   56.95  5096.1   56.84
#Mann= 3 , 0 , 0
  4910.1    .125       0  4939.6     .03       0  5029.6    .125       0
Bank Sta=4939.6,5029.6
XS Rating Curve= 0 ,0
Exp/Cntr=0.3,0.1

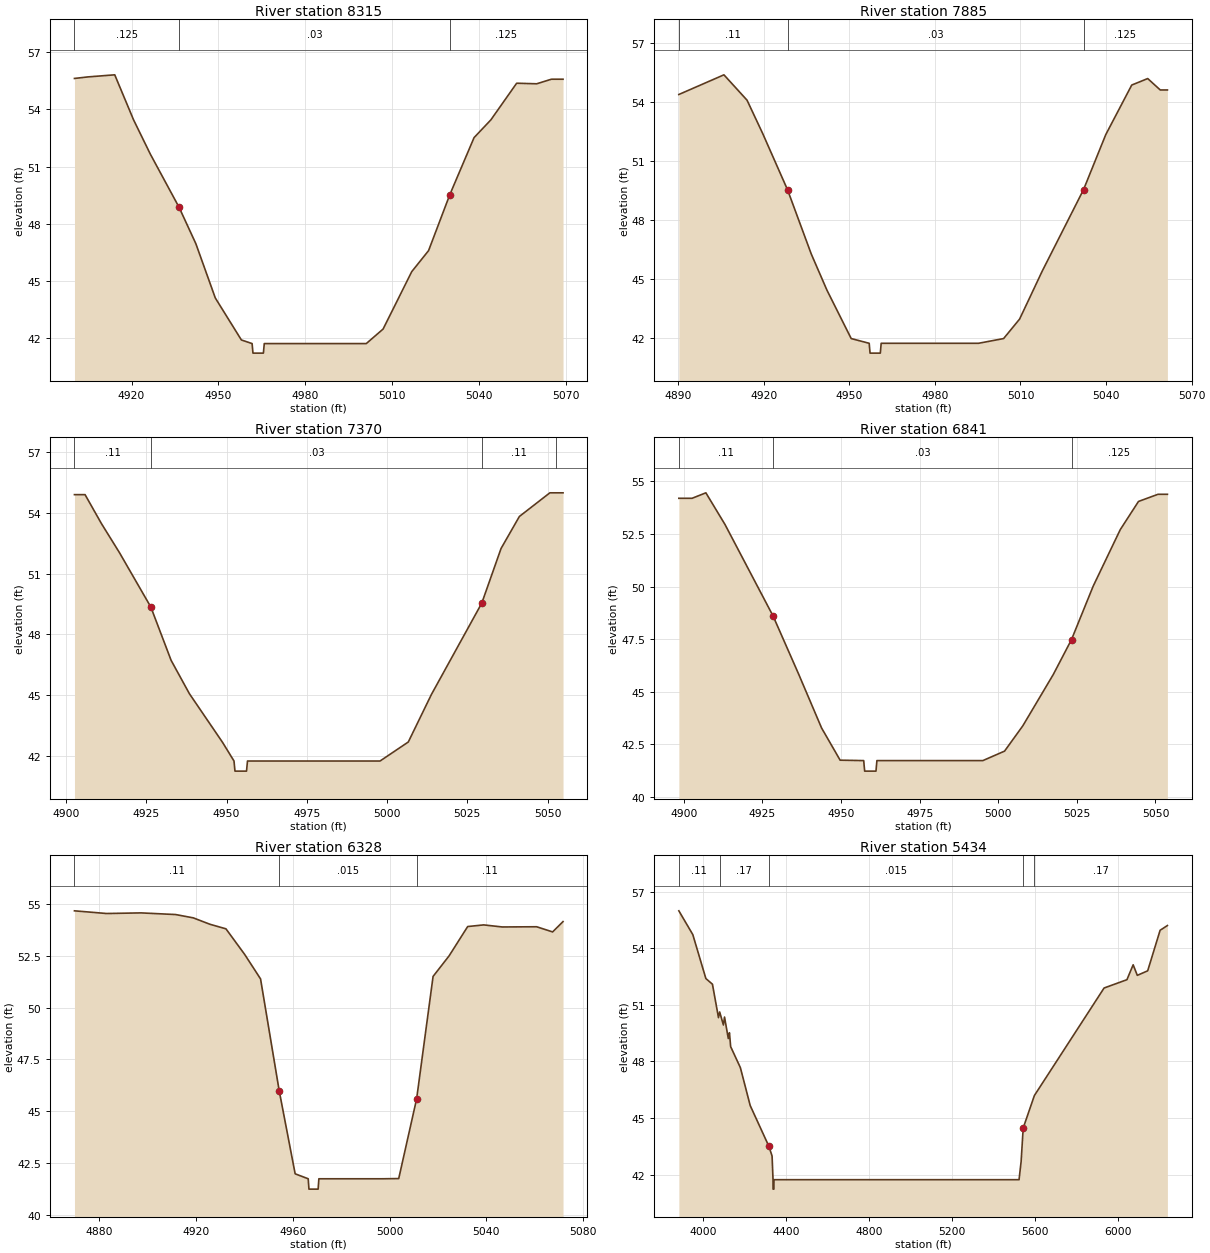
Type RM Length L Ch R = 1 ,8315    ,430,430,430
BEGIN DESCRIPTION:
Mapping XS 72401a65
END DESCRIPTION:
XS GIS Cut Line= 2
      3933422.27      9972943.07       3933506.9      9972797.25
#Sta/Elev= 26
  4900.3   55.62  4904.9    55.7  4914.2   55.81  4920.7   53.45  4926.5   51.65
  4936.4   48.87  4942.2   46.96  4948.9   44.12  4957.9   41.92  4961.6   41.73
  4961.9   41.23  4965.5   41.23  4965.8   41.73  4995.1   41.73    5001   41.73
  5006.8   42.49 5011.6243.95551  5016.7    45.5  5022.5    46.6  5029.8   49.52
  5038.2   52.52    5044   53.45  5052.9   55.37  5059.8   55.34  5064.9   55.58
  5068.9   55.58
#Mann= 3 , 0 , 0
  4900.3    .125       0  4936.4     .03       0  5029.8    .125       0
Bank Sta=4936.4,5029.8
XS Rating Curve= 0 ,0
Exp/Cntr=0.3,0.1

Type RM Length L Ch R = 1 ,7885    ,515,515,515
BEGIN DESCRIPTION:
Mapping XS 19bc098b
END DESCRIPTION:
XS GIS Cut Line= 2
      3933771.24      9973155.29      3933846.76      9973001.65
#Sta/Elev= 23
  4890.3   54.38  4906.1   55.38  4914.2   54.09  4919.7   52.39  4928.4   49.53
  4936.7   46.27  4942.2   44.43  4950.7   41.97    4957   41.73  4957.3   41.23
  4960.9   41.23  4961.2   41.73  4995.3   41.73  5004.1   41.97  5009.7   42.96
    5014   44.28  5017.6   45.39  5032.1   49.54  5039.9   52.34    5049   54.86
  5054.6   55.19    5059   54.61  5061.5   54.61
#Mann= 3 , 0 , 0
  4890.3     .11       0  4928.4     .03       0  5032.1    .125       0
Bank Sta=4928.4,5032.1
XS Rating Curve= 0 ,0
Exp/Cntr=0.3,0.1

Type RM Length L Ch R = 1 ,7370    ,529,529,529
BEGIN DESCRIPTION:
Mapping XS c43ca2b5
END DESCRIPTION:
XS GIS Cut Line= 2
       3934187.9      9973381.87      3934262.15      9973249.01
#Sta/Elev= 23
  4902.6    54.9  4905.9    54.9    4911   53.47  4916.7   52.01  4926.4   49.34
  4932.7   46.71  4938.4   45.06 4944.7543.58041  4948.7   42.66  4952.3   41.73
  4952.6   41.23  4956.2   41.23  4956.5   41.73  4997.8   41.73  5006.6   42.67
 5009.7743.70467  5013.8   45.02  5029.5   49.54  5035.5   52.24  5041.2   53.82
  5050.7   54.99  5052.7   54.99  5054.8   54.99
#Mann= 4 ,-1 , 0
  4902.6     .11       0  4926.4     .03       0  5029.5     .11       0
  5052.7    .125       0
Bank Sta=4926.4,5029.5
XS Rating Curve= 0 ,0
Exp/Cntr=0.3,0.1

Type RM Length L Ch R = 1 ,6841    ,513,513,513
BEGIN DESCRIPTION:
Mapping XS 830465a8
END DESCRIPTION:
XS GIS Cut Line= 2
      3934608.49      9973633.66      3934689.21      9973500.87
#Sta/Elev= 22
  4898.4   54.19  4902.6   54.19    4907   54.45  4913.1   52.94  4928.4   48.59
  4936.5   45.84  4943.8   43.28  4949.7   41.75  4957.2   41.73  4957.5   41.23
  4961.1   41.23  4961.4   41.73  4995.1   41.73    5002   42.18  5007.8   43.38
  5017.5   45.82  5023.3   47.48  5030.2   50.02  5038.8    52.7  5044.6   54.04
  5050.8   54.38  5053.8   54.38
#Mann= 3 , 0 , 0
  4898.4     .11       0  4928.4     .03       0  5023.3    .125       0
Bank Sta=4928.4,5023.3
XS Rating Curve= 0 ,0
Exp/Cntr=0.3,0.1

Type RM Length L Ch R = 1 ,6328    ,894,894,894
BEGIN DESCRIPTION:
Mapping XS 397b5a58
END DESCRIPTION:
XS GIS Cut Line= 2
       3934976.1      9973918.32      3935107.67      9973765.18
#Sta/Elev= 28
  4869.8   54.68  4883.1   54.55  4897.3   54.58  4911.6    54.5  4918.9   54.34
  4925.8   54.03  4932.4   53.81  4940.1   52.58  4946.7   51.39  4954.4   45.99
  4960.142.51812    4961   41.97  4966.4   41.73  4966.7   41.23  4970.5   41.23
  4970.8   41.73  4997.2   41.73  5003.8   41.74  5005.342.52036  5011.2   45.59
    5018   51.51  5024.6    52.5  5032.3   53.92  5038.9      54  5046.6    53.9
  5060.8   53.91  5067.4   53.66  5071.7   54.16
#Mann= 3 , 0 , 0
  4869.8     .11       0  4954.4    .015       0  5011.2     .11       0
Bank Sta=4954.4,5011.2
XS Rating Curve= 0 ,0
Exp/Cntr=0.3,0.1

Type RM Length L Ch R = 1 ,5434    ,0,0,0
BEGIN DESCRIPTION:
G103-52-99 1.0
END DESCRIPTION:
XS GIS Cut Line= 3
      3934817.85      9974611.07      3935844.91      9974175.46
      3935865.75      9972935.96
#Sta/Elev= 30
    3882   55.98  3949.3   54.72  4012.3   52.39    4044   52.09  4073.1   50.32
  4078.8   50.62  4096.8   49.93  4102.2   50.35  4120.4   49.21  4125.9   49.52
  4131.8   48.78  4178.6   47.67    4226   45.66  4316.5   43.49  4331.5   42.98
    4336   41.73  4336.3   41.23  4340.2   41.23  4340.5   41.73  5522.1   41.73
  5532.1    42.7  5542.1   44.47    5596   46.19  5932.1   51.89  6042.2   52.33
  6072.2   53.12  6092.2   52.56  6142.2    52.8  6202.2   54.95  6237.3    55.2
#Mann= 5 ,-1 , 0
    3882     .11       0  4078.8     .17       0  4316.5    .015       0
  5542.1     .11       0    5596     .17       0
Bank Sta=4316.5,5542.1
XS Rating Curve= 0 ,0
Exp/Cntr=0.3,0.1

Chan Stop Cuts=-1
Use User Specified Reach Order=0
Composite Channel Slope=5