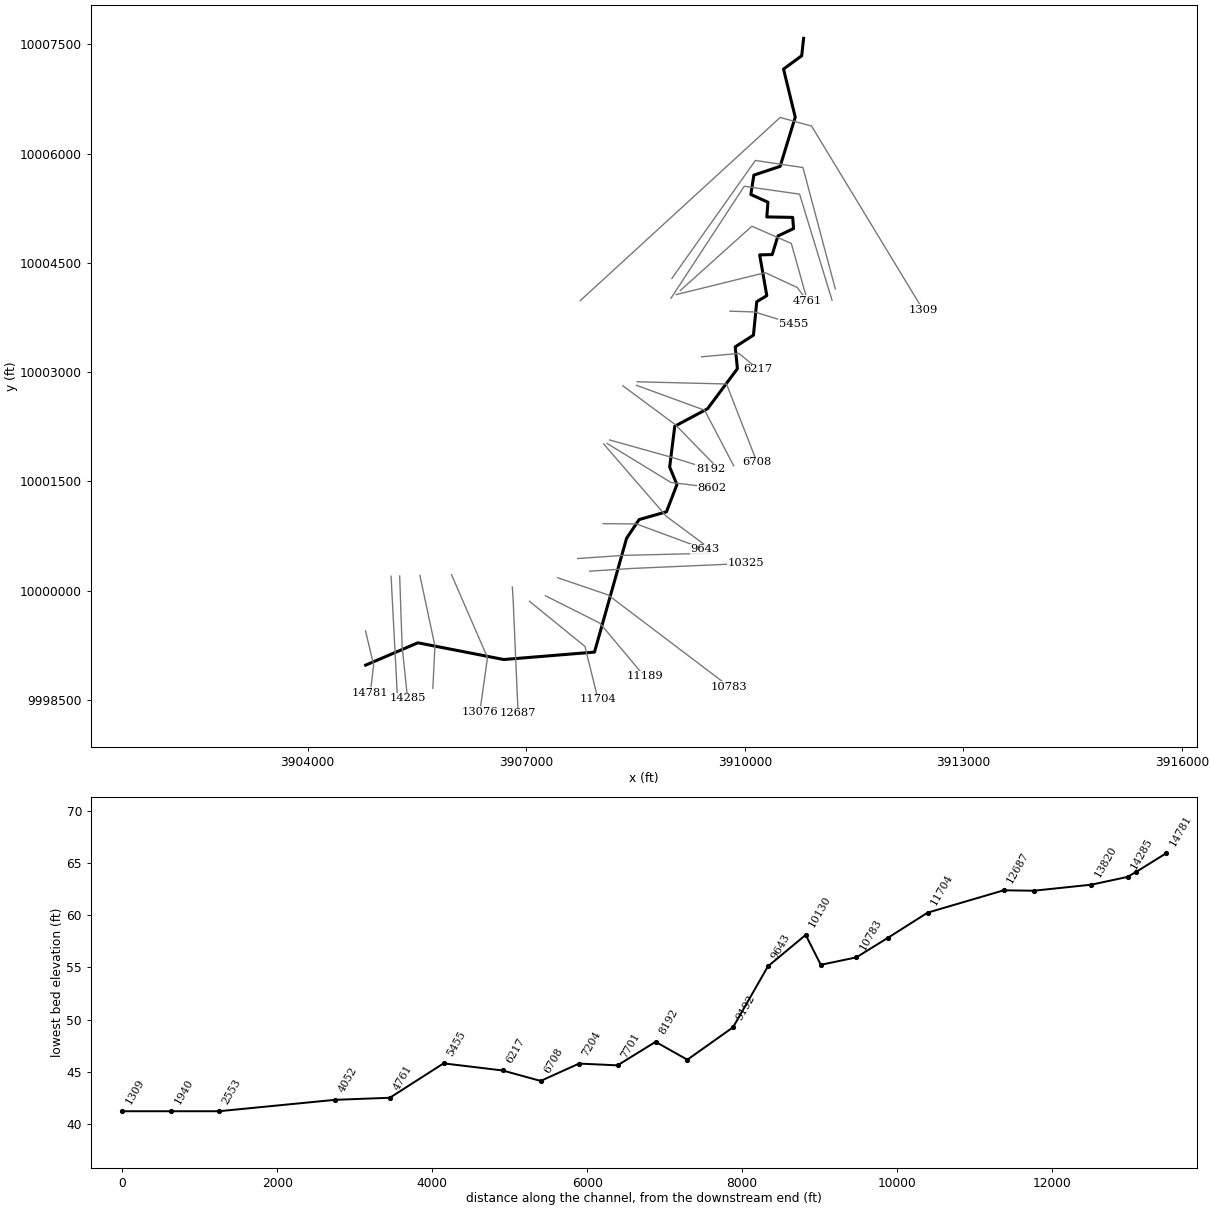
--- JORDAN GULLY.prj (project) ---

Proj Title=JORDAN GULLY Base Level Engineering
Current Plan=p01
Default Exp/Contr=0.3,0.1
English Units
Geom File=g01
Flow File=f01
Flow File=f02
Plan File=p01
Y Axis Title=Elevation
X Axis Title(PF)=Main Channel Distance
X Axis Title(XS)=Station
BEGIN DESCRIPTION:
JORDAN GULLY
END DESCRIPTION:
DSS Export Rating Curves= 0
DSS Export Rating Curve Sorted= 0
DSS Export Volume Flow Curves= 0
DXF OffsetX= 0
DXF OffsetY= 0
DXF ScaleX= 1
DXF ScaleY= 10

--- JORDAN GULLY.p01 (plan) ---

Plan Title=Multiple Run
Short Identifier=Multiple
Geom File=g01
Flow File=f01
Subcritical Flow
K Sum by GR= 0
Std Step Tol= 0.01
Critical Tol= 0.01
Num of Std Step Trials= 20
Max Error Tol= 0.3
Flow Tol Ratio= 0.001
Split Flow NTrial= 30
Split Flow Tol= 0.02
Split Flow Ratio= 0.02
Log Output Level= 0
Friction Slope Method= 1
Unsteady Friction Slope Method= 2
Unsteady Bridges Friction Slope Method= 1
Parabolic Critical Depth
Global Vel Dist=  1 , 1 , 1
Global Log Level= 0
CheckData=True
Encroach Param= -1, 0, 0, 0
BEGIN DESCRIPTION:
Multiple Run
END DESCRIPTION:

--- JORDAN GULLY.f01 (steady flow) ---

Flow Title=Multiple
Program Version=4.10
Number of Profiles= 7
Profile Names=10-year,25-year,50-year,1pct_min,100-year,1pct_plu,500-year
River Rch & RM=JORDAN GULLY,Reach-1         ,14781
     174     212     268     112     338    1021     556
River Rch & RM=JORDAN GULLY,Reach-1         ,12687
     465     612     813     356    1076    3249    1957
River Rch & RM=JORDAN GULLY,Reach-1         ,11704
     723     973    1312     583    1760    5315    3292
River Rch & RM=JORDAN GULLY,Reach-1         ,6217
    1345    1837    2497    1112    3359   10144    6281
Boundary for River Rch & Prof#=JORDAN GULLY,Reach-1         , 1
Up Type= 0
Dn Type= 3
Dn Slope=0.0006
Boundary for River Rch & Prof#=JORDAN GULLY,Reach-1         , 2
Up Type= 0
Dn Type= 3
Dn Slope=0.0006
Boundary for River Rch & Prof#=JORDAN GULLY,Reach-1         , 3
Up Type= 0
Dn Type= 3
Dn Slope=0.0006
Boundary for River Rch & Prof#=JORDAN GULLY,Reach-1         , 4
Up Type= 0
Dn Type= 3
Dn Slope=0.0006
Boundary for River Rch & Prof#=JORDAN GULLY,Reach-1         , 5
Up Type= 0
Dn Type= 3
Dn Slope=0.0006
Boundary for River Rch & Prof#=JORDAN GULLY,Reach-1         , 6
Up Type= 0
Dn Type= 3
Dn Slope=0.0006
Boundary for River Rch & Prof#=JORDAN GULLY,Reach-1         , 7
Up Type= 0
Dn Type= 3
Dn Slope=0.0006
DSS Import GetInterval= 0
DSS Import GetPeak= 0
DSS Import FillOption= 0

--- JORDAN GULLY.f02 (steady flow) ---

Flow Title=Orig_BLE_Flows
Program Version=4.10
Number of Profiles= 7
Profile Names=10-year,25-year,50-year,1pct_min,100-year,1pct_plu,500-year
River Rch & RM=JORDAN GULLY,Reach-1         ,14781
     174     208     233      86     260     785     323
River Rch & RM=JORDAN GULLY,Reach-1         ,12687
     465     600     707     274     828    2500    1138
River Rch & RM=JORDAN GULLY,Reach-1         ,11704
     723     954    1141     448    1354    4090    1914
River Rch & RM=JORDAN GULLY,Reach-1         ,6217
    1345    1801    2171     856    2584    7802    3652
Boundary for River Rch & Prof#=JORDAN GULLY,Reach-1         , 1
Up Type= 0
Dn Type= 3
Dn Slope=0.0006
Boundary for River Rch & Prof#=JORDAN GULLY,Reach-1         , 2
Up Type= 0
Dn Type= 3
Dn Slope=0.0006
Boundary for River Rch & Prof#=JORDAN GULLY,Reach-1         , 3
Up Type= 0
Dn Type= 3
Dn Slope=0.0006
Boundary for River Rch & Prof#=JORDAN GULLY,Reach-1         , 4
Up Type= 0
Dn Type= 3
Dn Slope=0.0006
Boundary for River Rch & Prof#=JORDAN GULLY,Reach-1         , 5
Up Type= 0
Dn Type= 3
Dn Slope=0.0006
Boundary for River Rch & Prof#=JORDAN GULLY,Reach-1         , 6
Up Type= 0
Dn Type= 3
Dn Slope=0.0006
Boundary for River Rch & Prof#=JORDAN GULLY,Reach-1         , 7
Up Type= 0
Dn Type= 3
Dn Slope=0.0006
DSS Import GetInterval= 0
DSS Import GetPeak= 0
DSS Import FillOption= 0

--- JORDAN GULLY.g01 (geometry) ---

Geom Title=Existing Conditions
Program Version=4.10

River Reach=JORDAN GULLY    ,Reach-1
Reach XY= 30
      3904796.25      9998978.41      3905512.48      9999284.85
      3906691.41       9999055.3      3907936.63      9999157.14
      3908377.34     10000719.98      3908549.26     10000976.05
       3908924.5     10001083.04      3909068.23     10001456.84
      3908968.23     10001696.84      3909038.23     10002256.84
      3909488.23     10002496.84      3909898.23     10003046.84
      3909868.23     10003346.84      3910118.23     10003506.84
      3910163.53     10003965.84      3910301.55     10004049.17
      3910203.89     10004609.07      3910375.76     10004612.98
      3910453.89     10004868.19      3910668.73     10004969.75
      3910657.01     10005123.39      3910301.55      10005129.9
      3910317.17     10005331.73      3910082.46     10005437.65
      3910123.74      10005703.3      3910484.53     10005823.56
      3910691.72     10006499.54      3910531.19     10007158.99
      3910780.69     10007342.08      3910806.78     10007580.83

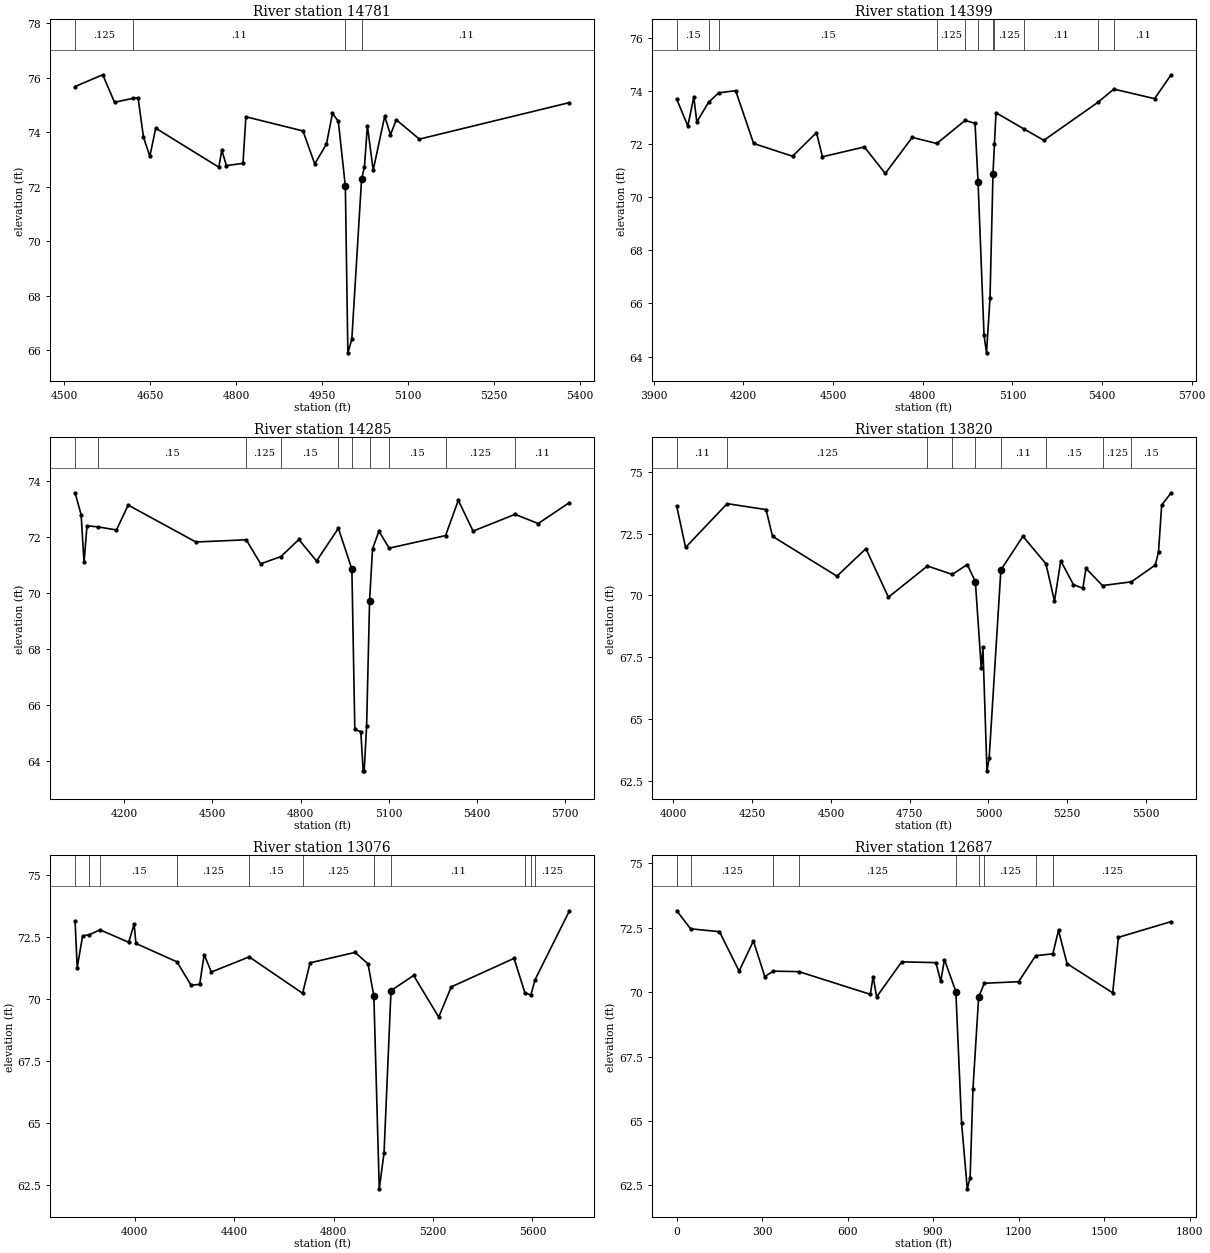
Type RM Length L Ch R = 1 ,14781   ,382,382,382
BEGIN DESCRIPTION:
JORDAN GULLY 22.0
END DESCRIPTION:
XS GIS Cut Line= 3
      3904794.14      9999448.05      3904905.71      9998980.16
      3904860.11       9998600.9
#Sta/Elev= 30
    4519   75.67  4567.3    76.1  4587.9   75.09  4620.9   75.24    4629   75.25
  4638.4   73.81  4649.5   73.11  4659.8   74.14  4769.9   72.71  4775.1   73.33
  4783.2   72.77  4812.1   72.85  4817.2   74.56  4916.8   74.04  4937.4   72.83
  4957.9   73.56  4968.2   74.68  4978.5    74.4  4990.8   72.01  4995.2    65.9
  5002.1    66.4  5019.1   72.26  5024.1   72.72  5029.3   74.23  5039.4    72.6
  5059.5   74.58  5069.6    73.9  5079.7   74.45    5120   73.74    5382   75.08
#Mann= 4 ,-1 , 0
    4519    .125       0  4620.9     .11       0  4990.8     .07       0
  5019.1     .11       0
Bank Sta=4990.8,5019.1
XS Rating Curve= 0 ,0
Exp/Cntr=0.3,0.1

Type RM Length L Ch R = 1 ,14399   ,114,114,114
BEGIN DESCRIPTION:
Mapping XS 2c1a6e4d
END DESCRIPTION:
XS GIS Cut Line= 2
      3905144.83     10000198.05      3905231.61      9998545.72
#Sta/Elev= 30
  3976.7    73.7  4013.7   72.69  4033.8   73.78  4043.8   72.84    4083   73.58
    4117   73.94  4173.9   74.02    4234   72.03  4364.2   71.55  4444.3   72.44
  4464.3   71.53  4604.5    71.9  4674.6    70.9  4764.8   72.26  4847.3   72.03
  4941.7    72.9    4975   72.79  4985.1   70.59  5005.1   64.81  5013.4   64.14
  5025.1    66.2  5035.1   70.89    5040   72.02  5045.1   73.19  5138.4   72.58
  5205.4   72.15    5386   73.58  5439.7   74.08  5575.9   73.72  5631.3   74.62
#Mann= 11 ,-1 , 0
  3976.7     .15       0    4083    .125       0    4117     .15       0
  4847.3    .125       0  4941.7     .11       0  4985.1     .06       0
  5035.1     .11       0    5040    .125       0  5138.4     .11       0
    5386    .125       0  5439.7     .11       0
Bank Sta=4985.1,5035.1
XS Rating Curve= 0 ,0
Exp/Cntr=0.3,0.1

Type RM Length L Ch R = 1 ,14285   ,465,465,465
BEGIN DESCRIPTION:
JORDAN GULLY 21.0
END DESCRIPTION:
XS GIS Cut Line= 3
      3905262.88     10000201.59      3905296.34      9999235.37
      3905370.44      9998525.23
#Sta/Elev= 30
  4033.2   73.59  4053.7   72.81  4063.7    71.1  4073.7   72.41  4112.3   72.37
  4173.8   72.26  4213.8   73.15    4444   71.83  4615.1   71.91  4664.1   71.05
  4733.2   71.31  4794.2   71.92  4854.2   71.15  4928.4   72.32  4974.3   70.86
  4984.3   65.13  5004.7   65.05  5012.6   63.65  5016.1   63.65  5024.4   65.25
  5034.5   69.73  5044.5   71.58  5066.2   72.22    5101   71.61  5292.8   72.06
  5336.1   73.32  5386.4   72.22  5529.2   72.82  5607.6   72.49    5714   73.24
#Mann= 10 ,-1 , 0
  4033.2    .125       0  4112.3     .15       0  4615.1    .125       0
  4733.2     .15       0  4928.4    .125       0  4974.3     .04       0
  5034.5    .125       0    5101     .15       0  5292.8    .125       0
  5529.2     .11       0
Bank Sta=4974.3,5034.5
XS Rating Curve= 0 ,0
Exp/Cntr=0.3,0.1

Type RM Length L Ch R = 1 ,13820   ,744,744,744
BEGIN DESCRIPTION:
JORDAN GULLY 20.0
END DESCRIPTION:
XS GIS Cut Line= 3
      3905540.67     10000208.46      3905746.86      9999240.58
      3905717.85      9998661.11
#Sta/Elev= 30
  4010.4    73.6  4038.4   71.94  4170.4   73.71    4294   73.47  4314.5   72.39
    4519   70.78    4611   71.89  4682.5   69.93  4806.3   71.19  4885.3   70.85
  4932.9   71.25  4958.6   70.56  4977.4   67.05  4982.5   67.91  4995.4   62.91
  5002.3   63.41  5039.6   71.03  5109.6   72.39  5182.7   71.28  5209.8   69.77
  5229.8    71.4  5269.8   70.44  5299.9   70.29  5309.9   71.09  5362.3    70.4
  5453.9   70.55  5530.2   71.23  5540.2   71.77  5550.2   73.65  5580.2   74.15
#Mann= 9 ,-1 , 0
  4010.4     .11       0  4170.4    .125       0  4806.3     .15       0
  4885.3    .125       0  4958.6     .04       0  5039.6     .11       0
  5182.7     .15       0  5362.3    .125       0  5453.9     .15       0
Bank Sta=4958.6,5039.6
XS Rating Curve= 0 ,0
Exp/Cntr=0.3,0.1

Type RM Length L Ch R = 1 ,13076   ,389,389,389
BEGIN DESCRIPTION:
JORDAN GULLY 19.0
END DESCRIPTION:
XS GIS Cut Line= 3
      3905974.67     10000218.95      3906468.21      9999081.73
      3906363.58      9998340.48
#Sta/Elev= 30
  3760.3   73.13  3768.9   71.26  3790.7   72.54  3816.9   72.58  3860.7   72.78
    3976   72.28  3997.8   73.01  4005.1   72.23  4169.9   71.49  4226.7   70.55
  4261.5   70.58  4279.5   71.78  4308.4   71.08  4460.6   71.69  4675.4   70.22
  4705.6   71.45  4886.2   71.87  4938.5   71.41    4962    70.1  4983.7   62.33
  5002.9   63.78    5031   70.33  5121.9   70.94  5222.8   69.26  5273.3   70.48
  5525.8   71.63  5569.8   70.23  5593.7   70.15  5609.8   70.76  5748.6   73.55
#Mann= 11 ,-1 , 0
  3760.3     .15       0  3816.9    .125       0  3860.7     .15       0
  4169.9    .125       0  4460.6     .15       0  4675.4    .125       0
    4962     .04       0    5031     .11       0  5569.8    .125       0
  5593.7     .15       0  5609.8    .125       0
Bank Sta=4962,5031
XS Rating Curve= 0 ,0
Exp/Cntr=0.3,0.1

Type RM Length L Ch R = 1 ,12687   ,983,983,983
BEGIN DESCRIPTION:
Mapping XS 14336fcc
END DESCRIPTION:
XS GIS Cut Line= 3
       3906808.9     10000049.59      3906818.85      9999903.77
      3906887.88      9998316.14
#Sta/Elev= 30
       0   73.15    48.6   72.45     150   72.34   218.9   70.81     269   71.98
     309    70.6     339   70.81   429.1   70.79   679.4   69.91   689.4    70.6
   701.5   69.81   789.5   71.17   909.6   71.14   926.7   70.41   939.6   71.26
   979.6   70.02   999.7   64.94  1019.7   62.37  1029.7    62.8  1039.7   66.24
  1059.7   69.81  1079.7   70.34  1199.9    70.4  1259.9   71.41    1320   71.48
    1340   72.39    1370    71.1  1530.2   69.97  1550.2   72.12  1735.3   72.73
#Mann= 9 ,-1 , 0
       0     .15       0    48.6    .125       0     339     .11       0
   429.1    .125       0   979.6     .04       0  1059.7     .11       0
  1079.7    .125       0  1259.9     .15       0    1320    .125       0
Bank Sta=979.6,1059.7
XS Rating Curve= 0 ,0
Exp/Cntr=0.3,0.1

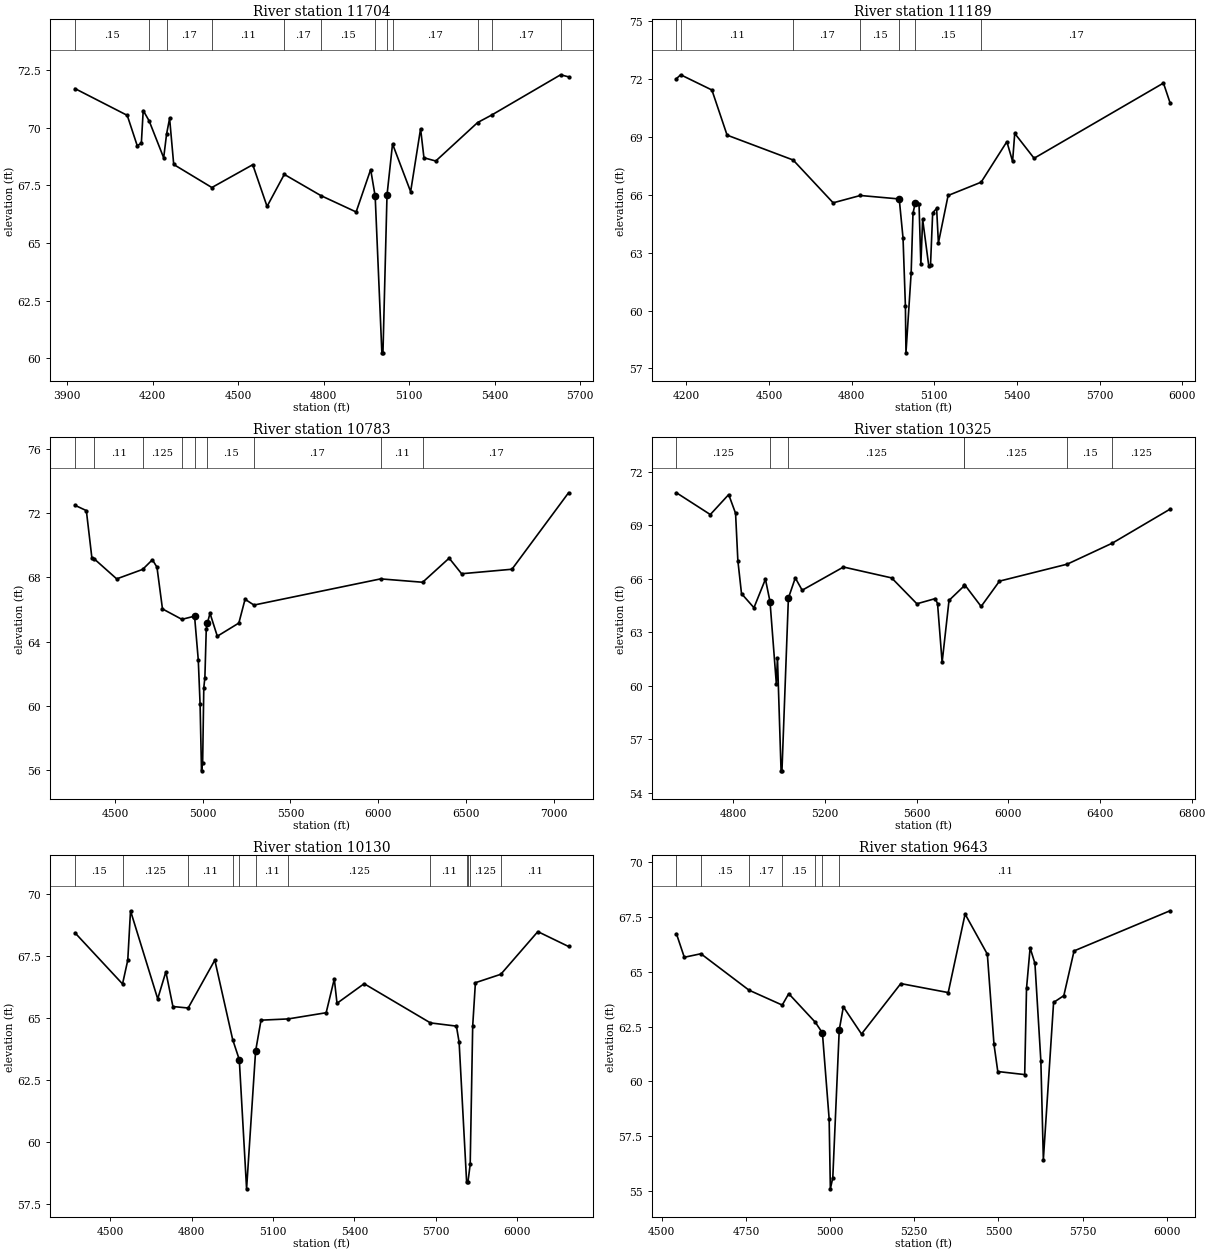
Type RM Length L Ch R = 1 ,11704   ,515,515,515
BEGIN DESCRIPTION:
JORDAN GULLY 18.0
END DESCRIPTION:
XS GIS Cut Line= 3
      3907044.11      9999854.36      3907805.71      9999235.11
      3907985.11      9998507.07
#Sta/Elev= 30
    3928   71.69  4111.2   70.53  4146.3   69.21  4160.7   69.33  4167.2   70.74
    4188   70.29    4239   68.69  4249.2   69.72  4259.8    70.4  4274.2    68.4
  4408.1    67.4  4551.5   68.39  4601.7   66.58  4662.1   67.97  4790.5   67.05
  4914.2   66.34  4965.2   68.18    4981   67.02  5004.5   60.23  5008.3   60.23
  5022.5   67.07  5041.9   69.29  5105.4   67.22  5140.3   69.95  5152.1   68.69
  5193.6   68.55  5340.5   70.22  5389.2   70.54  5631.6   72.29  5659.4    72.2
#Mann= 12 ,-1 , 0
    3928     .15       0    4188     .11       0  4249.2     .17       0
  4408.1     .11       0  4662.1     .17       0  4790.5     .15       0
    4981     .09       0  5022.5     .15       0  5041.9     .17       0
  5340.5     .11       0  5389.2     .17       0  5631.6     .11       0
Bank Sta=4981,5022.5
XS Rating Curve= 0 ,0
Exp/Cntr=0.3,0.1

Type RM Length L Ch R = 1 ,11189   ,406,406,406
BEGIN DESCRIPTION:
JORDAN GULLY 17.0
END DESCRIPTION:
XS GIS Cut Line= 3
      3907262.88      9999930.73      3908009.97      9999555.12
      3908624.02      9998823.05
#Sta/Elev= 30
  4163.8   72.03  4179.1   72.23  4292.5   71.44  4347.6    69.1  4587.4   67.81
  4732.7   65.59  4831.4   65.97  4972.6   65.79  4986.4   63.76    4995   60.24
    4997   57.81  5015.9   61.96  5022.5   65.04  5030.2   65.56  5044.4   65.54
  5051.1    62.4  5057.6   64.73  5079.7   62.33  5086.2   62.38    5094   65.07
  5108.3    65.3  5114.8   63.51    5150   65.97    5270   66.66  5363.3   68.76
  5384.1   67.74  5391.9   69.19  5462.2    67.9  5931.8    71.8  5955.5   70.79
#Mann= 7 ,-1 , 0
  4163.8     .15       0  4179.1     .11       0  4587.4     .17       0
  4831.4     .15       0  4972.6     .09       0  5030.2     .15       0
    5270     .17       0
Bank Sta=4972.6,5030.2
XS Rating Curve= 0 ,0
Exp/Cntr=0.3,0.1

Type RM Length L Ch R = 1 ,10783   ,458,458,458
BEGIN DESCRIPTION:
JORDAN GULLY 16.0
END DESCRIPTION:
XS GIS Cut Line= 3
      3907433.04     10000177.25      3908121.46      9999942.94
      3909783.73      9998684.18
#Sta/Elev= 30
  4272.8   72.48  4337.3   72.15  4368.6   69.23  4383.7   69.13  4510.3    67.9
  4658.1   68.49  4713.6   69.09  4739.7   68.63  4771.1   66.03  4881.8   65.38
  4953.9   65.58  4975.1   62.86  4985.3   60.14  4993.5   55.95    5000   56.45
  5006.6   61.13  5012.8   61.76  5020.6   64.76  5027.4   65.16  5041.9   65.76
  5083.6   64.33  5206.3   65.15  5241.7   66.63  5292.5   66.27  6014.3    67.9
  6253.7   67.69  6404.7   69.19  6475.6   68.22  6762.6    68.5  7085.1   73.26
#Mann= 9 ,-1 , 0
  4272.8    .125       0  4383.7     .11       0  4658.1    .125       0
  4881.8     .15       0  4953.9     .09       0  5027.4     .15       0
  5292.5     .17       0  6014.3     .11       0  6253.7     .17       0
Bank Sta=4953.9,5027.4
XS Rating Curve= 0 ,0
Exp/Cntr=0.3,0.1

Type RM Length L Ch R = 1 ,10325   ,195,195,195
BEGIN DESCRIPTION:
JORDAN GULLY 15.0
END DESCRIPTION:
XS GIS Cut Line= 3
      3907870.49     10000267.53      3908437.66     10000304.56
      3910020.96       10000374.
#Sta/Elev= 30
  4552.2   70.82  4699.9    69.6  4780.1   70.72  4810.1   69.67  4820.1   67.02
    4836   65.17  4890.3   64.38  4940.4   65.98  4960.4   64.72  4987.9   60.13
  4992.9   61.57  5008.6   55.24  5012.5   55.24  5040.6   64.92  5070.7   66.05
  5100.7   65.36  5280.9   66.66  5491.1   66.05  5601.2    64.6  5681.3   64.89
  5691.3   64.61  5711.3   61.32  5741.4   64.79  5807.2    65.6  5808.9   65.68
  5881.5   64.45  5961.6   65.87  6257.1   66.82  6454.2      68  6705.4    69.9
#Mann= 7 ,-1 , 0
  4552.2    .125       0  4960.4     .09       0  5040.6    .125       0
  5807.2     .11       0  5808.9    .125       0  6257.1     .15       0
  6454.2    .125       0
Bank Sta=4960.4,5040.6
XS Rating Curve= 0 ,0
Exp/Cntr=0.3,0.1

Type RM Length L Ch R = 1 ,10130   ,487,487,487
BEGIN DESCRIPTION:
JORDAN GULLY 14.0
END DESCRIPTION:
XS GIS Cut Line= 3
      3907703.87     10000441.14      3908340.43     10000485.11
      3909521.03     10000512.89
#Sta/Elev= 30
  4370.1   68.42  4545.2   66.36  4564.5   67.32  4574.6   69.31  4674.8   65.76
  4704.9   66.85  4730.9   65.45  4787.1   65.39  4885.3   67.32  4951.1   64.12
  4975.5   63.31  5002.4    58.1  5035.6   63.65  5055.6    64.9  5155.6   64.95
  5295.7    65.2  5325.7   66.56  5335.7   65.58  5435.7   66.37    5680   64.79
  5775.8   64.66  5785.8   64.01  5813.5   58.36  5818.1   58.36  5826.6   59.09
  5835.8   64.66  5845.8   66.41  5939.5   66.75  6075.9   68.47  6189.1   67.87
#Mann= 12 ,-1 , 0
  4370.1     .15       0  4545.2    .125       0  4787.1     .11       0
  4951.1    .125       0  4975.5     .09       0  5035.6     .11       0
  5155.6    .125       0    5680     .11       0  5813.5     .12       0
  5818.1     .11       0  5826.6    .125       0  5939.5     .11       0
Bank Sta=4975.5,5035.6
XS Rating Curve= 0 ,0
Exp/Cntr=0.3,0.1

Type RM Length L Ch R = 1 ,9643    ,451,451,451
BEGIN DESCRIPTION:
JORDAN GULLY 13.0
END DESCRIPTION:
XS GIS Cut Line= 3
      3908054.52     10000920.31      3908514.04     10000915.67
      3909457.32     10000566.14
#Sta/Elev= 30
  4543.8   66.73  4567.1   65.66  4616.4   65.82  4759.2   64.16  4857.9   63.48
  4877.2      64  4956.5   62.69  4977.2   62.21  4997.2   58.29  5000.8    55.1
    5008    55.6  5027.2   62.35  5039.4    63.4  5093.3   62.16    5210   64.46
  5350.8   64.05  5400.9   67.63    5467    65.8  5486.7   61.69    5498   60.45
  5577.9   60.31  5583.3   64.24    5594   66.09  5608.3   65.38  5625.9   60.93
  5633.3   56.43  5663.7    63.6  5694.1   63.91  5724.5   65.95  6009.3   67.78
#Mann= 7 ,-1 , 0
  4543.8     .17       0  4616.4     .15       0  4759.2     .17       0
  4857.9     .15       0  4956.5     .11       0  4977.2     .07       0
  5027.2     .11       0
Bank Sta=4977.2,5027.2
XS Rating Curve= 0 ,0
Exp/Cntr=0.3,0.1

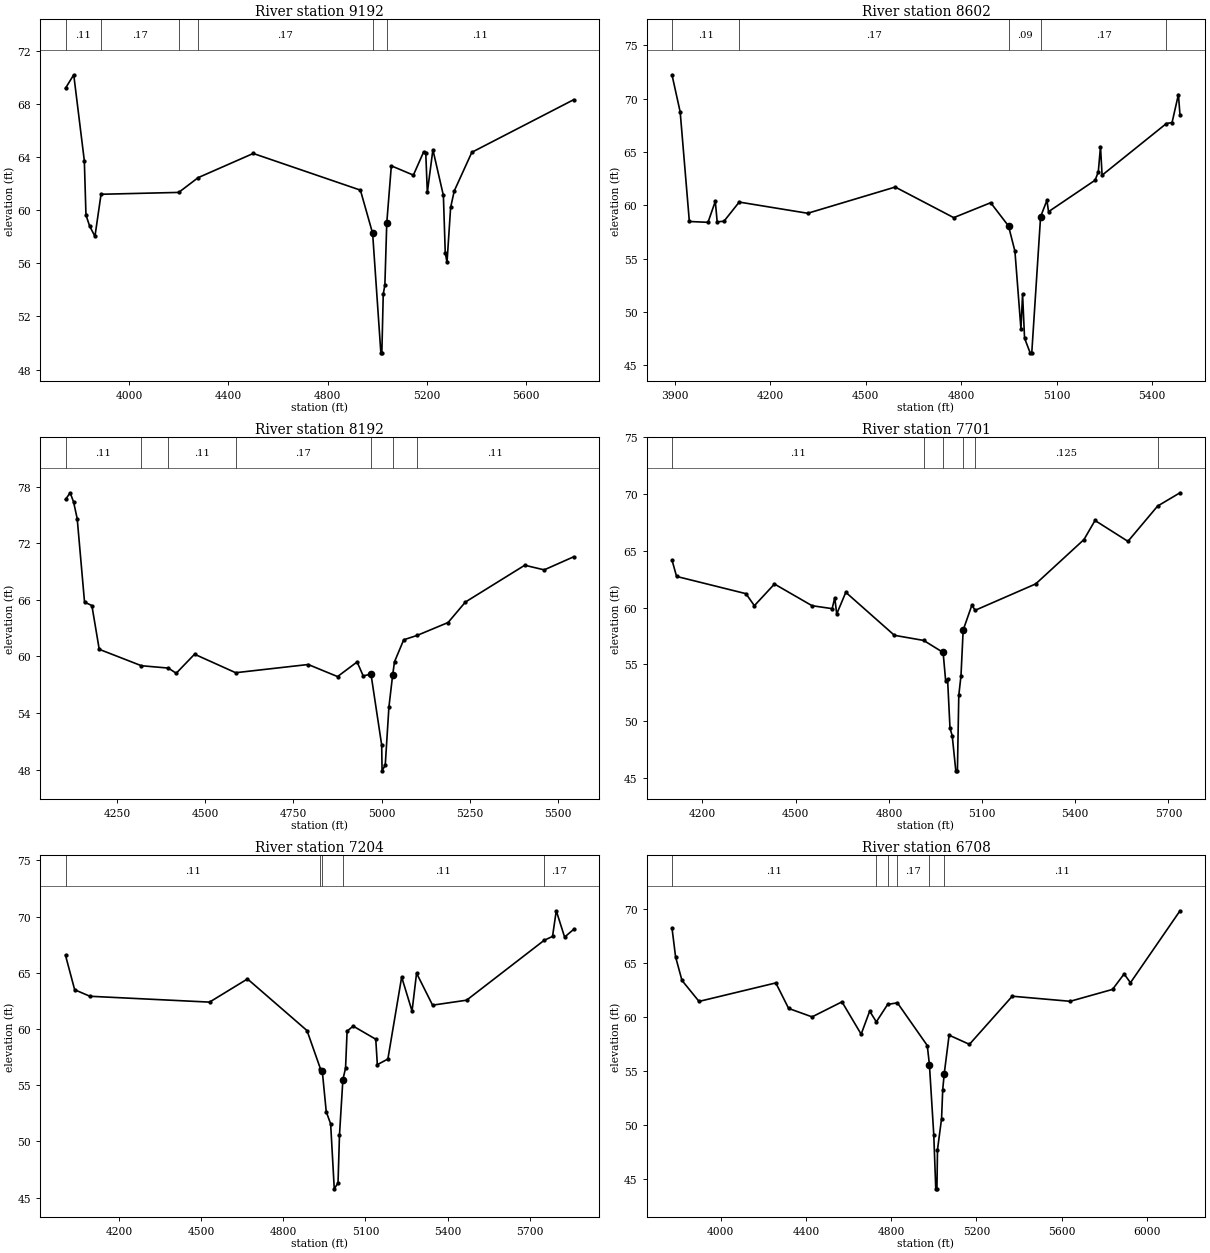
Type RM Length L Ch R = 1 ,9192    ,590,590,590
BEGIN DESCRIPTION:
JORDAN GULLY 12.0
END DESCRIPTION:
XS GIS Cut Line= 3
      3908062.65      10002012.9      3908923.77     10001019.84
      3909513.44     10000582.79
#Sta/Elev= 30
  3743.6   69.17  3776.8   70.18  3819.5   63.71  3826.1   59.63  3840.4   58.82
  3862.3   58.02  3886.9   61.19  4200.1   61.33  4278.3   62.44  4500.5   64.26
  4932.6    61.5  4981.9   58.25  5015.1   49.26  5019.1   49.26  5024.7   53.67
  5031.3   54.37  5038.9   59.03  5057.3   63.33  5146.2   62.63  5187.9   64.39
  5196.2   64.26  5202.5   61.33  5224.9   64.54  5267.2    61.1  5274.7    56.8
  5281.8   56.06  5296.4    60.2    5311   61.44    5382   64.35    5792    68.3
#Mann= 6 ,-1 , 0
  3743.6     .11       0  3886.9     .17       0  4200.1     .11       0
  4278.3     .17       0  4981.9     .09       0  5038.9     .11       0
Bank Sta=4981.9,5038.9
XS Rating Curve= 0 ,0
Exp/Cntr=0.3,0.1

Type RM Length L Ch R = 1 ,8602    ,410,410,410
BEGIN DESCRIPTION:
JORDAN GULLY 11.0
END DESCRIPTION:
XS GIS Cut Line= 3
      3908111.29     10002019.82      3908986.27     10001485.11
      3909552.64     10001416.04
#Sta/Elev= 30
    3892   72.24  3917.8   68.75  3946.6   58.48  4005.2    58.4  4028.1   60.37
    4034   58.45  4055.3    58.5  4103.2    60.3  4318.4   59.25  4593.3   61.71
  4777.1   58.84  4893.2   60.24  4949.2   58.06  4969.4   55.69  4988.3    48.4
  4993.4   51.69  4999.6   47.54  5017.2   46.16  5022.3   46.16    5050   58.93
  5069.9   60.46    5075    59.4  5221.2   62.35  5231.3   63.13  5238.2   65.51
  5243.2   62.82  5445.3   67.67    5463   67.76    5483   70.39    5488   68.43
#Mann= 5 ,-1 , 0
    3892     .11       0  4103.2     .17       0  4949.2     .09       0
    5050     .17       0  5445.3     .11       0
Bank Sta=4949.2,5050
XS Rating Curve= 0 ,0
Exp/Cntr=0.3,0.1

Type RM Length L Ch R = 1 ,8192    ,491,491,491
BEGIN DESCRIPTION:
JORDAN GULLY 10.0
END DESCRIPTION:
XS GIS Cut Line= 3
      3908145.94     10002068.46      3909008.23     10001826.84
      3909527.24     10001665.88
#Sta/Elev= 30
  4104.5   76.63  4117.7   77.34  4127.3   76.37  4137.6   74.61  4158.4   65.75
  4179.2   65.39    4200   60.75  4319.5   59.01    4396   58.76    4418   58.21
    4470   60.23  4586.4   58.27  4791.9   59.14    4875   57.86  4930.4   59.41
  4947.7   57.93  4969.7   58.12    5000    50.6  5001.1   47.87  5010.1   48.48
  5020.5   54.63    5031   58.01  5036.3   59.43  5062.4   61.76  5100.2   62.22
  5188.1   63.59  5237.1   65.76  5405.2   69.66  5460.3   69.17  5543.4   70.55
#Mann= 7 ,-1 , 0
  4104.5     .11       0  4319.5     .17       0    4396     .11       0
  4586.4     .17       0  4969.7     .09       0    5031     .17       0
  5100.2     .11       0
Bank Sta=4969.7,5031
XS Rating Curve= 0 ,0
Exp/Cntr=0.3,0.1

Type RM Length L Ch R = 1 ,7701    ,497,497,497
BEGIN DESCRIPTION:
JORDAN GULLY 9.0
END DESCRIPTION:
XS GIS Cut Line= 3
      3908326.51     10002811.53      3909048.23     10002276.84
      3909562.69     10001748.97
#Sta/Elev= 30
  4101.8    64.2  4116.6   62.75  4339.9   61.23    4367   60.17  4431.7   62.08
  4552.7   60.17  4617.4   59.91  4625.8   60.87  4632.1   59.44  4661.3   61.35
  4817.8   57.56    4912   57.11  4974.6   56.05  4982.7   53.56  4988.9   53.73
  4996.7   49.39  5003.9    48.7  5015.4   45.62  5020.6   45.62    5025   52.27
  5032.1      54  5039.1   58.02  5067.4   60.24  5077.3   59.76  5272.6   62.09
    5428      66  5463.5   67.68  5569.5   65.84    5665   68.95  5737.1   70.12
#Mann= 6 ,-1 , 0
  4101.8     .11       0    4912     .17       0  4974.6     .09       0
  5039.1     .17       0  5077.3    .125       0    5665     .11       0
Bank Sta=4974.6,5039.1
XS Rating Curve= 0 ,0
Exp/Cntr=0.3,0.1

Type RM Length L Ch R = 1 ,7204    ,496,496,496
BEGIN DESCRIPTION:
JORDAN GULLY 8.0
END DESCRIPTION:
XS GIS Cut Line= 3
      3908514.03     10002818.45      3909448.23     10002476.84
      3909846.91     10001715.18
#Sta/Elev= 30
  4005.3   66.55  4038.7   63.49  4094.4   62.91  4531.1   62.39  4669.5   64.45
  4886.8   59.86  4935.7   56.47  4942.5   56.27    4957   52.65  4973.1   51.56
  4986.3   45.79    5000   46.31  5005.4   50.61  5017.8   55.51  5027.5   56.52
  5033.1    59.8  5055.2   60.26  5137.8   59.09  5143.5   56.83    5182   57.33
  5232.3   64.62  5270.2   61.59  5286.7   64.96  5345.1   62.12  5469.3   62.56
  5752.2   67.88    5783   68.23  5796.6   70.51  5827.1   68.17  5859.7   68.85
#Mann= 5 ,-1 , 0
  4005.3     .11       0  4935.7     .11       0  4942.5     .07       0
  5017.8     .11       0  5752.2     .17       0
Bank Sta=4942.5,5017.8
XS Rating Curve= 0 ,0
Exp/Cntr=0.3,0.1

Type RM Length L Ch R = 1 ,6708    ,491,491,491
BEGIN DESCRIPTION:
JORDAN GULLY 7.0
END DESCRIPTION:
XS GIS Cut Line= 3
        3908521.     10002867.06      3909748.23     10002836.84
      3910167.85     10001761.09
#Sta/Elev= 30
  3772.4   68.27  3789.3   65.58  3819.3    63.4  3899.3   61.46  4259.4   63.17
  4319.4   60.81  4429.4   60.03  4569.5   61.42  4659.5   58.43  4699.5   60.56
  4730.7   59.57  4783.7   61.18  4829.4   61.33  4969.6   57.38  4979.6   55.61
    5000   49.14  5009.4   44.13  5014.8   44.13  5017.5   47.75  5036.6   50.63
    5042    53.3  5049.1   54.78  5071.9   58.34  5167.2   57.49  5368.1   61.94
  5639.5   61.47  5838.2   62.57  5892.5      64  5922.4   63.19  6154.7   69.84
#Mann= 6 ,-1 , 0
  3772.4     .11       0  4730.7     .17       0  4783.7     .11       0
  4829.4     .17       0  4979.6     .06       0  5049.1     .11       0
Bank Sta=4979.6,5049.1
XS Rating Curve= 0 ,0
Exp/Cntr=0.3,0.1

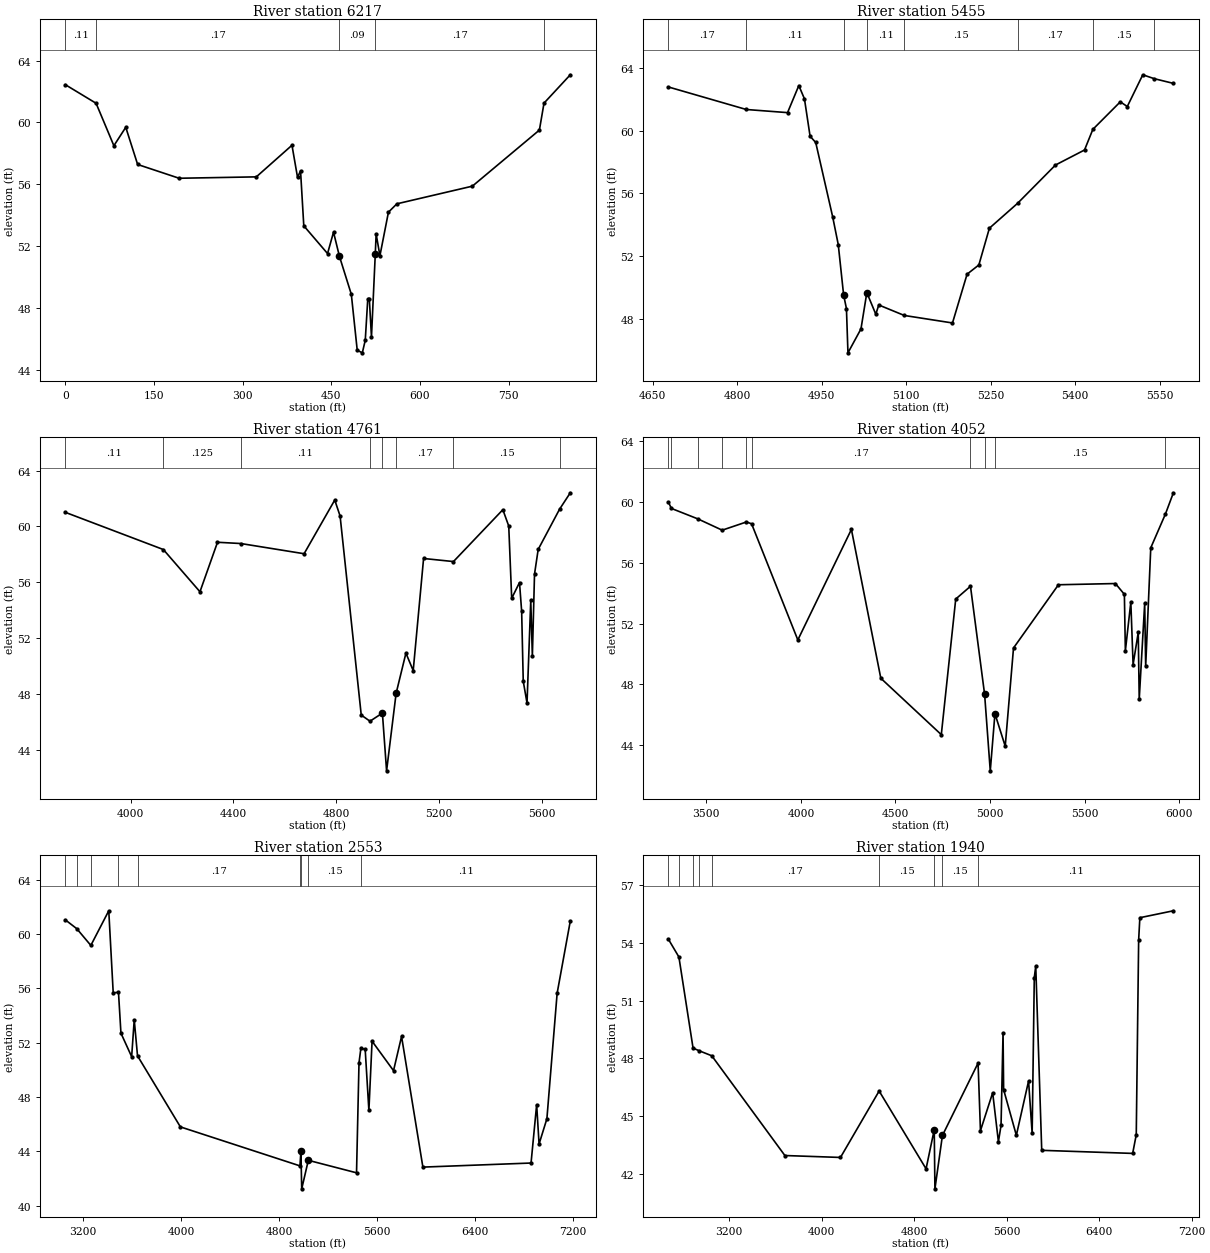
Type RM Length L Ch R = 1 ,6217    ,762,762,762
BEGIN DESCRIPTION:
JORDAN GULLY 6.0
END DESCRIPTION:
XS GIS Cut Line= 3
      3909406.12     10003209.49      3909918.23     10003256.84
      3910180.71     10003040.67
#Sta/Elev= 30
       0   62.44      52   61.24    82.1    58.5   102.2   59.69   122.3   57.29
   192.5    56.4   323.1   56.49   383.4   58.53   392.8   56.46   397.9   56.88
   403.4   53.33   443.6   51.54   453.7   52.92   463.7   51.36   483.8   48.91
   493.8    45.3   502.4   45.13   507.4   45.94   511.6   48.59   514.3   48.59
   517.9   46.15  524.35   51.51   525.8    52.8   532.2    51.4   546.6   54.21
   560.9   54.75   688.6   55.89     802   59.51   809.8   61.25   854.3   63.08
#Mann= 5 ,-1 , 0
       0     .11       0      52     .17       0   463.7     .09       0
  524.35     .17       0   809.8     .11       0
Bank Sta=463.7,524.35
XS Rating Curve= 0 ,0
Exp/Cntr=0.3,0.1

Type RM Length L Ch R = 1 ,5455    ,694,694,694
BEGIN DESCRIPTION:
JORDAN GULLY 4.0
END DESCRIPTION:
XS GIS Cut Line= 3
       3909796.6     10003836.24      3910132.97     10003825.39
      3910667.85     10003661.07
#Sta/Elev= 30
  4678.2   62.81  4816.4   61.37  4889.6   61.17  4909.6    62.9  4919.6   62.05
  4929.6   59.66  4939.6   59.26  4969.6   54.52  4979.6   52.73  4989.1   49.51
  4994.1   48.64  4996.8   45.81  5019.9   47.34  5030.3   49.66  5046.2   48.28
  5051.5   48.87  5096.8    48.2  5182.3   47.72  5208.2   50.84  5229.1   51.43
  5247.8   53.78  5297.8   55.37  5365.1   57.82  5416.6   58.78  5431.4    60.1
  5480.1   61.86  5492.5   61.56    5520   63.59  5540.4   63.34  5574.3   63.04
#Mann= 8 ,-1 , 0
  4678.2     .17       0  4816.4     .11       0  4989.1     .07       0
  5030.3     .11       0  5096.8     .15       0  5297.8     .17       0
  5431.4     .15       0  5540.4     .17       0
Bank Sta=4989.1,5030.3
XS Rating Curve= 0 ,0
Exp/Cntr=0.3,0.1

Type RM Length L Ch R = 1 ,4761    ,709,709,709
BEGIN DESCRIPTION:
JORDAN GULLY 3.0
END DESCRIPTION:
XS GIS Cut Line= 4
      3909058.78     10004064.11      3910280.24     10004364.75
      3910719.73     10004161.03      3910853.01     10003980.41
#Sta/Elev= 30
  3745.2   61.01  4126.9   58.35  4269.5   55.33  4337.8   58.87  4428.5   58.78
  4675.1   58.05  4794.5   61.89  4815.3   60.75  4897.7   46.51  4931.8   46.07
  4980.1   46.65  4996.4   42.52  5033.5   48.06  5071.7   50.94  5100.1   49.69
  5140.5   57.71  5256.9   57.49  5449.3    61.2  5472.2   60.03  5483.7   54.86
  5514.1   55.99  5522.5   53.93  5528.7   48.93  5543.4   47.37    5558   54.71
  5564.2   50.72  5572.6   56.59  5586.9   58.36    5670   61.23    5712   62.41
#Mann= 8 ,-1 , 0
  3745.2     .11       0  4126.9    .125       0  4428.5     .11       0
  4931.8     .17       0  4980.1     .09       0  5033.5     .17       0
  5256.9     .15       0    5670     .11       0
Bank Sta=4980.1,5033.5
XS Rating Curve= 0 ,0
Exp/Cntr=0.3,0.1

Type RM Length L Ch R = 1 ,4052    ,1499,1499,1499
BEGIN DESCRIPTION:
Mapping XS c61a36fe
END DESCRIPTION:
XS GIS Cut Line= 4
      3909113.56     10004119.08      3910096.21     10005001.91
      3910637.88     10004765.79      3910842.69     10004035.95
#Sta/Elev= 30
  3299.4   59.99  3315.2   59.58  3455.5   58.89  3583.7   58.15  3711.9   58.69
  3739.1   58.57  3983.6   50.93  4266.9    58.2  4422.4   48.41  4742.2    44.7
  4818.5   53.62  4896.5   54.46  4971.2   47.35  5001.1   42.32  5025.8   46.08
  5080.2   43.94    5124    50.4  5361.6   54.56  5662.8   54.64  5710.2   53.93
  5715.4   50.21  5744.3   53.42  5756.3   49.31  5783.5   51.42  5788.7   47.03
  5817.6   53.33  5822.8    49.2  5849.7   56.99  5927.5   59.22  5969.3   60.61
#Mann= 10 ,-1 , 0
  3299.4     .11       0  3315.2     .17       0  3455.5     .11       0
  3583.7     .17       0  3711.9    .125       0  3739.1     .17       0
  4896.5     .15       0  4971.2     .09       0  5025.8     .15       0
  5927.5     .11       0
Bank Sta=4971.2,5025.8
XS Rating Curve= 0 ,0
Exp/Cntr=0.3,0.1

Type RM Length L Ch R = 1 ,2553    ,613,613,613
BEGIN DESCRIPTION:
JORDAN GULLY 2.0
END DESCRIPTION:
XS GIS Cut Line= 4
      3908986.29     10004012.93      3909991.91     10005550.65
      3910751.46     10005442.14      3911196.33     10003988.19
#Sta/Elev= 30
  3055.1   61.03  3148.6   60.38  3263.3   59.15  3409.8    61.7    3446   55.67
  3489.2   55.69  3509.2   52.69  3596.7   50.96  3617.8   53.67  3644.7   51.02
  3994.9   45.79  4971.8   42.92  4979.3   44.01    4986   41.23  5039.9   43.33
  5433.8   42.41    5454   50.51  5469.4   51.58  5504.5    51.5  5534.8      47
  5560.7    52.1    5736   49.93  5801.6   52.45  5975.9   42.83  6859.5   43.13
  6905.3   47.43    6925   44.53  6988.9   46.39  7072.6   55.63  7180.2   60.95
#Mann= 9 ,-1 , 0
  3055.1     .17       0  3148.6     .11       0  3263.3     .17       0
  3489.2     .11       0  3644.7     .17       0  4971.8     .15       0
  4979.3    .015       0  5039.9     .15       0  5469.4     .11       0
#Block Obstruct= 2 , 0
                         5837.59           50.13
Bank Sta=4979.3,5039.9
XS Rating Curve= 0 ,0
Exp/Cntr=0.3,0.1

Type RM Length L Ch R = 1 ,1940    ,631,631,631
BEGIN DESCRIPTION:
Mapping XS 3553854d
END DESCRIPTION:
XS GIS Cut Line= 4
      3908999.01     10004286.65      3910144.82     10005904.68
       3910797.6     10005807.46      3911242.04     10004140.83
#Sta/Elev= 30
  2673.9   54.19  2764.6   53.27  2886.9   48.54  2935.8   48.41  3048.9   48.14
  3681.1   42.96    4162   42.86  4496.4   46.31  4902.3   42.27    4973    44.3
  4978.9   41.23  5043.8      44  5352.1   47.76  5372.7   44.25  5478.4   46.22
    5528   43.68  5550.8   44.52  5568.1   49.33  5573.2   46.38  5683.2   44.01
  5788.9   46.83  5819.9   44.11  5838.4    52.2    5851    52.8  5902.7   43.23
  6689.3   43.07  6720.3   44.04    6741   54.15  6751.4   55.31  7041.4   55.67
#Mann= 9 ,-1 , 0
  2673.9     .17       0  2764.6     .15       0  2886.9     .17       0
  2935.8     .11       0  3048.9     .17       0  4496.4     .15       0
    4973    .015       0  5043.8     .15       0  5352.1     .11       0
#Block Obstruct= 2 , 0
                         5859.49           52.72
Bank Sta=4973,5043.8
XS Rating Curve= 0 ,0
Exp/Cntr=0.3,0.1

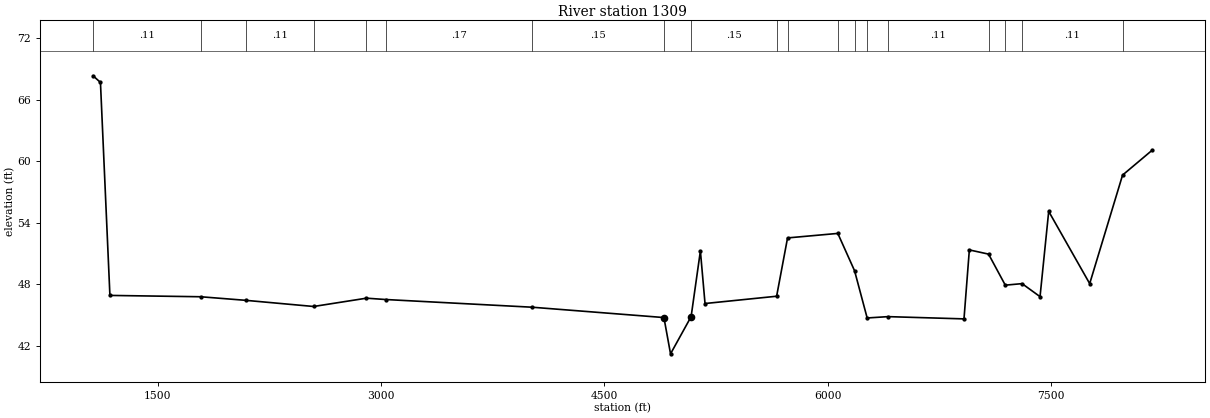
Type RM Length L Ch R = 1 ,1309    ,0,0,0
BEGIN DESCRIPTION:
JORDAN GULLY 1.0
END DESCRIPTION:
XS GIS Cut Line= 4
      3907739.64     10003979.51       3910485.1     10006494.96
      3910915.66     10006376.91      3912443.51     10003859.03
#Sta/Elev= 30
  1066.4   68.36    1116   67.71  1179.5   46.93  1788.3    46.8  2092.1   46.45
  2547.8   45.85  2902.5   46.66  3031.7   46.53    4014   45.78  4900.5   44.77
  4944.9   41.23  5083.1   44.86  5145.4   51.27  5176.5   46.14  5657.4   46.85
  5730.8   52.54  6068.3   52.98  6180.8   49.34  6265.5   44.73  6405.8   44.86
  6915.9   44.64  6951.8   51.37  7080.8   50.96  7193.3   47.93  7305.8   48.08
  7426.6   46.81  7484.8   55.13  7760.1   48.08  7980.9   58.67  8181.6   61.12
#Mann= 19 ,-1 , 0
  1066.4     .11       0  1788.3     .15       0  2092.1     .11       0
  2547.8     .17       0  2902.5     .11       0  3031.7     .17       0
    4014     .15       0  4900.5    .015       0  5083.1     .15       0
  5657.4     .11       0  5730.8     .17       0  6068.3     .11       0
  6180.8     .15       0  6265.5     .17       0  6405.8     .11       0
  7080.8     .15       0  7193.3     .11       0  7305.8     .11       0
  7980.9     .17       0
Bank Sta=4900.5,5083.1
XS Rating Curve= 0 ,0
Exp/Cntr=0.3,0.1

Chan Stop Cuts=-1
Use User Specified Reach Order=0
Composite Channel Slope=5