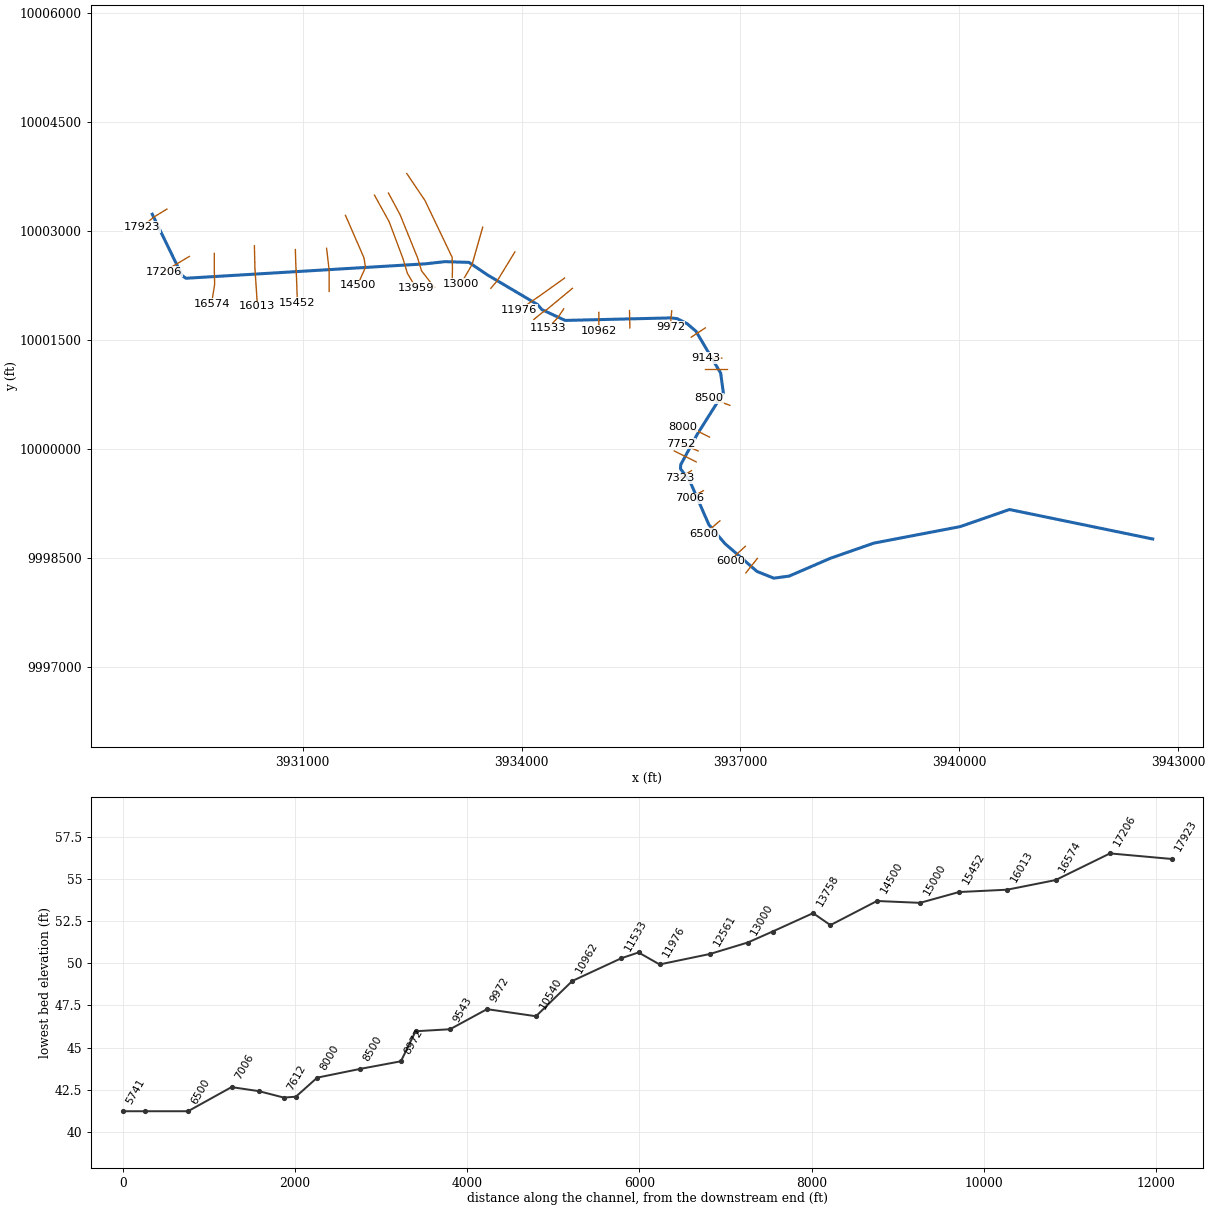
--- ROGERS GULLY.prj (project) ---

Proj Title=ROGERS GULLY Base Level Engineering
Current Plan=p01
Default Exp/Contr=0.3,0.1
English Units
Geom File=g01
Flow File=f01
Flow File=f02
Plan File=p01
Y Axis Title=Elevation
X Axis Title(PF)=Main Channel Distance
X Axis Title(XS)=Station
BEGIN DESCRIPTION:
ROGERS GULLY
END DESCRIPTION:
DSS Export Rating Curves= 0
DSS Export Rating Curve Sorted= 0
DSS Export Volume Flow Curves= 0
DXF OffsetX= 0
DXF OffsetY= 0
DXF ScaleX= 1
DXF ScaleY= 10

--- ROGERS GULLY.p01 (plan) ---

Plan Title=Multiple Run
Short Identifier=Multiple
Geom File=g01
Flow File=f01
Subcritical Flow
K Sum by GR= 0
Std Step Tol= 0.01
Critical Tol= 0.01
Num of Std Step Trials= 20
Max Error Tol= 0.3
Flow Tol Ratio= 0.001
Split Flow NTrial= 30
Split Flow Tol= 0.02
Split Flow Ratio= 0.02
Log Output Level= 0
Friction Slope Method= 1
Unsteady Friction Slope Method= 2
Unsteady Bridges Friction Slope Method= 1
Parabolic Critical Depth
Global Vel Dist=  1 , 1 , 1
Global Log Level= 0
CheckData=True
Encroach Param= -1, 0, 0, 0
BEGIN DESCRIPTION:
Multiple Run
END DESCRIPTION:

--- ROGERS GULLY.f01 (steady flow) ---

Flow Title=Multiple
Program Version=4.10
Number of Profiles= 7
Profile Names=10-year,25-year,50-year,1pct_min,100-year,1pct_plu,500-year
River Rch & RM=ROGERS GULLY,Reach-1         ,17923
     239     283     347     140     424    1280     648
River Rch & RM=ROGERS GULLY,Reach-1         ,17206
     305     368     459     187     566    1709     889
River Rch & RM=ROGERS GULLY,Reach-1         ,13758
     777    1010    1325     570    1722    5200    3001
River Rch & RM=ROGERS GULLY,Reach-1         ,8500
     349     431     547     228     690    2084    1139
River Rch & RM=ROGERS GULLY,Reach-1         ,7323
     845    1119    1492     653    1972    5955    3583
River Rch & RM=ROGERS GULLY,Reach-1         ,5313
     977    1304    1746     768    2318    7000    4248
River Rch & RM=ROGERS GULLY,Reach-1         ,2500
    1022    1363    1824     802    2421    7311    4431
Boundary for River Rch & Prof#=ROGERS GULLY,Reach-1         , 1
Up Type= 0
Dn Type= 3
Dn Slope=0.00073
Boundary for River Rch & Prof#=ROGERS GULLY,Reach-1         , 2
Up Type= 0
Dn Type= 3
Dn Slope=0.00073
Boundary for River Rch & Prof#=ROGERS GULLY,Reach-1         , 3
Up Type= 0
Dn Type= 3
Dn Slope=0.00073
Boundary for River Rch & Prof#=ROGERS GULLY,Reach-1         , 4
Up Type= 0
Dn Type= 3
Dn Slope=0.00073
Boundary for River Rch & Prof#=ROGERS GULLY,Reach-1         , 5
Up Type= 0
Dn Type= 3
Dn Slope=0.00073
Boundary for River Rch & Prof#=ROGERS GULLY,Reach-1         , 6
Up Type= 0
Dn Type= 3
Dn Slope=0.00073
Boundary for River Rch & Prof#=ROGERS GULLY,Reach-1         , 7
Up Type= 0
Dn Type= 3
Dn Slope=0.00073
DSS Import GetInterval= 0
DSS Import GetPeak= 0
DSS Import FillOption= 0

--- ROGERS GULLY.f02 (steady flow) ---

Flow Title=Orig_BLE_Flows
Program Version=4.10
Number of Profiles= 7
Profile Names=10-year,25-year,50-year,1pct_min,100-year,1pct_plu,500-year
River Rch & RM=ROGERS GULLY,Reach-1         ,17923
     239     277     302     108     326     983     377
River Rch & RM=ROGERS GULLY,Reach-1         ,17004
     305     361     399     144     435    1314     517
River Rch & RM=ROGERS GULLY,Reach-1         ,13959
     842    1081    1266     485    1464    4423    1953
River Rch & RM=ROGERS GULLY,Reach-1         ,8500
     349     423     476     176     531    1604     662
River Rch & RM=ROGERS GULLY,Reach-1         ,7323
     845    1097    1297     502    1517    4582    2083
River Rch & RM=ROGERS GULLY,Reach-1         ,5313
     977    1278    1518     591    1783    5386    2470
River Rch & RM=ROGERS GULLY,Reach-1         ,2500
    1022    1336    1586     617    1862    5625    2576
Boundary for River Rch & Prof#=ROGERS GULLY,Reach-1         , 1
Up Type= 0
Dn Type= 3
Dn Slope=0.00073
Boundary for River Rch & Prof#=ROGERS GULLY,Reach-1         , 2
Up Type= 0
Dn Type= 3
Dn Slope=0.00073
Boundary for River Rch & Prof#=ROGERS GULLY,Reach-1         , 3
Up Type= 0
Dn Type= 3
Dn Slope=0.00073
Boundary for River Rch & Prof#=ROGERS GULLY,Reach-1         , 4
Up Type= 0
Dn Type= 3
Dn Slope=0.00073
Boundary for River Rch & Prof#=ROGERS GULLY,Reach-1         , 5
Up Type= 0
Dn Type= 3
Dn Slope=0.00073
Boundary for River Rch & Prof#=ROGERS GULLY,Reach-1         , 6
Up Type= 0
Dn Type= 3
Dn Slope=0.00073
Boundary for River Rch & Prof#=ROGERS GULLY,Reach-1         , 7
Up Type= 0
Dn Type= 3
Dn Slope=0.00073
DSS Import GetInterval= 0
DSS Import GetPeak= 0
DSS Import FillOption= 0

--- ROGERS GULLY.g01 (geometry) ---

Geom Title=Existing Conditions
Program Version=4.10

River Reach=ROGERS GULLY    ,Reach-1
Reach XY= 30
      3928936.49      10003229.1      3929343.38     10002388.18
      3929397.85     10002348.33      3932678.23     10002546.84
      3932948.23     10002576.84      3933278.23     10002566.84
      3933528.23     10002396.84      3934218.23     10001986.84
      3934278.23     10001916.84      3934597.69     10001768.36
        3936050.     10001803.08      3936133.67      10001792.3
      3936268.68     10001724.08      3936389.85     10001620.39
      3936729.14     10001042.74      3936765.64     10000771.53
      3936408.12     10000202.12      3936181.28      9999784.51
      3936178.23      9999726.84      3936302.92      9999565.49
      3936567.63      9998957.02      3936789.23      9998696.39
      3937227.26      9998314.75      3937457.79      9998222.23
      3937668.69      9998251.28        3938235.      9998496.68
      3938829.19      9998704.69      3940013.17      9998931.82
      3940688.23      9999166.84        3942652.      9998761.28

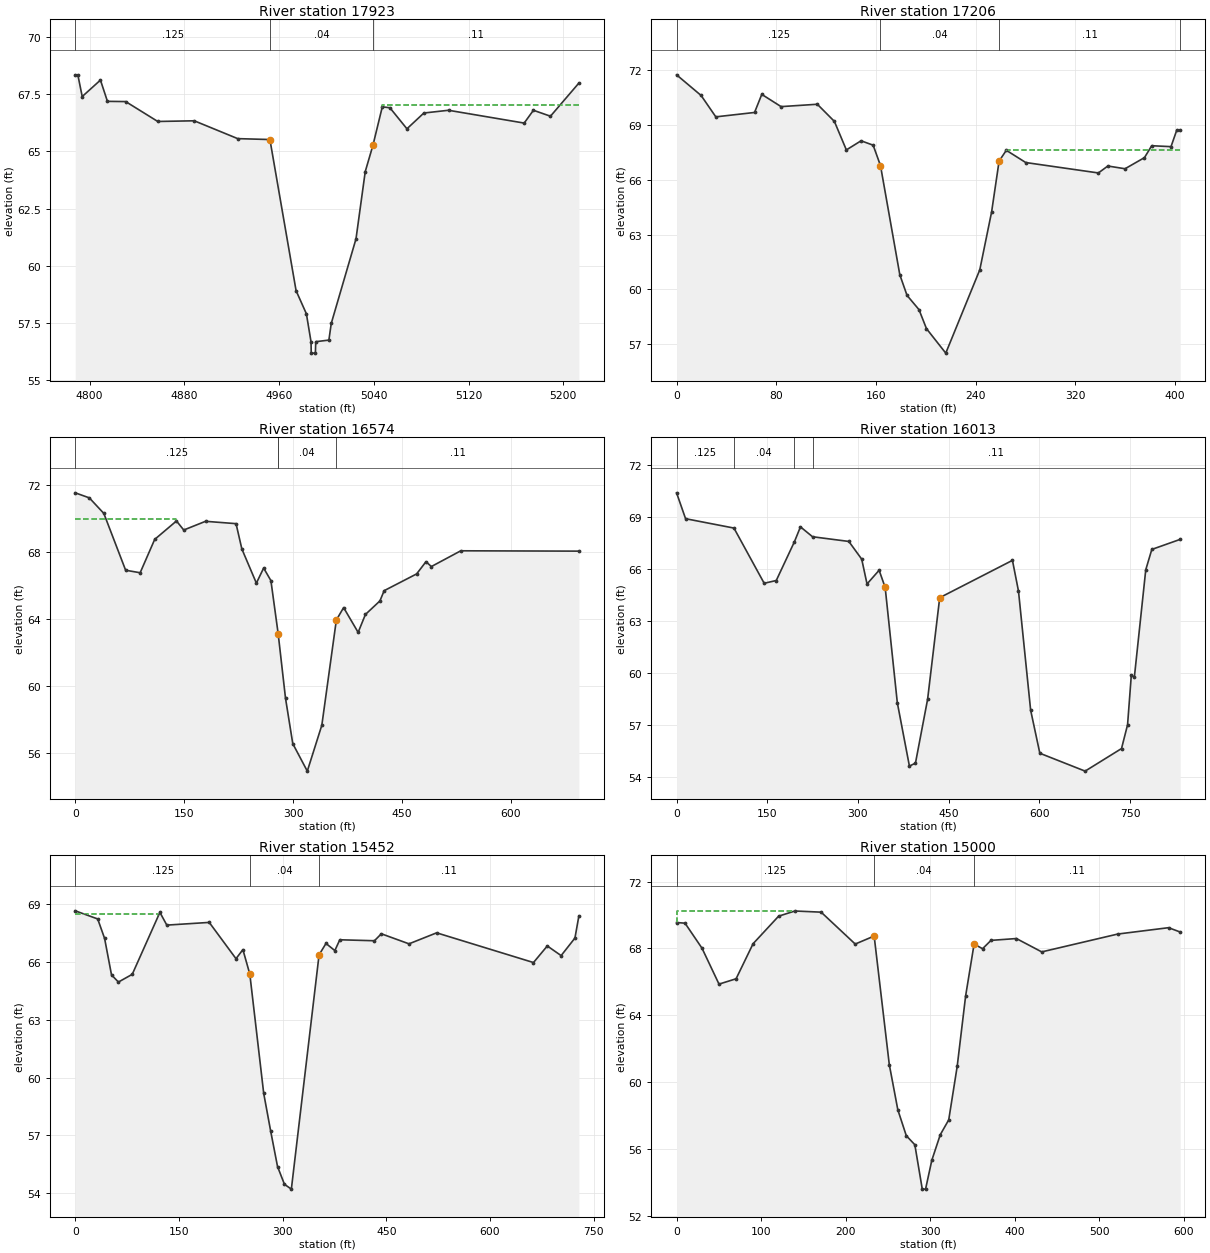
Type RM Length L Ch R = 1 ,17923   ,717,717,717
BEGIN DESCRIPTION:
ROGERS GULLY 35.0
END DESCRIPTION:
XS GIS Cut Line= 3
      3929136.67     10003299.88      3928956.03     10003188.73
      3928791.53      10003053.1
#Sta/Elev= 30
  4787.9   68.35  4790.1   68.35  4793.8    67.4  4809.2   68.12  4815.1   67.19
  4830.5   67.18  4857.6   66.31  4888.4   66.34  4925.1   65.56  4952.3   65.52
  4974.4   58.91  4983.1    57.9    4987   56.68  4987.2   56.18  4990.7   56.18
    4991   56.68  5002.1   56.75  5004.1   57.48    5025   61.18  5032.8   64.12
  5039.3   65.27  5047.2   66.95  5053.6   66.91    5068   65.99  5082.3   66.68
  5103.1    66.8    5167   66.24  5174.8    66.8  5189.2   66.54  5213.2   67.99
#Mann= 3 , 0 , 0
  4787.9    .125       0  4952.3     .04       0  5039.3     .11       0
#XS Ineff= 2 , 0
                         5046.94           67.01
Permanent Ineff=
       F       F
Bank Sta=4952.3,5039.3
XS Rating Curve= 0 ,0
Exp/Cntr=0.3,0.1

Type RM Length L Ch R = 1 ,17206   ,632,632,632
BEGIN DESCRIPTION:
Mapping XS 7c8f2227
END DESCRIPTION:
XS GIS Cut Line= 2
      3929444.74      10002649.3      3929097.95      10002441.4
#Sta/Elev= 30
       0   71.74    19.7   70.61    31.5   69.44    62.6   69.68    68.4   70.67
    83.9      70     113   70.13   126.7   69.19   136.3   67.63   148.1   68.13
   157.8   67.89   163.7   66.77   179.2    60.8     185   59.67   194.6   58.89
   200.6   57.85   216.1   56.51   243.4   61.07   252.9   64.24   258.9   67.02
   264.7   67.61   280.3   66.94   338.6   66.37   346.2   66.75     360    66.6
   375.6   67.21   381.4   67.86   396.9   67.81   401.5   68.71   404.3   68.71
#Mann= 4 ,-1 , 0
       0    .125       0   163.7     .04       0   258.9     .11       0
   404.3    .125       0
#XS Ineff= 2 , 0
                          264.25           67.65
Permanent Ineff=
       F       F
Bank Sta=163.7,258.9
XS Rating Curve= 0 ,0
Exp/Cntr=0.3,0.1

Type RM Length L Ch R = 1 ,16574   ,561,561,561
BEGIN DESCRIPTION:
Mapping XS 95462d7c
END DESCRIPTION:
XS GIS Cut Line= 4
      3929786.39      10002690.5      3929786.49     10002469.15
      3929791.49     10002264.45      3929749.16     10002000.53
#Sta/Elev= 30
       0   71.54    19.4   71.24    39.4   70.31    69.4   66.92    89.4   66.77
   109.4   68.76   139.4   69.86   149.4   69.32   179.4   69.84   221.4    69.7
   229.4   68.19   249.4   66.15   259.4   67.05   269.4    66.3   279.4   63.13
   289.5   59.28   299.5   56.57   319.5   54.93   339.5   57.67   359.5   63.95
   369.5   64.69   389.5   63.21   399.5   64.28   419.5   65.09   425.3    65.7
     470    66.7   482.9   67.43   490.3   67.14   530.8   68.08   693.4   68.06
#Mann= 4 ,-1 , 0
       0    .125       0   279.4     .11       0   279.4     .04       0
   359.5     .11       0
#XS Ineff= 2 , 0
          138.55   69.96
Permanent Ineff=
       F       F
Bank Sta=279.4,359.5
XS Rating Curve= 0 ,0
Exp/Cntr=0.3,0.1

Type RM Length L Ch R = 1 ,16013   ,561,561,561
BEGIN DESCRIPTION:
Mapping XS 8a17b06c
END DESCRIPTION:
XS GIS Cut Line= 4
      3930336.55     10002795.94      3930343.45     10002489.83
      3930358.11     10002267.91      3930378.21     10001962.18
#Sta/Elev= 30
       0   70.39    14.9    68.9    94.9   68.36   144.9   65.18   164.9   65.34
   194.9   67.57   204.9   68.43   224.9   67.86   284.9   67.59   306.2   66.57
     315   65.14     335   65.93     345   64.94   365.1    58.3   385.1   54.65
   395.1   54.82   415.2    58.5   435.2   64.35   555.5    66.5   565.5   64.73
   585.6   57.87   600.8   55.39   675.7   54.36   735.9   55.66   745.9   57.03
   752.1   59.89   757.1   59.76     776   65.96     786   67.13     833   67.71
#Mann= 4 ,-1 , 0
       0    .125       0    94.9     .04       0   194.9    .125       0
   224.9     .11       0
#Block Obstruct= 2 , 0
                           554.4           66.52
Bank Sta=345,435.2
XS Rating Curve= 0 ,0
Exp/Cntr=0.3,0.1

Type RM Length L Ch R = 1 ,15452   ,452,452,452
BEGIN DESCRIPTION:
Mapping XS 27bc7064
END DESCRIPTION:
XS GIS Cut Line= 4
      3930897.96     10002743.56      3930903.46     10002553.51
      3930913.88     10002350.38      3930925.55     10002014.81
#Sta/Elev= 30
       0   68.64    32.5   68.22    42.5   67.21    52.5   65.32    62.5   64.95
    82.5   65.35   122.5   68.56   132.5    67.9   193.9   68.04   232.6   66.16
   242.6   66.63   252.6   65.36   272.7   59.18   282.7   57.24   292.7   55.39
   302.7   54.47   312.7   54.22   352.8   66.36   362.8   66.95   375.6   66.58
   382.8   67.14   432.9   67.09   442.9   67.45   482.9   66.93   522.9    67.5
     663   65.96     683   66.82     703   66.32     723   67.23   728.7   68.38
#Mann= 3 , 0 , 0
       0    .125       0   252.6     .04       0   352.8     .11       0
#XS Ineff= 2 , 0
          120.21    68.5  523.11           67.46
Permanent Ineff=
       F       F
Bank Sta=252.6,352.8
XS Rating Curve= 0 ,0
Exp/Cntr=0.3,0.1

Type RM Length L Ch R = 1 ,15000   ,500,500,500
BEGIN DESCRIPTION:
ROGERS GULLY 30.0
END DESCRIPTION:
XS GIS Cut Line= 3
      3931326.21     10002760.98      3931360.19     10002468.47
      3931361.05     10002167.24
#Sta/Elev= 30
       0   69.55      10   69.51    30.1   68.01    50.2   65.86    70.4   66.18
    90.5   68.28   120.7   69.93     140   70.24     171   70.17   211.3   68.26
   233.7   68.74   251.6   61.04   261.7   58.33   271.7   56.78   281.8   56.24
   290.6   53.58   294.5   53.58   301.9   55.31   311.9   56.84   321.9   57.73
   331.9   60.93   341.9   65.16   351.9   68.26   361.9   67.98   371.9   68.48
   401.9   68.59   431.9   67.79   521.9   68.86   581.9   69.24   595.7   68.98
#Mann= 3 , 0 , 0
       0    .125       0   233.7     .04       0   351.9     .11       0
#XS Ineff= 2 , 0
          140.52   70.25
Permanent Ineff=
       F       F
Bank Sta=233.7,351.9
XS Rating Curve= 0 ,0
Exp/Cntr=0.3,0.1

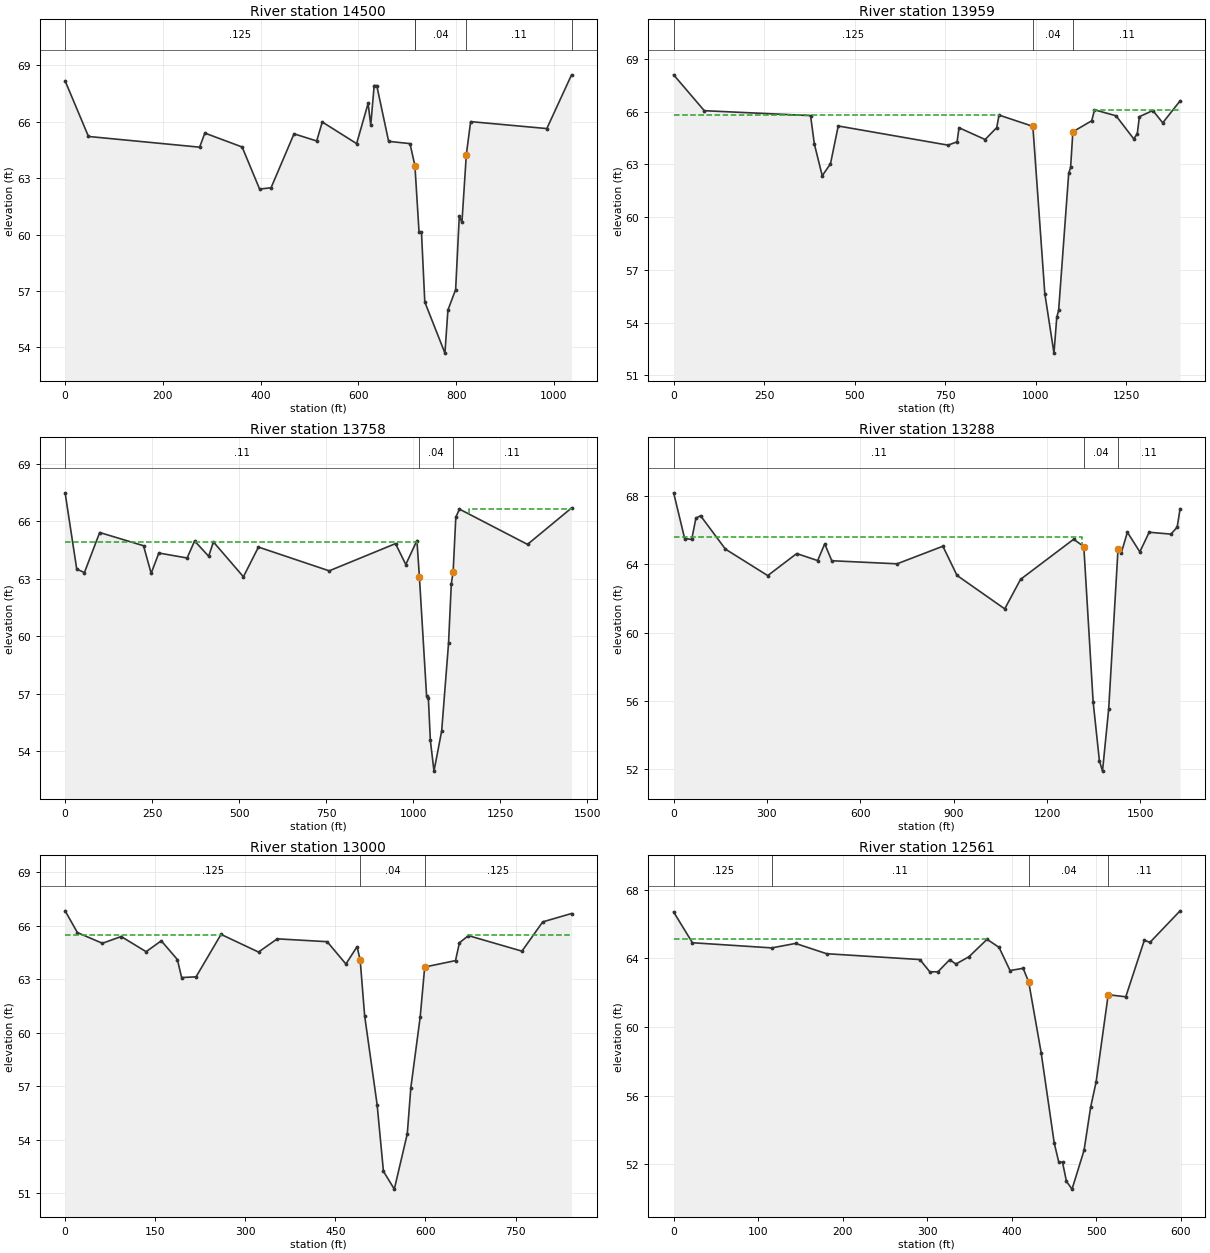
Type RM Length L Ch R = 1 ,14500   ,541,541,541
BEGIN DESCRIPTION:
ROGERS GULLY 29.0
END DESCRIPTION:
XS GIS Cut Line= 4
      3931585.27     10003213.28      3931838.41      10002630.3
      3931859.24     10002499.31      3931749.53     10002252.52
#Sta/Elev= 30
       0   68.18    47.8   65.22   275.3   64.65   285.9    65.4   362.2   64.66
     398   62.42   421.4   62.49   468.4   65.36   514.8   64.98   526.2   65.99
   596.5   64.84     620   66.98   625.4   65.82   632.4   67.93   637.7   67.93
     662   64.96   705.7   64.84   715.8   63.66   724.2   60.14   729.2   60.13
     736   56.41   777.2   53.69   783.3   55.98   799.1   57.07   806.6   60.98
     812   60.65     821   64.26   829.8   66.01   985.7   65.64  1036.3    68.5
#Mann= 5 ,-1 , 0
       0    .125       0   715.8     .11       0   715.8     .04       0
     821     .11       0  1036.3     .17       0
#XS Ineff= 2 , 0
          632.95   67.79
Permanent Ineff=
       F       F
Bank Sta=715.8,821
XS Rating Curve= 0 ,0
Exp/Cntr=0.3,0.1

Type RM Length L Ch R = 1 ,13959   ,201,201,201
BEGIN DESCRIPTION:
Mapping XS c7c7221c
END DESCRIPTION:
XS GIS Cut Line= 5
      3931982.84     10003491.51      3932183.95     10003126.04
      3932373.31     10002619.36      3932434.71     10002415.49
      3932549.49     10002218.87
#Sta/Elev= 30
       0   68.09    84.6   66.05   378.1   65.77   388.5   64.16   410.3   62.35
   433.1   63.03   454.5   65.18   757.8   64.09   782.7   64.28   788.1   65.08
   860.2   64.41   892.2   65.09   898.6    65.8     992   65.16    1025   55.65
  1050.3   52.26    1058   54.29  1063.2    54.7    1091   62.49  1096.2   62.82
  1102.5   64.85  1154.7   65.48  1162.2    66.1  1221.7   65.76  1270.5   64.45
  1280.3   64.73  1286.2   65.71  1323.4   66.06  1350.7   65.36  1398.6   66.61
#Mann= 3 , 0 , 0
       0    .125       0     992     .04       0  1102.5     .11       0
#XS Ineff= 2 , 0
          898.03   65.81 1160.62            66.1
Permanent Ineff=
       F       F
Bank Sta=992,1102.5
XS Rating Curve= 0 ,0
Exp/Cntr=0.3,0.1

Type RM Length L Ch R = 1 ,13758   ,470,470,470
BEGIN DESCRIPTION:
Mapping XS edef06af
END DESCRIPTION:
XS GIS Cut Line= 5
      3932174.28     10003520.52      3932334.78     10003220.79
      3932575.31     10002624.76       3932628.1      10002450.5
      3932805.57     10002221.04
#Sta/Elev= 30
       0   67.49    33.4   63.51    55.5   63.33    99.3   65.42   225.3   64.73
   247.2   63.29   269.2   64.35   350.5   64.09     372   64.98   412.4   64.18
     426   64.93   512.2   63.11   555.4   64.66   758.6   63.42   949.2   64.84
   978.7   63.75  1010.7      65  1017.9   63.08  1038.4    56.9  1043.6   56.76
  1049.3   54.57  1059.7   52.97  1081.8   55.07  1101.5   59.64  1109.5   62.75
  1114.7   63.36  1122.4   66.22  1132.9   66.64  1328.4    64.8  1454.9    66.7
#Mann= 3 , 0 , 0
       0     .11       0  1017.9     .04       0  1114.7     .11       0
#XS Ineff= 2 , 0
          1011.4   64.94 1160.62           66.65
Permanent Ineff=
       F       F
Bank Sta=1017.9,1114.7
XS Rating Curve= 0 ,0
Exp/Cntr=0.3,0.1

Type RM Length L Ch R = 1 ,13288   ,288,288,288
BEGIN DESCRIPTION:
Mapping XS 5f7d4ad7
END DESCRIPTION:
XS GIS Cut Line= 5
      3932425.66     10003789.31      3932675.11     10003418.03
      3933047.39     10002636.83       3933051.9      10002485.8
       3933048.4     10002321.66
#Sta/Elev= 30
       0   68.19    35.4   65.51    58.1   65.46    71.4    66.7    86.4   66.85
   166.5   64.89   302.4   63.34   395.5   64.63   462.9   64.22   485.6    65.2
   508.3   64.21   718.2   64.03   865.4   65.06   910.8   63.35  1064.2   61.39
  1115.1   63.12  1285.8   65.47  1318.4   65.04  1348.4   55.94  1368.5   52.49
  1378.5   51.88  1398.5   55.55  1428.5   64.92  1438.5   64.65  1458.5   65.88
  1498.5   64.73  1528.5   65.88  1598.5   65.77  1618.5   66.18  1627.9   67.26
#Mann= 3 , 0 , 0
       0     .11       0  1318.4     .04       0  1428.5     .11       0
#XS Ineff= 2 , 0
          1311.3    65.6 1458.65           65.86
Permanent Ineff=
       F       F
Bank Sta=1318.4,1428.5
XS Rating Curve= 0 ,0
Exp/Cntr=0.3,0.1

Type RM Length L Ch R = 1 ,13000   ,439,439,439
BEGIN DESCRIPTION:
ROGERS GULLY 26.0
END DESCRIPTION:
XS GIS Cut Line= 3
      3933466.37     10003050.82       3933320.5     10002536.84
      3933165.59     10002269.57
#Sta/Elev= 30
       0   66.83    20.5   65.61    62.1   65.01    93.3   65.39   134.9   64.54
   160.1   65.15   186.9    64.1     194   63.09     218   63.13   259.6   65.51
     322   64.52   353.2   65.26   436.3    65.1   467.5   63.85   486.1   64.82
   491.3   64.06   498.7   60.95   519.5   55.96     530   52.23   548.1   51.23
   569.7   54.33   575.6   56.91   591.2   60.88   598.7   63.68     650   64.04
   656.5   65.04   671.5   65.44   760.6   64.57   795.2   66.21   843.2   66.68
#Mann= 3 , 0 , 0
       0    .125       0   491.3     .04       0   598.7    .125       0
#XS Ineff= 2 , 0
          261.14    65.5   671.5            65.5
Permanent Ineff=
       F       F
Bank Sta=491.3,598.7
XS Rating Curve= 0 ,0
Exp/Cntr=0.3,0.1

Type RM Length L Ch R = 1 ,12561   ,585,585,585
BEGIN DESCRIPTION:
ROGERS GULLY 25.0
END DESCRIPTION:
XS GIS Cut Line= 3
      3933907.24     10002710.27      3933668.23     10002316.84
      3933578.06     10002210.87
#Sta/Elev= 30
       0    66.7    22.2   64.91   116.1   64.61   144.3   64.87   181.1   64.27
   291.5   63.93   303.3   63.21   312.9   63.22   326.7   63.92   334.2   63.67
   349.7    64.1     371   65.11   385.2   64.64   398.2   63.29   413.7   63.42
   420.3   62.62     435   58.51   450.5   53.24   455.9   52.12   460.3   52.12
     465      51   471.6   50.55   485.8   52.81   493.6   55.32   500.1    56.8
   514.4   61.88   535.2   61.76   557.2   65.06   563.8   64.93   599.5   66.77
#Mann= 4 ,-1 , 0
       0    .125       0   116.1     .11       0   420.3     .04       0
   514.4     .11       0
#XS Ineff= 2 , 0
          371.81   65.15
Permanent Ineff=
       F       F
Bank Sta=420.3,514.4
XS Rating Curve= 0 ,0
Exp/Cntr=0.3,0.1

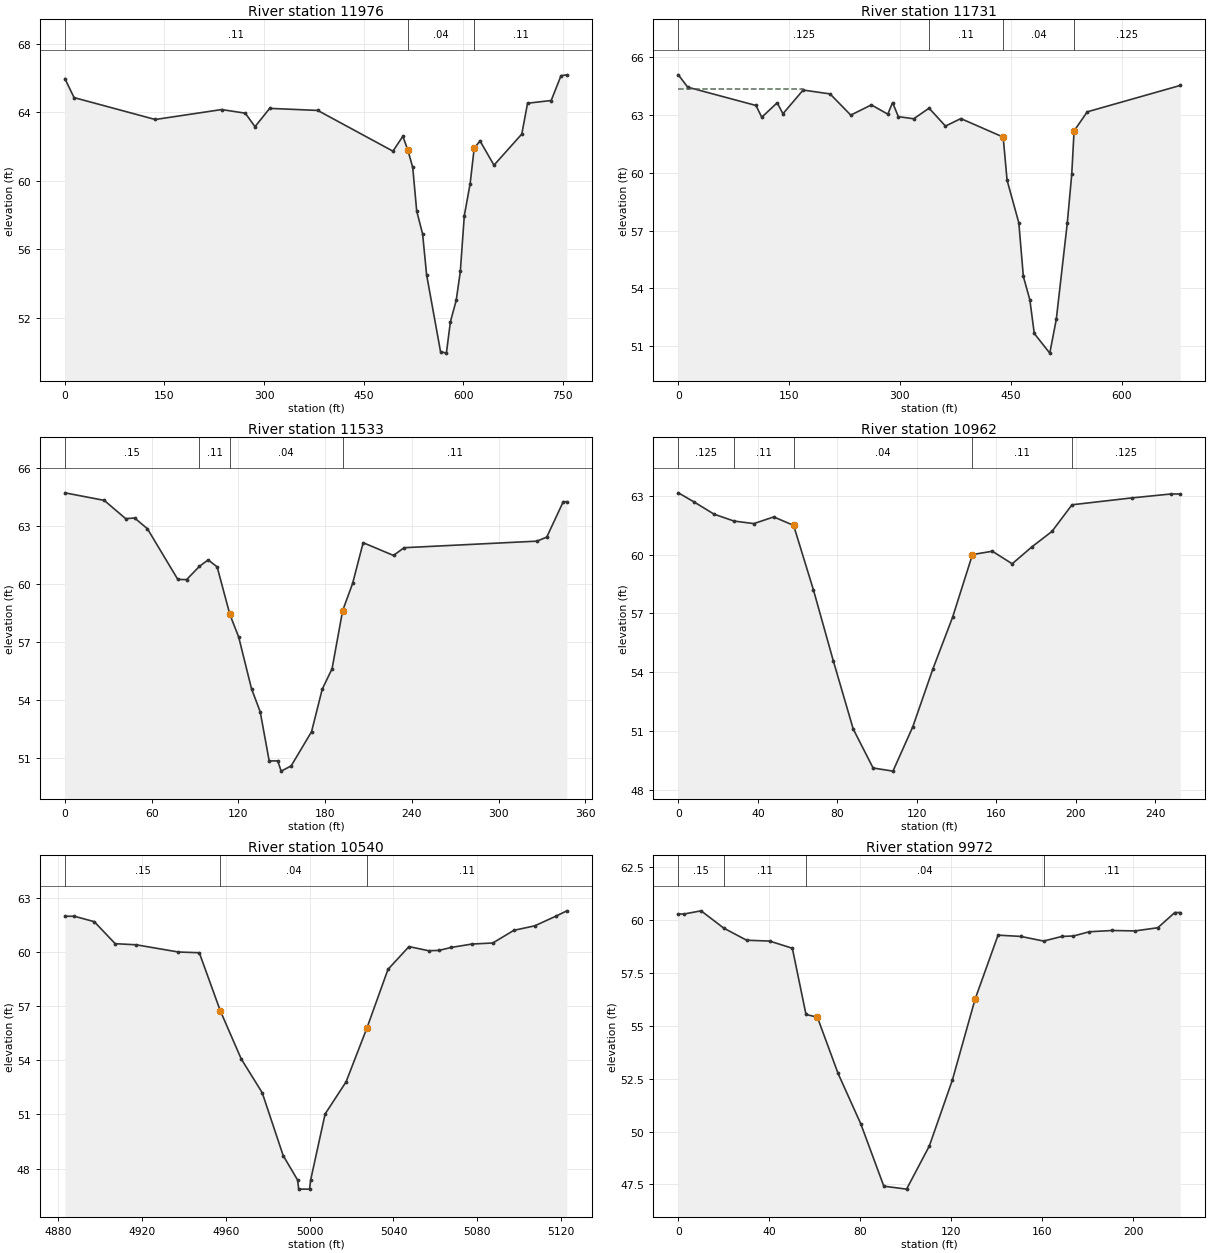
Type RM Length L Ch R = 1 ,11976   ,245,245,245
BEGIN DESCRIPTION:
Mapping XS 5c87fde0
END DESCRIPTION:
XS GIS Cut Line= 4
      3934588.46     10002350.96      3934230.73     10002094.24
      3934032.06     10001957.38      3933969.62     10001913.02
#Sta/Elev= 30
       0   65.97    13.8   64.86   136.1   63.58   236.1   64.16   271.7   63.95
   286.4   63.16   308.5   64.23   380.9   64.11   494.2   61.73   509.1    62.6
   516.7   61.79     524   60.78     530   58.23   538.9   56.89   544.9   54.51
   565.9   50.02   574.7   49.93   580.8   51.77   589.5   53.01   595.7    54.7
   601.7   57.96   610.5   59.83   616.6    61.9   625.4   62.33   646.4   60.91
   688.3   62.73     697   64.53   732.6   64.69   747.4   66.14   756.2   66.19
#Mann= 3 , 0 , 0
       0     .11       0   516.7     .04       0   616.6     .11       0
Bank Sta=516.7,616.6
XS Rating Curve= 0 ,0
Exp/Cntr=0.3,0.1

Type RM Length L Ch R = 1 ,11731   ,198,198,198
BEGIN DESCRIPTION:
Mapping XS 329b3da7
END DESCRIPTION:
XS GIS Cut Line= 4
      3934697.19     10002210.37      3934354.68     10001925.14
      3934278.43     10001872.49      3934169.07     10001783.23
#Sta/Elev= 30
       0   65.08    12.7   64.44   105.1   63.49   112.9   62.88   133.8   63.63
   141.6   63.06   168.9   64.29   205.4   64.09   233.4   62.99   261.3   63.52
   283.5   63.04     290   63.64   297.8   62.91   318.6    62.8   339.4   63.35
   361.6   62.42   382.4   62.81   439.7   61.85     445   59.61   460.9    57.4
     467   54.62   475.8   53.41   481.8   51.66   502.8   50.64   511.6   52.39
   526.5   57.39   532.5   59.91   535.7   62.17   553.5   63.16   679.5   64.53
#Mann= 4 ,-1 , 0
       0    .125       0   339.4     .11       0   439.7     .04       0
   535.7    .125       0
#XS Ineff= 2 , 0
          169.02   64.34
Permanent Ineff=
       F       F
Bank Sta=439.7,535.7
XS Rating Curve= 0 ,0
Exp/Cntr=0.3,0.1

Type RM Length L Ch R = 1 ,11533   ,571,571,571
BEGIN DESCRIPTION:
ROGERS GULLY 23.0
END DESCRIPTION:
XS GIS Cut Line= 3
      3934578.15     10001928.42      3934495.93     10001806.28
       3934359.4     10001660.19
#Sta/Elev= 30
       0    64.7    27.2   64.31    42.1   63.36    48.2    63.4    57.1   62.84
    78.1   60.22    84.2   60.21    93.1    60.9    99.1   61.23   105.3   60.87
   114.1   58.41   120.2   57.24   129.1   54.56   135.1   53.37   141.3   50.83
   147.2   50.83   149.6    50.3   156.5   50.57   170.6   52.34     178   54.54
   184.8    55.6   192.1    58.6     199   60.01   206.3   62.12   227.3   61.46
   234.6   61.86   326.5    62.2   333.3   62.41   344.7   64.24   347.2   64.24
#Mann= 4 ,-1 , 0
       0     .15       0    93.1     .11       0   114.1     .04       0
   192.1     .11       0
Bank Sta=114.1,192.1
XS Rating Curve= 0 ,0
Exp/Cntr=0.3,0.1

Type RM Length L Ch R = 1 ,10962   ,422,422,422
BEGIN DESCRIPTION:
Mapping XS 8cf0be0f
END DESCRIPTION:
XS GIS Cut Line= 2
      3935058.18     10001879.11      3935060.79     10001626.51
#Sta/Elev= 24
       0   63.15       8   62.68      18   62.06      28   61.71      38   61.58
      48   61.92      58   61.49      68   58.19      78   54.57      88    51.1
      98   49.11     108   48.95     118   51.22     128   54.14     138    56.8
     148      60     158   60.17     168   59.53     178    60.4     188   61.18
   198.1   62.54   228.1   62.89   247.8   63.09   252.6   63.09
#Mann= 5 ,-1 , 0
       0    .125       0      28     .11       0      58     .04       0
     148     .11       0   198.1    .125       0
Bank Sta=58,148
XS Rating Curve= 0 ,0
Exp/Cntr=0.3,0.1

Type RM Length L Ch R = 1 ,10540   ,568,568,568
BEGIN DESCRIPTION:
Mapping XS fb357211
END DESCRIPTION:
XS GIS Cut Line= 2
      3935478.98     10001905.11      3935484.19     10001665.77
#Sta/Elev= 29
  4883.3   61.97  4887.8   61.97  4897.3   61.67  4907.3   60.45  4917.3   60.39
  4937.4   59.99  4947.4   59.95  4957.4   56.74  4967.4   54.07  4977.4    52.2
  4987.4   48.72  4994.3   47.36  4994.8   46.86    5000   46.86  5000.5   47.36
  5007.4   51.02  5017.4    52.8  5027.4    55.8  5037.4   59.03  5047.4   60.29
  5056.8   60.06  5061.8   60.08  5067.4   60.24  5077.4   60.43  5087.4   60.49
  5097.4   61.19  5107.4   61.44  5117.4   61.97  5122.7   62.27
#Mann= 3 , 0 , 0
  4883.3     .15       0  4957.4     .04       0  5027.4     .11       0
Bank Sta=4957.4,5027.4
XS Rating Curve= 0 ,0
Exp/Cntr=0.3,0.1

Type RM Length L Ch R = 1 ,9972    ,429,429,429
BEGIN DESCRIPTION:
Mapping XS e755e2a5
END DESCRIPTION:
XS GIS Cut Line= 2
      3936057.84     10001900.99      3936038.56     10001681.19
#Sta/Elev= 27
       0   60.29     2.5   60.29      10   60.44      20   59.62      30   59.05
    40.1   59.01    50.1   58.67    56.1   55.54    61.1   55.41    70.2   52.75
    80.2   50.36    90.3   47.42   100.3   47.28   110.3   49.32   120.4   52.43
   130.4   56.26   140.5   59.29   150.5   59.23   160.5   59.01   168.6   59.23
   173.6   59.25   180.6   59.45   190.6   59.51   200.7   59.49   210.7   59.64
   218.2   60.36   220.6   60.36
#Mann= 4 ,-1 , 0
       0     .15       0      20     .11       0    56.1     .04       0
   160.5     .11       0
Bank Sta=61.1,130.4
XS Rating Curve= 0 ,0
Exp/Cntr=0.3,0.1

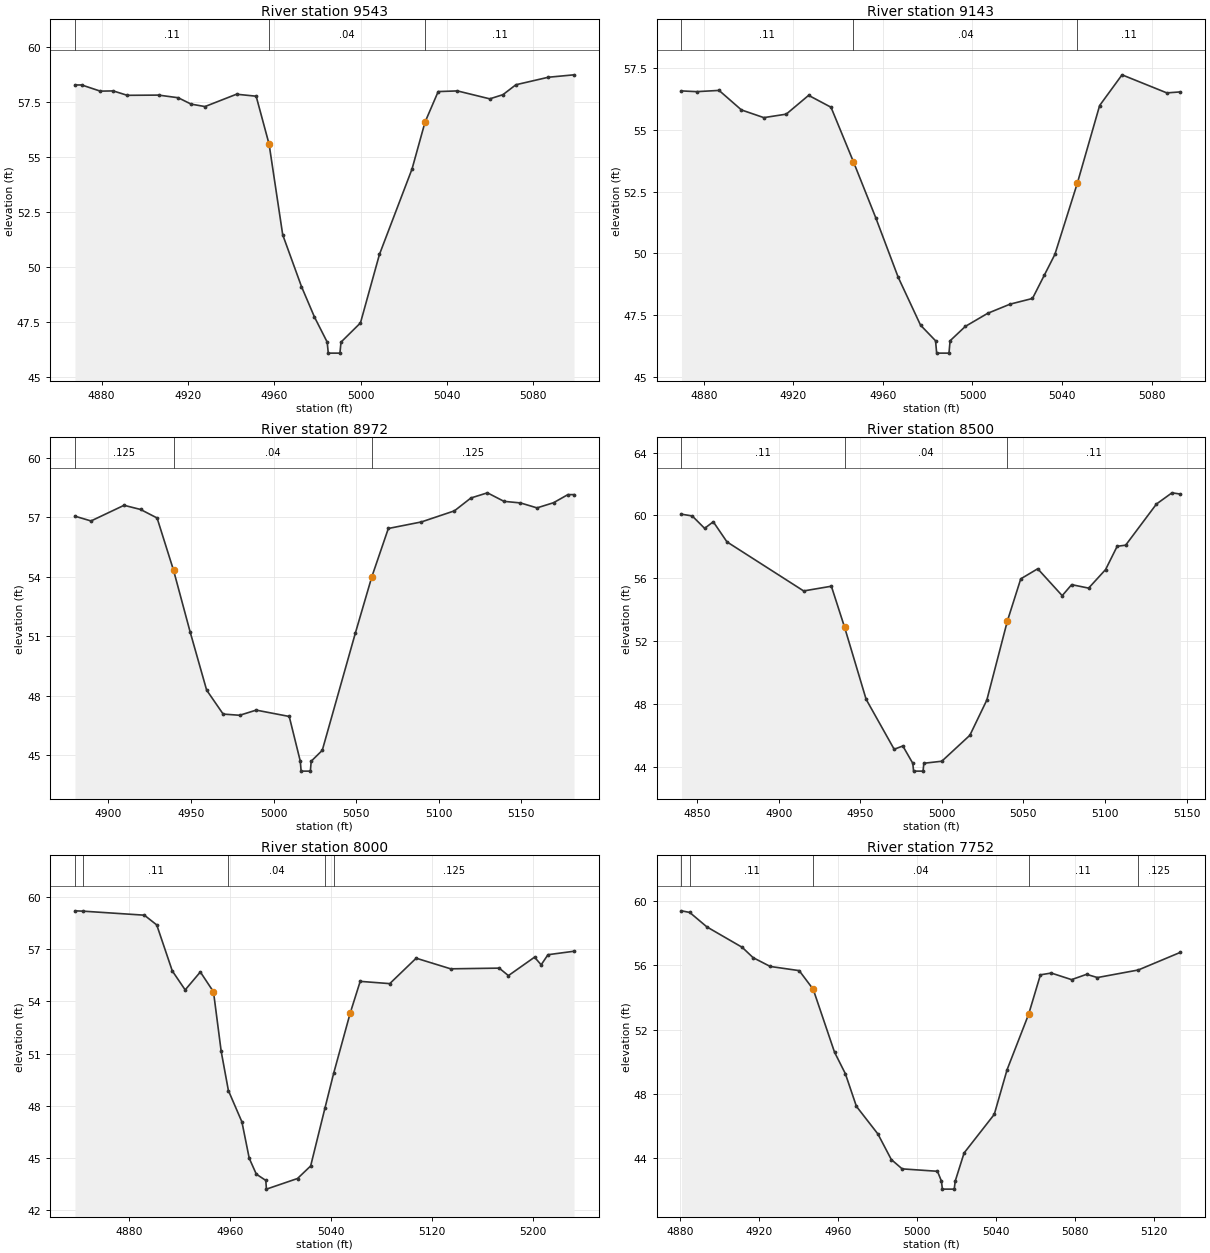
Type RM Length L Ch R = 1 ,9543    ,400,400,400
BEGIN DESCRIPTION:
Mapping XS ab627ea0
END DESCRIPTION:
XS GIS Cut Line= 2
      3936518.06      10001665.5      3936325.37     10001537.91
#Sta/Elev= 30
  4867.7   58.26  4870.8   58.26  4879.4   57.98  4885.4   57.99  4891.9   57.79
  4906.4    57.8  4915.5   57.68  4921.5   57.39  4927.9   57.28  4942.5   57.84
  4951.6   57.75  4957.6   55.57  4963.9   51.46  4972.6   49.11  4978.6   47.73
  4984.5   46.59    4985   46.09  4990.4   46.09  4990.9   46.59  4999.9   47.46
  5008.7   50.57  5023.8   54.45  5029.8   56.57  5035.9   57.96  5044.8   57.99
  5059.8   57.63  5065.9   57.82  5071.9   58.27  5086.9   58.61  5098.8   58.72
#Mann= 3 , 0 , 0
  4867.7     .11       0  4957.6     .04       0  5029.8     .11       0
Bank Sta=4957.6,5029.8
XS Rating Curve= 0 ,0
Exp/Cntr=0.3,0.1

Type RM Length L Ch R = 1 ,9143    ,171,171,171
BEGIN DESCRIPTION:
Mapping XS 02cfffbc
END DESCRIPTION:
XS GIS Cut Line= 2
      3936744.63     10001248.82      3936521.74     10001251.41
#Sta/Elev= 27
    4870   56.57  4876.8   56.54  4886.8   56.59  4896.8    55.8  4906.8   55.49
  4916.8   55.63  4926.8   56.39  4936.8   55.91  4946.8   53.71  4956.8   51.44
  4966.8   49.04  4976.8    47.1  4983.5   46.47    4984   45.97  4989.5   45.97
    4990   46.47  4996.8   47.05  5006.8   47.58  5016.8   47.95  5026.8   48.18
  5032.149.12345  5036.8   49.96  5046.8   52.83  5056.8   55.98  5066.8   57.22
  5086.8   56.49  5092.9   56.53
#Mann= 3 , 0 , 0
    4870     .11       0  4946.8     .04       0  5046.8     .11       0
Bank Sta=4946.8,5046.8
XS Rating Curve= 0 ,0
Exp/Cntr=0.3,0.1

Type RM Length L Ch R = 1 ,8972    ,472,472,472
BEGIN DESCRIPTION:
Mapping XS 0d84ed83
END DESCRIPTION:
XS GIS Cut Line= 2
      3936817.55     10001100.38      3936515.45     10001100.38
#Sta/Elev= 30
  4879.8   57.06  4889.5   56.82  4909.5   57.61  4919.5    57.4  4929.5   56.97
  4939.5   54.32  4949.5   51.22  4959.5   48.28  4969.5   47.07  4979.5   47.01
  4989.5   47.27  5009.5   46.95  5016.2   44.69  5016.7   44.19  5022.3   44.19
  5022.8   44.69  5029.5   45.24  5049.5   51.15  5059.5      54  5069.5   56.44
  5089.5   56.77  5109.5   57.33  5119.5   57.98  5129.5   58.24  5139.5   57.81
  5149.5   57.73  5159.5   57.48  5169.5   57.74  5178.2   58.15  5181.9   58.15
#Mann= 3 , 0 , 0
  4879.8    .125       0  4939.5     .04       0  5059.5    .125       0
Bank Sta=4939.5,5059.5
XS Rating Curve= 0 ,0
Exp/Cntr=0.3,0.1

Type RM Length L Ch R = 1 ,8500    ,500,500,500
BEGIN DESCRIPTION:
ROGERS GULLY 17.0
END DESCRIPTION:
XS GIS Cut Line= 3
      3936854.01     10000600.37      3936704.34     10000655.78
      3936563.77     10000696.32
#Sta/Elev= 30
  4840.4   60.08    4847   59.97  4854.6   59.18  4859.9    59.6  4868.3   58.32
  4915.3    55.2  4932.3    55.5  4940.4   52.89  4953.6   48.31  4970.8   45.13
  4976.1   45.34  4982.2   44.24  4982.7   43.74  4988.5   43.74    4989   44.24
    5000   44.37  5017.2   46.02  5027.6   48.26  5040.2   53.29  5048.4   55.97
  5058.8   56.61  5073.8    54.9  5079.6    55.6    5090   55.38  5100.4   56.56
  5107.5   58.04  5112.7   58.11  5131.6   60.73  5141.1   61.44  5146.3   61.36
#Mann= 3 , 0 , 0
  4840.4     .11       0  4940.4     .04       0  5040.2     .11       0
Bank Sta=4940.4,5040.2
XS Rating Curve= 0 ,0
Exp/Cntr=0.3,0.1

Type RM Length L Ch R = 1 ,8000    ,248,248,248
BEGIN DESCRIPTION:
ROGERS GULLY 16.0
END DESCRIPTION:
XS GIS Cut Line= 3
      3936575.34     10000162.88      3936430.77      10000237.3
      3936208.11     10000303.52
#Sta/Elev= 30
  4837.4    59.2    4844   59.18  4892.3   58.95  4902.1   58.39  4914.4   55.75
  4924.6   54.66  4936.6   55.69    4947   54.55  4953.1   51.13  4958.8   48.88
  4969.5   47.08  4975.3   44.99  4980.9   44.08  4988.4   43.72  4988.9   43.22
  5013.5   43.83  5023.9   44.55  5035.2   47.87  5042.1   49.87  5055.2   53.33
  5063.1   55.15  5086.5   55.02  5107.4   56.48  5134.7   55.87  5173.1   55.91
  5180.4   55.48  5201.1   56.54  5206.3    56.1  5211.7   56.68  5232.3   56.88
#Mann= 5 ,-1 , 0
  4837.4    .125       0    4844     .11       0  4958.8     .04       0
  5035.2     .11       0  5042.1    .125       0
Bank Sta=4947,5055.2
XS Rating Curve= 0 ,0
Exp/Cntr=0.3,0.1

Type RM Length L Ch R = 1 ,7752    ,140,140,140
BEGIN DESCRIPTION:
Mapping XS f32838ca
END DESCRIPTION:
XS GIS Cut Line= 2
      3936419.06      9999972.79      3936187.33     10000074.34
#Sta/Elev= 30
  4880.5    59.4  4884.7    59.3  4893.4    58.4  4911.3   57.13  4916.8   56.49
  4925.5   55.94  4940.2   55.68  4947.3   54.52  4958.1   50.61  4963.6   49.27
  4969.2   47.24  4980.1   45.52  4986.9   43.93  4992.4   43.35  5010.3    43.2
  5012.3   42.59  5012.8   42.09  5018.8   42.09  5019.3   42.59  5023.8   44.34
  5039.1   46.74  5045.6   49.52  5056.5   52.96  5062.5   55.42    5068   55.53
  5078.3   55.12  5085.9   55.45  5091.4   55.25  5112.1   55.72  5133.5   56.82
#Mann= 5 ,-1 , 0
  4880.5    .125       0  4884.7     .11       0  4947.3     .04       0
  5056.5     .11       0  5112.1    .125       0
Bank Sta=4947.3,5056.5
XS Rating Curve= 0 ,0
Exp/Cntr=0.3,0.1

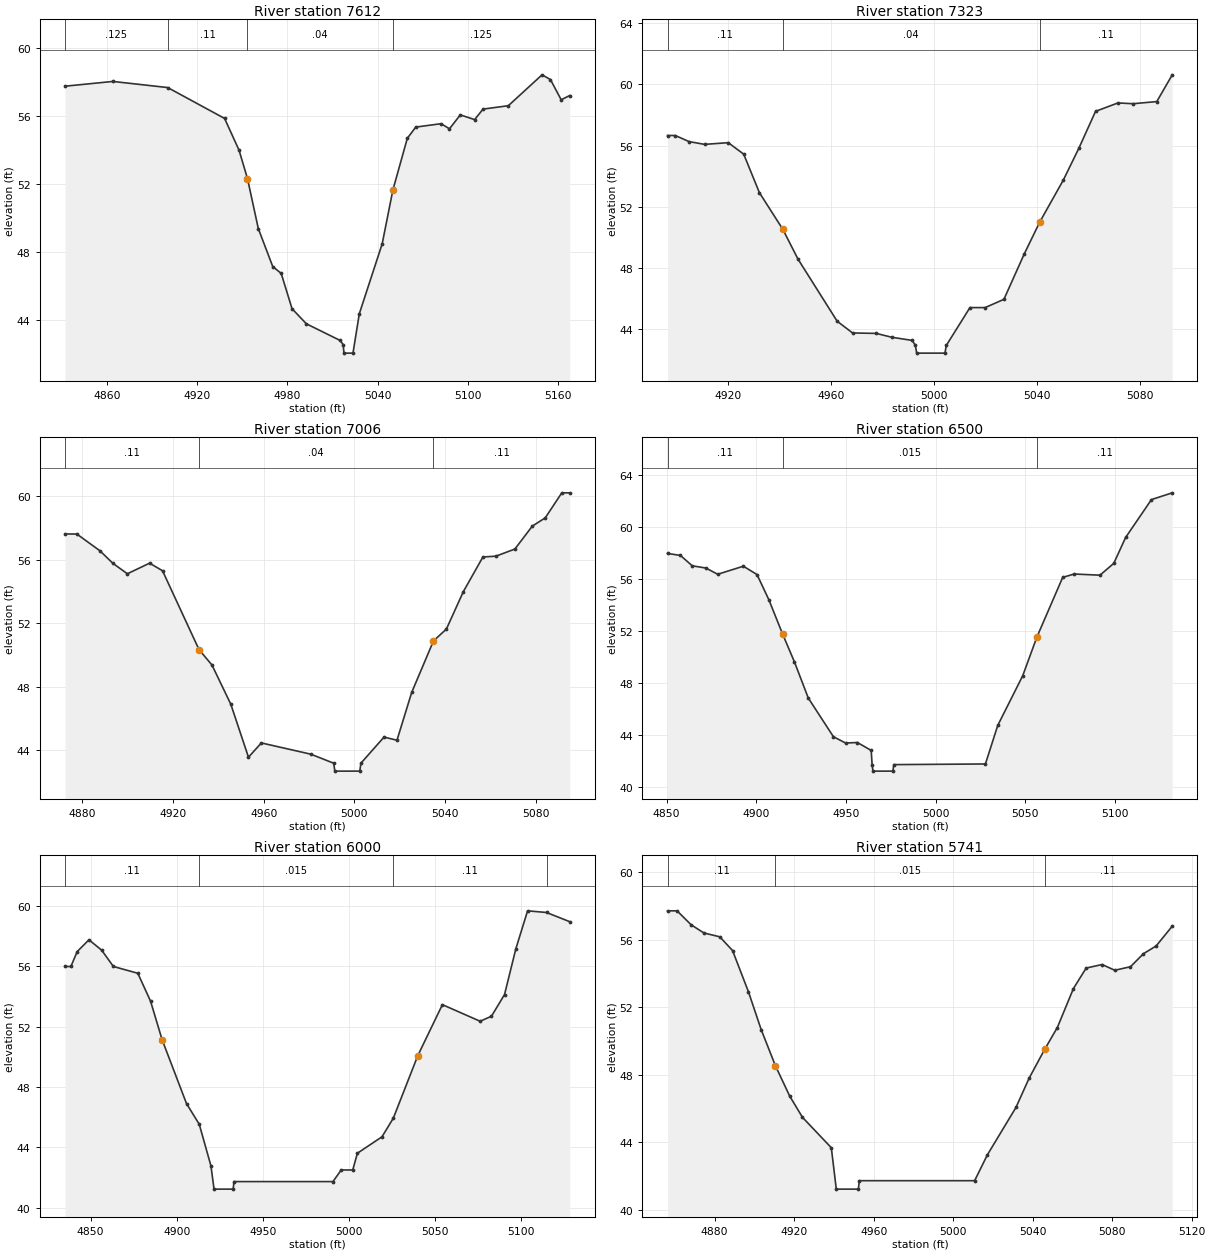
Type RM Length L Ch R = 1 ,7612    ,289,289,289
BEGIN DESCRIPTION:
ROGERS GULLY 15.0
END DESCRIPTION:
XS GIS Cut Line= 2
      3936392.69      9999822.58      3936092.79      9999972.53
#Sta/Elev= 30
  4832.3   57.77  4864.1   58.05  4900.5   57.69  4938.3   55.87  4947.9      54
  4953.5   52.33  4960.7   49.38  4970.3   47.14  4975.9   46.74  4983.1   44.66
  4992.6   43.77    5015   42.79  5017.1   42.54  5017.6   42.04  5023.6   42.04
  5027.8   44.36    5043   48.48  5050.1   51.65  5059.7    54.7  5065.3   55.36
  5082.1   55.56  5087.7   55.26  5094.9   56.08  5104.4    55.8    5110   56.42
  5126.8   56.62  5149.2   58.44  5154.8   58.16  5161.9   56.97  5167.6   57.22
#Mann= 4 ,-1 , 0
  4832.3    .125       0  4900.5     .11       0  4953.5     .04       0
  5050.1    .125       0
Bank Sta=4953.5,5050.1
XS Rating Curve= 0 ,0
Exp/Cntr=0.3,0.1

Type RM Length L Ch R = 1 ,7323    ,317,317,317
BEGIN DESCRIPTION:
Mapping XS b83f1562
END DESCRIPTION:
XS GIS Cut Line= 2
      3936327.91      9999701.92      3936162.79      9999596.14
#Sta/Elev= 30
  4896.4   56.66  4899.4   56.66  4904.8   56.26  4910.8   56.08    4920   56.19
    4926   55.44  4932.1   52.92  4941.2   50.52  4947.1   48.57  4962.3   44.51
  4968.3   43.74  4977.5   43.71  4983.5   43.46  4991.5   43.25  4992.7   42.92
  4993.2   42.42  5004.2   42.42  5004.7   42.92  5013.9    45.4  5019.8    45.4
  5027.1   45.94    5035   48.91    5041   50.99  5050.2   53.75  5056.2   55.82
  5062.7   58.24  5071.4   58.79  5077.3   58.74  5086.5   58.88  5092.5   60.63
#Mann= 3 , 0 , 0
  4896.4     .11       0  4941.2     .04       0    5041     .11       0
Bank Sta=4941.2,5041
XS Rating Curve= 0 ,0
Exp/Cntr=0.3,0.1

Type RM Length L Ch R = 1 ,7006    ,506,506,506
BEGIN DESCRIPTION:
Mapping XS 06d69a14
END DESCRIPTION:
XS GIS Cut Line= 2
      3936491.98      9999425.89      3936296.66      9999319.12
#Sta/Elev= 30
  4872.4   57.63  4877.6   57.63  4887.8   56.57  4893.5   55.78  4899.9   55.12
  4909.7   55.79  4915.4   55.31  4931.5   50.33  4937.2   49.36  4945.5   46.89
  4953.3   43.54    4959   44.44  4980.8   43.73  4990.9   43.16  4991.4   42.66
  5002.4   42.66  5002.9   43.16  5013.1   44.81  5018.8   44.61  5025.3   47.63
  5034.9   50.88  5040.6   51.63  5048.1      54  5056.7   56.18  5062.4   56.23
  5070.8   56.68  5078.5   58.13  5084.2   58.65  5091.5   60.23    5095   60.23
#Mann= 3 , 0 , 0
  4872.4     .11       0  4931.5     .04       0  5034.9     .11       0
Bank Sta=4931.5,5034.9
XS Rating Curve= 0 ,0
Exp/Cntr=0.3,0.1

Type RM Length L Ch R = 1 ,6500    ,500,500,500
BEGIN DESCRIPTION:
ROGERS GULLY 13.0
END DESCRIPTION:
XS GIS Cut Line= 3
      3936717.88       9999011.1       3936604.7      9998913.42
      3936502.63      9998829.72
#Sta/Elev= 30
  4850.5   57.96  4857.7   57.81  4864.3   57.01  4871.9   56.84  4878.5   56.36
  4892.8   56.98  4900.4   56.34    4907   54.41  4914.7   51.76  4921.3   49.62
    4929   46.85    4943   43.88  4949.8   43.39  4956.4   43.43  4964.1   42.82
  4964.6   41.73  4965.1   41.23  4976.2   41.23  4976.7   41.73  5027.8   41.78
  5034.7   44.75  5048.6   48.56  5056.5   51.53  5070.9   56.12  5077.3   56.38
  5091.7   56.29  5099.4    57.2    5106   59.19  5120.4    62.1    5132   62.62
#Mann= 3 , 0 , 0
  4850.5     .11       0  4914.7    .015       0  5056.5     .11       0
Bank Sta=4914.7,5056.5
XS Rating Curve= 0 ,0
Exp/Cntr=0.3,0.1

Type RM Length L Ch R = 1 ,6000    ,259,259,259
BEGIN DESCRIPTION:
ROGERS GULLY 12.0
END DESCRIPTION:
XS GIS Cut Line= 3
      3937067.87      9998661.09      3936946.43      9998549.53
       3936862.3      9998452.53
#Sta/Elev= 30
  4835.1   55.99  4838.5   55.99  4842.2   56.98    4849   57.76  4856.4   57.07
  4863.2   55.99  4877.4   55.54  4884.8   53.69  4891.5   51.14  4905.7    46.9
  4913.1   45.53  4919.9   42.77  4921.7   41.23  4932.8   41.23  4933.3   41.73
  4990.8   41.73  4995.6    42.5  5002.3    42.5    5005   43.61  5019.3    44.7
  5025.9   45.94  5040.1   50.08  5054.4   53.46  5076.3   52.36  5082.9   52.69
  5090.5   54.13  5097.1   57.17  5103.9   59.68  5114.9   59.57  5128.4   58.96
#Mann= 4 ,-1 , 0
  4835.1     .11       0  4913.1    .015       0  5025.9     .11       0
  5114.9    .125       0
Bank Sta=4891.5,5040.1
XS Rating Curve= 0 ,0
Exp/Cntr=0.3,0.1

Type RM Length L Ch R = 1 ,5741    ,161,161,161
BEGIN DESCRIPTION:
Mapping XS 44ad4891
END DESCRIPTION:
XS GIS Cut Line= 2
      3937231.61      9998493.63      3937073.94      9998294.62
#Sta/Elev= 29
  4856.3   57.71  4861.1   57.71  4868.2   56.88  4874.6    56.4  4882.6   56.17
    4889   55.36    4897   52.92  4903.4   50.68  4910.6   48.53  4917.8   46.73
  4924.2   45.48  4938.7   43.68  4941.2   41.23  4952.3   41.23  4952.8   41.73
  5010.8   41.73  5017.2   43.26  5031.6   46.07  5038.2    47.8    5046    49.5
  5052.4    50.8  5060.5   53.11  5066.9   54.32  5074.9   54.53  5081.3   54.19
  5089.2    54.4  5095.7   55.17  5102.1   55.63  5110.2    56.8
#Mann= 3 , 0 , 0
  4856.3     .11       0  4910.6    .015       0    5046     .11       0
Bank Sta=4910.6,5046
XS Rating Curve= 0 ,0
Exp/Cntr=0.3,0.1