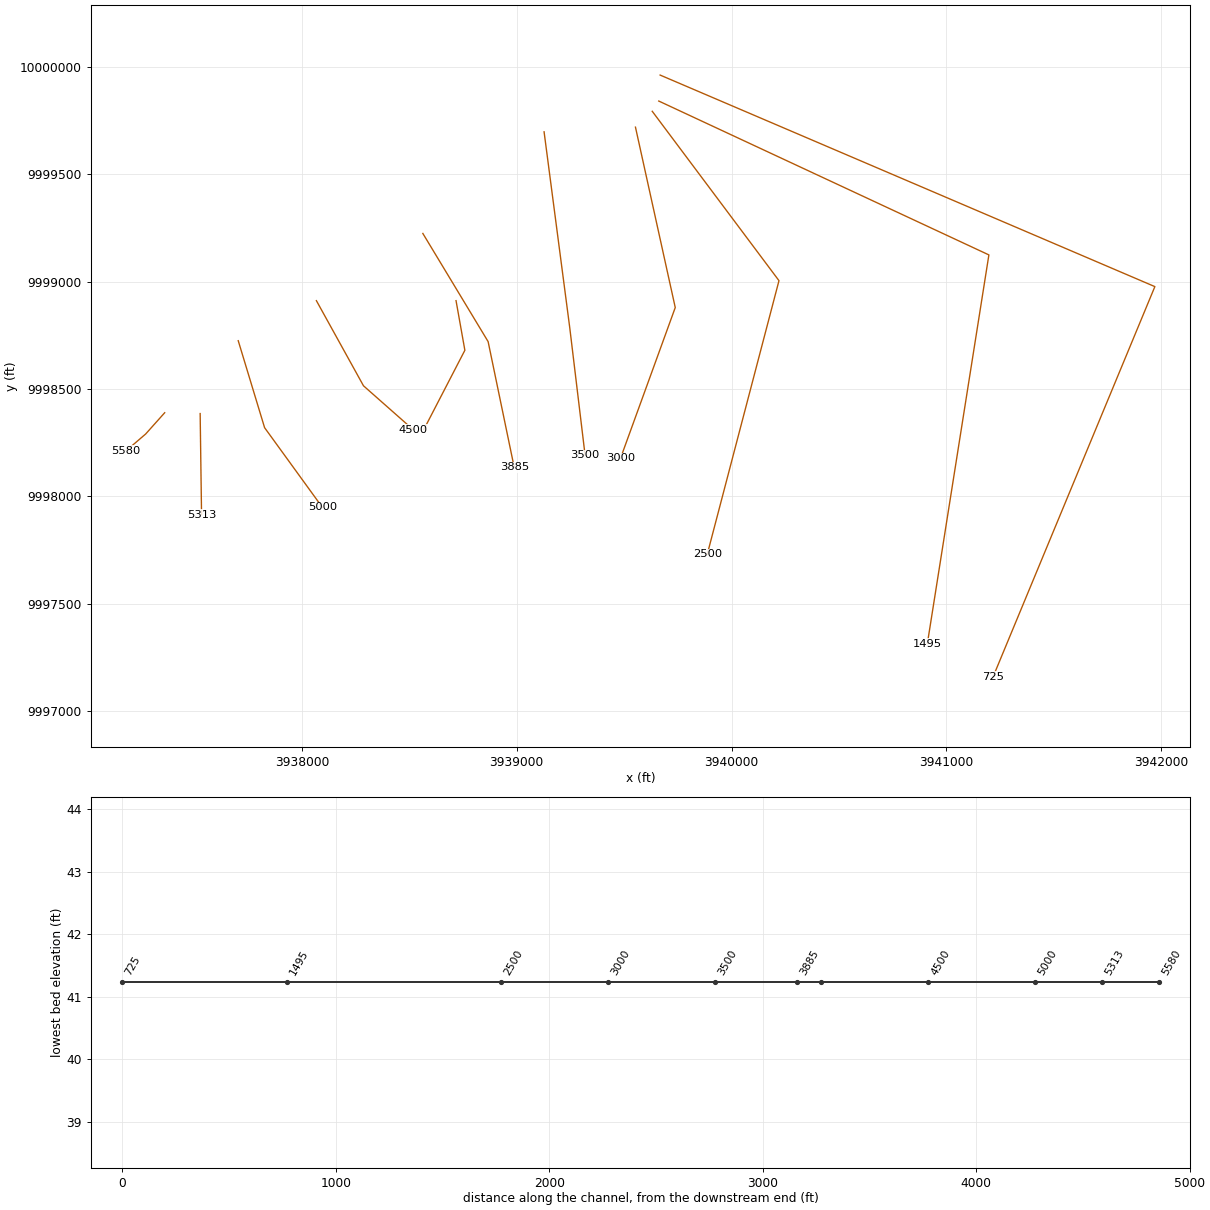
HEC-RAS study ROGERS GULLY.prj: ROGERS GULLY Base Level Engineering

--- ROGERS GULLY.g01 (geometry) --- (continued)

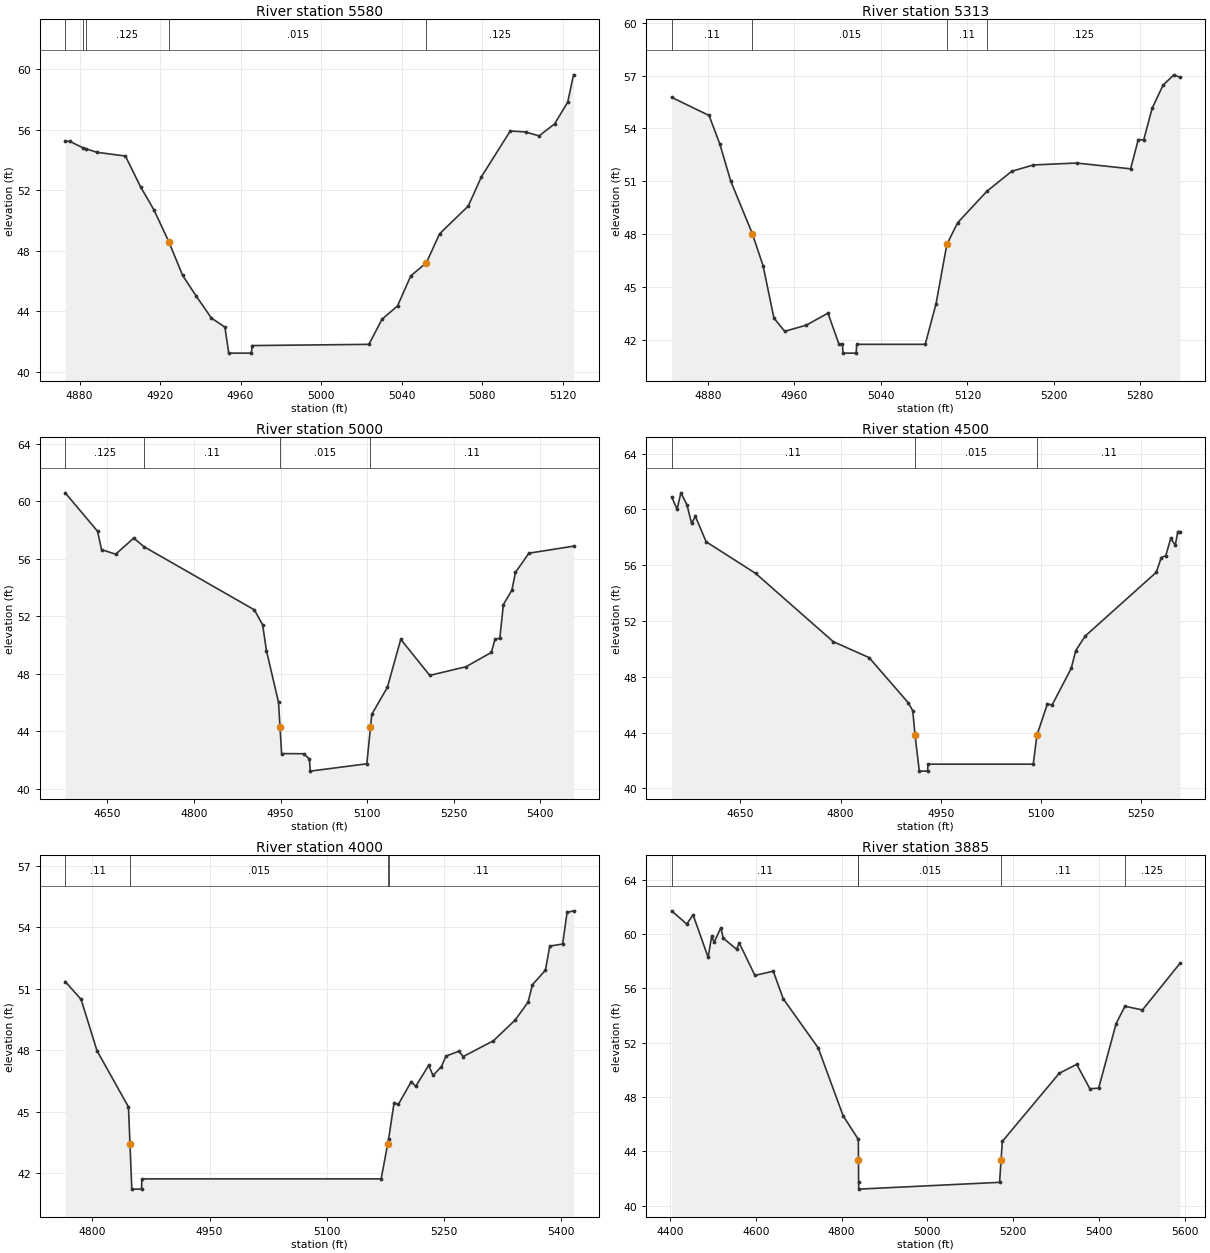
Type RM Length L Ch R = 1 ,5580    ,267,267,267
BEGIN DESCRIPTION:
ROGERS GULLY 11.0
END DESCRIPTION:
XS GIS Cut Line= 3
      3937361.82      9998389.48      3937273.26      9998290.49
      3937182.47      9998212.67
#Sta/Elev= 30
  4872.9   55.23  4875.2   55.23  4881.8    54.8  4883.2   54.74  4888.6   54.51
  4902.8   54.26  4910.3   52.23    4917   50.69  4924.4   48.58  4931.2   46.37
    4938   44.99  4945.5   43.55  4952.2   42.95  4954.1   41.23  4965.3   41.23
  4965.8   41.73  5023.7   41.81  5030.2   43.47  5037.9   44.35  5044.5   46.34
  5052.2    47.2  5058.8   49.12    5073   50.95  5079.6    52.9  5093.9   55.92
  5101.6   55.85  5108.2   55.59  5115.9   56.39  5122.4   57.82  5125.3   59.63
#Mann= 5 ,-1 , 0
  4872.9    .125       0  4881.8     .11       0  4883.2    .125       0
  4924.4    .015       0  5052.2    .125       0
Bank Sta=4924.4,5052.2
XS Rating Curve= 0 ,0
Exp/Cntr=0.3,0.1

Type RM Length L Ch R = 1 ,5313    ,313,313,313
BEGIN DESCRIPTION:
Mapping XS 628176de
END DESCRIPTION:
XS GIS Cut Line= 2
      3937526.86      9998385.62      3937533.36      9997915.37
#Sta/Elev= 30
  4846.4   55.76    4881   54.73    4891    53.1    4901   51.01    4921   48.02
    4931   46.19    4941   43.22    4951   42.47    4971   42.82    4991    43.5
    5001   41.77  5004.4   41.73  5004.9   41.23  5017.1   41.23  5017.6   41.73
    5081   41.73    5091   44.04    5101   47.41    5111   48.64  5138.1   50.43
    5161   51.56    5181   51.92    5221   52.03    5271    51.7  5278.1   53.36
  5283.1   53.34    5291   55.15    5301   56.45    5311   57.04  5316.7    56.9
#Mann= 4 ,-1 , 0
  4846.4     .11       0    4921    .015       0    5101     .11       0
  5138.1    .125       0
Bank Sta=4921,5101
XS Rating Curve= 0 ,0
Exp/Cntr=0.3,0.1

Type RM Length L Ch R = 1 ,5000    ,500,500,500
BEGIN DESCRIPTION:
ROGERS GULLY 10.0
END DESCRIPTION:
XS GIS Cut Line= 3
      3937704.04       9998724.7      3937826.81       9998319.8
      3938095.41      9997949.45
#Sta/Elev= 30
  4576.9   60.59  4632.9   57.92  4639.9   56.64  4664.3   56.32  4695.6   57.44
  4713.5   56.84  4904.6   52.45  4918.9   51.41  4925.5   49.62  4946.4   46.02
 4949.0444.27454  4951.8   42.45  4989.9   42.44    5000   42.08  5001.3   41.23
  5099.4   41.74 5105.73  44.272    5108   45.18    5135   47.06  5158.2    50.4
  5208.4   47.89  5271.1   48.49  5315.2   49.49  5321.3    50.4  5329.8   50.48
    5336   52.82  5350.7   53.82  5356.9   55.05  5380.1   56.39  5457.5   56.88
#Mann= 4 ,-1 , 0
  4576.9    .125       0  4713.5     .11       0 4949.04    .015       0
 5105.73     .11       0
Bank Sta=4949.04,5105.73
XS Rating Curve= 0 ,0
Exp/Cntr=0.3,0.1

Type RM Length L Ch R = 1 ,4500    ,500,500,500
BEGIN DESCRIPTION:
ROGERS GULLY 9.0
END DESCRIPTION:
XS GIS Cut Line= 3
      3938067.84       9998911.1      3938287.04      9998514.89
      3938517.83      9998311.09
#Sta/Elev= 30
  4547.2    60.9  4555.3   60.02    4561   61.19  4570.1   60.33    4577      59
  4582.7    59.5  4598.8   57.68  4672.9   55.41  4788.9   50.52  4842.7   49.37
  4901.5   46.12    4908   45.56 4911.3943.81146  4917.8   41.23  4930.2   41.23
  4930.7   41.73  5088.3   41.73 5093.8343.80998  5109.2   46.02  5116.8      46
  5145.2   48.61  5151.9   49.88  5166.1   50.92  5272.4   55.49  5279.9   56.55
  5286.6   56.68  5294.1   57.93  5300.8   57.43  5304.6   58.41  5307.9   58.41
#Mann= 3 , 0 , 0
  4547.2     .11       0 4911.39    .015       0 5093.83     .11       0
Bank Sta=4911.39,5093.83
XS Rating Curve= 0 ,0
Exp/Cntr=0.3,0.1

Type RM Length L Ch R = 1 ,4000    ,115,115,115
BEGIN DESCRIPTION:
ROGERS GULLY 8.0
END DESCRIPTION:
XS GIS Cut Line= 3
      3938717.85      9998911.08      3938758.96      9998680.11
      3938567.84      9998311.05
#Sta/Elev= 30
  4765.4   51.36  4785.7   50.49    4806   47.99  4846.3   45.24 4848.2543.43877
  4850.6   41.23    4863   41.23  4863.5   41.73  5169.5   41.73 5177.8943.43423
  5179.1   43.68    5186   45.43  5191.6   45.37  5208.1   46.48  5213.7   46.24
  5230.3   47.27  5235.9   46.78  5246.7   47.21  5252.4   47.72  5268.9   47.96
  5274.5    47.7  5313.2   48.47  5340.9   49.48  5357.4   50.35  5363.1   51.21
  5379.6   51.91  5385.2   53.09  5401.7   53.19  5407.3   54.73  5415.6   54.81
#Mann= 4 ,-1 , 0
  4765.4     .11       0 4848.25    .015       0 5177.89     .08       0
  5179.1     .11       0
Bank Sta=4848.25,5177.89
XS Rating Curve= 0 ,0
Exp/Cntr=0.3,0.1

Type RM Length L Ch R = 1 ,3885    ,385,385,385
BEGIN DESCRIPTION:
Mapping XS c7416be0
END DESCRIPTION:
XS GIS Cut Line= 3
       3938563.4      9999223.87      3938867.22      9998720.39
      3938988.58      9998135.29
#Sta/Elev= 30
  4403.7    61.7  4438.8   60.73  4453.7    61.4  4488.7   58.28    4497   59.82
  4502.8   59.39  4518.3   60.45  4524.2   59.68  4555.2   58.87  4561.1   59.35
  4597.9   56.95  4640.6   57.26  4663.9   55.23  4745.4   51.62  4803.7   46.62
  4839.1   44.89 4839.3943.36271  4839.7   41.73  4840.2   41.23  5168.5   41.73
 5171.9743.36211  5174.9   44.74  5307.6   49.75  5348.5   50.41  5379.1   48.61
  5399.6   48.66  5440.4   53.41  5460.8   54.68  5501.7   54.41  5589.3   57.84
#Mann= 5 ,-1 , 0
  4403.7     .11       0  4839.1     .08       0 4839.39    .015       0
 5171.97     .11       0  5460.8    .125       0
Bank Sta=4839.39,5171.97
XS Rating Curve= 0 ,0
Exp/Cntr=0.3,0.1

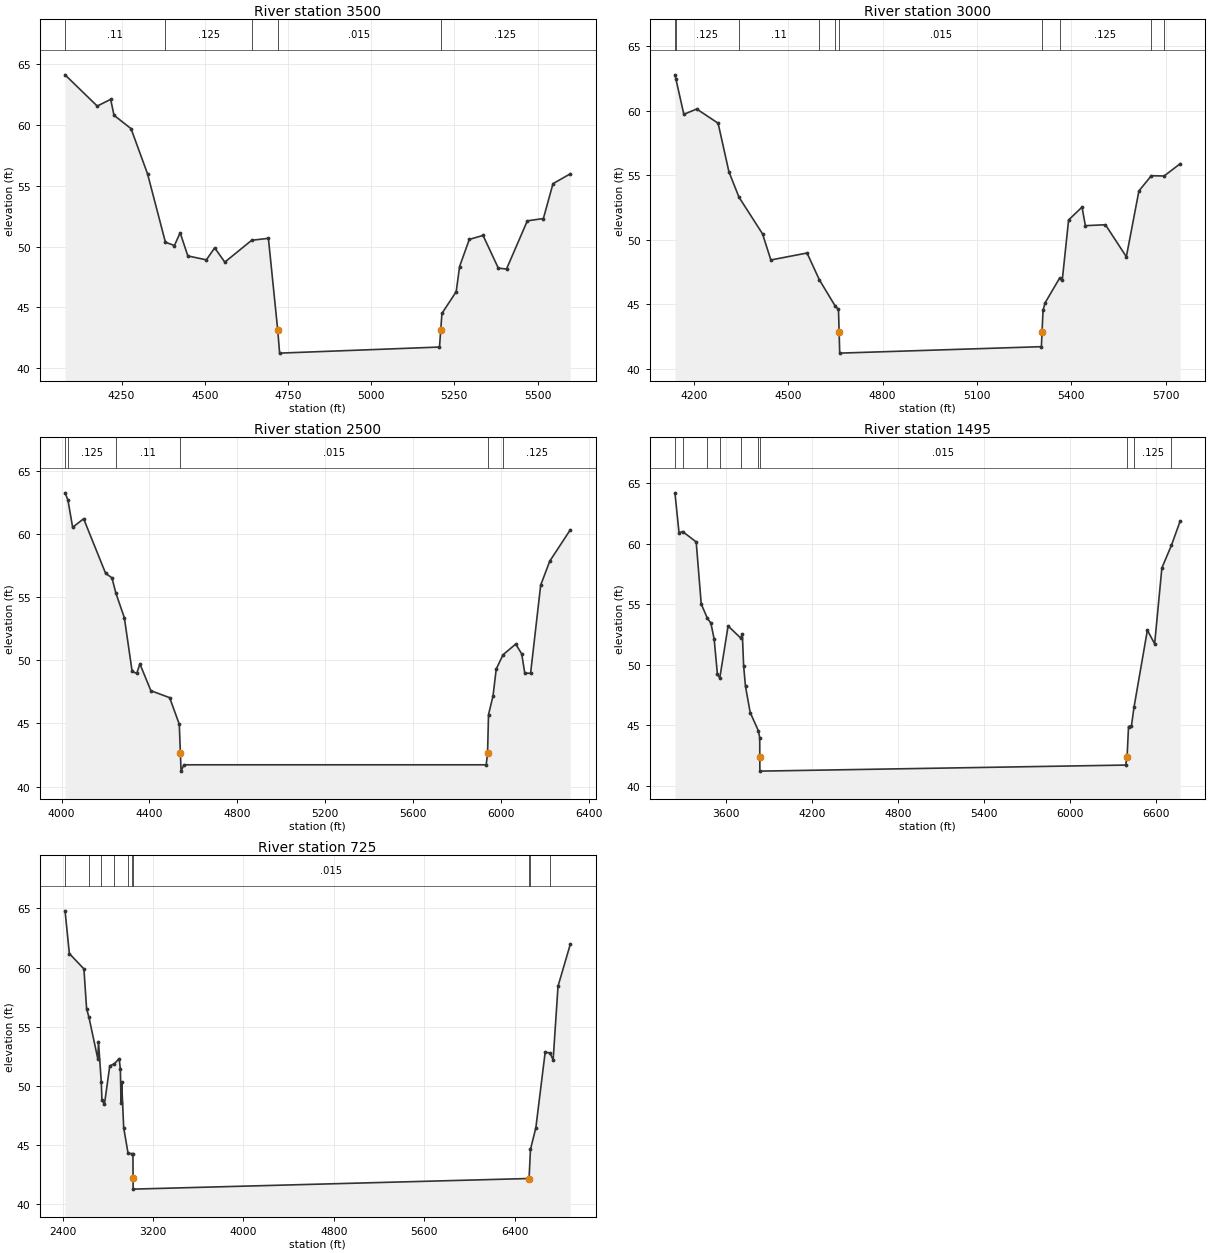
Type RM Length L Ch R = 1 ,3500    ,500,500,500
BEGIN DESCRIPTION:
ROGERS GULLY 7.0
END DESCRIPTION:
XS GIS Cut Line= 3
      3939127.64      9999696.97      3939247.16      9998784.87
      3939318.62      9998190.85
#Sta/Elev= 30
  4080.1   64.14  4176.8   61.57  4217.2   62.12  4227.2   60.81  4278.4   59.71
  4328.1   55.98  4381.7   50.36  4408.8   50.09    4426   51.14  4449.1   49.23
  4504.8   48.91  4529.8    49.9  4560.1   48.72    4641   50.52  4691.2   50.68
 4719.17 43.1369  4724.9   41.23  5205.3   41.73 5209.0543.13781  5212.7    44.5
  5255.6   46.29  5265.7   48.36  5294.9   50.59  5336.2   50.92  5382.1   48.23
  5406.7   48.15  5469.3   52.12  5517.5   52.31  5546.4   55.18  5598.3   55.99
#Mann= 5 ,-1 , 0
  4080.1     .11       0  4381.7    .125       0    4641     .11       0
 4719.17    .015       0 5209.05    .125       0
Bank Sta=4719.17,5209.05
XS Rating Curve= 0 ,0
Exp/Cntr=0.3,0.1

Type RM Length L Ch R = 1 ,3000    ,500,500,500
BEGIN DESCRIPTION:
ROGERS GULLY 6.0
END DESCRIPTION:
XS GIS Cut Line= 3
      3939552.98      9999718.68       3939738.2      9998879.07
      3939483.55      9998177.88
#Sta/Elev= 30
  4140.2    62.8  4143.5   62.45  4168.5   59.74  4209.4   60.15  4277.4   59.05
  4311.8   55.28  4343.7   53.32  4418.7   50.47    4445   48.45  4560.1   48.99
  4599.3   46.91  4649.3   44.89    4660   44.62 4662.0842.85188  4663.9   41.23
  5304.9   41.73    530742.85131  5310.2   44.56    5317   45.14  5362.5   47.03
  5371.4   46.91  5391.4   51.55  5434.1   52.55  5444.7   51.11  5508.5   51.18
    5575    48.7  5614.9    53.8  5654.4   54.98  5695.1   54.96    5746   55.91
#Mann= 10 ,-1 , 0
  4140.2     .11       0  4143.5    .125       0  4343.7     .11       0
  4599.3    .125       0  4649.3     .11       0 4662.08    .015       0
    5307     .11       0  5362.5    .125       0  5654.4     .11       0
  5695.1    .125       0
Bank Sta=4662.08,5307
XS Rating Curve= 0 ,0
Exp/Cntr=0.3,0.1

Type RM Length L Ch R = 1 ,2500    ,1005,1005,1005
BEGIN DESCRIPTION:
ROGERS GULLY 5.0
END DESCRIPTION:
XS GIS Cut Line= 3
      3939631.13      9999792.42      3940220.96      9999004.16
      3939887.18      9997730.78
#Sta/Elev= 30
  4015.5   63.24  4028.6   62.67  4050.1   60.51  4100.1   61.19  4200.1   56.88
  4229.3   56.51  4246.9   55.31  4285.6   53.36    4321   49.12  4341.9   48.96
  4356.4   49.71  4406.4   47.59  4491.9   47.04  4535.7   44.94  4540.842.66152
  4543.8   41.23  4557.1   41.73  5933.6   41.73 5939.7742.66073  5944.1    45.7
  5964.6   47.17  5979.3   49.31  6010.2   50.43    6068   51.28  6095.3    50.5
  6109.3   48.98  6135.7   48.97  6181.7   55.94  6223.1   57.84  6316.4   60.31
#Mann= 6 ,-1 , 0
  4015.5     .11       0  4028.6    .125       0  4246.9     .11       0
  4540.8    .015       0 5939.77     .11       0  6010.2    .125       0
Bank Sta=4540.8,5939.77
XS Rating Curve= 0 ,0
Exp/Cntr=0.3,0.1

Type RM Length L Ch R = 1 ,1495    ,770,770,770
BEGIN DESCRIPTION:
ROGERS GULLY 3.0
END DESCRIPTION:
XS GIS Cut Line= 3
      3939661.49      9999840.18      3941197.95      9999124.04
      3940911.65      9997315.12
#Sta/Elev= 30
  3243.6   64.18  3272.1   60.88    3297   60.99  3391.9   60.13  3427.1   55.01
  3470.7   53.82  3494.4   53.44  3517.3   52.12  3540.2   49.21  3556.6   48.91
  3614.7    53.2    3703    52.2    3714   52.55  3723.1    49.9  3736.1   48.21
  3768.9   46.06  3825.6   44.57  3835.4   43.99 3835.8242.40763  3836.5   41.23
  6389.6   41.73 6399.9342.41807  6409.8   44.91  6430.1   44.96  6448.5   46.53
  6541.4   52.85  6592.1   51.73  6642.7   57.99  6709.6   59.86  6770.2   61.85
#Mann= 10 ,-1 , 0
  3243.6     .11       0    3297    .125       0  3470.7     .11       0
  3556.6    .125       0    3703     .11       0  3825.6     .08       0
 3835.82    .015       0 6399.93     .11       0  6448.5    .125       0
  6709.6     .11       0
Bank Sta=3835.82,6399.93
XS Rating Curve= 0 ,0
Exp/Cntr=0.3,0.1

Type RM Length L Ch R = 1 ,725     ,0,0,0
BEGIN DESCRIPTION:
ROGERS GULLY 1.0
END DESCRIPTION:
XS GIS Cut Line= 3
      3939667.83      9999961.08      3941970.52      9998976.47
      3941217.85      9997161.08
#Sta/Elev= 30
  2421.4    64.8  2459.5   61.18  2588.4   59.88    2612   56.51  2632.9   55.78
  2711.8   52.24  2717.2   53.72  2741.7   50.32  2747.7   48.79  2769.8   48.41
    2817   51.67  2856.6   51.84    2900   52.28  2910.8    51.4  2916.8   48.55
  2922.3   50.27  2940.4   46.42  2978.6   44.28  3016.6   44.22  3022.1   44.22
 3023.1942.13222  3023.9   41.23 6526.65   42.13  6538.9   44.59  6586.6   46.43
  6669.1   52.83  6710.9   52.76  6739.5   52.18  6782.8   58.42    6891   61.96
#Mann= 10 ,-1 , 0
  2421.4     .11       0  2632.9    .125       0  2741.7     .11       0
  2856.6    .125       0  2978.6     .11       0  3016.6     .08       0
 3023.19    .015       0 6526.65     .08       0  6538.9     .11       0
  6710.9    .125       0
Bank Sta=3023.19,6526.65
XS Rating Curve= 0 ,0
Exp/Cntr=0.3,0.1

Chan Stop Cuts=-1
Use User Specified Reach Order=0
Composite Channel Slope=5