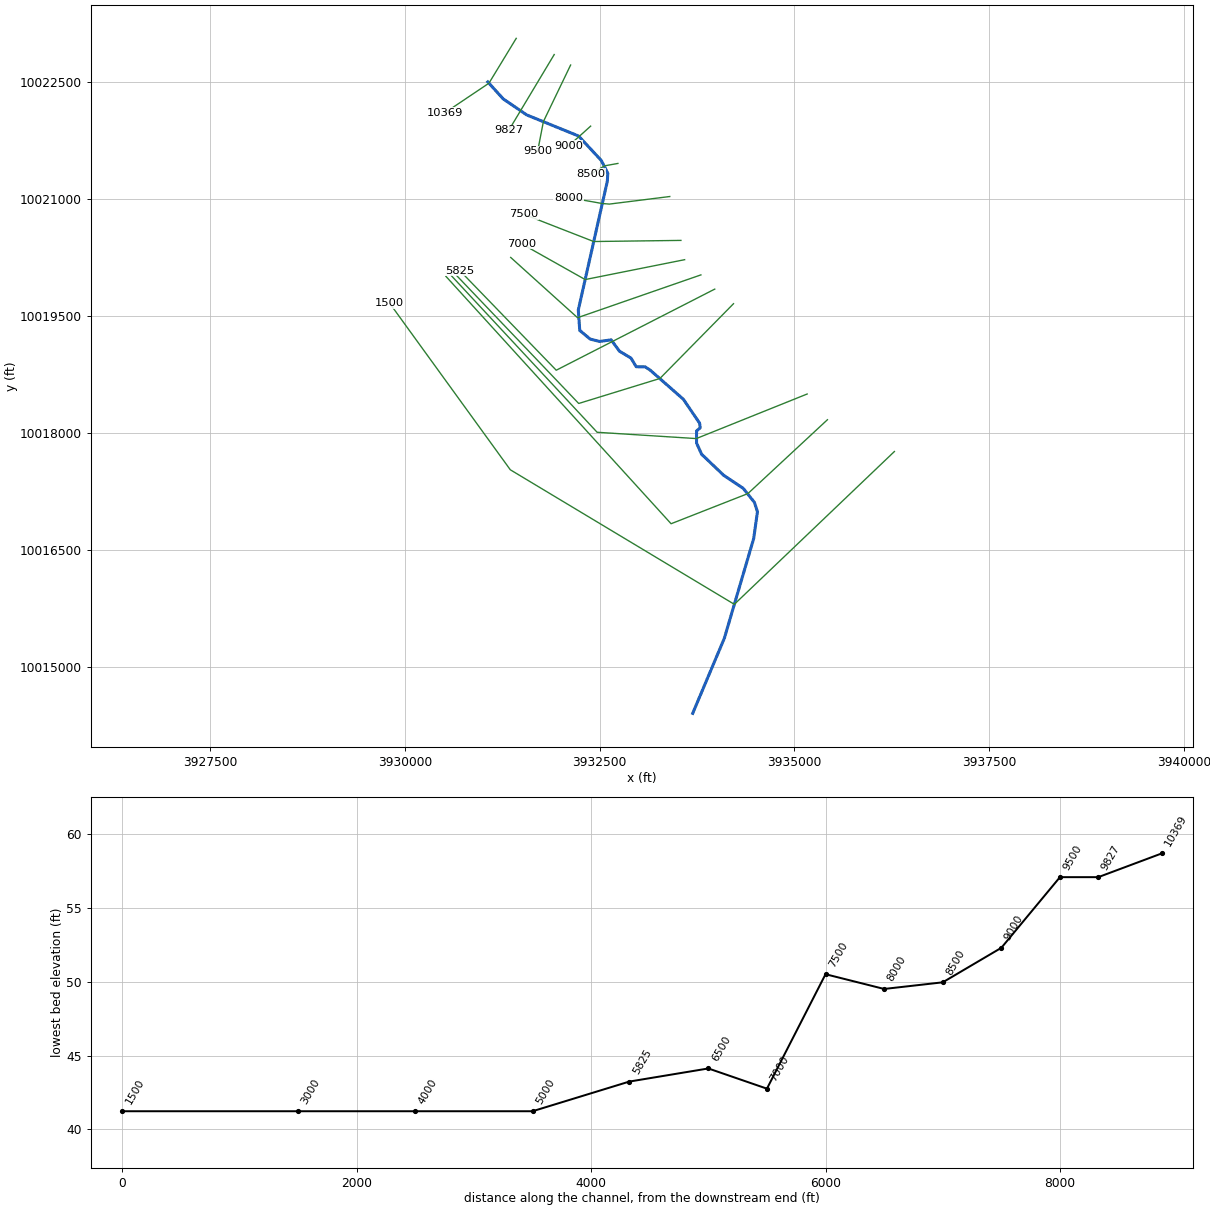
--- SAND BRANCH.prj (project) ---

Proj Title=SAND BRANCH Base Level Engineering
Current Plan=p01
Default Exp/Contr=0.3,0.1
English Units
Geom File=g01
Flow File=f01
Flow File=f02
Plan File=p01
Y Axis Title=Elevation
X Axis Title(PF)=Main Channel Distance
X Axis Title(XS)=Station
BEGIN DESCRIPTION:
SAND BRANCH
END DESCRIPTION:
DSS File=dss
DSS Export Rating Curves= 0
DSS Export Rating Curve Sorted= 0
DSS Export Volume Flow Curves= 0
DXF OffsetX= 0
DXF OffsetY= 0
DXF ScaleX= 1
DXF ScaleY= 10

--- SAND BRANCH.p01 (plan) ---

Plan Title=Multiple Run
Program Version=4.10
Short Identifier=Multiple Run
Geom File=g01
Flow File=f01
Subcritical Flow
K Sum by GR= 0
Std Step Tol= 0.01
Critical Tol= 0.01
Num of Std Step Trials= 20
Max Error Tol= 0.3
Flow Tol Ratio= 0.001
Split Flow NTrial= 30
Split Flow Tol= 0.02
Split Flow Ratio= 0.02
Log Output Level= 0
Friction Slope Method= 1
Unsteady Friction Slope Method= 2
Unsteady Bridges Friction Slope Method= 1
Parabolic Critical Depth
Global Vel Dist= 1 , 1 , 1
Global Log Level= 0
CheckData=True
Encroach Param=-1 ,0,0, 0
BEGIN DESCRIPTION:
Multiple Run
END DESCRIPTION:
Computation Interval=1HOUR
Output Interval=1HOUR
Run HTab= 0
Run UNet= 0
Run PostProcess= 0
Run WQNet= 0
UNET Theta= 1
UNET Theta Warmup= 1
UNET ZTol= 0.02
UNET ZSATol= 0.05
UNET MxIter= 20
UNET MaxInSteps= 0
UNET DtIC= 0
UNET DtMin= 0
UNET MaxCRTS= 20
UNET WFStab= 2
UNET SFStab= 1
UNET WFX= 1
UNET SFX= 1
UNET DSS MLevel= 4
UNET DZMax Abort= 100
UNET Convert EG Bridges= 0
UNET Use Existing IB Tables=-1
UNET Froude Reduction=False
UNET Froude Limit= 1
UNET Froude Power= 10
UNET Time Slicing=0,0, 5
UNET Junction Losses=0
Instantaneous Interval=1HOUR
DSS File=dss
Write IC File= 0
Write IC File at Sim End=0
Echo Input=False
Echo Parameters=False
Echo Output=False
Write Detailed= 0
WQ AD Non Conservative
WQ ULTIMATE=-1
WQ Max Comp Step=1HOUR
WQ Output Interval=15MIN
WQ Output Selected Increments= 0
WQ Output face flow=0
WQ Output face velocity=0
WQ Output face area=0
WQ Output face dispersion=0
WQ Output cell volume=0
WQ Output cell surface area=0
WQ Output cell continuity=0
WQ Output cumulative cell continuity=0
WQ Output face conc=0
WQ Output face dconc_dx=0
WQ Output face courant=0
WQ Output face peclet=0
WQ Output face adv mass=0
WQ Output face disp mass=0
WQ Output cell mass=0
WQ Output cell source sink temp=0
WQ Output cell source sink nsm=0
WQ Output MaxMinRange=-1
WQ Daily Max Min Mean=-1
WQ Daily Range=0
WQ Daily Time=0
WQ Create Restart=0
WQ Fixed Restart=0
WQ System Summary=0
WQ Use Fixed Temperature=0
Sorting and Armoring Iterations= 10
XS Update Threshold= 0.02
Hydraulics Update Threshold= 0.02
Energy Slope Method= 1
Volume Change Method= 0
XS Weighting Method= 0
Number of US Weighted Cross Sections= 1
Number of DS Weighted Cross Sections= 1
Upstream XS Weight=0.25
Main XS Weight=0.5
Downstream XS Weight=0.25
Number of DS XS's Weighted with US Boundary= 1
Upstream Boundary Weight= 1
Weight of XSs Associated with US Boundary= 0
Number of US XS's Weighted with DS Boundary= 1
Downstream Boundary Weight= 0.5
Weight of XSs Associated with DS Boundary= 0.5
Sediment Output Level= 4
Mass or Volume Output= 0
Output Increment Type= 1
Profile and TS Output Increment= 10
XS Output Flag= 0
XS Output Increment= 10
Disregard all LS=0
Disregard all Conn=0
Disregard all Breaches=0
Disregard all Pumps=0

--- SAND BRANCH.f01 (steady flow) ---

Flow Title=Multiple
Program Version=4.10
Number of Profiles= 7
Profile Names=10-year,25-year,50-year,1pct_min,100-year,1pct_plu,500-year
River Rch & RM=SAND BRANCH,Reach-1         ,10369
     347     437     561     237     716    2162    1204
River Rch & RM=SAND BRANCH,Reach-1         ,4000
     732     962    1272     552    1668    5037    2958
Boundary for River Rch & Prof#=SAND BRANCH,Reach-1         , 1
Up Type= 0
Dn Type= 3
Dn Slope=0.00053
Boundary for River Rch & Prof#=SAND BRANCH,Reach-1         , 2
Up Type= 0
Dn Type= 3
Dn Slope=0.00053
Boundary for River Rch & Prof#=SAND BRANCH,Reach-1         , 3
Up Type= 0
Dn Type= 3
Dn Slope=0.00053
Boundary for River Rch & Prof#=SAND BRANCH,Reach-1         , 4
Up Type= 0
Dn Type= 3
Dn Slope=0.00053
Boundary for River Rch & Prof#=SAND BRANCH,Reach-1         , 5
Up Type= 0
Dn Type= 3
Dn Slope=0.00053
Boundary for River Rch & Prof#=SAND BRANCH,Reach-1         , 6
Up Type= 0
Dn Type= 3
Dn Slope=0.00053
Boundary for River Rch & Prof#=SAND BRANCH,Reach-1         , 7
Up Type= 0
Dn Type= 3
Dn Slope=0.00053
DSS Import GetInterval= 0
DSS Import GetPeak= 0
DSS Import FillOption= 0

--- SAND BRANCH.f02 (steady flow) ---

Flow Title=Orig_BLE_Flows
Program Version=4.10
Number of Profiles= 7
Profile Names=10-year,25-year,50-year,1pct_min,100-year,1pct_plu,500-year
River Rch & RM=SAND BRANCH,Reach-1         ,10336
     347     428     488     182     551    1663     700
River Rch & RM=SAND BRANCH,Reach-1         ,4000
     732     943    1106     425    1283    3873    1720
Boundary for River Rch & Prof#=SAND BRANCH,Reach-1         , 1
Up Type= 0
Dn Type= 3
Dn Slope=0.00053
Boundary for River Rch & Prof#=SAND BRANCH,Reach-1         , 2
Up Type= 0
Dn Type= 3
Dn Slope=0.00053
Boundary for River Rch & Prof#=SAND BRANCH,Reach-1         , 3
Up Type= 0
Dn Type= 3
Dn Slope=0.00053
Boundary for River Rch & Prof#=SAND BRANCH,Reach-1         , 4
Up Type= 0
Dn Type= 3
Dn Slope=0.00053
Boundary for River Rch & Prof#=SAND BRANCH,Reach-1         , 5
Up Type= 0
Dn Type= 3
Dn Slope=0.00053
Boundary for River Rch & Prof#=SAND BRANCH,Reach-1         , 6
Up Type= 0
Dn Type= 3
Dn Slope=0.00053
Boundary for River Rch & Prof#=SAND BRANCH,Reach-1         , 7
Up Type= 0
Dn Type= 3
Dn Slope=0.00053
DSS Import GetInterval= 0
DSS Import GetPeak= 0
DSS Import FillOption= 0

--- SAND BRANCH.g01 (geometry) ---

Geom Title=Existing Conditions
Program Version=4.10

River Reach=SAND BRANCH     ,Reach-1
Reach XY= 30
      3931064.62     10022506.71      3931262.55     10022288.97
        3931564.     10022083.55      3932229.56     10021812.81
      3932521.47     10021498.52      3932604.37     10021334.79
      3932599.03     10021234.44       3932226.1     10019580.22
      3932244.82     10019318.05      3932378.23     10019206.84
      3932498.23     10019176.84      3932648.23     10019196.84
        3932754.     10019052.05       3932903.3     10018961.77
      3932969.27      10018852.4      3933083.86     10018850.66
      3933148.09       10018809.      3933575.18       10018434.
      3933782.64     10018127.57      3933790.45     10018067.68
      3933743.58     10018028.61      3933743.58     10017872.36
      3933808.68     10017729.13      3934092.54      10017458.3
      3934342.54     10017291.63      3934485.77     10017111.95
      3934524.83     10016992.16      3934477.21     10016649.53
      3934099.62     10015366.46      3933693.84     10014404.07

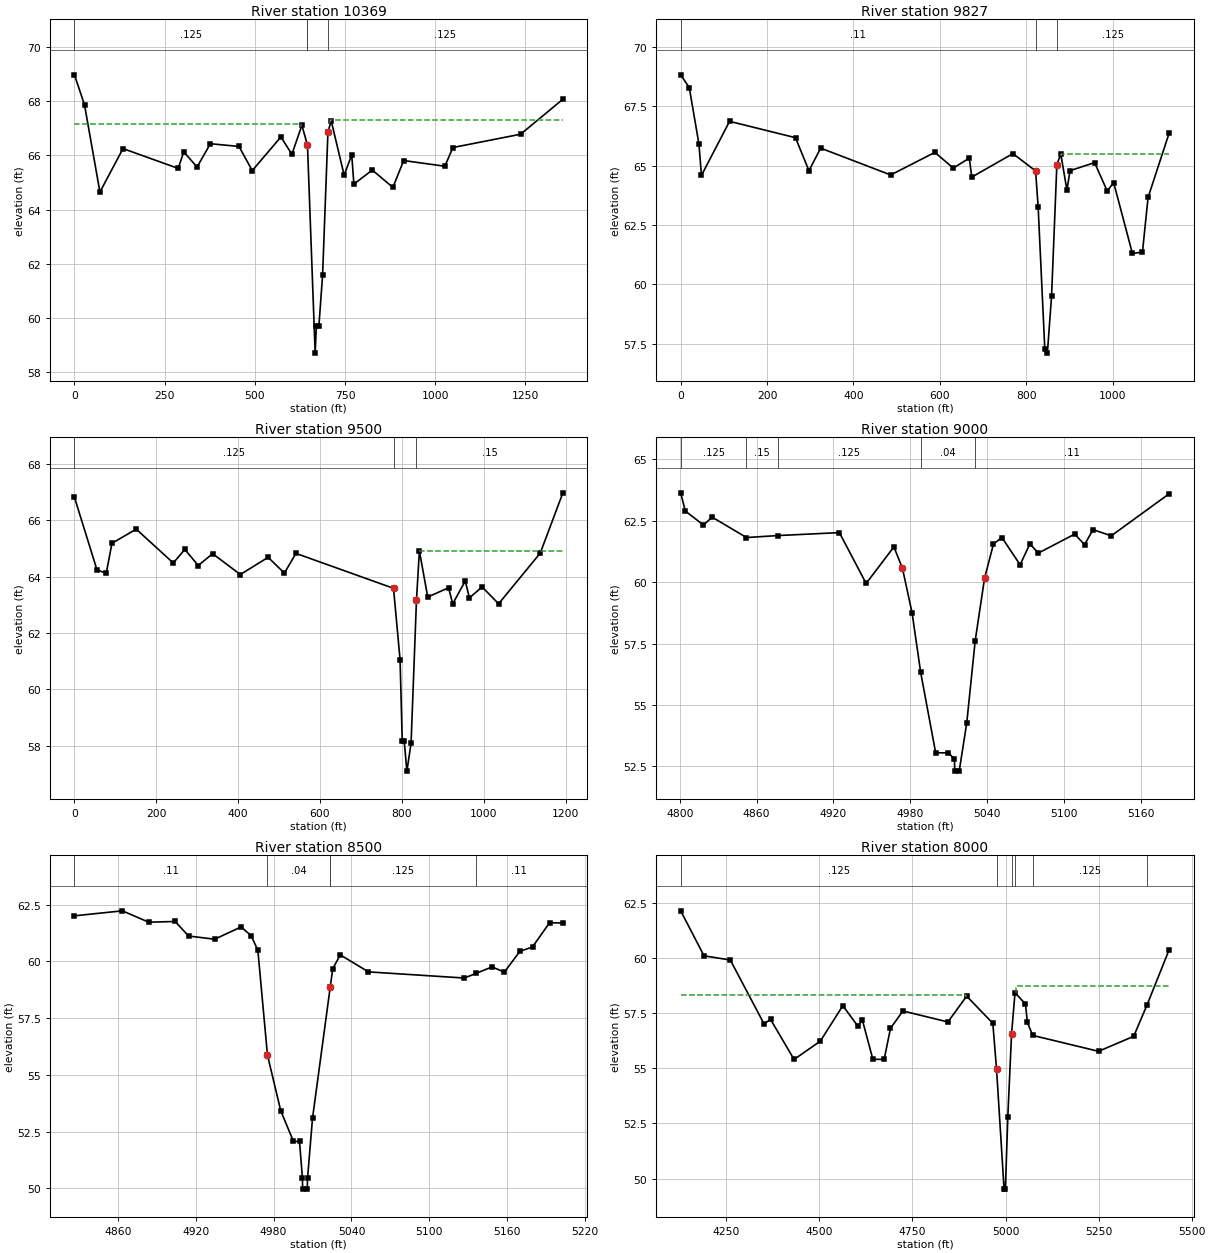
Type RM Length L Ch R = 1 ,10369   ,542,542,542
BEGIN DESCRIPTION:
SAND BRANCH 20.0
END DESCRIPTION:
XS GIS Cut Line= 3
       3931429.7     10023066.07      3931079.52     10022490.31
      3930514.76     10022111.21
#Sta/Elev= 30
       0   68.97    27.9   67.86    70.6   64.65   134.6   66.25   287.6   65.52
   303.1   66.13   339.9   65.57   376.7   66.43   456.1   66.33   492.9   65.44
   572.4   66.68   602.8   66.04   630.5   67.11     646   66.38   667.3   58.71
   670.7   59.72   677.7   59.72   687.9   61.58   702.7   66.85   711.7   67.28
   747.7   65.27   768.7   66.02   774.7   64.94   825.7   65.46   882.8   64.82
   912.7   65.81  1026.8    65.6  1049.3   66.29  1236.8   66.78  1354.1   68.07
#Mann= 4 ,-1 , 0
       0    .125       0     646     .11       0     646     .04       0
   702.7    .125       0
#XS Ineff= 2 , 0
          628.41   67.17  709.72           67.32
Permanent Ineff=
       F       F
Bank Sta=646,702.7
XS Rating Curve= 0 ,0
Exp/Cntr=0.3,0.1

Type RM Length L Ch R = 1 ,9827    ,327,327,327
BEGIN DESCRIPTION:
Mapping XS 2409114b
END DESCRIPTION:
XS GIS Cut Line= 2
      3931917.11     10022858.17      3931335.51     10021888.12
#Sta/Elev= 30
       0   68.83    19.9   68.29    42.3   65.91    48.1   64.59   113.2   66.87
   265.9   66.18     297   64.79   324.2   65.74   486.3   64.61   588.6   65.56
   631.3    64.9   668.3   65.32   674.1   64.52   769.4   65.51   821.8   64.78
   827.7   63.28   843.2   57.26   849.1    57.1   858.8    59.5   871.1   65.05
   880.2   65.49   894.4   63.97   901.5   64.79   958.5   65.13   987.7   63.93
  1002.6   64.29    1046    61.3  1069.3   61.36  1082.3   63.66    1131   66.37
#Mann= 3 , 0 , 0
       0     .11       0   821.8     .04       0   871.1    .125       0
#XS Ineff= 2 , 0
                          881.06           65.49
Permanent Ineff=
       F       F
Bank Sta=821.8,871.1
XS Rating Curve= 0 ,0
Exp/Cntr=0.3,0.1

Type RM Length L Ch R = 1 ,9500    ,500,500,500
BEGIN DESCRIPTION:
SAND BRANCH 19.0
END DESCRIPTION:
XS GIS Cut Line= 3
      3932127.61     10022723.62      3931778.19     10021997.57
      3931704.43     10021616.85
#Sta/Elev= 30
       0   66.82    54.9   64.25    77.6   64.12    91.6   65.19     151   65.69
   241.5   64.49   269.7   64.97   302.5    64.4   337.6   64.82   405.4   64.08
   473.3   64.69     513   64.13   541.2   64.83   779.7   63.59   795.7   61.06
     801   58.17   805.8   58.17   812.4    57.1   822.6   58.09   835.8   63.17
   842.9   64.92   863.3   63.28   914.2   63.61   924.4   63.04     955   63.85
   965.2   63.25   996.2   63.64  1036.5   63.04  1138.3   64.84  1193.6   66.98
#Mann= 3 , 0 , 0
       0    .125       0   779.7     .04       0   835.8     .15       0
#XS Ineff= 2 , 0
                          843.18           64.93
Permanent Ineff=
       F       F
Bank Sta=779.7,835.8
XS Rating Curve= 0 ,0
Exp/Cntr=0.3,0.1

Type RM Length L Ch R = 1 ,9000    ,500,500,500
BEGIN DESCRIPTION:
SAND BRANCH 18.0
END DESCRIPTION:
XS GIS Cut Line= 3
      3932384.47     10021939.49      3932236.48       10021806.
      3932099.38     10021685.84
#Sta/Elev= 30
  4800.7   63.64  4804.3    62.9  4818.5   62.33  4825.3   62.65  4852.1   61.82
  4876.5    61.9  4924.7   62.02  4945.6   59.95  4967.3   61.44    4974   60.56
  4981.5   58.75  4988.2   56.33  4999.9   53.06  5009.9   53.05  5014.6   52.81
  5014.8   52.31  5018.3   52.31  5024.2   54.27  5030.8   57.62  5038.1   60.16
  5045.1   61.56  5051.7   61.82  5065.9   60.71  5073.5   61.56  5080.2   61.19
  5108.6   61.96  5116.2   61.53  5122.9   62.14  5137.1   61.89  5182.3    63.6
#Mann= 5 ,-1 , 0
  4800.7    .125       0  4852.1     .15       0  4876.5    .125       0
  4988.2     .04       0  5030.8     .11       0
Bank Sta=4974,5038.1
XS Rating Curve= 0 ,0
Exp/Cntr=0.3,0.1

Type RM Length L Ch R = 1 ,8500    ,500,500,500
BEGIN DESCRIPTION:
SAND BRANCH 17.0
END DESCRIPTION:
XS GIS Cut Line= 3
      3932734.17     10021460.85      3932563.54     10021429.95
      3932389.11      10021326.3
#Sta/Elev= 30
  4826.6   62.01  4863.5   62.23  4883.8   61.73  4904.2   61.76  4914.5   61.12
  4934.6   60.98    4955   61.52  4962.8   61.13  4967.9   60.49  4975.3   55.87
  4985.5   53.43  4995.3   52.07    5000   52.07  5002.2   50.47  5002.4   49.97
  5005.9   49.97  5006.2   50.47    5010   53.09  5023.7   58.89  5025.6   59.68
  5031.4   60.29  5053.1   59.54  5126.9   59.27  5135.9   59.47  5148.3   59.76
  5157.8   59.53  5169.7   60.44  5179.5   60.64  5192.7   61.71  5202.9   61.69
#Mann= 5 ,-1 , 0
  4826.6     .11       0  4975.3     .04       0  5023.7     .11       0
  5023.7    .125       0  5135.9     .11       0
Bank Sta=4975.3,5023.7
XS Rating Curve= 0 ,0
Exp/Cntr=0.3,0.1

Type RM Length L Ch R = 1 ,8000    ,500,500,500
BEGIN DESCRIPTION:
SAND BRANCH 16.0
END DESCRIPTION:
XS GIS Cut Line= 4
      3933400.08     10021036.31      3932624.13     10020939.19
      3932533.83     10020946.42      3932101.15     10021022.97
#Sta/Elev= 30
  4127.4   62.14  4190.1    60.1  4260.7   59.91  4351.4   57.01  4368.7   57.22
    4432    55.4  4502.5   56.23    4563   57.84  4603.3   56.91  4615.4   57.19
  4643.6   55.41  4673.9    55.4    4691   56.81  4724.3    57.6  4845.2    57.1
  4895.6   58.27  4965.9   57.04  4975.9   54.95  4996.1   49.52  4999.6   49.52
  5006.1   52.79  5016.2   56.56  5025.5   58.43  5053.6   57.91  5058.7   57.08
  5073.1   56.49  5249.8   55.77  5344.3   56.45  5379.8   57.86  5439.4   60.37
#Mann= 6 ,-1 , 0
  4127.4    .125       0  4975.9     .04       0  5016.2     .11       0
  5025.5     .15       0  5073.1    .125       0  5379.8     .11       0
#XS Ineff= 2 , 0
         4893.94   58.34 5027.27           58.73
Permanent Ineff=
       F       F
Bank Sta=4975.9,5016.2
XS Rating Curve= 0 ,0
Exp/Cntr=0.3,0.1

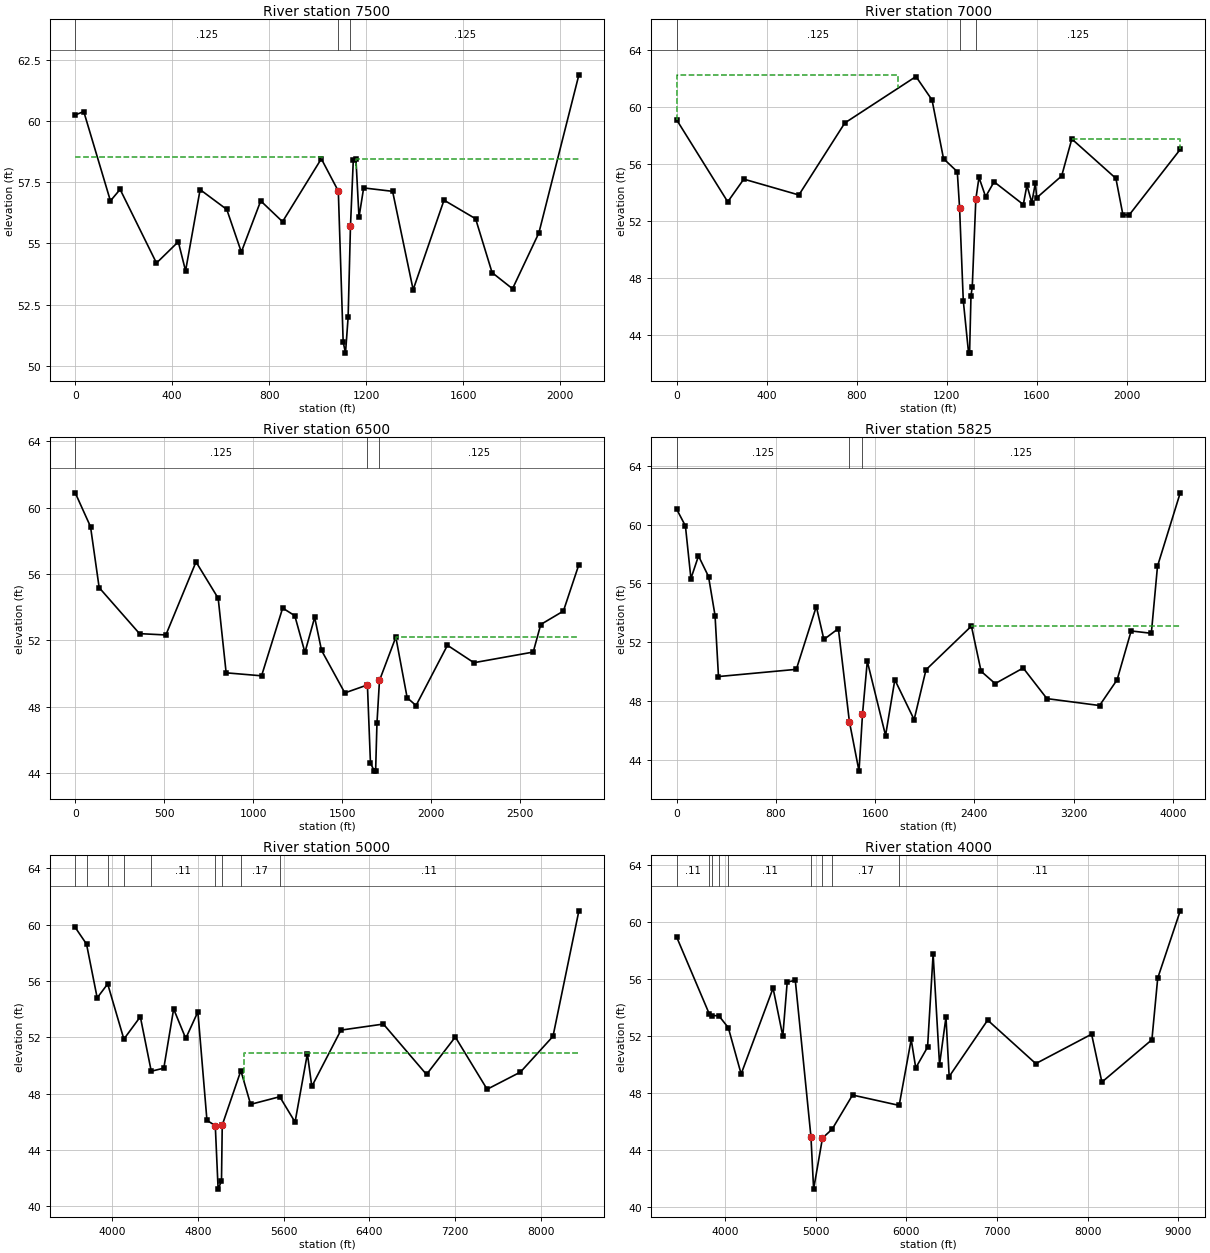
Type RM Length L Ch R = 1 ,7500    ,500,500,500
BEGIN DESCRIPTION:
SAND BRANCH 15.0
END DESCRIPTION:
XS GIS Cut Line= 3
      3933543.01      10020473.2      3932423.54     10020458.74
      3931529.12      10020807.4
#Sta/Elev= 30
       0   60.25    35.2   60.39   145.2   56.74   185.2   57.21   335.2    54.2
   425.2   55.07   455.2   53.88   515.2    57.2   625.2   56.39   685.2   54.65
   765.2   56.74   855.2   55.89  1015.2   58.46  1085.3   57.14  1105.3   50.98
  1114.9   50.52  1125.7   51.98  1135.4    55.7  1147.1   58.41  1157.9   58.46
  1170.6   56.07  1189.8   57.27  1309.2   57.13    1394   53.11  1521.3   56.77
  1651.6   56.01  1719.6   53.81  1803.9   53.15  1912.6   55.43  2077.7   61.89
#Mann= 3 , 0 , 0
       0    .125       0  1085.3     .04       0  1135.4    .125       0
#XS Ineff= 2 , 0
         1016.41   58.52 1160.04           58.46
Permanent Ineff=
       F       F
Bank Sta=1085.3,1135.4
XS Rating Curve= 0 ,0
Exp/Cntr=0.3,0.1

Type RM Length L Ch R = 1 ,7000    ,500,500,500
BEGIN DESCRIPTION:
SAND BRANCH 14.0
END DESCRIPTION:
XS GIS Cut Line= 3
      3933590.76     10020225.81      3932314.29     10019970.82
      3931498.74      10020429.8
#Sta/Elev= 30
       0    59.1   227.3   53.35   298.7   54.94   543.4   53.83   747.4   58.87
  1063.5   62.12  1134.9   60.48  1185.9   56.37  1247.1   55.46  1257.3   52.91
  1273.7   46.43  1297.3   42.76  1301.7   42.76  1307.9   46.77  1313.6    47.4
  1329.5   53.54  1343.5   55.06  1372.9   53.71  1410.5   54.75  1540.5   53.16
  1556.4   54.51  1578.1    53.3    1594   54.68  1599.8   53.63  1710.7   55.16
  1755.9   57.75  1951.7   54.99  1982.8   52.45  2010.2   52.42  2237.5   57.02
#Mann= 3 , 0 , 0
       0    .125       0  1257.3     .04       0  1329.5    .125       0
#XS Ineff= 2 , 0
          984.85   62.24 1758.21           57.75
Permanent Ineff=
       F       F
Bank Sta=1257.3,1329.5
XS Rating Curve= 0 ,0
Exp/Cntr=0.3,0.1

Type RM Length L Ch R = 1 ,6500    ,675,675,675
BEGIN DESCRIPTION:
SAND BRANCH 13.0
END DESCRIPTION:
XS GIS Cut Line= 3
      3933799.09      10020030.5      3932216.39     10019481.13
      3931358.59     10020254.69
#Sta/Elev= 30
       0   60.89      86   58.85   134.5   55.18   361.2   52.41   509.4   52.33
   678.8   56.73   803.4   54.54   848.1   50.05  1047.2   49.87  1165.7   53.95
  1233.9   53.49  1290.9   51.28  1345.6   53.39  1384.2    51.4    1515   48.84
    1642   49.32  1659.1   44.61  1681.4   44.13  1688.1   44.14  1695.6   47.01
  1709.8   49.59  1801.7    52.2  1865.3   48.55  1915.3   48.08  2091.7   51.71
  2240.4   50.66  2573.7    51.3    2616   52.96  2743.4   53.77  2830.4   56.57
#Mann= 3 , 0 , 0
       0    .125       0    1642     .04       0  1709.8    .125       0
#XS Ineff= 2 , 0
                         1804.92           52.18
Permanent Ineff=
       F       F
#Block Obstruct= 2 , 0
         1140.15   53.82
Bank Sta=1642,1709.8
XS Rating Curve= 0 ,0
Exp/Cntr=0.3,0.1

Type RM Length L Ch R = 1 ,5825    ,825,825,825
BEGIN DESCRIPTION:
SAND BRANCH 12.0
END DESCRIPTION:
XS GIS Cut Line= 3
      3933977.04      10019848.2      3931943.08     10018807.35
      3930709.45     10020081.94
#Sta/Elev= 30
       0   61.06    71.3   59.91   115.7   56.33   176.7   57.87   257.5   56.47
     310   53.82   337.8   49.67     965   50.16  1126.1   54.43  1187.1   52.19
  1303.8   52.93  1392.6   46.61  1470.2   43.24  1498.1   47.09  1536.9   50.71
  1684.1   45.66  1758.9   49.45  1914.4   46.74  2009.9   50.13  2375.9    53.1
  2453.9   50.03    2567   49.19  2793.2   50.25  2984.3   48.17  3408.5    47.7
    3550   49.45  3663.1   52.77  3825.7   52.61  3875.4   57.17  4058.6   62.16
#Mann= 3 , 0 , 0
       0    .125       0  1392.6     .06       0  1498.1    .125       0
#XS Ineff= 2 , 0
                         2376.49           53.14
Permanent Ineff=
       F       F
#Block Obstruct= 2 , 0
         1123.74    54.5
Bank Sta=1392.6,1498.1
XS Rating Curve= 0 ,0
Exp/Cntr=0.3,0.1

Type RM Length L Ch R = 1 ,5000    ,1000,1000,1000
BEGIN DESCRIPTION:
SAND BRANCH 10.0
END DESCRIPTION:
XS GIS Cut Line= 4
      3934217.85     10019661.07      3933273.31     10018701.29
      3932231.21      10018380.6      3930666.02     10020021.21
#Sta/Elev= 30
  3653.4   59.81  3758.9   58.63  3858.5   54.81  3956.6    55.8  4107.8   51.88
  4261.5   53.47  4363.5    49.6  4480.8   49.82  4572.7   54.02  4685.8   51.93
    4799   53.82  4883.8   46.11  4961.6   45.74  4988.1   41.23  5019.6   41.81
  5026.6   45.78  5200.6   49.64  5291.6   47.25  5563.7   47.79  5706.7   45.99
  5821.8   50.85  5863.1   48.52  6135.4   52.52  6531.7   52.95  6934.6   49.37
  7203.5   52.03  7500.7   48.32  7811.8   49.54  8115.9   52.08  8357.8   60.99
#Mann= 9 ,-1 , 0
  3653.4     .11       0  3758.9    .125       0  3956.6     .11       0
  4107.8    .125       0  4363.5     .11       0  4961.6    .015       0
  5026.6     .11       0  5200.6     .17       0  5563.7     .11       0
#XS Ineff= 2 , 0
                         5227.27           50.93
Permanent Ineff=
       F       F
Bank Sta=4961.6,5026.6
XS Rating Curve= 0 ,0
Exp/Cntr=0.3,0.1

Type RM Length L Ch R = 1 ,4000    ,1000,1000,1000
BEGIN DESCRIPTION:
SAND BRANCH 8.0
END DESCRIPTION:
XS GIS Cut Line= 4
       3935162.6     10018502.09      3933740.24     10017930.27
      3932467.85     10018011.07      3930596.63     10020021.15
#Sta/Elev= 30
    3467   58.98  3828.1   53.55  3854.4   53.44  3932.8   53.43  4037.5   52.59
  4179.1   49.33  4531.2   55.37  4638.7   51.99  4687.1    55.8  4776.2   55.92
  4948.7   44.93  4978.3   41.23    5076   44.82  5182.9   45.45  5407.6   47.85
  5921.7   47.12  6054.5   51.76  6104.6   49.76  6234.9   51.22  6296.2   57.77
    6367   49.99  6437.9   53.33  6473.1   49.15  6897.6   53.12  7428.2   50.06
  8043.8   52.13  8157.2   48.76  8708.8   51.74  8772.8   56.07  9021.2   60.81
#Mann= 9 ,-1 , 0
    3467     .11       0  3828.1    .125       0  3854.4     .11       0
  3932.8    .125       0  4037.5     .11       0  4948.7    .015       0
    5076     .11       0  5182.9     .17       0  5921.7     .11       0
Bank Sta=4948.7,5076
XS Rating Curve= 0 ,0
Exp/Cntr=0.3,0.1

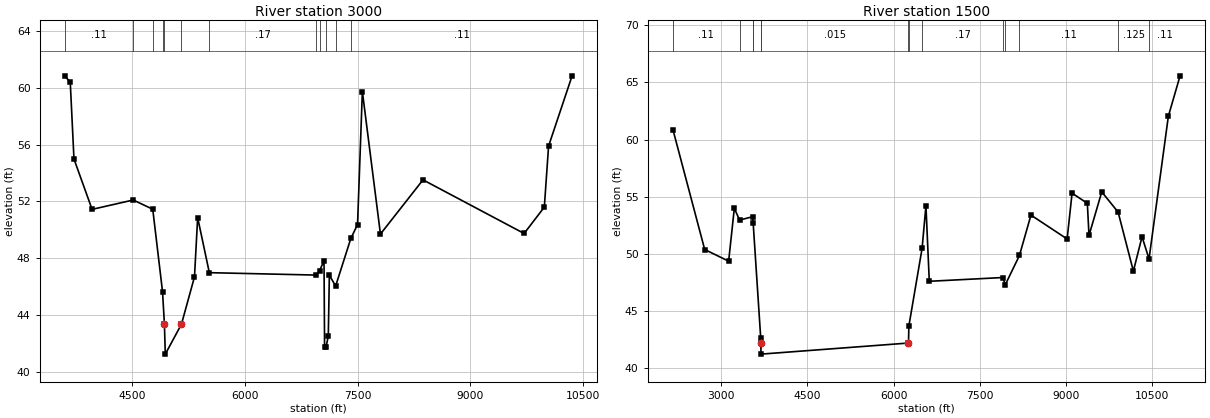
Type RM Length L Ch R = 1 ,3000    ,1500,1500,1500
BEGIN DESCRIPTION:
SAND BRANCH 6.0
END DESCRIPTION:
XS GIS Cut Line= 4
      3935422.99     10018172.21      3934402.52     10017224.45
      3933416.99     10016837.44      3930527.13     10020012.53
#Sta/Elev= 30
  3607.3    60.8  3675.4   60.39  3724.8   54.98  3965.7   51.43  4512.9   52.09
  4772.9   51.44    4903   45.63  4927.7   43.38  4939.9   41.23  5154.9   43.34
  5328.3   46.68  5370.3   50.85  5525.6   46.97  6948.8    46.8  6992.8   47.12
  7051.5   47.81  7058.9   41.73  7077.5   41.73  7108.3   42.48  7122.5   46.79
  7206.1   46.03  7408.2   49.38  7497.5   50.36  7561.7   59.73  7802.2   49.69
  8368.4   53.51  9713.7   49.73  9982.7   51.59 10039.1   55.89 10352.1   60.84
#Mann= 12 ,-1 , 0
  3607.3     .11       0  4512.9    .125       0  4772.9     .11       0
    4903     .15       0  4927.7    .015       0  5154.9     .11       0
  5525.6     .17       0  6948.8     .15       0  6992.8     .11       0
  7077.5     .15       0  7206.1     .17       0  7408.2     .11       0
#XS Ineff= 1 ,-1
 7052.11 7207.26   46.02
Permanent Ineff=
       F
Bank Sta=4927.7,5154.9
XS Rating Curve= 0 ,0
Exp/Cntr=0.3,0.1

Type RM Length L Ch R = 1 ,1500    ,0,0,0
BEGIN DESCRIPTION:
SAND BRANCH 3.0
END DESCRIPTION:
XS GIS Cut Line= 4
      3936282.36     10017764.22      3934228.23     10015803.49
      3931353.65     10017529.93      3929806.47     10019665.62
#Sta/Elev= 30
  2160.3   60.81  2710.3   50.38  3127.6   49.36  3226.7   53.99    3318   52.95
  3545.1   53.25  3555.1   52.67  3686.5   42.63 3688.5942.21198  3691.3   41.23
  6260.3    42.2  6266.8   43.69  6497.4   50.49  6564.1   54.21  6622.4    47.6
  7906.1   47.93  7943.3   47.27  8192.8   49.86  8393.2   53.39  9023.4    51.3
  9109.3   55.31  9375.3   54.42  9404.2   51.61  9626.5   55.42  9911.4   53.65
 10177.2   48.49   10328    51.5 10449.9   49.55 10786.5   62.04 10990.4   65.57
#Mann= 14 ,-1 , 0
  2160.3     .11       0    3318    .125       0  3545.1     .11       0
  3555.1     .15       0  3686.5     .11       0 3688.59    .015       0
  6260.3     .11       0  6266.8     .11       0  6497.4     .17       0
  7906.1     .11       0  7943.3     .17       0  8192.8     .11       0
  9911.4    .125       0 10449.9     .11       0
Bank Sta=3688.59,6260.3
XS Rating Curve= 0 ,0
Exp/Cntr=0.3,0.1

Chan Stop Cuts=-1
Use User Specified Reach Order=0
Composite Channel Slope=5