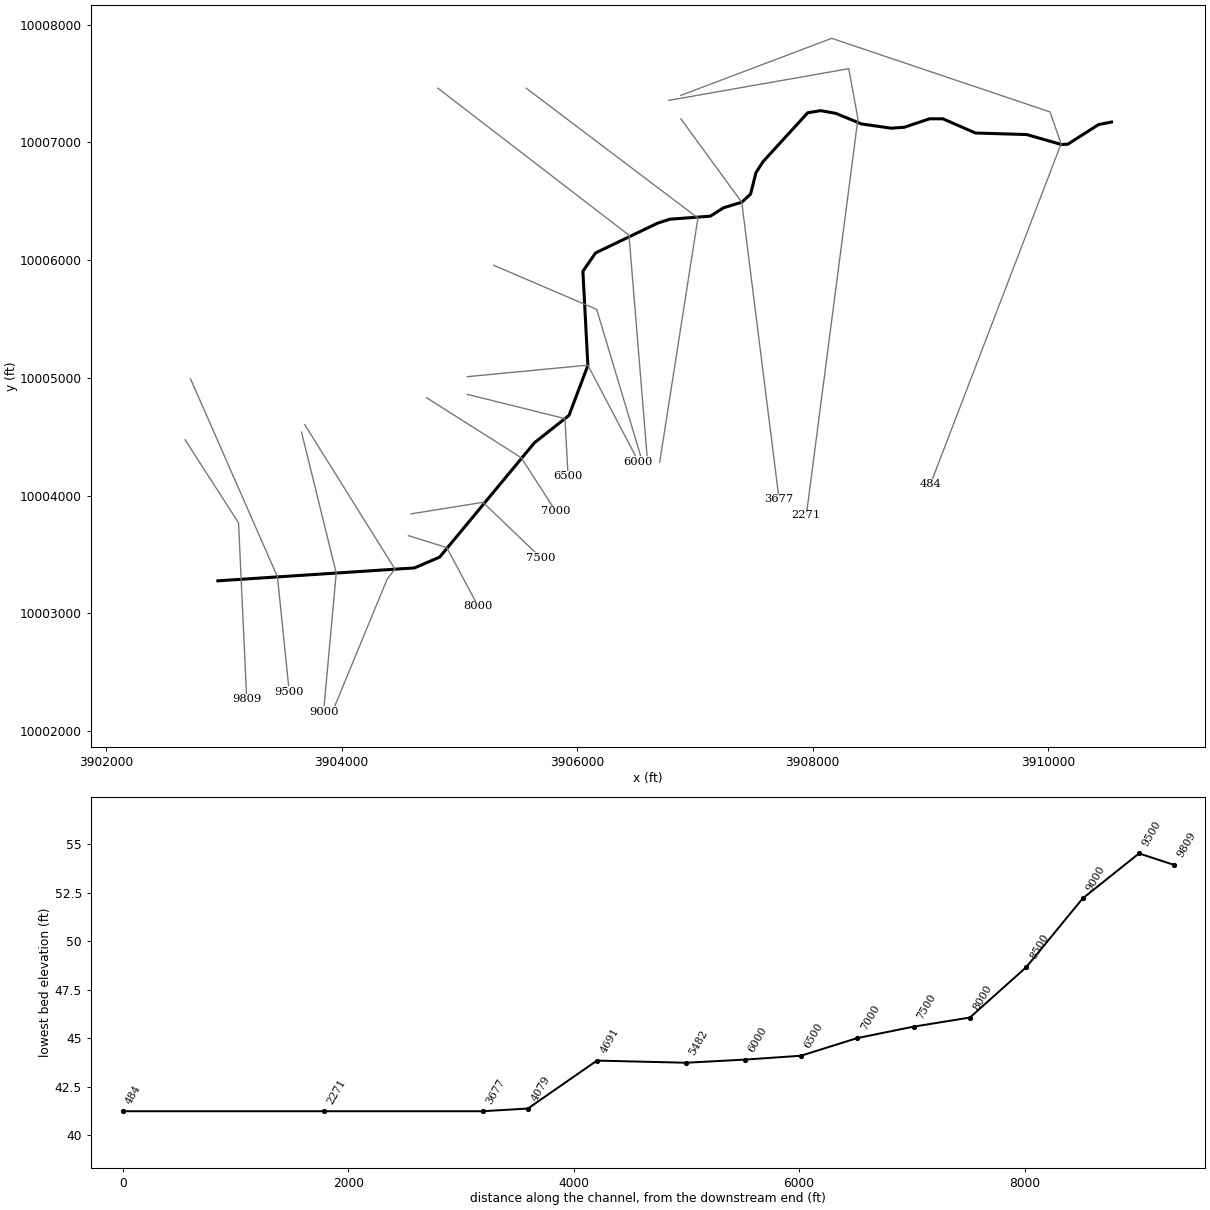
--- TxDOT DITCH NO 4.prj (project) ---

Proj Title=TxDOT DITCH NO 4 Base Level Engineering
Current Plan=p01
Default Exp/Contr=0.3,0.1
English Units
Geom File=g01
Flow File=f01
Flow File=f02
Plan File=p01
Y Axis Title=Elevation
X Axis Title(PF)=Main Channel Distance
X Axis Title(XS)=Station
BEGIN DESCRIPTION:
TxDOT DITCH NO 4
END DESCRIPTION:
DSS Export Rating Curves= 0
DSS Export Rating Curve Sorted= 0
DSS Export Volume Flow Curves= 0
DXF OffsetX= 0
DXF OffsetY= 0
DXF ScaleX= 1
DXF ScaleY= 10

--- TxDOT DITCH NO 4.p01 (plan) ---

Plan Title=Multiple Run
Short Identifier=Multiple
Geom File=g01
Flow File=f01
Subcritical Flow
K Sum by GR= 0
Std Step Tol= 0.01
Critical Tol= 0.01
Num of Std Step Trials= 20
Max Error Tol= 0.3
Flow Tol Ratio= 0.001
Split Flow NTrial= 30
Split Flow Tol= 0.02
Split Flow Ratio= 0.02
Log Output Level= 0
Friction Slope Method= 1
Unsteady Friction Slope Method= 2
Unsteady Bridges Friction Slope Method= 1
Parabolic Critical Depth
Global Vel Dist=  1 , 1 , 1
Global Log Level= 0
CheckData=True
Encroach Param= -1, 0, 0, 0
BEGIN DESCRIPTION:
Multiple Run
END DESCRIPTION:

--- TxDOT DITCH NO 4.f01 (steady flow) ---

Flow Title=Multiple
Program Version=4.10
Number of Profiles= 7
Profile Names=10-year,25-year,50-year,1pct_min,100-year,1pct_plu,500-year
River Rch & RM=TxDOT DITCH NO 4,Reach-1         ,9809
     781    1053    1419     630    1902    5744    3521
River Rch & RM=TxDOT DITCH NO 4,Reach-1         ,7500
     987    1330    1791     791    2389    7215    4395
Boundary for River Rch & Prof#=TxDOT DITCH NO 4,Reach-1         , 1
Up Type= 0
Dn Type= 3
Dn Slope=0.00032
Boundary for River Rch & Prof#=TxDOT DITCH NO 4,Reach-1         , 2
Up Type= 0
Dn Type= 3
Dn Slope=0.00032
Boundary for River Rch & Prof#=TxDOT DITCH NO 4,Reach-1         , 3
Up Type= 0
Dn Type= 3
Dn Slope=0.00032
Boundary for River Rch & Prof#=TxDOT DITCH NO 4,Reach-1         , 4
Up Type= 0
Dn Type= 3
Dn Slope=0.00032
Boundary for River Rch & Prof#=TxDOT DITCH NO 4,Reach-1         , 5
Up Type= 0
Dn Type= 3
Dn Slope=0.00032
Boundary for River Rch & Prof#=TxDOT DITCH NO 4,Reach-1         , 6
Up Type= 0
Dn Type= 3
Dn Slope=0.00032
Boundary for River Rch & Prof#=TxDOT DITCH NO 4,Reach-1         , 7
Up Type= 0
Dn Type= 3
Dn Slope=0.00032
DSS Import GetInterval= 0
DSS Import GetPeak= 0
DSS Import FillOption= 0

--- TxDOT DITCH NO 4.f02 (steady flow) ---

Flow Title=Orig_BLE_Flows
Program Version=4.10
Number of Profiles= 7
Profile Names=10-year,25-year,50-year,1pct_min,100-year,1pct_plu,500-year
River Rch & RM=TxDOT DITCH NO 4,Reach-1         ,9809
     781    1032    1234     484    1463    4417    2047
River Rch & RM=TxDOT DITCH NO 4,Reach-1         ,7500
     987    1304    1557     609    1838    5550    2555
Boundary for River Rch & Prof#=TxDOT DITCH NO 4,Reach-1         , 1
Up Type= 0
Dn Type= 3
Dn Slope=0.00032
Boundary for River Rch & Prof#=TxDOT DITCH NO 4,Reach-1         , 2
Up Type= 0
Dn Type= 3
Dn Slope=0.00032
Boundary for River Rch & Prof#=TxDOT DITCH NO 4,Reach-1         , 3
Up Type= 0
Dn Type= 3
Dn Slope=0.00032
Boundary for River Rch & Prof#=TxDOT DITCH NO 4,Reach-1         , 4
Up Type= 0
Dn Type= 3
Dn Slope=0.00032
Boundary for River Rch & Prof#=TxDOT DITCH NO 4,Reach-1         , 5
Up Type= 0
Dn Type= 3
Dn Slope=0.00032
Boundary for River Rch & Prof#=TxDOT DITCH NO 4,Reach-1         , 6
Up Type= 0
Dn Type= 3
Dn Slope=0.00032
Boundary for River Rch & Prof#=TxDOT DITCH NO 4,Reach-1         , 7
Up Type= 0
Dn Type= 3
Dn Slope=0.00032
DSS Import GetInterval= 0
DSS Import GetPeak= 0
DSS Import FillOption= 0

--- TxDOT DITCH NO 4.g01 (geometry) ---

Geom Title=Existing Conditions
Program Version=4.10

River Reach=TxDOT DITCH NO 4,Reach-1
Reach XY= 30
      3902949.69     10003277.44      3904619.15      10003387.1
      3904832.62     10003478.49      3905637.85     10004449.92
      3905931.36     10004682.01      3906091.83     10005106.56
      3906049.52     10005906.84      3906157.06     10006062.05
      3906683.76     10006314.85      3906787.62     10006348.52
      3907131.74      10006374.2      3907244.74     10006446.11
      3907398.82     10006492.33       3907473.3     10006561.67
      3907519.52       10006744.      3907578.59     10006836.45
      3907958.66     10007252.48      3908069.09     10007270.46
      3908197.49     10007247.35      3908415.78     10007157.46
      3908667.45     10007121.51      3908777.88     10007129.21
       3908993.6     10007201.12      3909106.59     10007201.12
      3909383.95     10007080.42      3909817.95     10007067.58
      3910113.28     10006982.83      3910167.21      10006985.4
      3910429.16     10007152.33      3910539.01     10007173.65

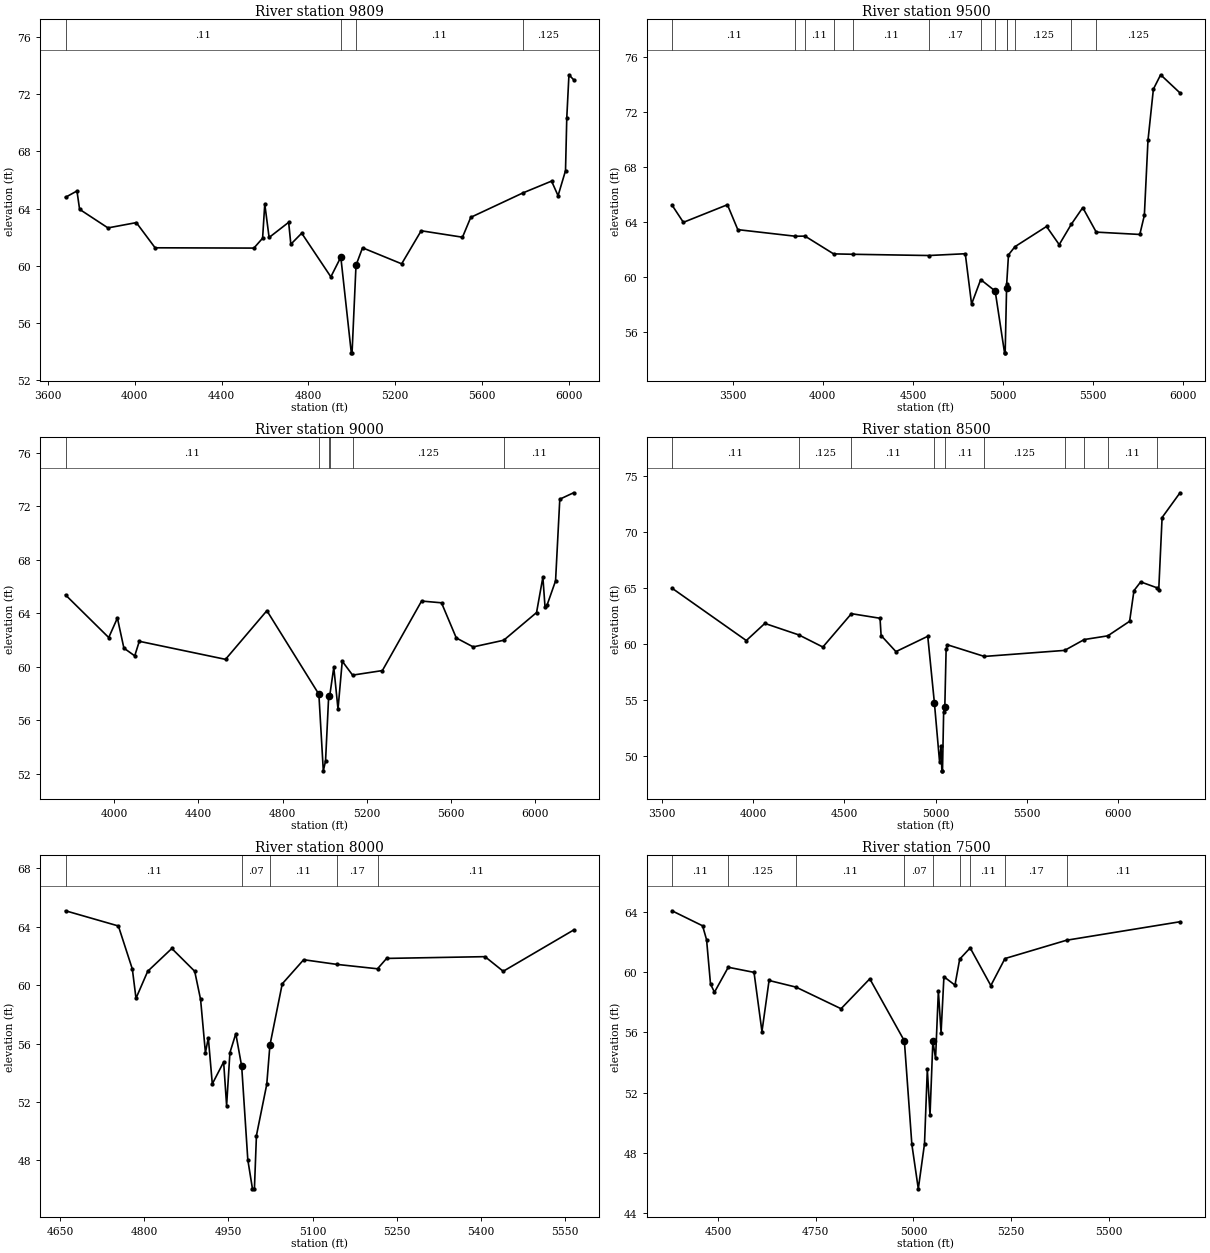
Type RM Length L Ch R = 1 ,9809    ,309,309,309
BEGIN DESCRIPTION:
TxDOT DITCH NO. 4 20.0
END DESCRIPTION:
XS GIS Cut Line= 3
      3902670.83     10004475.45      3903125.16     10003769.84
       3903194.6     10002269.87
#Sta/Elev= 30
    3681    64.8  3733.8   65.24  3745.9   63.96  3876.5   62.66  4007.3   63.03
  4093.8   61.27    4549   61.25  4589.1   61.94  4599.1   64.33  4619.1   61.99
  4709.2   63.05  4719.2   61.52  4769.3   62.29  4903.6   59.24  4949.5   60.62
  4997.8   53.93  5001.3   53.93  5019.5   60.05  5049.6   61.27  5229.8   60.15
  5319.8   62.46  5510.1   62.01  5548.3    63.4  5787.8    65.1  5920.5   65.93
  5950.5   64.91  5984.8   66.66  5990.6   70.35  6000.6   73.36  6021.8   73.02
#Mann= 4 ,-1 , 0
    3681     .11       0  4949.5     .04       0  5019.5     .11       0
  5787.8    .125       0
Bank Sta=4949.5,5019.5
XS Rating Curve= 0 ,0
Exp/Cntr=0.3,0.1

Type RM Length L Ch R = 1 ,9500    ,500,500,500
BEGIN DESCRIPTION:
TxDOT DITCH NO. 4 19.0
END DESCRIPTION:
XS GIS Cut Line= 3
      3902717.15     10004993.26      3903455.77     10003311.08
      3903555.53     10002334.16
#Sta/Elev= 30
  3162.8   65.26    3226      64  3470.5   65.28  3528.1   63.47  3848.1   62.99
    3901      63  4059.5   61.71  4165.2   61.68    4588   61.59  4790.4   61.72
  4825.3   58.06  4876.1   59.84  4956.3   59.01  5008.3   54.52  5011.8   54.52
  5019.6   59.22  5020.1    59.5  5030.2   61.64  5065.8   62.23  5241.3    63.7
  5311.6   62.38  5378.7   63.86  5442.3   65.07  5517.1   63.29  5758.9   63.12
  5784.1   64.51  5804.2   69.95  5834.3   73.68  5874.5   74.72    5982    73.4
#Mann= 13 ,-1 , 0
  3162.8     .11       0  3848.1     .17       0    3901     .11       0
  4059.5     .17       0  4165.2     .11       0    4588     .17       0
  4876.1     .11       0  4956.3     .04       0  5019.6     .08       0
  5020.1     .11       0  5065.8    .125       0  5378.7     .11       0
  5517.1    .125       0
Bank Sta=4956.3,5019.6
XS Rating Curve= 0 ,0
Exp/Cntr=0.3,0.1

Type RM Length L Ch R = 1 ,9000    ,500,500,500
BEGIN DESCRIPTION:
TxDOT DITCH NO. 4 18.0
END DESCRIPTION:
XS GIS Cut Line= 3
      3903659.88     10004540.65      3903954.67     10003344.23
       3903847.4     10002165.91
#Sta/Elev= 30
  3767.8   65.36  3973.3   62.17  4014.5   63.63  4045.4   61.38  4096.9    60.8
  4118.6   61.89  4528.5   60.54  4725.2   64.18  4972.4   57.93  4993.5    52.2
  5004.1   52.93  5019.1   57.81  5024.2   57.84  5043.3   59.94  5063.4   56.82
  5083.5    60.4  5132.7   59.36  5274.3    59.7  5460.7    64.9  5555.4   64.77
  5625.7   62.14  5706.1   61.47  5851.3   61.97  6007.3   64.04  6037.4   66.69
  6047.5   64.48  6057.5   64.61  6097.7   66.41  6117.8   72.52  6183.2      73
#Mann= 6 ,-1 , 0
  3767.8     .11       0  4972.4     .04       0  5019.1     .08       0
  5024.2     .11       0  5132.7    .125       0  5851.3     .11       0
Bank Sta=4972.4,5019.1
XS Rating Curve= 0 ,0
Exp/Cntr=0.3,0.1

Type RM Length L Ch R = 1 ,8500    ,500,500,500
BEGIN DESCRIPTION:
TxDOT DITCH NO. 4 17.0
END DESCRIPTION:
XS GIS Cut Line= 4
      3903687.65     10004603.18      3904453.62      10003376.6
       3904388.1     10003293.27       3903916.8     10002151.74
#Sta/Elev= 30
  3553.9   64.98  3961.7    60.3  4063.3   61.83  4250.3    60.8  4381.7   59.72
  4538.3    62.7  4695.3   62.29  4701.2   60.75  4782.5   59.31  4957.1   60.68
  4993.7   54.71  5021.8   49.48  5029.9   50.86  5034.5   48.66    5038   48.66
  5044.3   53.92  5050.7   54.37  5057.9   59.53  5065.1   59.92  5267.5   58.88
  5708.1   59.42  5815.7   60.39  5944.7   60.72  6064.5   62.02  6088.4   64.76
  6125.3   65.54    6215   65.01  6224.2    64.8  6242.7   71.29    6341    73.5
#Mann= 10 ,-1 , 0
  3553.9     .11       0  4250.3    .125       0  4538.3     .11       0
  4993.7     .04       0  5050.7     .11       0  5267.5    .125       0
  5708.1     .15       0  5815.7    .125       0  5944.7     .11       0
    6215    .125       0
Bank Sta=4993.7,5050.7
XS Rating Curve= 0 ,0
Exp/Cntr=0.3,0.1

Type RM Length L Ch R = 1 ,8000    ,500,500,500
BEGIN DESCRIPTION:
TxDOT DITCH NO. 4 16.0
END DESCRIPTION:
XS GIS Cut Line= 3
      3904567.81     10003661.08      3904893.08     10003560.04
      3905159.86     10003061.53
#Sta/Elev= 30
  4659.4   65.09  4753.7   64.05  4778.6    61.1  4785.1    59.1    4806   60.95
    4849   62.51  4889.8   60.95  4900.3   59.02  4908.9   55.38  4914.1   56.39
  4921.2   53.24  4941.4   54.74  4946.7   51.76  4952.6   55.38  4963.1   56.68
  4973.6   54.44  4984.5   48.05  4992.8   46.06  4996.3   46.06  4999.9   49.71
  5018.3   53.21  5023.9   55.88  5045.9   60.09  5084.1   61.74  5143.5   61.42
  5215.8   61.12    5232   61.83  5407.5   61.95    5440   60.95  5565.4   63.77
#Mann= 5 ,-1 , 0
  4659.4     .11       0  4973.6     .07       0  5023.9     .11       0
  5143.5     .17       0  5215.8     .11       0
Bank Sta=4973.6,5023.9
XS Rating Curve= 0 ,0
Exp/Cntr=0.3,0.1

Type RM Length L Ch R = 1 ,7500    ,500,500,500
BEGIN DESCRIPTION:
TxDOT DITCH NO. 4 15.0
END DESCRIPTION:
XS GIS Cut Line= 3
       3904590.4     10003846.22      3905200.89     10003944.17
      3905693.74     10003472.05
#Sta/Elev= 30
  4381.7    64.1  4460.1    63.1  4470.3   62.17  4480.4   59.22  4490.5   58.68
  4525.8   60.34  4591.8      60  4612.1   56.06  4630.3   59.46  4699.1   59.02
  4814.6   57.58  4888.2   59.57  4976.7   55.44  4995.9   48.55  5012.4   45.59
  5028.3   48.59  5035.5   53.54  5042.4    50.5  5049.7   55.42  5056.6   54.27
  5063.8   58.77  5070.7   55.98    5078   59.71  5106.3   59.15  5118.4   60.88
  5145.2   61.63  5198.1   59.12  5234.3   60.92  5392.1   62.14  5682.5   63.37
#Mann= 9 ,-1 , 0
  4381.7     .11       0  4525.8    .125       0  4699.1     .11       0
  4976.7     .07       0  5049.7     .11       0  5118.4     .17       0
  5145.2     .11       0  5234.3     .17       0  5392.1     .11       0
Bank Sta=4976.7,5049.7
XS Rating Curve= 0 ,0
Exp/Cntr=0.3,0.1

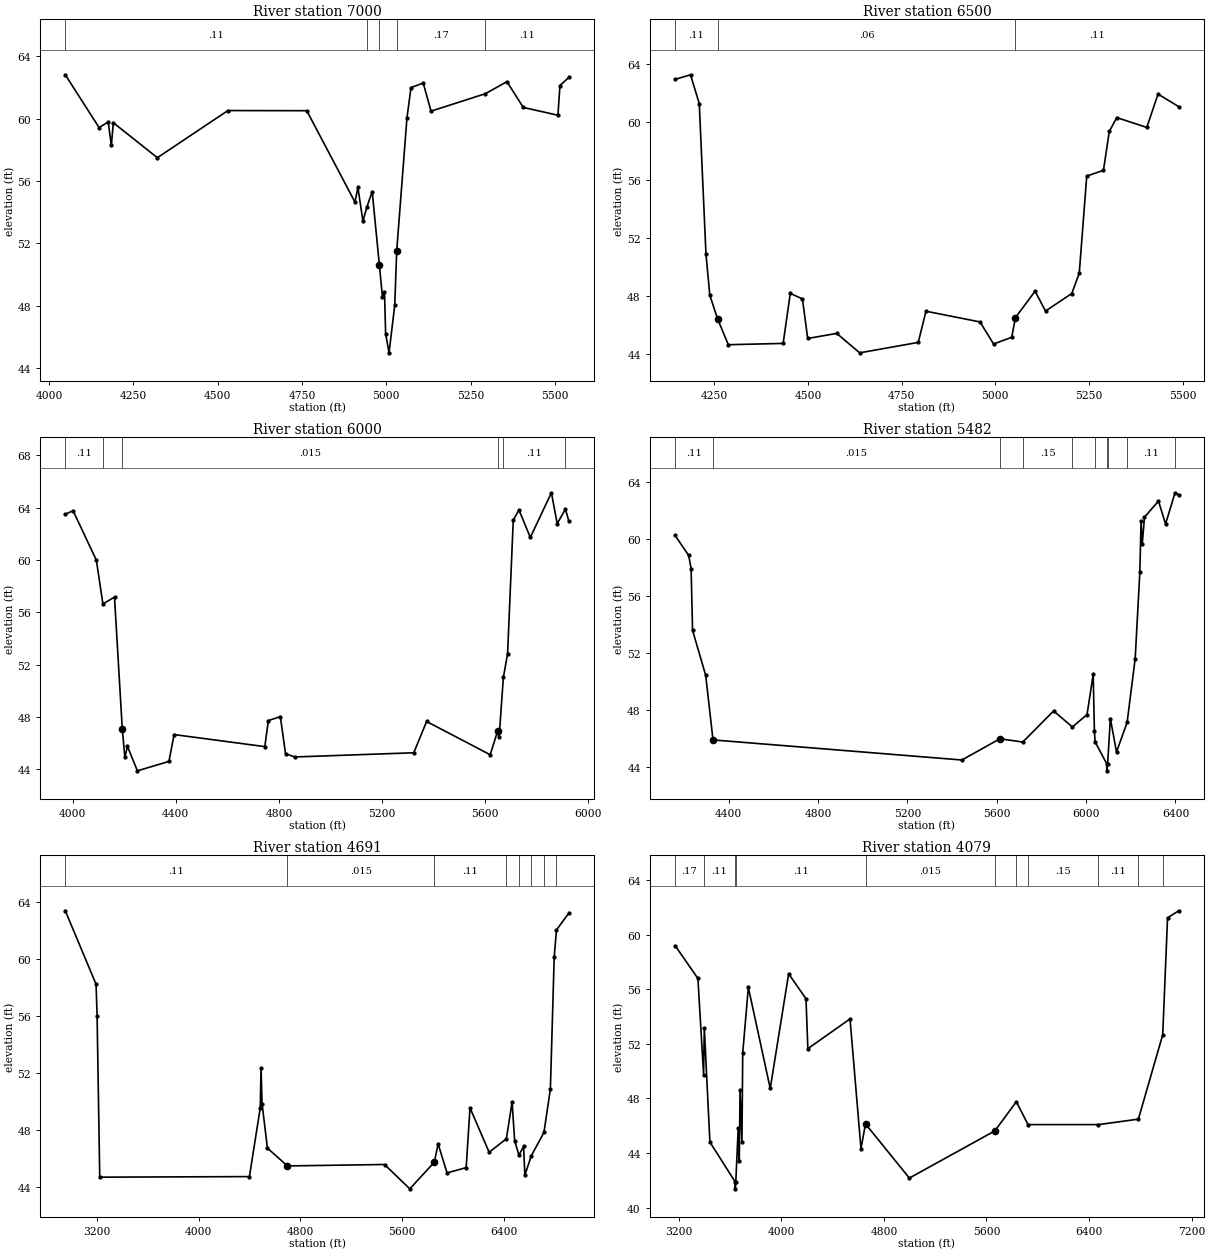
Type RM Length L Ch R = 1 ,7000    ,500,500,500
BEGIN DESCRIPTION:
TxDOT DITCH NO. 4 14.0
END DESCRIPTION:
XS GIS Cut Line= 3
      3904722.38     10004832.33      3905526.43     10004322.44
       3905819.6     10003867.05
#Sta/Elev= 30
  4047.9    62.8  4148.1   59.42  4175.2   59.78  4184.5   58.28  4190.4   59.73
  4320.9   57.49  4530.2   60.51    4764    60.5  4906.9   54.65  4915.7   55.59
  4930.6   53.43  4942.3   54.34  4958.1   55.32  4979.2   50.64  4988.6   48.55
  4994.5   48.92  4997.9   46.23    5008      45  5024.9   48.05  5030.8   51.55
  5061.1   60.03  5073.1   61.98  5109.4   62.27  5132.5   60.47  5293.8   61.59
  5357.7   62.36    5406   60.71  5508.9   60.21  5514.8   62.11  5541.6   62.64
#Mann= 5 ,-1 , 0
  4047.9     .11       0  4942.3     .17       0  4979.2     .09       0
  5030.8     .17       0  5293.8     .11       0
Bank Sta=4979.2,5030.8
XS Rating Curve= 0 ,0
Exp/Cntr=0.3,0.1

Type RM Length L Ch R = 1 ,6500    ,500,500,500
BEGIN DESCRIPTION:
TxDOT DITCH NO. 4 13.0
END DESCRIPTION:
XS GIS Cut Line= 3
      3905067.85     10004861.07      3905897.25     10004655.04
      3905923.76     10004165.86
#Sta/Elev= 30
  4145.4   62.94  4186.6   63.26    4210   61.27  4227.8   50.92  4238.1   48.07
  4258.7   46.44  4287.5   44.65  4433.9   44.74  4452.9   48.19  4485.4   47.81
  4499.4   45.08    4577   45.43  4638.2   44.09  4794.5   44.81  4815.2   46.96
  4959.4   46.22  4995.6    44.7    5044   45.16    5054   46.52  5106.4   48.34
  5134.2   46.97  5204.3   48.18  5224.3   49.58  5244.3   56.28  5288.9   56.67
  5304.4   59.35  5324.4   60.31  5404.6   59.63  5434.6   61.93  5489.9   61.06
#Mann= 3 , 0 , 0
  4145.4     .11       0  4258.7     .06       0    5054     .11       0
Bank Sta=4258.7,5054
XS Rating Curve= 0 ,0
Exp/Cntr=0.3,0.1

Type RM Length L Ch R = 1 ,6000    ,518,518,518
BEGIN DESCRIPTION:
TxDOT DITCH NO. 4 12.0
END DESCRIPTION:
XS GIS Cut Line= 3
      3905067.88     10005011.07      3906091.69     10005109.21
        3906521.     10004290.65
#Sta/Elev= 30
  3971.5   63.49  4001.6   63.76    4092   59.98  4117.4   56.64  4162.3   57.16
  4192.5   47.08  4202.5   44.92  4212.6   45.76    4251   43.89  4373.3   44.61
  4393.4   46.66    4745   45.74  4758.8   47.73  4805.3   48.03  4825.4    45.2
  4861.4   44.95  5322.6   45.27  5372.3   47.66  5618.9   45.12  5647.8   46.94
  5653.4   46.44    5670   51.03  5686.3   52.84  5708.3   63.04  5730.4   63.82
  5774.5   61.72  5856.1   65.13  5878.7   62.78  5910.6   63.87  5924.3   62.94
#Mann= 6 ,-1 , 0
  3971.5     .11       0  4117.4     .15       0  4192.5    .015       0
  5647.8     .17       0    5670     .11       0  5910.6     .17       0
Bank Sta=4192.5,5647.8
XS Rating Curve= 0 ,0
Exp/Cntr=0.3,0.1

Type RM Length L Ch R = 1 ,5482    ,791,791,791
BEGIN DESCRIPTION:
TxDOT DITCH NO. 4 11.0
END DESCRIPTION:
XS GIS Cut Line= 3
      3905291.82     10005957.34      3906166.82     10005582.34
      3906541.27     10004334.17
#Sta/Elev= 30
  4159.5   60.25  4220.5   58.84  4231.3   57.92  4237.8   53.59  4296.6   50.43
  4329.3    45.9  5443.7   44.49  5613.9   45.98  5716.4   45.75  5854.1   47.93
  5938.6   46.81    6004   47.68  6031.5    50.5    6037    46.5  6040.2   45.76
  6092.1   44.23  6092.4   43.73  6096.2   44.23  6108.4    47.4  6135.9   45.05
  6183.4   47.13  6219.5   51.61  6240.4   57.67  6245.8   61.23  6251.1   59.64
  6261.2   61.53  6323.9   62.66  6355.5   61.05  6397.9   63.24  6414.6    63.1
#Mann= 10 ,-1 , 0
  4159.5     .11       0  4329.3    .015       0  5613.9     .11       0
  5716.4     .15       0  5938.6     .11       0  6040.2     .17       0
  6092.1     .08       0  6096.2     .17       0  6183.4     .11       0
  6397.9     .17       0
Bank Sta=4329.3,5613.9
XS Rating Curve= 0 ,0
Exp/Cntr=0.3,0.1

Type RM Length L Ch R = 1 ,4691    ,612,612,612
BEGIN DESCRIPTION:
TxDOT DITCH NO. 4 10.0
END DESCRIPTION:
XS GIS Cut Line= 3
      3904817.83     10007461.09      3906441.02     10006212.42
      3906597.32     10004305.31
#Sta/Elev= 30
  2952.1   63.38    3194   58.22  3202.2   56.01  3223.1   44.66  4400.2    44.7
  4485.3   49.52  4491.6   52.31  4499.8   49.82  4541.8    46.7  4699.2   45.45
  5462.9   45.55  5661.7   43.84  5854.2   45.71  5884.4   46.99  5954.5   44.96
    6105   45.33  6135.1   49.53  6285.6   46.41  6421.3   47.36  6466.2   49.94
  6486.3   47.22  6519.7   46.21  6556.5   46.82  6566.6   44.81  6618.2   46.18
  6716.6    47.8  6767.3   50.85  6797.4   60.12    6815   62.03  6913.5   63.23
#Mann= 8 ,-1 , 0
  2952.1     .11       0  4699.2    .015       0  5854.2     .11       0
  6421.3     .17       0  6519.7     .11       0  6618.2     .17       0
  6716.6     .11       0    6815     .17       0
Bank Sta=4699.2,5854.2
XS Rating Curve= 0 ,0
Exp/Cntr=0.3,0.1

Type RM Length L Ch R = 1 ,4079    ,402,402,402
BEGIN DESCRIPTION:
TxDOT DITCH NO. 4 8.0
END DESCRIPTION:
XS GIS Cut Line= 3
      3905567.82      10007461.1      3907026.45     10006358.79
      3906701.72     10004284.86
#Sta/Elev= 30
  3171.7   59.21  3349.7    56.8  3394.2   49.74  3399.6   53.18  3443.3    44.8
  3640.9   41.87  3641.2   41.37  3645.3   41.87  3663.9   45.82  3672.2   43.38
  3678.5   48.62  3693.1    44.8  3699.3   51.34    3743   56.14  3913.7   48.73
  4057.3   57.14  4192.5   55.31  4207.1   51.65  4535.9   53.83  4621.2   44.32
  4656.6   46.13  4998.5   42.16  5665.2   45.62  5833.1   47.76  5923.7   46.08
  6473.2   46.08  6784.3   46.48  6974.1   52.67  7011.9   61.25  7099.2   61.76
#Mann= 11 ,-1 , 0
  3171.7     .17       0  3394.2     .11       0  3640.9     .12       0
  3645.3     .11       0  4656.6    .015       0  5665.2     .15       0
  5833.1     .11       0  5923.7     .15       0  6473.2     .11       0
  6784.3     .17       0  6974.1     .11       0
Bank Sta=4656.6,5665.2
XS Rating Curve= 0 ,0
Exp/Cntr=0.3,0.1

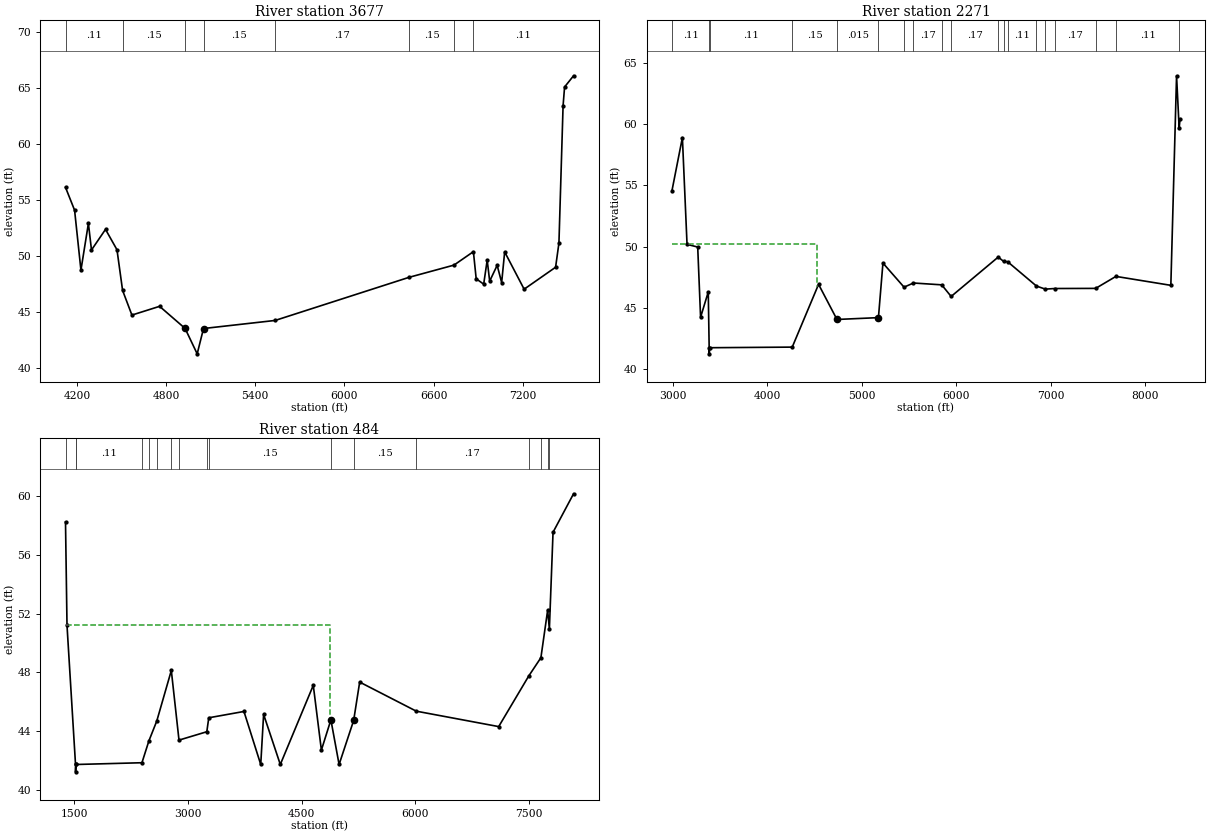
Type RM Length L Ch R = 1 ,3677    ,1406,1406,1406
BEGIN DESCRIPTION:
TxDOT DITCH NO. 4 7.0
END DESCRIPTION:
XS GIS Cut Line= 3
      3906882.07     10007200.43      3907398.82     10006492.33
      3907715.43     10003971.23
#Sta/Elev= 30
  4123.4   56.09  4184.5   54.05  4227.2    48.7  4277.4   52.87  4298.2    50.5
  4392.5   52.34  4469.7   50.52  4507.4   46.89  4570.1   44.69  4756.3   45.47
  4927.7    43.5  5009.2   41.23  5051.7   43.49  5533.3   44.21  6434.4   48.06
  6736.5   49.15  6867.2   50.35    6886   47.93  6936.4   47.45    6960   49.59
  6976.7   47.72  7027.1   49.13  7057.3   47.59  7077.5   50.33  7208.5      47
  7420.1   48.96  7442.6   51.12  7470.5   63.38  7480.6   65.05  7540.9   66.05
#Mann= 8 ,-1 , 0
  4123.4     .11       0  4507.4     .15       0  4927.7    .015       0
  5051.7     .15       0  5533.3     .17       0  6434.4     .15       0
  6736.5     .17       0  6867.2     .11       0
Bank Sta=4927.7,5051.7
XS Rating Curve= 0 ,0
Exp/Cntr=0.3,0.1

Type RM Length L Ch R = 1 ,2271    ,1787,1787,1787
BEGIN DESCRIPTION:
Mapping XS 81d5265a
END DESCRIPTION:
XS GIS Cut Line= 4
       3906779.5     10007357.75      3908307.27     10007626.85
      3908385.39      10007201.5      3907947.19     10003834.75
#Sta/Elev= 30
  2989.4   54.57  3099.7   58.91  3148.9   50.18  3261.9   49.96  3292.3   44.22
  3373.6   46.29  3383.2   41.73  3383.7   41.23  3388.8   41.73  4262.7   41.78
 4541.48   46.91  4736.2   44.04  5175.3   44.19    5223   48.65  5446.5   46.68
  5546.2   47.02  5845.3   46.87  5945.1   45.92  6443.6   49.14  6500.2   48.79
  6543.3   48.76  6848.6   46.77  6942.2   46.52  7041.9   46.57  7475.3   46.58
  7689.6   47.56  8271.2   46.83  8331.7   63.96  8359.2   59.68  8368.3   60.39
#Mann= 19 ,-1 , 0
  2989.4     .11       0  3383.2     .08       0  3388.8     .11       0
  4262.7     .15       0  4736.2    .015       0  5175.3     .17       0
  5446.5     .11       0  5546.2     .17       0  5845.3     .11       0
  5945.1     .17       0  6443.6     .11       0  6500.2     .17       0
  6543.3     .11       0  6848.6     .17       0  6942.2     .11       0
  7041.9     .17       0  7475.3     .15       0  7689.6     .11       0
  8359.2     .17       0
#XS Ineff= 2 , 0
         4529.73   50.19
Permanent Ineff=
       F       F
Bank Sta=4736.2,5175.3
XS Rating Curve= 0 ,0
Exp/Cntr=0.3,0.1

Type RM Length L Ch R = 1 ,484     ,0,0,0
BEGIN DESCRIPTION:
Mapping XS 51f34e06
END DESCRIPTION:
XS GIS Cut Line= 5
      3906881.44     10007400.16      3908162.71     10007884.55
      3910016.87     10007259.55      3910110.62     10006988.71
      3909001.26     10004098.12
#Sta/Elev= 30
  1382.6   58.24  1402.4    51.2  1514.9   41.73  1515.4   41.23  1520.6   41.73
  2392.1   41.85    2484   43.34  2587.9   44.69    2780   48.13  2881.3   43.39
  3248.7   43.96  3274.4   44.91  3739.2   45.34  3960.8   41.73  3998.8   45.14
  4219.2   41.73  4654.7   47.12  4761.8   42.71  4887.3   44.77  4995.6   41.73
    5188   44.73  5267.4   47.34  6015.1   45.36  7103.2   44.31  7499.4   47.75
  7660.7      49    7750   52.24  7772.5   50.94  7820.9   57.54  8091.8   60.16
#Mann= 17 ,-1 , 0
  1382.6     .11       0  1514.9     .12       0  1520.6     .11       0
  2392.1     .15       0    2484     .11       0  2587.9     .15       0
    2780     .17       0  2881.3     .15       0  3248.7     .17       0
  3274.4     .15       0  4887.3    .015       0    5188     .15       0
  6015.1     .17       0  7499.4     .11       0  7660.7     .17       0
    7750     .15       0  7772.5     .17       0
#XS Ineff= 2 , 0
         4871.91    51.2
Permanent Ineff=
       F       F
Bank Sta=4887.3,5188
XS Rating Curve= 0 ,0
Exp/Cntr=0.3,0.1

Chan Stop Cuts=-1
Use User Specified Reach Order=0
Composite Channel Slope=5