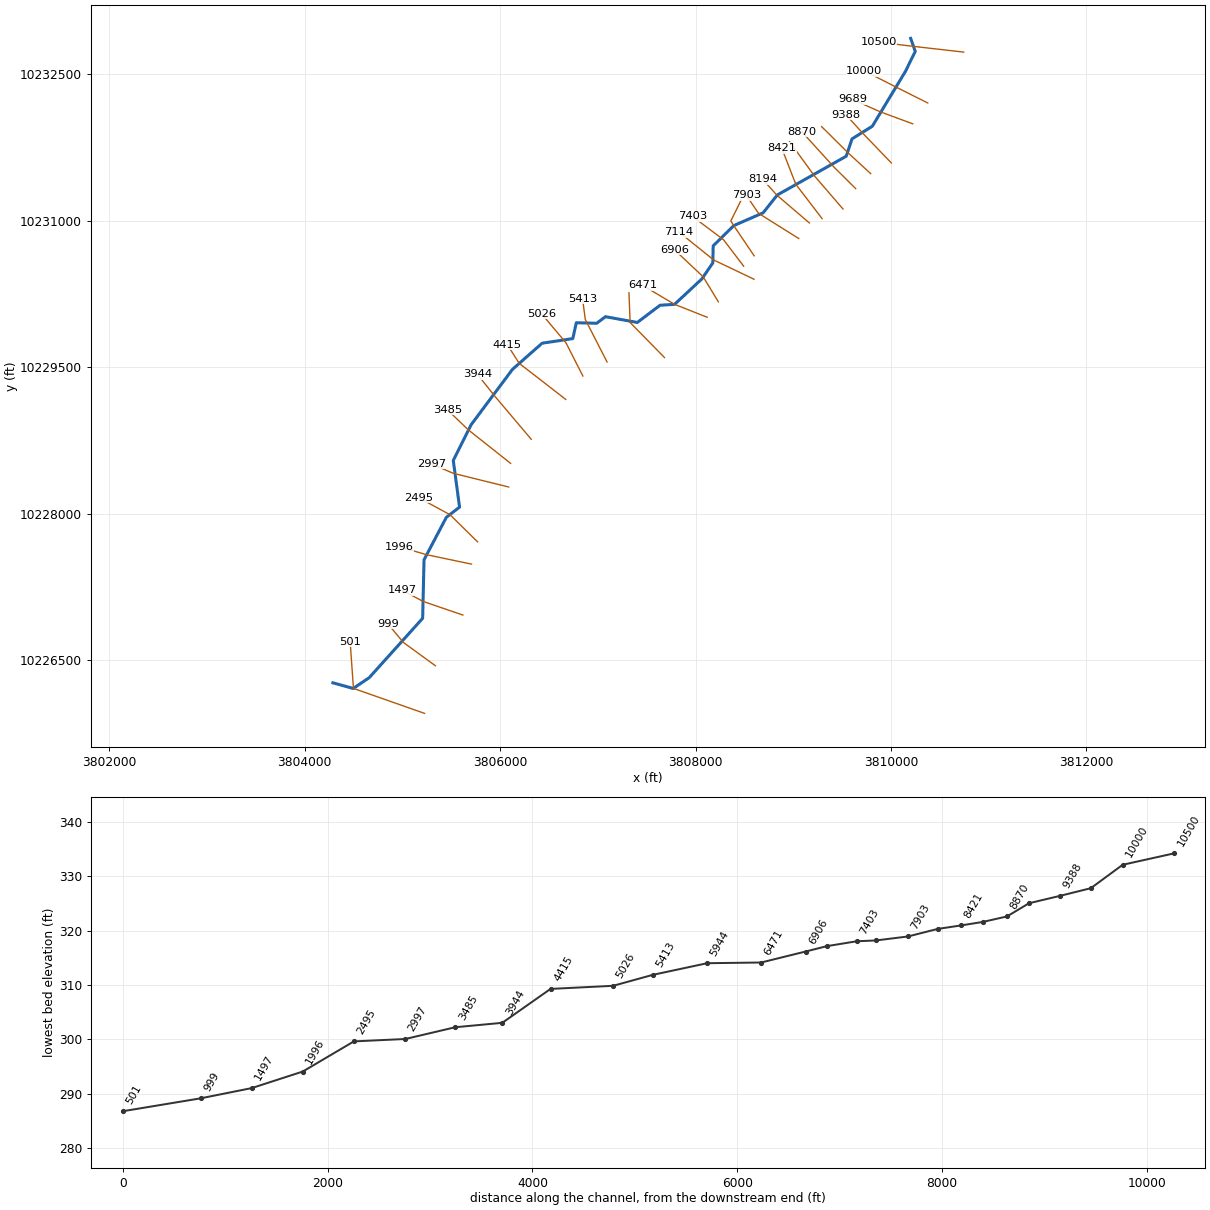
--- ALLIGATOR BRANCH.prj (project) ---

Proj Title=ALLIGATOR BRANCH Base Level Engineering
Current Plan=p01
Default Exp/Contr=0.3,0.1
English Units
Geom File=g01
Flow File=f01
Flow File=f02
Plan File=p01
Y Axis Title=Elevation
X Axis Title(PF)=Main Channel Distance
X Axis Title(XS)=Station
BEGIN DESCRIPTION:
ALLIGATOR BRANCH
END DESCRIPTION:
DSS File=dss
DSS Export Rating Curves= 0
DSS Export Rating Curve Sorted= 0
DSS Export Volume Flow Curves= 0
DXF OffsetX= 0
DXF OffsetY= 0
DXF ScaleX= 1
DXF ScaleY= 10

--- ALLIGATOR BRANCH.p01 (plan) ---

Plan Title=Multiple Run
Program Version=4.10
Short Identifier=Multiple Run
Geom File=g01
Flow File=f01
Subcritical Flow
K Sum by GR= 0
Std Step Tol= 0.01
Critical Tol= 0.01
Num of Std Step Trials= 20
Max Error Tol= 0.3
Flow Tol Ratio= 0.001
Split Flow NTrial= 30
Split Flow Tol= 0.02
Split Flow Ratio= 0.02
Log Output Level= 0
Friction Slope Method= 1
Unsteady Friction Slope Method= 2
Unsteady Bridges Friction Slope Method= 1
Parabolic Critical Depth
Global Vel Dist= 1 , 1 , 1
Global Log Level= 0
CheckData=True
Encroach Param=-1 ,0,0, 0
BEGIN DESCRIPTION:
Multiple Run
END DESCRIPTION:
Computation Interval=1HOUR
Output Interval=1HOUR
Run HTab= 0
Run UNet= 0
Run PostProcess= 0
Run WQNet= 0
UNET Theta= 1
UNET Theta Warmup= 1
UNET ZTol= 0.02
UNET ZSATol= 0.05
UNET MxIter= 20
UNET MaxInSteps= 0
UNET DtIC= 0
UNET DtMin= 0
UNET MaxCRTS= 20
UNET WFStab= 2
UNET SFStab= 1
UNET WFX= 1
UNET SFX= 1
UNET DSS MLevel= 4
UNET DZMax Abort= 100
UNET Convert EG Bridges= 0
UNET Use Existing IB Tables=-1
UNET Froude Reduction=False
UNET Froude Limit= 1
UNET Froude Power= 10
UNET Time Slicing=0,0, 5
UNET Junction Losses=0
Instantaneous Interval=1HOUR
DSS File=dss
Write IC File= 0
Write IC File at Sim End=0
Echo Input=False
Echo Parameters=False
Echo Output=False
Write Detailed= 0
WQ AD Non Conservative
WQ ULTIMATE=-1
WQ Max Comp Step=1HOUR
WQ Output Interval=15MIN
WQ Output Selected Increments= 0
WQ Output face flow=0
WQ Output face velocity=0
WQ Output face area=0
WQ Output face dispersion=0
WQ Output cell volume=0
WQ Output cell surface area=0
WQ Output cell continuity=0
WQ Output cumulative cell continuity=0
WQ Output face conc=0
WQ Output face dconc_dx=0
WQ Output face courant=0
WQ Output face peclet=0
WQ Output face adv mass=0
WQ Output face disp mass=0
WQ Output cell mass=0
WQ Output cell source sink temp=0
WQ Output cell source sink nsm=0
WQ Output MaxMinRange=-1
WQ Daily Max Min Mean=-1
WQ Daily Range=0
WQ Daily Time=0
WQ Create Restart=0
WQ Fixed Restart=0
WQ System Summary=0
WQ Use Fixed Temperature=0
Sorting and Armoring Iterations= 10
XS Update Threshold= 0.02
Hydraulics Update Threshold= 0.02
Energy Slope Method= 1
Volume Change Method= 0
XS Weighting Method= 0
Number of US Weighted Cross Sections= 1
Number of DS Weighted Cross Sections= 1
Upstream XS Weight=0.25
Main XS Weight=0.5
Downstream XS Weight=0.25
Number of DS XS's Weighted with US Boundary= 1
Upstream Boundary Weight= 1
Weight of XSs Associated with US Boundary= 0
Number of US XS's Weighted with DS Boundary= 1
Downstream Boundary Weight= 0.5
Weight of XSs Associated with DS Boundary= 0.5
Sediment Output Level= 4
Mass or Volume Output= 0
Output Increment Type= 1
Profile and TS Output Increment= 10
XS Output Flag= 0
XS Output Increment= 10
Disregard all LS=0
Disregard all Conn=0
Disregard all Breaches=0
Disregard all Pumps=0

--- ALLIGATOR BRANCH.f01 (steady flow) ---

Flow Title=Multiple
Program Version=4.10
Number of Profiles= 7
Profile Names=10-year,25-year,50-year,1pct_min,100-year,1pct_plu,500-year
River Rch & RM=ALLIGATOR BRANCH,Reach-1         ,10500
     807    1115    1530     691    2087    6303    4013
River Rch & RM=ALLIGATOR BRANCH,Reach-1         ,7403
    1348    1892    2620    1190    3595   10857    7004
River Rch & RM=ALLIGATOR BRANCH,Reach-1         ,7114
    1348    1892    2620    1190    3595   10857    7004
River Rch & RM=ALLIGATOR BRANCH,Reach-1         ,6906
    1348    1892    2620    1190    3595   10857    7004
Boundary for River Rch & Prof#=ALLIGATOR BRANCH,Reach-1         , 1
Up Type= 0
Dn Type= 3
Dn Slope=0.005
Boundary for River Rch & Prof#=ALLIGATOR BRANCH,Reach-1         , 2
Up Type= 0
Dn Type= 3
Dn Slope=0.005
Boundary for River Rch & Prof#=ALLIGATOR BRANCH,Reach-1         , 3
Up Type= 0
Dn Type= 3
Dn Slope=0.005
Boundary for River Rch & Prof#=ALLIGATOR BRANCH,Reach-1         , 4
Up Type= 0
Dn Type= 3
Dn Slope=0.005
Boundary for River Rch & Prof#=ALLIGATOR BRANCH,Reach-1         , 5
Up Type= 0
Dn Type= 3
Dn Slope=0.005
Boundary for River Rch & Prof#=ALLIGATOR BRANCH,Reach-1         , 6
Up Type= 0
Dn Type= 3
Dn Slope=0.005
Boundary for River Rch & Prof#=ALLIGATOR BRANCH,Reach-1         , 7
Up Type= 0
Dn Type= 3
Dn Slope=0.005
DSS Import GetInterval= 0
DSS Import GetPeak= 0
DSS Import FillOption= 0

--- ALLIGATOR BRANCH.f02 (steady flow) ---

Flow Title=Orig_BLE_Flow
Program Version=4.10
Number of Profiles= 7
Profile Names=10-year,25-year,50-year,1pct_min,100-year,1pct_plu,500-year
River Rch & RM=ALLIGATOR BRANCH,Reach-1         ,10500
     807    1093    1330     532    1605    4848    2333
River Rch & RM=ALLIGATOR BRANCH,Reach-1         ,7403
    1348    1855    2278     916    2765    8352    4072
River Rch & RM=ALLIGATOR BRANCH,Reach-1         ,7114
    1348    1855    2278     916    2765    8352    4072
River Rch & RM=ALLIGATOR BRANCH,Reach-1         ,6906
    1348    1855    2278     916    2765    8352    4072
Boundary for River Rch & Prof#=ALLIGATOR BRANCH,Reach-1         , 1
Up Type= 0
Dn Type= 3
Dn Slope=0.005
Boundary for River Rch & Prof#=ALLIGATOR BRANCH,Reach-1         , 2
Up Type= 0
Dn Type= 3
Dn Slope=0.005
Boundary for River Rch & Prof#=ALLIGATOR BRANCH,Reach-1         , 3
Up Type= 0
Dn Type= 3
Dn Slope=0.005
Boundary for River Rch & Prof#=ALLIGATOR BRANCH,Reach-1         , 4
Up Type= 0
Dn Type= 3
Dn Slope=0.005
Boundary for River Rch & Prof#=ALLIGATOR BRANCH,Reach-1         , 5
Up Type= 0
Dn Type= 3
Dn Slope=0.005
Boundary for River Rch & Prof#=ALLIGATOR BRANCH,Reach-1         , 6
Up Type= 0
Dn Type= 3
Dn Slope=0.005
Boundary for River Rch & Prof#=ALLIGATOR BRANCH,Reach-1         , 7
Up Type= 0
Dn Type= 3
Dn Slope=0.005
DSS Import GetInterval= 0
DSS Import GetPeak= 0
DSS Import FillOption= 0

--- ALLIGATOR BRANCH.g01 (geometry) ---

Geom Title=Existing Conditions
Program Version=4.10

River Reach=ALLIGATOR BRANCH,Reach-1
Reach XY= 30
      3810200.67     10232867.56      3810248.07     10232733.71
      3810146.16     10232526.81      3809808.23     10231966.84
      3809601.12     10231838.36      3809541.21     10231659.96
      3808835.94     10231263.17      3808691.47     10231080.86
      3808390.42     10230949.44      3808179.78     10230741.72
      3808176.23     10230567.64      3808062.81     10230402.21
      3807784.46     10230143.07      3807636.66     10230133.96
      3807403.04     10229957.53      3807077.27     10230016.66
      3806986.98     10229948.91      3806779.08     10229954.76
      3806743.03     10229792.13      3806429.18     10229745.01
      3806125.29     10229476.78      3805702.42     10228909.95
      3805519.91      10228545.2      3805584.11     10228066.12
      3805449.14     10227961.94      3805220.54     10227526.78
      3805206.57     10226927.56      3804659.72     10226319.64
      3804496.26     10226209.01      3804287.78     10226266.77

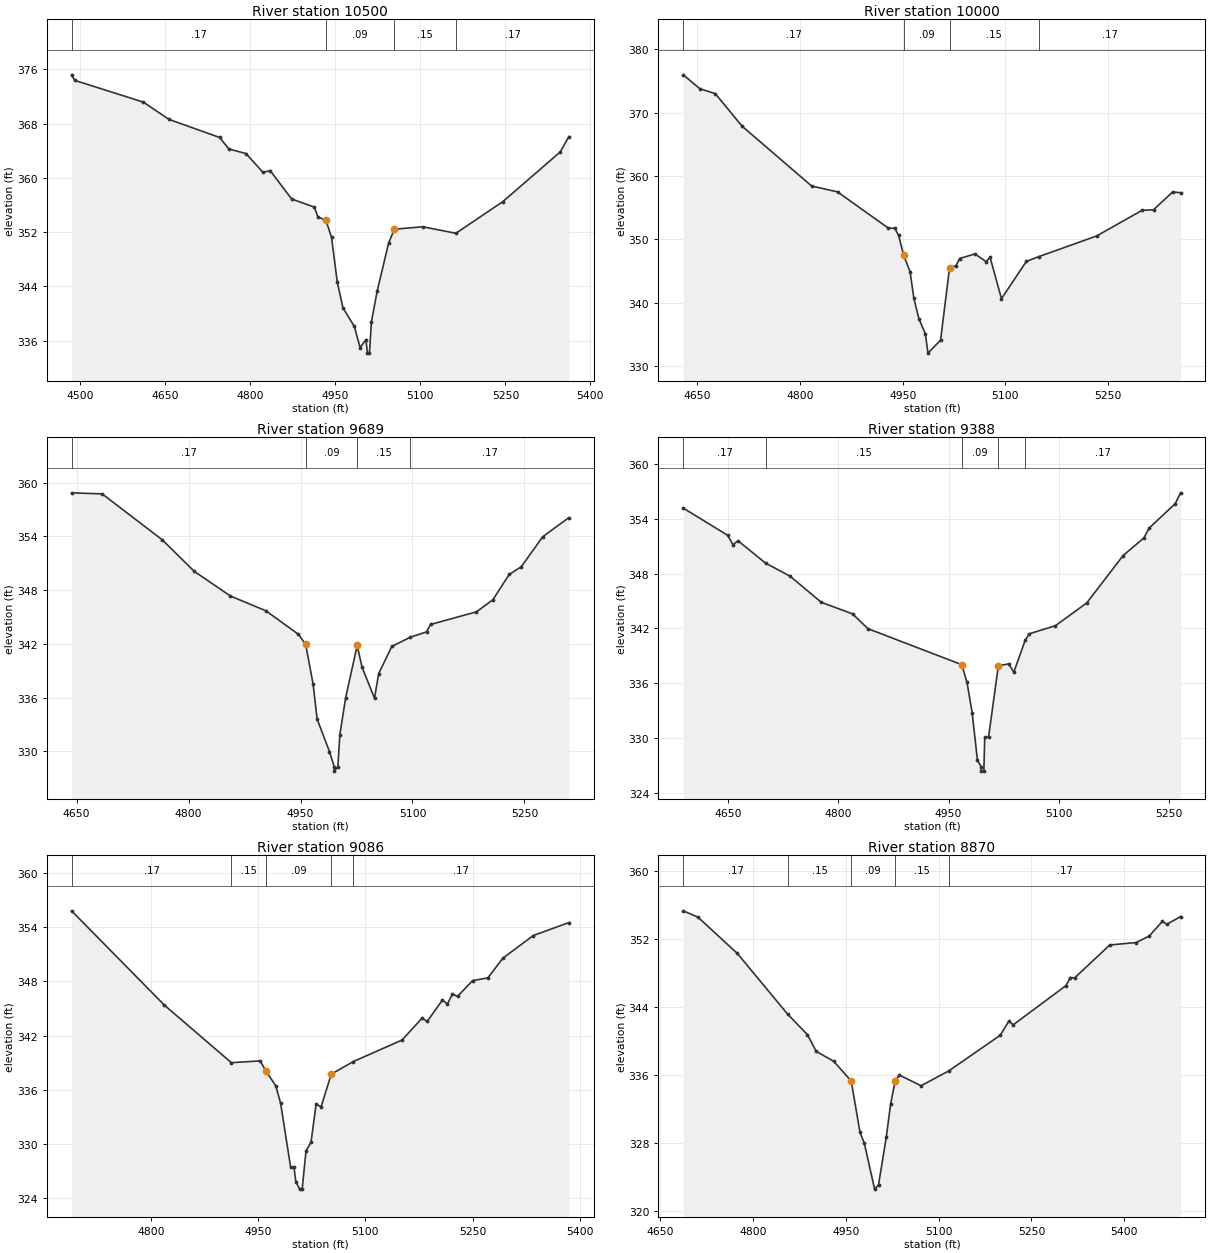
Type RM Length L Ch R = 1 ,10500   ,500,500,500
BEGIN DESCRIPTION:
ALLIGATOR BRANCH 26.0
END DESCRIPTION:
XS GIS Cut Line= 3
      3810743.61      10232726.5      3810231.45     10232785.11
      3809872.05     10232828.39
#Sta/Elev= 30
  4484.5  375.18  4490.3  374.36  4611.1  371.16  4656.5  368.61  4745.8  365.95
  4762.1  364.25  4792.2  363.58  4822.4   360.8    4835  361.07  4872.8  356.89
    4913  355.68  4919.3  354.21  4933.2  353.78  4943.2  351.25  4953.3  344.68
  4963.4  340.84  4983.5   338.1  4993.6  334.99    5004  336.16  5006.6  334.17
  5010.1  334.17  5013.7  338.82  5023.8  343.32  5043.9  350.37    5054  352.43
  5104.3  352.79  5162.7  351.83  5245.4  356.49  5346.8  363.82    5362  366.08
#Mann= 4 ,-1 , 0
  4484.5     .17       0  4933.2     .09       0    5054     .15       0
  5162.7     .17       0
Bank Sta=4933.2,5054
XS Rating Curve= 0 ,0
Exp/Cntr=0.3,0.1

Type RM Length L Ch R = 1 ,10000   ,311,311,311
BEGIN DESCRIPTION:
ALLIGATOR BRANCH 25.0
END DESCRIPTION:
XS GIS Cut Line= 3
      3810375.64     10232205.58      3810044.33     10232371.87
      3809727.14     10232533.73
#Sta/Elev= 30
  4629.3  375.95  4653.7  373.76  4676.1  372.99  4715.2  367.87    4817  358.42
  4854.8   357.5  4928.9   351.8  4938.5  351.75  4944.1  350.63  4951.3  347.55
  4960.8  344.93  4966.4   340.7  4973.7  337.51  4983.2  335.11    4987  332.08
  5005.4  334.13  5018.5  345.51  5027.7  345.85  5033.3  346.99  5055.5  347.72
  5072.1   346.5  5077.7   347.2  5094.4  340.66  5130.8  346.54  5149.4  347.31
  5233.3  350.54    5300   354.6  5316.6  354.68  5344.5  357.48  5356.1  357.37
#Mann= 4 ,-1 , 0
  4629.3     .17       0  4951.3     .09       0  5018.5     .15       0
  5149.4     .17       0
#XS Ineff= 2 , 0
       0                  5055.5       0  347.72
Permanent Ineff=
       F       F
Bank Sta=4951.3,5018.5
XS Rating Curve= 0 ,0
Exp/Cntr=0.3,0.1

Type RM Length L Ch R = 1 ,9689    ,301,301,301
BEGIN DESCRIPTION:
ALLIGATOR BRANCH 24.0
END DESCRIPTION:
XS GIS Cut Line= 3
      3810221.99     10231992.04       3809887.4     10232115.93
      3809604.76     10232242.06
#Sta/Elev= 30
  4643.2  358.86  4684.3  358.74  4764.8  353.61  4807.6  350.09    4856  347.34
  4903.5  345.69  4947.2  343.06  4956.9  341.93  4966.9  337.47  4972.2   333.6
  4988.8  329.96  4995.1  328.28  4995.3  327.78    5000  328.28  5002.7  331.87
  5010.5     336  5025.9  341.81  5032.4  339.39  5049.1  335.92  5054.6  338.65
  5072.3  341.71  5097.3  342.74  5118.8  343.33  5124.2  344.16  5185.7  345.57
  5207.6  346.91  5229.5  349.74  5245.8  350.61  5274.5  353.96  5309.5  356.09
#Mann= 4 ,-1 , 0
  4643.2     .17       0  4956.9     .09       0  5025.9     .15       0
  5097.3     .17       0
#XS Ineff= 2 , 0
       0                  5025.9       0  341.81
Permanent Ineff=
       F       F
Bank Sta=4956.9,5025.9
XS Rating Curve= 0 ,0
Exp/Cntr=0.3,0.1

Type RM Length L Ch R = 1 ,9388    ,302,302,302
BEGIN DESCRIPTION:
ALLIGATOR BRANCH 23.0
END DESCRIPTION:
XS GIS Cut Line= 3
       3810003.2     10231591.02      3809718.67     10231887.33
      3809539.69     10232083.17
#Sta/Elev= 30
  4589.2  355.18  4649.6   352.2  4656.8  351.17  4663.7   351.6  4701.2  349.15
  4734.5  347.72  4776.9  344.86  4819.4  343.59  4840.4  341.97  4967.8  338.03
    4975   336.1    4982  332.77  4989.2  327.55  4994.1  326.87  4994.4  326.37
  4997.9  326.37  4999.1  330.09  5004.3  330.09  5017.6   337.9  5031.8  338.12
  5038.6  337.21  5054.1  340.69  5059.6  341.41  5095.3   342.3  5137.9   344.8
  5187.2  349.98  5215.6  351.92  5222.4  352.97  5258.2  355.68  5265.3  356.85
#Mann= 5 ,-1 , 0
  4589.2     .17       0  4701.2     .15       0  4967.8     .09       0
  5017.6     .15       0  5054.1     .17       0
Bank Sta=4967.8,5017.6
XS Rating Curve= 0 ,0
Exp/Cntr=0.3,0.1

Type RM Length L Ch R = 1 ,9086    ,216,216,216
BEGIN DESCRIPTION:
ALLIGATOR BRANCH 22.0
END DESCRIPTION:
XS GIS Cut Line= 3
      3809792.27     10231481.64      3809562.94     10231692.31
      3809289.69     10231963.38
#Sta/Elev= 30
  4688.6  355.79  4818.5  345.37  4912.4     339  4952.9   339.2  4960.3  338.12
  4974.5  336.45  4981.3  334.52  4995.4  327.43    5000  327.43  5002.7  325.82
    5008  325.02  5011.5  325.02  5016.9  329.24  5023.9  330.21    5031  334.39
  5038.1  334.14  5052.2  337.73    5083  339.12  5151.2   341.5  5179.5  343.93
  5186.6  343.57  5207.8  345.92  5214.9   345.5  5221.9  346.58    5229  346.33
  5250.2  348.08  5271.4  348.37  5292.6  350.56  5335.1  353.06  5384.9  354.49
#Mann= 5 ,-1 , 0
  4688.6     .17       0  4912.4     .15       0  4960.3     .09       0
  5052.2     .15       0    5083     .17       0
Bank Sta=4960.3,5052.2
XS Rating Curve= 0 ,0
Exp/Cntr=0.3,0.1

Type RM Length L Ch R = 1 ,8870    ,236,236,236
BEGIN DESCRIPTION:
ALLIGATOR BRANCH 21.0
END DESCRIPTION:
XS GIS Cut Line= 3
       3809638.6     10231328.01       3809416.9     10231548.25
      3809086.53     10231911.34
#Sta/Elev= 30
  4687.5  355.34  4711.4  354.59    4775  350.32  4856.3  343.17  4888.2  340.77
  4902.3   338.8  4930.6  337.64  4958.9  335.32    4973   329.3  4980.1  327.97
  4996.7  322.59    5003  323.09  5015.7  328.77  5022.5  332.58  5029.9  335.35
  5036.7  336.01  5071.8  334.76  5116.4   336.5  5199.5  340.69  5213.7  342.38
  5220.5  341.92  5305.6  346.53    5313  347.49  5319.8  347.45  5376.6  351.32
  5419.1  351.61  5440.1  352.36  5461.7  354.11  5468.5  353.75  5490.9  354.66
#Mann= 5 ,-1 , 0
  4687.5     .17       0  4856.3     .15       0  4958.9     .09       0
  5029.9     .15       0  5116.4     .17       0
#XS Ineff= 2 , 0
       0                  5036.7       0  336.01
Permanent Ineff=
       F       F
Bank Sta=4958.9,5029.9
XS Rating Curve= 0 ,0
Exp/Cntr=0.3,0.1

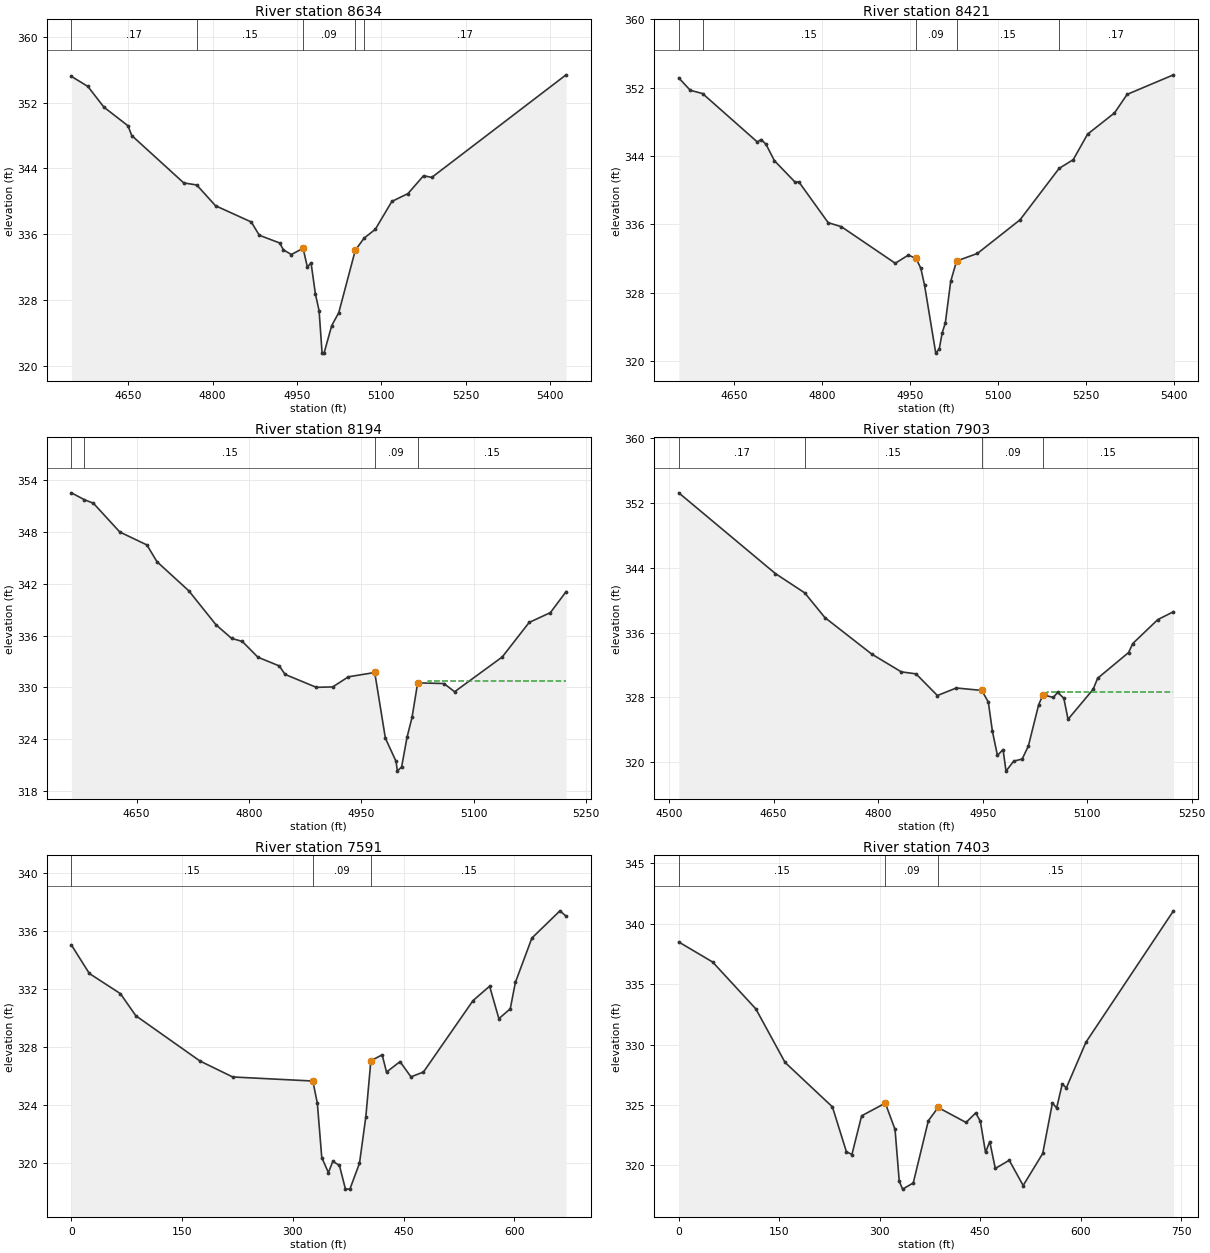
Type RM Length L Ch R = 1 ,8634    ,213,213,213
BEGIN DESCRIPTION:
ALLIGATOR BRANCH 20.0
END DESCRIPTION:
XS GIS Cut Line= 3
      3809508.38     10231119.69      3809213.71     10231461.51
      3808962.22     10231808.82
#Sta/Elev= 30
  4548.7  355.17    4578  353.95  4606.5  351.44  4649.3  349.18  4656.1  347.99
  4748.6  342.24  4771.7  341.99  4805.1  339.47  4868.7   337.5    4883  335.89
  4919.2  334.95  4925.8  334.12    4940  333.55  4960.9   334.3  4968.5  332.04
  4975.1  332.53  4982.8  328.77  4989.4  326.72  4994.7  321.58  4998.2  321.58
  5011.8  324.91  5024.4   326.5  5053.8  334.07  5069.5  335.54  5089.4  336.61
  5118.8  339.99  5147.6  340.95  5175.2  343.11  5189.9  342.91  5428.8  355.36
#Mann= 5 ,-1 , 0
  4548.7     .17       0  4771.7     .15       0  4960.9     .09       0
  5053.8     .15       0  5069.5     .17       0
#XS Ineff= 2 , 0
       0  4960.9   334.3               0
Permanent Ineff=
       F       F
Bank Sta=4960.9,5053.8
XS Rating Curve= 0 ,0
Exp/Cntr=0.3,0.1

Type RM Length L Ch R = 1 ,8421    ,227,227,227
BEGIN DESCRIPTION:
ALLIGATOR BRANCH 19.0
END DESCRIPTION:
XS GIS Cut Line= 3
      3809294.88     10231020.68       3809025.2     10231372.89
      3808880.82     10231744.64
#Sta/Elev= 30
  4556.4  353.15    4576   351.7  4596.9  351.32  4690.2  345.65  4696.5  345.94
  4704.8   345.4  4719.3  343.46  4754.6  340.94  4760.9  340.98  4810.8  336.21
  4833.5  335.73    4925  331.46  4947.3  332.41  4960.4  332.03  4968.6  330.87
  4974.9  328.91    4994  320.94    5000  321.44    5005  323.33  5010.3  324.47
  5019.5  329.35  5029.5  331.72  5064.8   332.6  5137.5  336.54  5204.1  342.56
  5228.1  343.58  5252.6  346.57  5298.4  349.05  5319.9  351.22  5398.8  353.51
#Mann= 5 ,-1 , 0
  4556.4     .17       0  4596.9     .15       0  4960.4     .09       0
  5029.5     .15       0  5204.1     .17       0
Bank Sta=4960.4,5029.5
XS Rating Curve= 0 ,0
Exp/Cntr=0.3,0.1

Type RM Length L Ch R = 1 ,8194    ,291,291,291
BEGIN DESCRIPTION:
ALLIGATOR BRANCH 18.0
END DESCRIPTION:
XS GIS Cut Line= 3
      3809164.65     10230976.44      3808832.52     10231260.59
      3808683.26     10231426.54
#Sta/Elev= 30
  4562.9  352.55  4580.1  351.76  4592.3  351.34  4627.5  348.01  4663.7  346.51
  4677.1  344.57  4719.7  341.19  4755.9  337.26  4776.8  335.68    4791  335.33
  4811.9   333.5  4840.4  332.49  4848.1  331.51  4889.8  330.01  4911.8  330.06
  4932.6  331.23  4967.8  331.73    4982  324.12  4996.3  321.42    4998   320.3
  5003.7   320.8  5010.9  324.22  5017.6  326.53  5025.1  330.53  5060.2  330.45
  5074.4   329.5    5138  333.53  5173.9  337.53  5202.3  338.67  5223.2   341.1
#Mann= 4 ,-1 , 0
  4562.9     .17       0  4580.1     .15       0  4967.8     .09       0
  5025.1     .15       0
#XS Ineff= 2 , 0
       0  4967.8  331.73  5039.3       0  330.72
Permanent Ineff=
       F       F
Bank Sta=4967.8,5025.1
XS Rating Curve= 0 ,0
Exp/Cntr=0.3,0.1

Type RM Length L Ch R = 1 ,7903    ,313,313,313
BEGIN DESCRIPTION:
ALLIGATOR BRANCH 17.0
END DESCRIPTION:
XS GIS Cut Line= 3
      3809055.27     10230817.59      3808643.49     10231075.92
      3808517.83     10231261.11
#Sta/Elev= 30
  4513.9  353.22  4652.5  343.27  4694.6  340.89  4723.6  337.84  4790.8  333.34
  4833.2  331.15  4854.4   330.9    4885  328.23  4912.2  329.16  4948.7  328.86
  4958.1  327.43    4964  323.82  4971.2  320.85  4979.3  321.57  4983.5  318.91
  4994.5  320.14  5006.7   320.4  5015.6  322.01  5030.4  327.11  5036.6  328.32
  5051.5  327.99  5057.6  328.63  5066.5  327.89  5072.5   325.3  5108.5  328.99
    5115  330.36  5159.4  333.53  5165.4  334.64  5201.3  337.59  5223.8  338.56
#Mann= 4 ,-1 , 0
  4513.9     .17       0  4694.6     .15       0  4948.7     .09       0
  5036.6     .15       0
#XS Ineff= 2 , 0
       0  4912.2  329.16  5042.6       0  328.62
Permanent Ineff=
       F       F
Bank Sta=4948.7,5036.6
XS Rating Curve= 0 ,0
Exp/Cntr=0.3,0.1

Type RM Length L Ch R = 1 ,7591    ,187,187,187
XS GIS Cut Line= 4
      3808599.12     10230639.95      3808390.42     10230949.44
      3808360.41     10230997.63      3808467.02     10231212.57
#Sta/Elev= 30
       0  335.05    24.3  333.08    66.3  331.69    87.3  330.16   174.2  327.03
   218.5  325.93     327  325.65   333.1  324.12   339.1  320.36   348.1  319.32
   354.1   320.1     363  319.82   371.2  318.18   377.2  318.18   390.2  319.97
   398.8  323.19   405.6  327.05   420.9  327.46   426.8  326.27   445.1  326.99
   459.9  325.94   476.8  326.27     544  331.21   566.4   332.2     579  329.96
   594.4  330.64   601.3  332.46   623.7  335.53   661.7  337.41     670  337.04
#Mann= 3 , 0 , 0
       0     .15       0     327     .09       0   405.6     .15       0
Bank Sta=327,405.6
XS Rating Curve= 0 ,0
Exp/Cntr=0.3,0.1

Type RM Length L Ch R = 1 ,7403    ,290,290,290
XS GIS Cut Line= 3
      3808491.94     10230533.75      3808286.78      10230803.5
      3807967.64     10231044.16
#Sta/Elev= 30
       0  338.49    50.6  336.83   115.1  332.95   158.7  328.52   229.4  324.84
   250.2  321.14   258.5  320.89     273   324.1   308.4  325.15   322.9  322.97
   329.2  318.68   334.2  318.03   350.1  318.54   372.6  323.69   387.2  324.79
   428.9  323.55   443.4  324.34   450.3  323.64     458  321.07   464.3  321.97
   472.6  319.74   493.4  320.42   514.2  318.33   543.4  320.98   557.9  325.16
   564.2  324.75   572.5  326.72   578.7  326.42   607.9  330.19   738.6  341.07
#Mann= 3 , 0 , 0
       0     .15       0   308.4     .09       0   387.2     .15       0
Bank Sta=308.4,387.2
XS Rating Curve= 0 ,0
Exp/Cntr=0.3,0.1

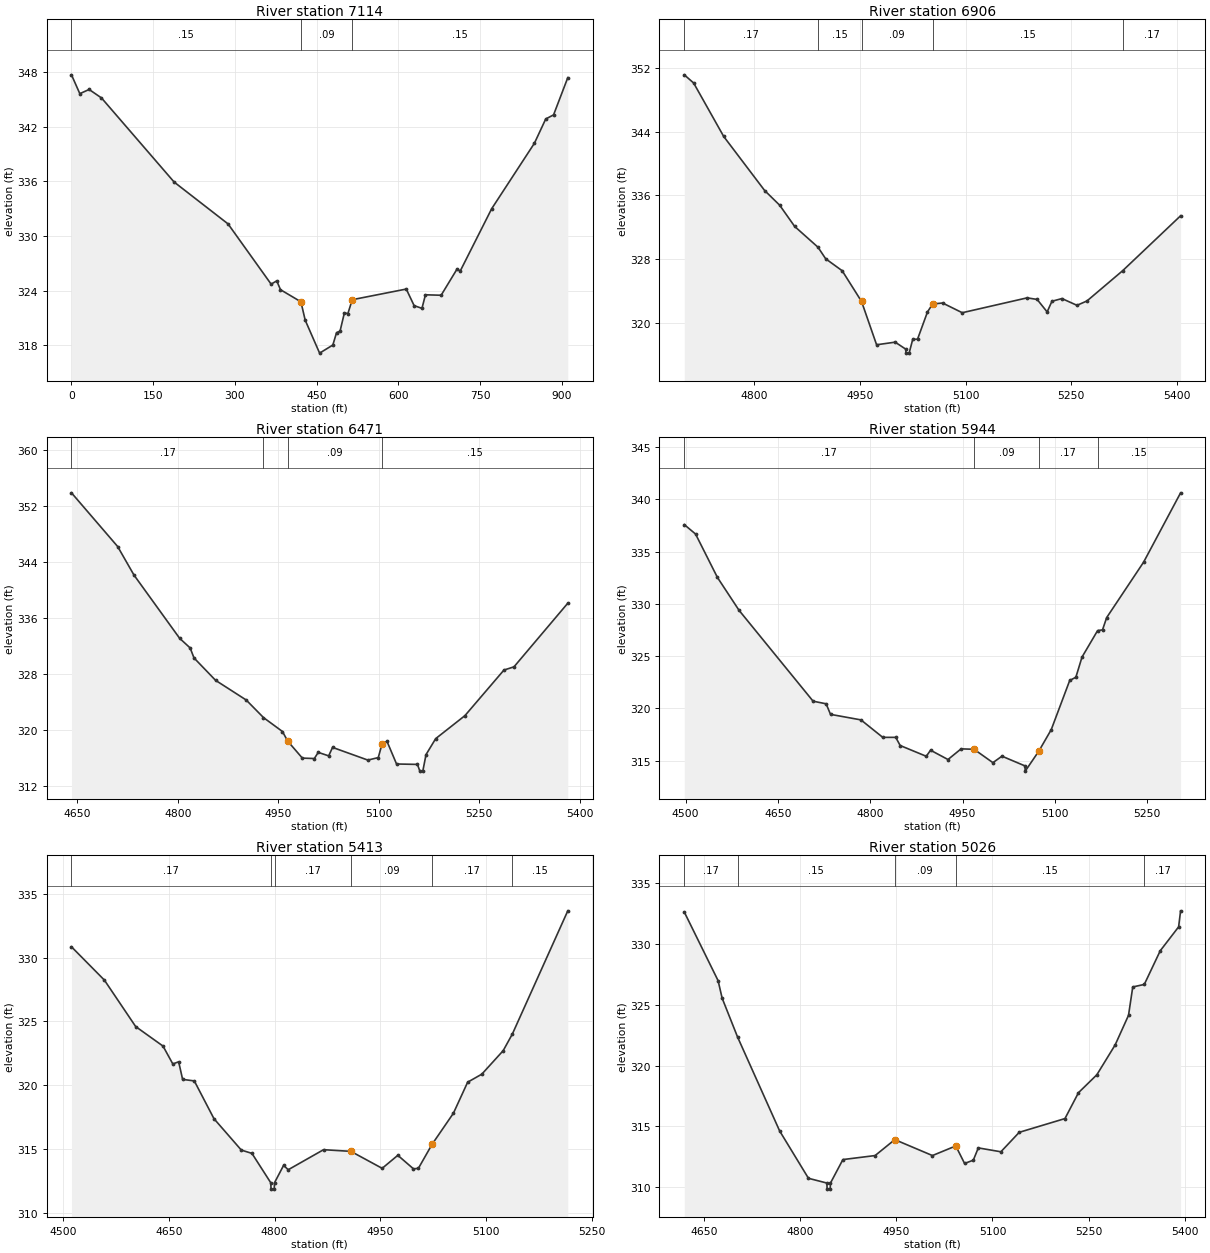
Type RM Length L Ch R = 1 ,7114    ,208,208,208
XS GIS Cut Line= 3
      3808597.85     10230400.07        3808186.     10230596.93
      3807830.48     10230882.71
#Sta/Elev= 30
       0  347.72    15.3  345.65    32.4  346.11    55.1  345.18   188.4  335.94
   287.4  331.34   366.5  324.72   376.8  325.08   383.7  324.11   421.2  322.78
     429  320.77   455.5  317.14   479.8  318.03   486.6  319.39     493  319.55
     501  321.57   507.4  321.48   515.4  323.01   614.6  324.18     629  322.36
   643.4  322.06   649.8  323.55   678.6   323.5   707.4  326.34   713.8  326.18
   771.4  333.01   849.8   340.2   870.6  342.87     885  343.32   911.1  347.41
#Mann= 3 , 0 , 0
       0     .15       0   421.2     .09       0   515.4     .15       0
Bank Sta=421.2,515.4
XS Rating Curve= 0 ,0
Exp/Cntr=0.3,0.1

Type RM Length L Ch R = 1 ,6906    ,435,435,435
BEGIN DESCRIPTION:
ALLIGATOR BRANCH 14.0
END DESCRIPTION:
XS GIS Cut Line= 3
      3808232.55     10230169.27      3808077.18     10230425.43
      3807782.04     10230703.49
#Sta/Elev= 30
  4700.4  351.14  4713.7  350.11  4756.4  343.39  4814.6  336.59  4835.9  334.75
  4857.2  332.08  4890.3  329.47  4901.3  328.01  4924.7  326.51  4952.2  322.65
  4973.6   317.2    5000  317.53    5015  316.65  5015.4  316.15  5019.8  316.15
  5024.9  317.87  5031.8  317.91  5045.9  321.33  5053.2  322.33  5067.4  322.45
  5095.3  321.23  5187.5   323.1  5201.7   322.9  5215.9  321.33  5222.7  322.67
  5236.9  323.01  5258.3  322.16  5272.5  322.71  5323.4  326.53  5405.5  333.42
#Mann= 5 ,-1 , 0
  4700.4     .17       0  4890.3     .15       0  4952.2     .09       0
  5053.2     .15       0  5323.4     .17       0
Bank Sta=4952.2,5053.2
XS Rating Curve= 0 ,0
Exp/Cntr=0.3,0.1

Type RM Length L Ch R = 1 ,6471    ,527,527,527
BEGIN DESCRIPTION:
ALLIGATOR BRANCH 13.0
END DESCRIPTION:
XS GIS Cut Line= 3
      3808117.88     10230011.06      3807784.46     10230143.07
      3807455.96     10230338.41
#Sta/Elev= 30
  4641.4  353.89  4710.3  346.22  4734.7  342.14  4802.8  333.11  4818.5  331.73
  4824.3   330.3  4856.5   327.1  4902.2  324.29    4928  321.78  4956.3  319.79
  4964.1  318.42    4986  315.99  5003.9  315.93  5009.7  316.81  5025.3  316.31
  5031.1  317.52  5083.7  315.71  5099.3  316.06  5105.1  318.05  5112.4  318.37
  5126.6  315.15  5157.8  315.09  5161.4  314.13  5165.8  314.13  5170.6  316.49
    5185  318.77  5228.7  322.06  5286.9  328.57  5301.9  329.03  5382.2  338.12
#Mann= 4 ,-1 , 0
  4641.4     .17       0    4928     .15       0  4964.1     .09       0
  5105.1     .15       0
Bank Sta=4964.1,5105.1
XS Rating Curve= 0 ,0
Exp/Cntr=0.3,0.1

Type RM Length L Ch R = 1 ,5944    ,531,531,531
BEGIN DESCRIPTION:
ALLIGATOR BRANCH 12.0
END DESCRIPTION:
XS GIS Cut Line= 3
      3807681.22     10229598.43      3807329.69     10229956.95
      3807317.85     10230261.12
#Sta/Elev= 30
  4497.9  337.58  4516.2  336.68  4551.7  332.53  4586.9  329.38  4707.2  320.69
  4728.4  320.44  4735.5  319.43    4785   318.9  4820.4  317.23  4841.5  317.23
  4848.7  316.45  4891.1  315.42  4898.1     316  4926.4  315.11  4947.7  316.13
  4968.8  316.09  4999.4  314.81  5014.1  315.43  5051.5   314.5  5051.9     314
  5074.2  315.93  5094.2  317.97  5124.2  322.67  5134.2  322.98  5144.2  324.91
  5169.5  327.44  5177.5  327.51  5184.3  328.69  5244.3  333.99  5304.4  340.62
#Mann= 4 ,-1 , 0
  4497.9     .17       0  4968.8     .09       0  5074.2     .17       0
  5169.5     .15       0
Bank Sta=4968.8,5074.2
XS Rating Curve= 0 ,0
Exp/Cntr=0.3,0.1

Type RM Length L Ch R = 1 ,5413    ,387,387,387
BEGIN DESCRIPTION:
ALLIGATOR BRANCH 11.0
END DESCRIPTION:
XS GIS Cut Line= 3
      3807093.35     10229553.06      3806871.15     10229987.65
      3806842.69     10230201.97
#Sta/Elev= 30
  4511.9  330.85  4558.6  328.24    4603   324.6  4641.8  323.07  4655.7  321.67
    4664  321.84  4669.6  320.46  4686.2  320.34  4714.1  317.38  4752.9  314.92
    4768  314.66  4794.7  312.36  4795.1  311.86  4799.6  311.86    4800  312.36
  4812.9  313.72  4819.5  313.38  4869.6  314.95  4908.4  314.82  4952.8  313.49
    4975  314.51  4997.2  313.45  5004.2  313.49  5023.6  315.37  5053.9  317.81
  5074.1  320.24  5094.2  320.87  5124.5  322.71  5137.5  324.01  5216.2  333.67
#Mann= 6 ,-1 , 0
  4511.9     .17       0  4794.7     .12       0    4800     .17       0
  4908.4     .09       0  5023.6     .17       0  5137.5     .15       0
Bank Sta=4908.4,5023.6
XS Rating Curve= 0 ,0
Exp/Cntr=0.3,0.1

Type RM Length L Ch R = 1 ,5026    ,611,611,611
BEGIN DESCRIPTION:
ALLIGATOR BRANCH 10.0
END DESCRIPTION:
XS GIS Cut Line= 3
      3806846.39     10229408.49      3806674.02     10229747.71
      3806421.58      10230049.3
#Sta/Elev= 30
  4619.5  332.63  4672.2  326.99  4678.5  325.55  4702.6  322.35  4768.2  314.63
  4813.1  310.74  4841.8  310.35  4842.2  309.85  4846.9  309.85  4847.4  310.35
  4866.8  312.28    4917  312.61  4947.7  313.92  5006.4  312.61  5042.8   313.4
  5056.5  311.96  5070.1  312.23  5077.9  313.24  5113.1  312.92  5141.7  314.52
    5213  315.65  5234.1  317.78  5262.7  319.25  5291.3  321.71  5312.1  324.14
  5318.7  326.47  5336.7  326.68  5361.6  329.45  5390.2  331.41  5393.3  332.73
#Mann= 5 ,-1 , 0
  4619.5     .17       0  4702.6     .15       0  4947.7     .09       0
  5042.8     .15       0  5336.7     .17       0
Bank Sta=4947.7,5042.8
XS Rating Curve= 0 ,0
Exp/Cntr=0.3,0.1

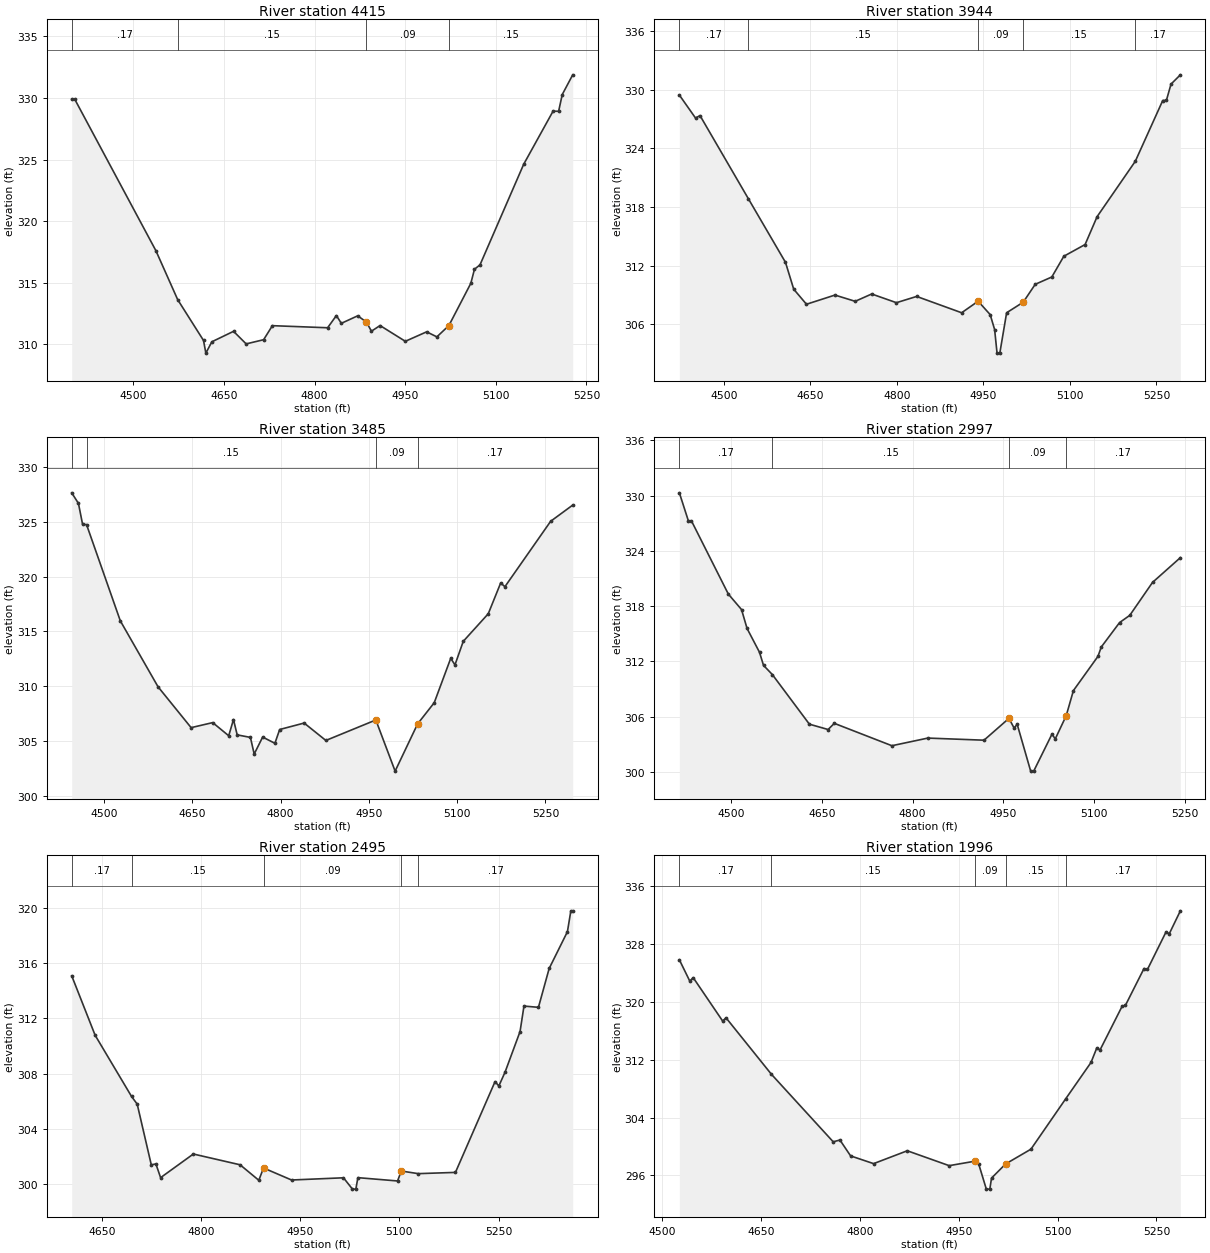
Type RM Length L Ch R = 1 ,4415    ,471,471,471
BEGIN DESCRIPTION:
ALLIGATOR BRANCH 9.0
END DESCRIPTION:
XS GIS Cut Line= 3
      3806671.07     10229169.26      3806195.54     10229538.09
      3806072.55     10229729.24
#Sta/Elev= 30
  4398.2  329.88  4403.4  329.88  4537.5   317.6  4573.6  313.62  4616.3  310.31
  4620.2  309.28  4630.1   310.2    4666  311.05  4686.9  310.03  4715.8  310.37
  4730.3  311.51  4821.7  311.34  4836.2  312.33  4844.4   311.7  4871.5  312.31
    4886   311.8  4894.2  311.06  4908.5  311.52  4950.3  310.24  4985.6  311.01
  5002.5   310.6  5022.4  311.52  5058.7  314.95  5064.7  316.09  5073.9  316.45
  5146.2  324.62  5194.8  328.93    5204  328.92    5210  330.28  5227.3  331.88
#Mann= 4 ,-1 , 0
  4398.2     .17       0  4573.6     .15       0    4886     .09       0
  5022.4     .15       0
Bank Sta=4886,5022.4
XS Rating Curve= 0 ,0
Exp/Cntr=0.3,0.1

Type RM Length L Ch R = 1 ,3944    ,459,459,459
BEGIN DESCRIPTION:
ALLIGATOR BRANCH 8.0
END DESCRIPTION:
XS GIS Cut Line= 3
      3806317.87     10228761.04      3805945.28     10229202.01
      3805763.94     10229430.23
#Sta/Elev= 30
  4422.7  329.45  4450.7   327.1  4458.5  327.35  4542.2  318.86  4606.7  312.34
    4621  309.59  4643.1  308.05  4692.5  308.99  4727.6  308.35  4756.2   309.1
  4799.1  308.21  4834.2  308.85  4912.2  307.18  4940.8  308.36  4961.7  306.99
  4969.4  305.46  4973.6  303.05  4978.4  303.05  4990.2  307.18    5019  308.26
  5039.8  310.09  5068.6  310.84  5089.4  312.96  5126.3  314.16  5147.1  317.01
  5213.4  322.68  5260.9  328.89  5267.3  328.91  5275.3  330.57  5291.5  331.52
#Mann= 5 ,-1 , 0
  4422.7     .17       0  4542.2     .15       0  4940.8     .09       0
    5019     .15       0  5213.4     .17       0
Bank Sta=4940.8,5019
XS Rating Curve= 0 ,0
Exp/Cntr=0.3,0.1

Type RM Length L Ch R = 1 ,3485    ,488,488,488
BEGIN DESCRIPTION:
ALLIGATOR BRANCH 7.0
END DESCRIPTION:
XS GIS Cut Line= 3
       3806106.8     10228514.15      3805672.02     10228859.11
      3805458.13      10229064.3
#Sta/Elev= 30
    4445  327.65  4456.4  326.69  4463.5  324.77  4470.2  324.75  4527.6  315.96
  4591.7  309.94  4647.9  306.21  4684.6  306.67  4711.8  305.47  4719.9  306.95
  4726.2  305.55  4748.7  305.32  4755.1   303.8  4769.5  305.35  4790.3  304.78
  4798.4  306.04    4840  306.63  4876.9  305.04  4961.8  306.91  4994.6  302.24
  5032.8  306.55  5061.1  308.49  5089.1  312.54  5096.3  311.94  5110.4  314.09
  5152.9  316.61    5174  319.42  5181.2  319.08  5258.9  325.05  5296.4  326.53
#Mann= 4 ,-1 , 0
    4445     .17       0  4470.2     .15       0  4961.8     .09       0
  5032.8     .17       0
Bank Sta=4961.8,5032.8
XS Rating Curve= 0 ,0
Exp/Cntr=0.3,0.1

Type RM Length L Ch R = 1 ,2997    ,502,502,502
BEGIN DESCRIPTION:
ALLIGATOR BRANCH 6.0
END DESCRIPTION:
XS GIS Cut Line= 3
      3806086.35      10228272.3      3805518.22     10228413.05
      3805295.63     10228509.01
#Sta/Elev= 30
  4414.7  330.31  4429.5  327.28  4434.6  327.27  4495.6  319.31  4517.4  317.63
  4526.5  315.58  4547.1  312.99  4553.7  311.57  4568.3  310.57  4629.5  305.18
  4660.4   304.6  4670.7  305.27  4765.8  302.84  4825.2  303.67    4918  303.44
  4959.2  305.81  4967.7  304.76  4972.8  305.17  4995.1  300.08  5000.1  300.08
  5030.3   304.1  5035.7  303.58  5053.8   306.1  5065.7  308.83  5106.3  312.55
  5111.7  313.56    5142  316.22  5158.8     317  5196.4  320.58  5242.4  323.27
#Mann= 4 ,-1 , 0
  4414.7     .17       0  4568.3     .15       0  4959.2     .09       0
  5053.8     .17       0
Bank Sta=4959.2,5053.8
XS Rating Curve= 0 ,0
Exp/Cntr=0.3,0.1

Type RM Length L Ch R = 1 ,2495    ,499,499,499
BEGIN DESCRIPTION:
ALLIGATOR BRANCH 5.0
END DESCRIPTION:
XS GIS Cut Line= 3
      3805767.88     10227711.04      3805486.31     10227988.64
      3805167.89     10228161.05
#Sta/Elev= 30
  4604.6  315.07    4640  310.77  4695.1  306.34  4703.6  305.79  4724.9   301.4
  4731.9  301.46    4739  300.47  4788.5  302.18  4859.2   301.4  4887.5  300.28
  4894.6  301.17    4937   300.3  5015.5  300.46  5029.1  299.64  5034.2  299.64
  5037.3  300.47  5097.3  300.23  5102.9  300.95  5128.5  300.76  5184.8  300.85
  5244.7  307.42  5250.4   307.1  5259.8   308.1  5282.5  311.04  5288.4  312.88
  5310.3  312.79  5326.5   315.6  5354.1  318.26  5359.3  319.77  5362.1  319.77
#Mann= 5 ,-1 , 0
  4604.6     .17       0  4695.1     .15       0  4894.6     .09       0
  5102.9     .15       0  5128.5     .17       0
Bank Sta=4894.6,5102.9
XS Rating Curve= 0 ,0
Exp/Cntr=0.3,0.1

Type RM Length L Ch R = 1 ,1996    ,499,499,499
BEGIN DESCRIPTION:
ALLIGATOR BRANCH 4.0
END DESCRIPTION:
XS GIS Cut Line= 3
      3805706.33     10227482.38      3805242.47     10227579.94
      3804967.81     10227661.08
#Sta/Elev= 30
    4526  325.85  4541.8   322.9    4547  323.38  4591.7  317.37  4596.8  317.82
  4665.8  309.99  4759.5  300.65  4769.7   300.9  4785.9   298.7  4820.8  297.63
  4871.9  299.41  4935.5  297.35  4974.1  297.96  4980.2  297.61  4991.9   294.1
  4997.2   294.1  4999.8  295.63  5021.1  297.58  5059.6  299.63  5112.1  306.57
  5150.8  311.64  5159.4  313.61  5164.6  313.39  5197.9   319.4  5203.1  319.56
  5231.2  324.64  5236.4  324.51  5264.5  329.68  5269.7  329.48  5286.4  332.63
#Mann= 5 ,-1 , 0
    4526     .17       0  4665.8     .15       0  4974.1     .09       0
  5021.1     .15       0  5112.1     .17       0
Bank Sta=4974.1,5021.1
XS Rating Curve= 0 ,0
Exp/Cntr=0.3,0.1

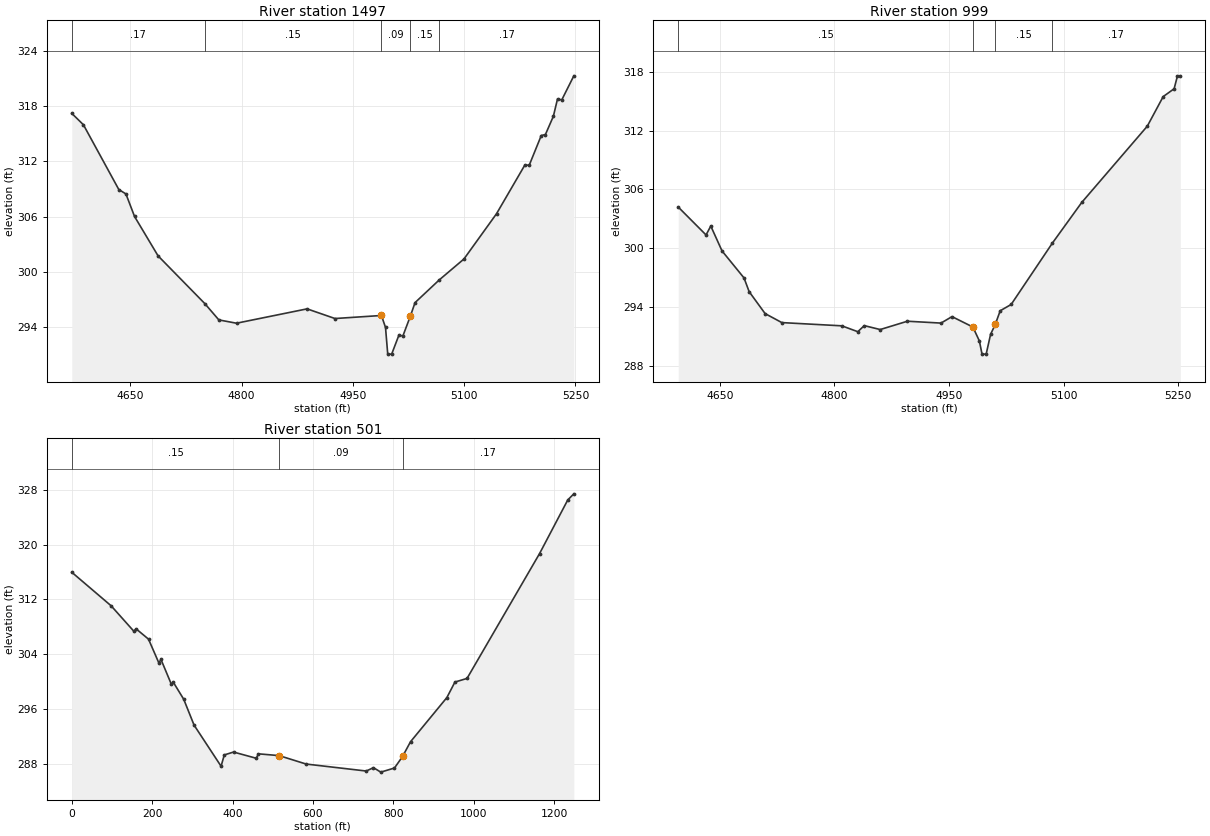
Type RM Length L Ch R = 1 ,1497    ,498,498,498
BEGIN DESCRIPTION:
ALLIGATOR BRANCH 3.0
END DESCRIPTION:
XS GIS Cut Line= 3
      3805617.87     10226961.07      3805212.16     10227099.88
      3804993.46     10227216.39
#Sta/Elev= 30
  4571.2  317.23  4586.9  315.99  4634.6  308.95  4644.2  308.47  4655.8  306.02
  4687.5  301.74  4750.4  296.56  4769.4  294.78  4793.2  294.42  4888.3  295.98
  4925.9  294.93  4988.5  295.26    4994  293.96    4997  291.06  5002.3  291.06
  5011.9  293.09  5017.5  293.05  5027.5  295.19  5033.8  296.66  5066.6  299.14
  5099.7   301.4  5143.6  306.32  5181.9  311.63  5187.6  311.58  5203.9  314.82
  5209.5  314.93  5220.2  316.91  5225.8   318.8  5231.5  318.69  5247.8  321.31
#Mann= 5 ,-1 , 0
  4571.2     .17       0  4750.4     .15       0  4988.5     .09       0
  5027.5     .15       0  5066.6     .17       0
Bank Sta=4988.5,5027.5
XS Rating Curve= 0 ,0
Exp/Cntr=0.3,0.1

Type RM Length L Ch R = 1 ,999     ,761,761,761
BEGIN DESCRIPTION:
ALLIGATOR BRANCH 2.0
END DESCRIPTION:
XS GIS Cut Line= 3
      3805337.46     10226441.14      3805010.66     10226679.17
      3804848.02     10226872.71
#Sta/Elev= 30
  4595.7   304.2  4632.1  301.35  4638.3  302.26    4653  299.72  4681.8  296.96
  4688.5  295.56  4709.4  293.32  4731.3   292.4  4809.8  292.07  4830.7  291.47
  4839.2  292.09    4860  291.69  4895.6  292.54  4939.6  292.35    4954  293.01
  4981.3  291.95  4989.8  290.53  4993.3  289.18  4998.7  289.18  5004.5   291.2
  5010.6  292.21  5017.1  293.61  5031.4  294.25  5085.3  300.51  5123.8  304.67
  5209.6  312.46  5230.4  315.48  5244.7  316.28  5249.1   317.6  5252.8   317.6
#Mann= 4 ,-1 , 0
  4595.7     .15       0  4981.3     .09       0  5010.6     .15       0
  5085.3     .17       0
Bank Sta=4981.3,5010.6
XS Rating Curve= 0 ,0
Exp/Cntr=0.3,0.1

Type RM Length L Ch R = 1 ,501     ,0,0,0
XS GIS Cut Line= 3
      3805225.75     10225953.74      3804498.24     10226209.59
      3804464.47     10226686.14
#Sta/Elev= 30
       0  315.97      98  311.07   154.6  307.35   159.9  307.72   190.9  306.21
   216.6  302.74   221.9  303.25   247.5  299.66   252.8   299.9   278.5  297.44
   304.2  293.67   371.4  287.67   379.4  289.32   402.4  289.74     459  288.83
   464.3  289.48   515.7  289.22   582.9  287.99   732.5  286.97   750.4  287.46
   768.7  286.81   802.7  287.41   822.8  289.09   842.6  291.24   933.1  297.69
   953.1  299.95   983.2  300.48  1163.6  318.69  1233.8  326.52  1248.9  327.41
#Mann= 3 , 0 , 0
       0     .15       0   515.7     .09       0   822.8     .17       0
Bank Sta=515.7,822.8
XS Rating Curve= 0 ,0
Exp/Cntr=0.3,0.1

Chan Stop Cuts=-1
Use User Specified Reach Order=0
Composite Channel Slope=5