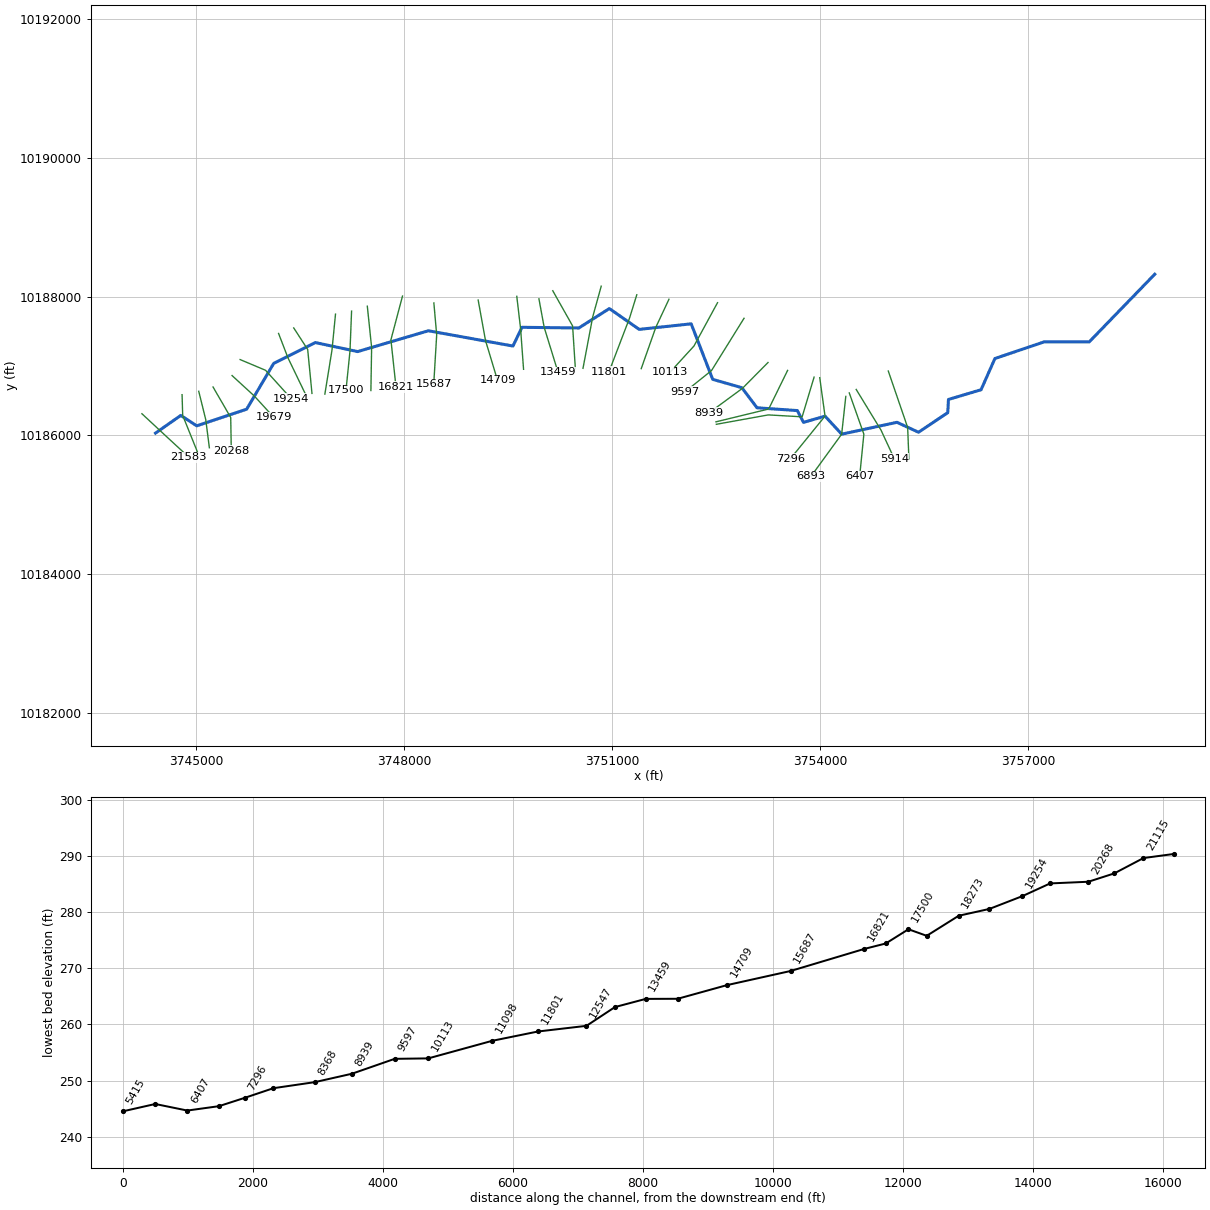
--- ANTHONY BRANCH.prj (project) ---

Proj Title=ANTHONY BRANCH Base Level Engineering
Current Plan=p01
Default Exp/Contr=0.3,0.1
English Units
Geom File=g01
Flow File=f01
Flow File=f02
Plan File=p01
Y Axis Title=Elevation
X Axis Title(PF)=Main Channel Distance
X Axis Title(XS)=Station
BEGIN DESCRIPTION:
ANTHONY BRANCH
END DESCRIPTION:
DSS Export Rating Curves= 0
DSS Export Rating Curve Sorted= 0
DSS Export Volume Flow Curves= 0
DXF OffsetX= 0
DXF OffsetY= 0
DXF ScaleX= 1
DXF ScaleY= 10

--- ANTHONY BRANCH.p01 (plan) ---

Plan Title=Multiple Run
Short Identifier=Multiple
Geom File=g01
Flow File=f01
Subcritical Flow
K Sum by GR= 0
Std Step Tol= 0.01
Critical Tol= 0.01
Num of Std Step Trials= 20
Max Error Tol= 0.3
Flow Tol Ratio= 0.001
Split Flow NTrial= 30
Split Flow Tol= 0.02
Split Flow Ratio= 0.02
Log Output Level= 0
Friction Slope Method= 1
Unsteady Friction Slope Method= 2
Unsteady Bridges Friction Slope Method= 1
Parabolic Critical Depth
Global Vel Dist=  1 , 1 , 1
Global Log Level= 0
CheckData=True
Encroach Param= -1, 0, 0, 0
BEGIN DESCRIPTION:
Multiple Run
END DESCRIPTION:

--- ANTHONY BRANCH.f01 (steady flow) ---

Flow Title=Multiple
Program Version=4.10
Number of Profiles= 7
Profile Names=10-year,25-year,50-year,1pct_min,100-year,1pct_plu,500-year
River Rch & RM=ANTHONY BRANCH,Reach-1         ,21583
     507     682     918     407    1229    3712    2276
River Rch & RM=ANTHONY BRANCH,Reach-1         ,20666
     740    1002    1352     600    1811    5469    3361
River Rch & RM=ANTHONY BRANCH,Reach-1         ,12985
     899    1226    1663     740    2235    6750    4176
River Rch & RM=ANTHONY BRANCH,Reach-1         ,7731
    1418    1982    2734    1235    3731   11267    7196
River Rch & RM=ANTHONY BRANCH,Reach-1         ,3133
    1442    2012    2773    1251    3778   11409    7265
Boundary for River Rch & Prof#=ANTHONY BRANCH,Reach-1         , 1
Up Type= 0
Dn Type= 3
Dn Slope=0.005
Boundary for River Rch & Prof#=ANTHONY BRANCH,Reach-1         , 2
Up Type= 0
Dn Type= 3
Dn Slope=0.005
Boundary for River Rch & Prof#=ANTHONY BRANCH,Reach-1         , 3
Up Type= 0
Dn Type= 3
Dn Slope=0.005
Boundary for River Rch & Prof#=ANTHONY BRANCH,Reach-1         , 4
Up Type= 0
Dn Type= 3
Dn Slope=0.005
Boundary for River Rch & Prof#=ANTHONY BRANCH,Reach-1         , 5
Up Type= 0
Dn Type= 3
Dn Slope=0.005
Boundary for River Rch & Prof#=ANTHONY BRANCH,Reach-1         , 6
Up Type= 0
Dn Type= 3
Dn Slope=0.005
Boundary for River Rch & Prof#=ANTHONY BRANCH,Reach-1         , 7
Up Type= 0
Dn Type= 3
Dn Slope=0.005
DSS Import GetInterval= 0
DSS Import GetPeak= 0
DSS Import FillOption= 0

--- ANTHONY BRANCH.f02 (steady flow) ---

Flow Title=Orig_BLE_Flow
Program Version=4.10
Number of Profiles= 7
Profile Names=10-year,25-year,50-year,1pct_min,100-year,1pct_plu,500-year
River Rch & RM=ANTHONY BRANCH,Reach-1         ,21583
     507     669     798     313     945    2854    1323
River Rch & RM=ANTHONY BRANCH,Reach-1         ,20666
     740     982    1176     461    1393    4208    1954
River Rch & RM=ANTHONY BRANCH,Reach-1         ,12985
     899    1202    1446     569    1719    5190    2428
River Rch & RM=ANTHONY BRANCH,Reach-1         ,7731
    1418    1943    2377     950    2870    8668    4184
River Rch & RM=ANTHONY BRANCH,Reach-1         ,3133
    1442    1973    2411     962    2906    8777    4224
Boundary for River Rch & Prof#=ANTHONY BRANCH,Reach-1         , 1
Up Type= 0
Dn Type= 3
Dn Slope=0.005
Boundary for River Rch & Prof#=ANTHONY BRANCH,Reach-1         , 2
Up Type= 0
Dn Type= 3
Dn Slope=0.005
Boundary for River Rch & Prof#=ANTHONY BRANCH,Reach-1         , 3
Up Type= 0
Dn Type= 3
Dn Slope=0.005
Boundary for River Rch & Prof#=ANTHONY BRANCH,Reach-1         , 4
Up Type= 0
Dn Type= 3
Dn Slope=0.005
Boundary for River Rch & Prof#=ANTHONY BRANCH,Reach-1         , 5
Up Type= 0
Dn Type= 3
Dn Slope=0.005
Boundary for River Rch & Prof#=ANTHONY BRANCH,Reach-1         , 6
Up Type= 0
Dn Type= 3
Dn Slope=0.005
Boundary for River Rch & Prof#=ANTHONY BRANCH,Reach-1         , 7
Up Type= 0
Dn Type= 3
Dn Slope=0.005
DSS Import GetInterval= 0
DSS Import GetPeak= 0
DSS Import FillOption= 0

--- ANTHONY BRANCH.g01 (geometry) ---

Geom Title=Existing Conditions
Program Version=4.10

River Reach=ANTHONY BRANCH  ,Reach-1
Reach XY= 30
      3744413.23     10186031.84      3744778.23     10186286.84
      3745008.23     10186136.84      3745728.23     10186376.84
      3746118.23     10187036.84      3746718.23     10187336.84
      3747328.23     10187206.84      3748348.23     10187506.84
      3749568.23     10187286.84      3749698.23     10187556.84
      3750518.23     10187546.84      3750958.23     10187826.84
      3751388.23     10187526.84      3752138.23     10187606.84
      3752448.23     10186806.84      3752868.23     10186686.84
      3753088.23     10186396.84      3753668.23     10186356.84
      3753758.23     10186186.84      3754068.23     10186276.84
      3754308.23     10186016.84        3755106.     10186187.66
      3755416.29     10186044.54      3755838.23     10186326.84
      3755848.23     10186516.84      3756318.23     10186656.84
      3756518.23     10187106.84      3757228.23     10187346.84
      3757878.23     10187346.84      3758823.29     10188321.78

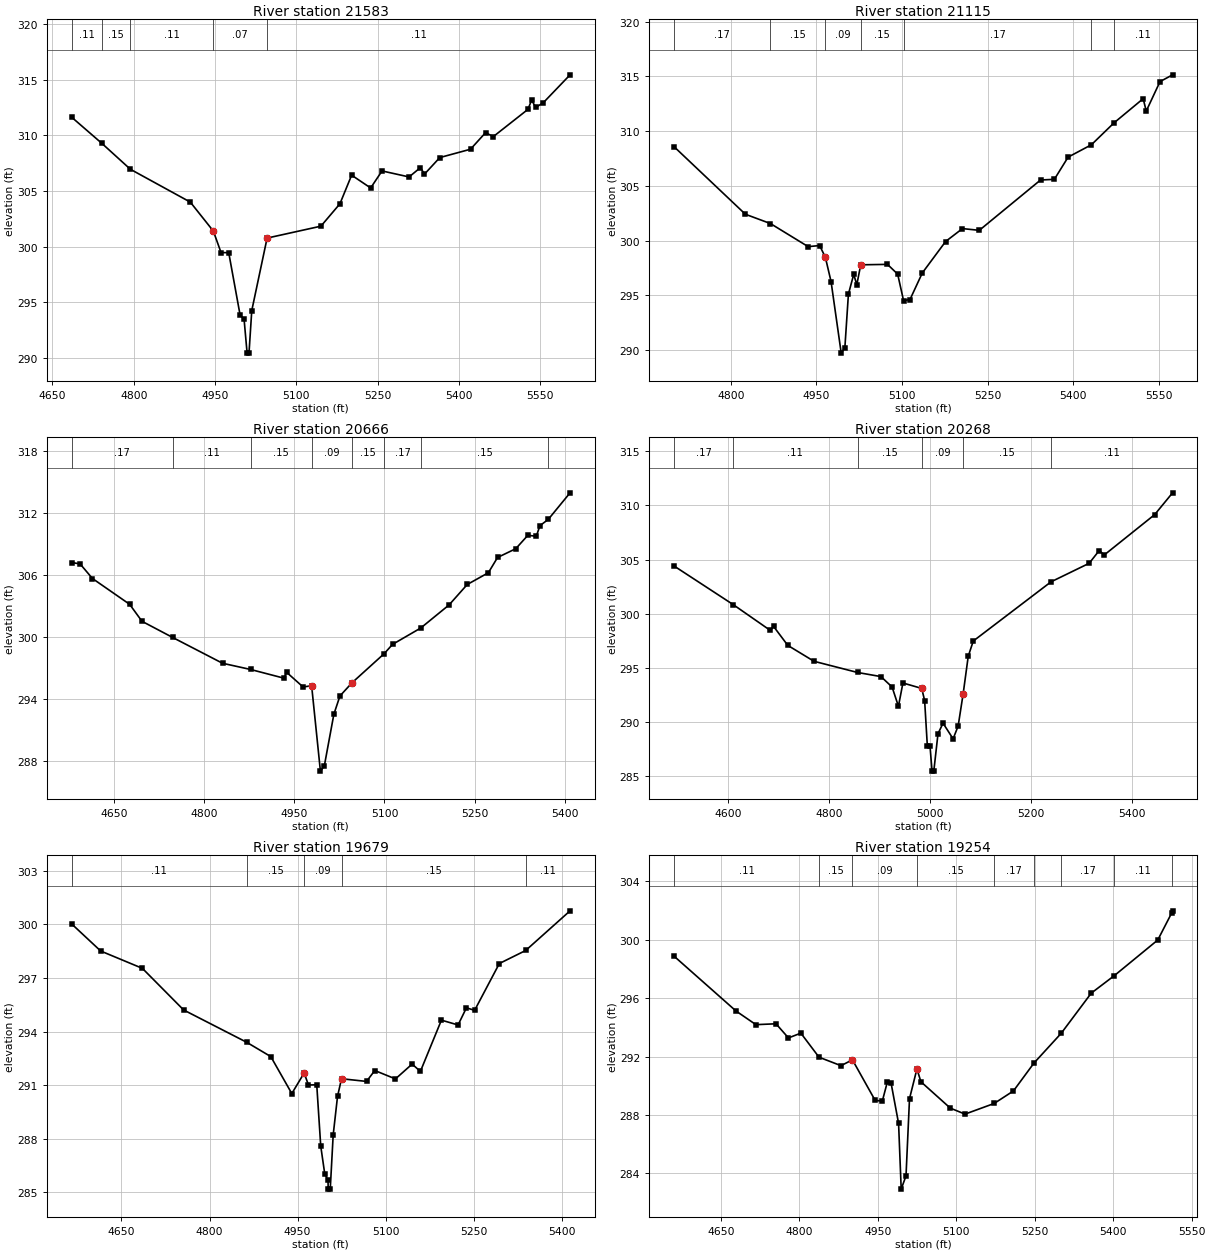
Type RM Length L Ch R = 1 ,21583   ,468,468,468
BEGIN DESCRIPTION:
ANTHONY BRANCH 41.0
END DESCRIPTION:
XS GIS Cut Line= 3
      3744217.84     10186311.08      3744448.23     10186096.84
      3744892.73     10185685.99
#Sta/Elev= 30
  4685.4  311.63  4741.4  309.27  4793.9  306.95  4904.5     304    4947   301.4
  4961.2  299.47  4975.4  299.46  4996.3  293.88  5003.7   293.5  5009.3  290.44
  5012.8  290.44  5017.9  294.26  5046.2  300.77  5145.5  301.84  5180.6  303.85
  5202.2  306.42  5237.3  305.27  5258.3   306.8  5308.2  306.26  5329.2   307.1
  5336.6  306.51  5364.9     308  5421.6  308.75  5449.4  310.24  5463.6  309.88
  5527.6  312.33  5534.4  313.17  5541.8   312.5    5556  312.93  5605.3  315.43
#Mann= 5 ,-1 , 0
  4685.4     .11       0  4741.4     .15       0  4793.9     .11       0
    4947     .07       0  5046.2     .11       0
Bank Sta=4947,5046.2
XS Rating Curve= 0 ,0
Exp/Cntr=0.3,0.1

Type RM Length L Ch R = 1 ,21115   ,449,449,449
BEGIN DESCRIPTION:
ANTHONY BRANCH 40.0
END DESCRIPTION:
XS GIS Cut Line= 3
      3744796.69     10186585.91      3744805.59     10186286.84
      3745020.65     10185754.55
#Sta/Elev= 30
  4700.8  308.57  4825.7   302.4  4869.6  301.55  4935.7  299.44  4955.8  299.54
  4965.8  298.47  4975.8  296.25  4993.6  289.71    5000  290.21  5006.2   295.1
  5015.5  296.91  5020.9  295.96  5027.8  297.78  5074.6  297.82  5092.5  296.93
  5102.8  294.51  5114.1  294.61  5135.7  297.04  5176.5  299.91    5206  301.09
  5235.5  300.93  5342.8  305.53    5367  305.59  5391.1  307.62  5431.9  308.75
  5471.5  310.75  5522.6  312.96    5528  311.83  5552.1  314.52  5574.1  315.14
#Mann= 7 ,-1 , 0
  4700.8     .17       0  4869.6     .15       0  4965.8     .09       0
  5027.8     .15       0  5102.8     .17       0  5431.9     .15       0
  5471.5     .11       0
Bank Sta=4965.8,5027.8
XS Rating Curve= 0 ,0
Exp/Cntr=0.3,0.1

Type RM Length L Ch R = 1 ,20666   ,398,398,398
BEGIN DESCRIPTION:
ANTHONY BRANCH 39.0
END DESCRIPTION:
XS GIS Cut Line= 3
      3745036.83     10186634.73      3745138.23     10186226.84
      3745190.15     10185821.46
#Sta/Elev= 30
  4579.7   307.2  4593.8  307.07  4614.4  305.65  4676.2  303.15  4696.8   301.5
  4747.9  299.93  4830.8  297.43  4877.3  296.83  4932.5  295.99  4937.6  296.54
  4964.7  295.13  4978.9  295.25  4993.5  286.97    5000  287.47  5015.9  292.49
    5026  294.26  5046.1  295.54  5099.7  298.37  5113.4  299.26  5160.4  300.85
  5207.5  303.09  5237.7  305.07  5272.8  306.21  5288.1  307.69  5318.4  308.54
  5338.5  309.84  5352.5  309.75  5358.7  310.78  5372.4  311.38  5408.7  313.96
#Mann= 8 ,-1 , 0
  4579.7     .17       0  4747.9     .11       0  4877.3     .15       0
  4978.9     .09       0  5046.1     .15       0  5099.7     .17       0
  5160.4     .15       0  5372.4     .11       0
Bank Sta=4978.9,5046.1
XS Rating Curve= 0 ,0
Exp/Cntr=0.3,0.1

Type RM Length L Ch R = 1 ,20268   ,589,589,589
BEGIN DESCRIPTION:
ANTHONY BRANCH 38.0
END DESCRIPTION:
XS GIS Cut Line= 3
      3745243.54     10186696.27      3745498.23     10186256.84
      3745506.48     10185775.62
#Sta/Elev= 30
  4492.1   304.4  4609.4  300.84    4683  298.46  4689.5  298.83  4717.7  297.08
  4769.8  295.61  4856.1  294.58  4902.6   294.2  4924.7  293.24  4937.3  291.46
  4946.2  293.61  4983.5  293.11  4989.3  291.99  4994.7  287.77    5000  287.77
    5004  285.48  5007.5  285.48  5015.8  288.93  5025.8   289.9  5045.8  288.46
  5055.8  289.64  5065.8  292.63  5075.8  296.07  5085.8  297.48  5240.1  302.94
  5315.8  304.65  5335.8  305.83  5345.8  305.42  5445.8  309.14  5481.3  311.15
#Mann= 6 ,-1 , 0
  4492.1     .17       0  4609.4     .11       0  4856.1     .15       0
  4983.5     .09       0  5065.8     .15       0  5240.1     .11       0
Bank Sta=4983.5,5065.8
XS Rating Curve= 0 ,0
Exp/Cntr=0.3,0.1

Type RM Length L Ch R = 1 ,19679   ,425,425,425
BEGIN DESCRIPTION:
ANTHONY BRANCH 37.0
END DESCRIPTION:
XS GIS Cut Line= 3
      3745517.84     10186861.08      3745838.23     10186566.84
      3746117.82     10186261.11
#Sta/Elev= 30
    4565  300.03  4614.6  298.51  4685.6  297.54  4755.9  295.21  4863.4   293.4
  4904.4   292.6  4940.2  290.53  4961.2  291.68  4968.6  291.01  4982.7  291.02
  4989.5  287.59  4996.3  286.04  5001.9  285.68  5002.2  285.18  5005.7  285.18
  5010.7  288.21  5018.1  290.37  5024.9  291.36  5067.5  291.21  5081.6  291.82
  5116.8  291.35  5145.2  292.18  5159.3  291.77  5195.1  294.64  5223.5  294.37
  5237.7  295.33  5251.7  295.19  5293.8  297.81  5338.7  298.54  5414.3  300.76
#Mann= 5 ,-1 , 0
    4565     .11       0  4863.4     .15       0  4961.2     .09       0
  5024.9     .15       0  5338.7     .11       0
Bank Sta=4961.2,5024.9
XS Rating Curve= 0 ,0
Exp/Cntr=0.3,0.1

Type RM Length L Ch R = 1 ,19254   ,508,508,508
BEGIN DESCRIPTION:
ANTHONY BRANCH 36.0
END DESCRIPTION:
XS GIS Cut Line= 3
      3745633.65      10187091.8      3746000.52     10186937.44
      3746372.95     10186526.25
#Sta/Elev= 30
  4560.7  298.88  4678.9  295.13  4717.1  294.19  4755.5  294.25  4779.3  293.28
    4803  293.61  4837.7  291.96  4879.7  291.38  4901.6  291.78    4945     289
  4958.7  288.95  4968.1  290.23  4975.6  290.16  4989.8  287.42  4994.8  282.92
    5004  283.83  5010.7  289.12  5024.9  291.16  5032.4  290.28  5088.7  288.47
  5116.8  288.06  5172.5  288.79  5209.4  289.65  5248.6  291.56  5300.7   293.6
  5358.1  296.35  5402.2  297.55  5485.2  299.99  5511.5  301.82  5513.5  301.99
#Mann= 9 ,-1 , 0
  4560.7     .11       0  4837.7     .15       0  4901.6     .09       0
  5024.9     .15       0  5172.5     .17       0  5248.6     .11       0
  5300.7     .17       0  5402.2     .11       0  5511.5     .17       0
#XS Ineff= 2 , 0
       0                  5024.9       0  291.16
Permanent Ineff=
       F       F
Bank Sta=4901.6,5024.9
XS Rating Curve= 0 ,0
Exp/Cntr=0.3,0.1

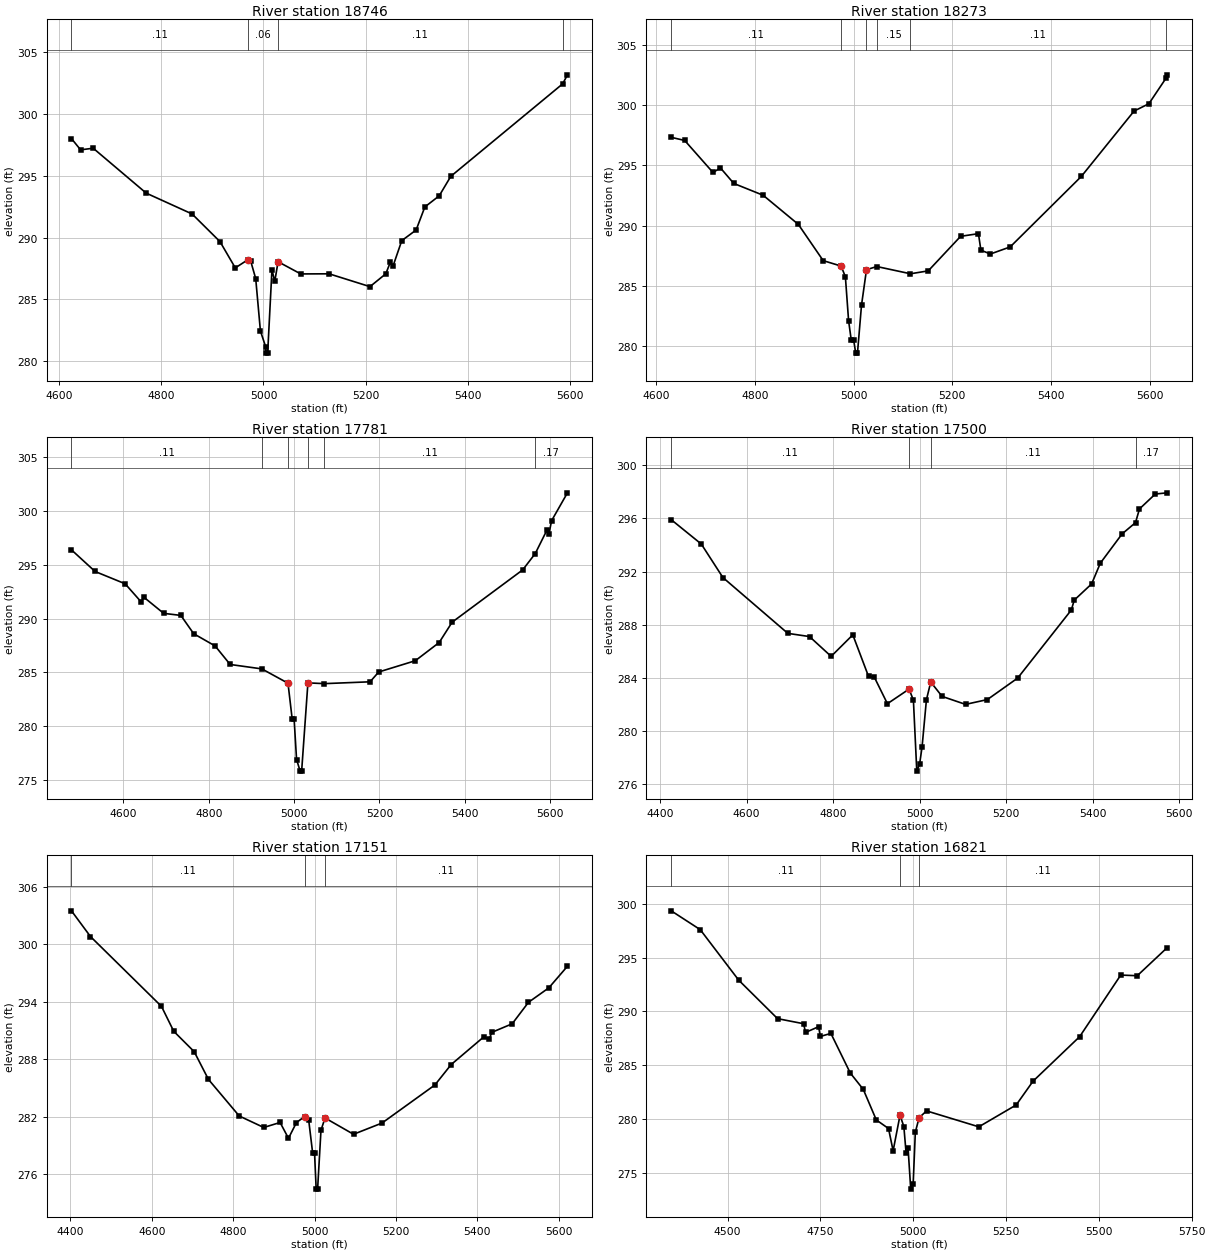
Type RM Length L Ch R = 1 ,18746   ,473,473,473
BEGIN DESCRIPTION:
ANTHONY BRANCH 35.0
END DESCRIPTION:
XS GIS Cut Line= 3
      3746188.31     10187467.76      3746323.62     10187116.84
      3746582.32     10186580.58
#Sta/Elev= 30
  4623.9  298.02  4641.8  297.11  4666.5  297.24  4770.3   293.6  4860.2  291.91
  4914.8  289.67  4944.8  287.54  4969.4   288.2  4974.7  288.13  4984.8  286.67
    4994  282.43  5004.4  281.13  5004.7  280.63  5008.2  280.63  5016.6  287.39
  5022.1  286.44  5028.6  288.04    5073  287.05  5128.5  287.06  5208.6  286.02
  5239.6  287.06  5248.3  287.98  5253.8  287.69  5270.9  289.75    5299  290.61
  5316.1  292.48  5344.2  293.38  5366.9  294.96  5586.1  302.46  5595.4  303.19
#Mann= 4 ,-1 , 0
  4623.9     .11       0  4969.4     .06       0  5028.6     .11       0
  5586.1     .17       0
Bank Sta=4969.4,5028.6
XS Rating Curve= 0 ,0
Exp/Cntr=0.3,0.1

Type RM Length L Ch R = 1 ,18273   ,492,492,492
BEGIN DESCRIPTION:
ANTHONY BRANCH 34.0
END DESCRIPTION:
XS GIS Cut Line= 3
      3746407.08     10187547.51      3746608.23     10187236.84
       3746669.9     10186604.14
#Sta/Elev= 30
  4629.9  297.33  4657.2  297.07  4714.6  294.41  4729.7  294.79  4756.8   293.5
  4816.3  292.52  4887.7   290.1  4938.1  287.09  4974.4  286.64  4983.1  285.75
  4989.6   282.1  4995.1  280.46    5000  280.46  5004.1  279.41  5007.6  279.41
  5015.8   283.4  5025.9  286.34  5046.9   286.6  5115.1     286  5151.1  286.24
  5216.8  289.11  5252.9  289.33  5257.9  287.96  5277.1  287.64  5317.3  288.23
  5461.5  294.08  5568.5  299.51  5598.6  300.12  5633.1  302.23  5635.7  302.52
#Mann= 6 ,-1 , 0
  4629.9     .11       0  4974.4     .06       0  5025.9     .11       0
  5046.9     .15       0  5115.1     .11       0  5633.1     .17       0
Bank Sta=4974.4,5025.9
XS Rating Curve= 0 ,0
Exp/Cntr=0.3,0.1

Type RM Length L Ch R = 1 ,17781   ,281,281,281
BEGIN DESCRIPTION:
ANTHONY BRANCH 33.0
END DESCRIPTION:
XS GIS Cut Line= 3
      3747009.17     10187746.25      3746958.23     10187226.84
       3746855.8     10186594.28
#Sta/Elev= 30
  4478.1  296.39  4533.5  294.38  4603.9  293.24  4642.2  291.52  4647.2  292.01
  4694.3  290.49  4734.5   290.3  4764.6   288.6  4814.9  287.46  4850.1  285.74
  4924.4  285.33  4985.7     284  4995.4  280.71    5000  280.71  5005.8  276.91
  5014.2  275.83  5017.7  275.83  5032.4  284.03  5071.2  283.96  5178.1  284.13
  5198.3  285.04  5284.2  286.09  5340.1  287.78  5370.5  289.67  5535.9  294.53
  5565.4  296.05  5592.5  298.21  5597.6  297.88  5603.5  299.09  5640.8  301.69
#Mann= 6 ,-1 , 0
  4478.1     .11       0  4924.4     .15       0  4985.7     .09       0
  5032.4     .15       0  5071.2     .11       0  5565.4     .17       0
Bank Sta=4985.7,5032.4
XS Rating Curve= 0 ,0
Exp/Cntr=0.3,0.1

Type RM Length L Ch R = 1 ,17500   ,349,349,349
BEGIN DESCRIPTION:
ANTHONY BRANCH 34.5
END DESCRIPTION:
XS GIS Cut Line= 3
      3747240.94      10187790.5      3747218.23     10187216.84
      3747160.21     10186647.29
#Sta/Elev= 30
  4425.9  295.91  4495.4  294.08  4545.4  291.56  4695.5  287.36  4745.6  287.12
  4795.6  285.63  4845.7  287.25    4882  284.13  4895.7  284.05  4925.7  282.07
  4975.8  283.17  4985.8  282.33  4993.6     277    5000   277.5  5005.8  278.82
  5015.9  282.37  5025.9   283.7  5052.1  282.62  5106.3  282.02  5156.7  282.38
  5226.9     284  5350.9  289.12  5357.6  289.86  5397.8  291.08  5417.9  292.64
  5468.2  294.84  5499.3  295.69  5508.4  296.72    5545  297.84  5572.5  297.93
#Mann= 4 ,-1 , 0
  4425.9     .11       0  4975.8     .06       0  5025.9     .11       0
  5499.3     .17       0
Bank Sta=4975.8,5025.9
XS Rating Curve= 0 ,0
Exp/Cntr=0.3,0.1

Type RM Length L Ch R = 1 ,17151   ,330,330,330
BEGIN DESCRIPTION:
ANTHONY BRANCH 32.0
END DESCRIPTION:
XS GIS Cut Line= 3
      3747467.85      10187861.1        3747530.     10187266.84
       3747519.6     10186645.33
#Sta/Elev= 30
  4402.5  303.48  4449.2   300.8  4623.7  293.52  4653.9  290.92  4704.2  288.79
  4739.2   285.9  4814.8  282.09  4875.1  280.89  4915.3  281.41  4935.9  279.76
  4955.5   281.4  4975.6  282.03  4985.7  281.63  4995.4   278.2    5000   278.2
    5004  274.46  5007.5  274.46  5015.8   280.6  5025.8  281.88  5095.8  280.18
  5165.8  281.35  5295.8  285.32  5335.8  287.45  5415.8  290.33    5429  290.08
  5435.8  290.81  5485.8   291.7  5525.8  293.94  5575.9  295.45  5621.6   297.7
#Mann= 3 , 0 , 0
  4402.5     .11       0  4975.6     .06       0  5025.8     .11       0
Bank Sta=4975.6,5025.8
XS Rating Curve= 0 ,0
Exp/Cntr=0.3,0.1

Type RM Length L Ch R = 1 ,16821   ,1134,1134,1134
BEGIN DESCRIPTION:
ANTHONY BRANCH 31.0
END DESCRIPTION:
XS GIS Cut Line= 3
      3747975.32     10188006.66      3747808.23     10187376.84
      3747881.57     10186696.69
#Sta/Elev= 30
  4348.4  299.35  4426.6   297.6  4530.1  292.91  4634.8  289.33  4704.9  288.86
  4710.1  288.05  4745.1  288.58  4750.2  287.68  4778.4  287.96  4830.6  284.28
  4865.6  282.76  4900.7  279.92  4933.6  279.12    4946  277.05  4964.6  280.36
  4974.9   279.3    4981  276.82  4986.2  277.34  4993.4  273.49    5000  273.99
  5005.8  278.78  5015.9  280.12    5036  280.76  5176.8  279.28  5277.4  281.31
  5322.8  283.52  5448.4  287.66    5559  293.38  5603.5  293.32  5684.1  295.93
#Mann= 3 , 0 , 0
  4348.4     .11       0  4964.6     .06       0  5015.9     .11       0
#XS Ineff= 2 , 0
       0                    5036       0  280.76
Permanent Ineff=
       F       T
Bank Sta=4964.6,5015.9
XS Rating Curve= 0 ,0
Exp/Cntr=0.3,0.1

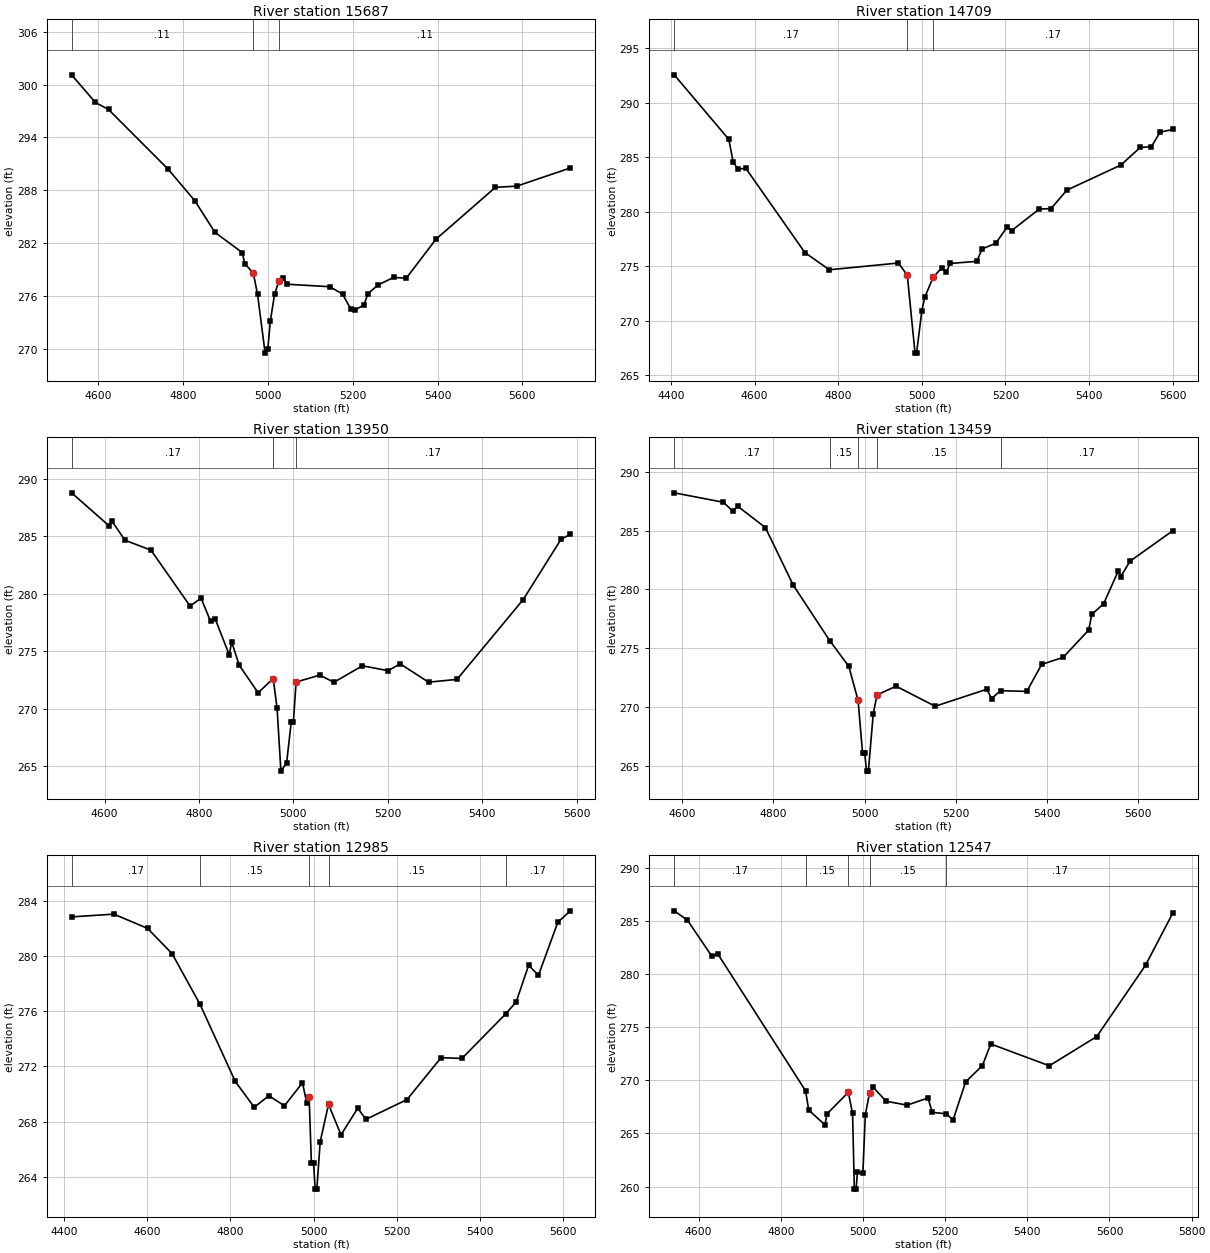
Type RM Length L Ch R = 1 ,15687   ,978,978,978
BEGIN DESCRIPTION:
ANTHONY BRANCH 30.0
END DESCRIPTION:
XS GIS Cut Line= 3
      3748427.57     10187907.75      3748468.23     10187446.84
      3748425.64     10186735.02
#Sta/Elev= 30
  4537.3   301.1  4593.3  297.97  4624.3  297.17  4764.9   290.4  4827.6  286.84
  4875.3  283.24  4939.7  280.95  4945.6  279.68  4965.6  278.65  4975.7  276.21
  4993.6  269.55    5000  270.05  5005.8  273.16  5015.8   276.2  5025.8   277.7
  5035.8  278.09  5045.9  277.36    5146  277.08  5176.1  276.25  5196.1   274.5
  5206.1  274.47  5226.2  274.99  5236.2  276.29  5259.4  277.27  5296.3  278.13
  5326.4  278.05  5396.5  282.47  5536.7  288.35  5586.8  288.48  5713.1  290.54
#Mann= 3 , 0 , 0
  4537.3     .11       0  4965.6     .06       0  5025.8     .11       0
Bank Sta=4965.6,5025.8
XS Rating Curve= 0 ,0
Exp/Cntr=0.3,0.1

Type RM Length L Ch R = 1 ,14709   ,759,759,759
BEGIN DESCRIPTION:
ANTHONY BRANCH 27.0
END DESCRIPTION:
XS GIS Cut Line= 3
      3749066.34     10187949.62      3749172.13     10187366.84
      3749345.79      10186791.9
#Sta/Elev= 30
  4407.7  292.54  4538.4  286.62  4548.5  284.57    4560   283.9    4579  283.97
  4720.2  276.25  4778.7  274.67  4943.9  275.29  4965.2  274.18  4983.7  267.03
  4987.4  267.03    5000  270.91  5006.9  272.14  5026.9  273.97  5047.8  274.86
  5058.3  274.43  5067.6  275.25  5131.4  275.44    5144  276.58  5176.9   277.1
  5204.5  278.62  5215.1  278.27    5281  280.24  5308.8  280.27  5346.9  281.97
  5476.1  284.27  5522.2  285.88  5549.2  285.96  5570.1  287.29  5600.6  287.53
#Mann= 3 , 0 , 0
  4407.7     .17       0  4965.2     .09       0  5026.9     .17       0
Bank Sta=4965.2,5026.9
XS Rating Curve= 0 ,0
Exp/Cntr=0.3,0.1

Type RM Length L Ch R = 1 ,13950   ,491,491,491
BEGIN DESCRIPTION:
ANTHONY BRANCH 26.0
END DESCRIPTION:
XS GIS Cut Line= 3
      3749623.25     10188003.52      3749678.23     10187536.84
      3749721.06     10186951.61
#Sta/Elev= 30
  4530.1  288.77  4610.1  285.88  4615.2  286.33  4643.3  284.65  4698.2  283.79
  4781.2  278.93  4804.4  279.62  4824.6   277.6  4834.6   277.8  4864.2  274.68
  4869.2  275.83    4885  273.81  4925.3   271.4  4957.3  272.63  4965.5  270.05
  4973.6  264.59  4985.7   265.3  4995.4  268.82    5000  268.82  5005.8  272.33
  5055.9  272.93    5086  272.31  5146.2  273.74  5200.8  273.32  5226.4  273.91
  5286.5  272.32  5346.7  272.56  5487.1   279.5  5567.3  284.74  5586.8  285.16
#Mann= 3 , 0 , 0
  4530.1     .17       0  4957.3     .09       0  5005.8     .17       0
Bank Sta=4957.3,5005.8
XS Rating Curve= 0 ,0
Exp/Cntr=0.3,0.1

Type RM Length L Ch R = 1 ,13459   ,474,474,474
BEGIN DESCRIPTION:
ANTHONY BRANCH 25.0
END DESCRIPTION:
XS GIS Cut Line= 3
      3749942.62     10187967.64      3750018.23     10187556.84
      3750217.84     10186911.09
#Sta/Elev= 30
  4582.3   288.2  4689.8   287.4    4711  286.64  4721.2  287.07  4782.2  285.25
  4843.2  280.37  4923.1  275.66  4965.2  273.46  4985.5  270.57  4995.3  266.11
    5000  266.11    5004  264.57  5008.1  264.57  5018.7  269.43    5027  271.04
  5068.8  271.78  5154.5  270.08  5267.7  271.52  5278.2  270.73  5297.9   271.4
  5355.5  271.34  5388.1  273.63  5435.2  274.23  5491.2  276.55    5498  277.88
  5523.9  278.78  5556.5   281.6  5561.7  281.09  5581.7  282.39  5675.9  284.99
#Mann= 5 ,-1 , 0
  4582.3     .17       0  4923.1     .15       0  4985.5     .09       0
    5027     .15       0  5297.9     .17       0
Bank Sta=4985.5,5027
XS Rating Curve= 0 ,0
Exp/Cntr=0.3,0.1

Type RM Length L Ch R = 1 ,12985   ,438,438,438
BEGIN DESCRIPTION:
ANTHONY BRANCH 24.0
END DESCRIPTION:
XS GIS Cut Line= 3
      3750142.24     10188083.39      3750428.23     10187576.84
      3750467.85     10186961.12
#Sta/Elev= 30
  4418.3  282.84  4519.9  283.04  4600.8  282.01    4660  280.17    4727   276.5
  4811.6  270.92  4857.3  269.04  4892.4  269.88    4930  269.15  4973.3  270.82
  4983.5  269.35  4989.2  269.82  4994.7     265    5000     265  5003.7  263.11
  5007.8  263.11  5015.8  266.54  5035.8  269.25  5065.9  267.05    5106  268.97
    5126  268.17  5224.5   269.6  5306.4  272.64  5356.5  272.58  5461.4   275.8
  5486.8  276.67  5516.8  279.33  5540.5  278.61    5587  282.45    5617  283.28
#Mann= 5 ,-1 , 0
  4418.3     .17       0    4727     .15       0  4989.2     .09       0
  5035.8     .15       0  5461.4     .17       0
Bank Sta=4989.2,5035.8
XS Rating Curve= 0 ,0
Exp/Cntr=0.3,0.1

Type RM Length L Ch R = 1 ,12547   ,746,746,746
BEGIN DESCRIPTION:
ANTHONY BRANCH 23.0
END DESCRIPTION:
XS GIS Cut Line= 3
      3750840.88     10188149.26      3750718.23     10187706.84
      3750578.15     10186965.56
#Sta/Elev= 30
  4540.9  285.93  4573.1  285.05  4632.4  281.66  4646.9  281.88  4860.5  269.01
  4868.2  267.19  4907.6   265.8  4912.8  266.84  4964.5  268.86  4974.9  266.89
  4979.2  259.76  4983.6  259.76  4986.6  261.33    5000  261.31  5005.9  266.74
  5016.1  268.81  5025.1  269.33  5056.8  268.02  5107.6  267.66  5158.5  268.33
  5168.7  266.98    5202  266.85  5219.6  266.28  5250.1  269.85  5290.8  271.38
  5311.2  273.41  5453.7  271.36  5569.1  274.11  5687.7  280.81  5754.4  285.74
#Mann= 5 ,-1 , 0
  4540.9     .17       0  4860.5     .15       0  4964.5     .09       0
  5016.1     .15       0    5202     .17       0
Bank Sta=4964.5,5016.1
XS Rating Curve= 0 ,0
Exp/Cntr=0.3,0.1

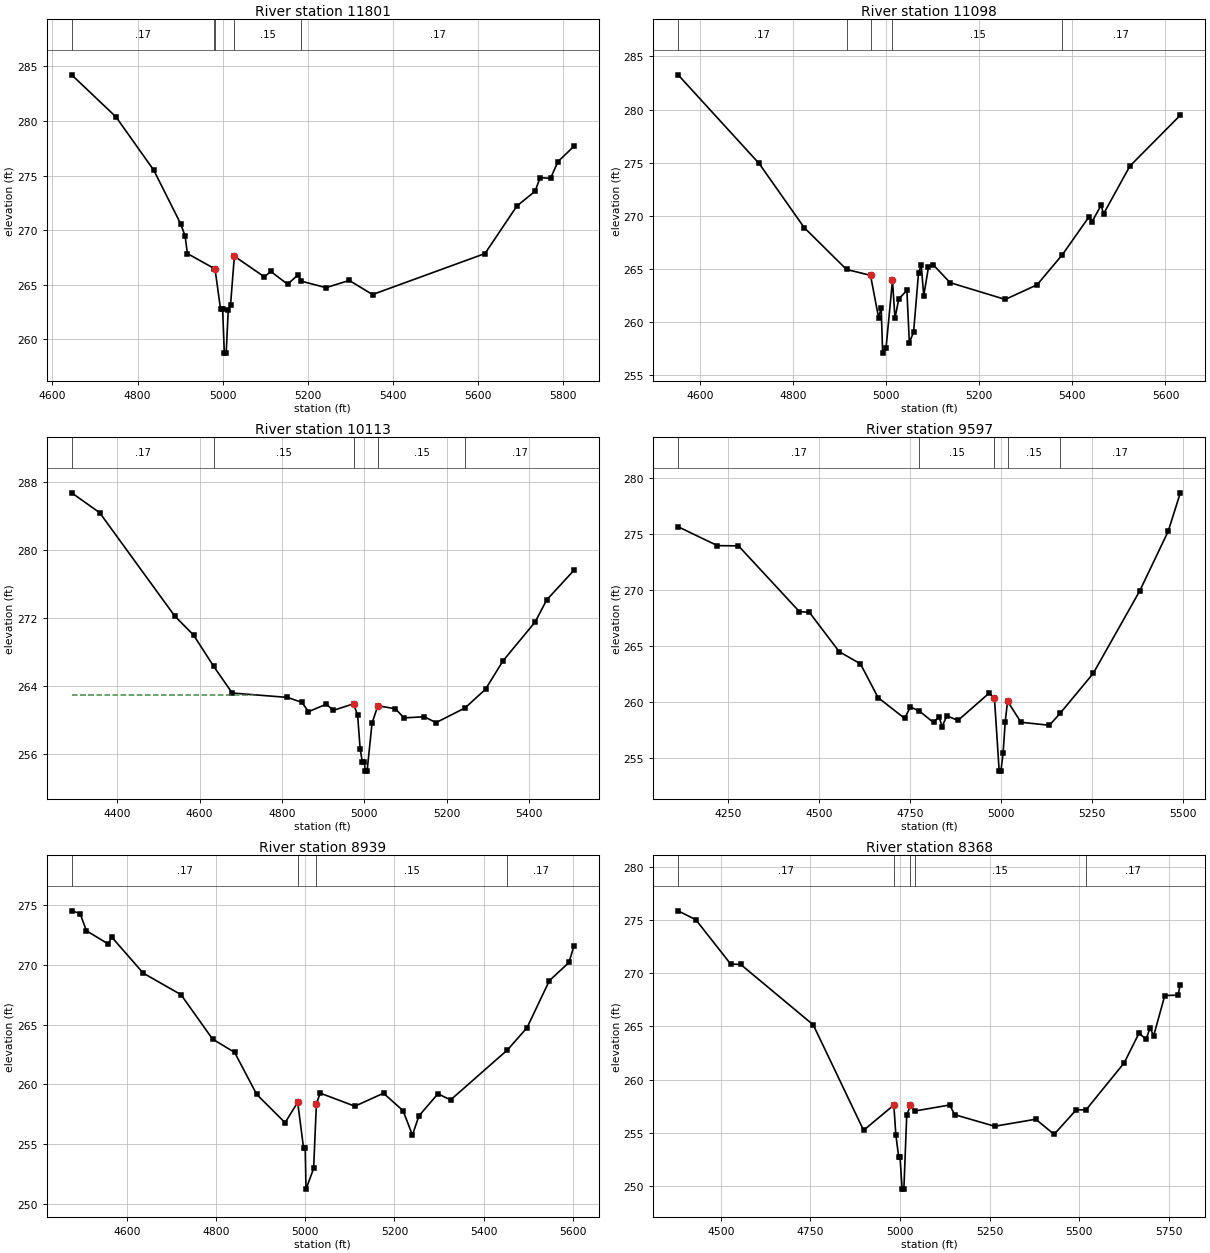
Type RM Length L Ch R = 1 ,11801   ,703,703,703
BEGIN DESCRIPTION:
ANTHONY BRANCH 22.0
END DESCRIPTION:
XS GIS Cut Line= 3
       3751353.9     10188025.54      3751248.23     10187686.84
      3750952.84     10186916.11
#Sta/Elev= 30
  4645.2  284.21  4749.4  280.36  4838.4  275.47  4901.3  270.59  4911.8  269.46
  4917.2  267.86  4980.8  266.48  4982.2  266.44  4995.2  262.75    5000  262.75
    5004  258.75  5008.4  258.75  5013.3  262.74  5018.6  263.16  5027.6  267.62
    5098  265.73  5113.3  266.22  5152.7  265.05  5177.4  265.92  5185.3  265.33
  5242.9  264.74  5297.6   265.4  5352.3  264.11  5616.6  267.86  5691.6  272.21
  5734.4  273.56    5746   274.8  5770.7  274.74    5788  276.27  5825.4  277.66
#Mann= 5 ,-1 , 0
  4645.2     .17       0  4980.8     .15       0  4982.2     .09       0
  5027.6     .15       0  5185.3     .17       0
#XS Ineff= 2 , 0
       0                  5027.6       0  267.62
Permanent Ineff=
       F       T
Bank Sta=4982.2,5027.6
XS Rating Curve= 0 ,0
Exp/Cntr=0.3,0.1

Type RM Length L Ch R = 1 ,11098   ,985,985,985
BEGIN DESCRIPTION:
ANTHONY BRANCH 20.0
END DESCRIPTION:
XS GIS Cut Line= 3
      3751817.85     10187961.08      3751628.23     10187556.84
      3751417.86      10186961.1
#Sta/Elev= 30
  4553.5  283.27  4727.4  274.93  4824.2   268.9  4915.1  264.96  4966.6  264.41
  4983.9  260.44  4989.5  261.35  4992.7  257.09    5000  257.59  5013.8  263.94
  5019.1  260.36  5027.3  262.19  5044.7  262.99    5050  258.07  5059.1  259.07
  5069.8  264.66  5075.6  265.34  5080.9  262.49    5091  265.16  5101.3   265.4
  5137.5  263.72  5255.9  262.14  5324.3  263.52  5378.6  266.35  5436.1  269.93
  5441.4  269.38  5461.7     271    5467  270.19  5523.6  274.69  5631.8  279.47
#Mann= 5 ,-1 , 0
  4553.5     .17       0  4915.1     .15       0  4966.6     .09       0
  5013.8     .15       0  5378.6     .17       0
Bank Sta=4966.6,5013.8
XS Rating Curve= 0 ,0
Exp/Cntr=0.3,0.1

Type RM Length L Ch R = 1 ,10113   ,516,516,516
BEGIN DESCRIPTION:
ANTHONY BRANCH 18.0
END DESCRIPTION:
XS GIS Cut Line= 3
      3752517.83     10187911.04      3752178.23     10187286.84
       3751834.6     10186911.61
#Sta/Elev= 30
  4289.4  286.67  4357.3  284.34  4539.8  272.18  4585.4  269.95  4634.4  266.26
  4679.3  263.13    4813  262.62  4848.4  262.04  4864.5  260.94  4908.2  261.83
  4924.4  261.09  4973.8  261.86  4983.8  260.52  4989.9  256.59  4995.2  255.03
    5000  255.03  5002.3  253.95  5006.8  253.95  5018.7  259.57  5032.9  261.64
  5075.4  261.28  5096.4  260.21  5145.7  260.34  5174.1  259.65    5245  261.39
  5294.3  263.58  5336.9  266.92  5414.6  271.47  5442.9  274.08  5508.8  277.55
#Mann= 5 ,-1 , 0
  4289.4     .17       0  4634.4     .15       0  4973.8     .09       0
  5032.9     .15       0    5245     .17       0
#XS Ineff= 2 , 0
       0  4739.1  262.91               0
Permanent Ineff=
       F       F
Bank Sta=4973.8,5032.9
XS Rating Curve= 0 ,0
Exp/Cntr=0.3,0.1

Type RM Length L Ch R = 1 ,9597    ,658,658,658
BEGIN DESCRIPTION:
ANTHONY BRANCH 17.0
END DESCRIPTION:
XS GIS Cut Line= 3
      3752900.39     10187687.08      3752431.55     10186933.52
      3752047.15     10186625.32
#Sta/Elev= 30
  4112.5  275.62  4220.5  273.94  4278.4  273.92    4446  268.06  4473.1  268.01
  4555.3   264.5  4613.6  263.42    4662  260.42  4735.2  258.56  4750.6  259.58
  4775.4  259.22  4814.4   258.2  4829.6  258.72    4838  257.82  4850.9   258.8
  4881.6  258.38  4967.6  260.82  4981.9  260.36  4994.9  253.87  4999.6  253.87
  5005.6  255.45  5011.5  258.26  5017.9  260.09  5054.7  258.22  5132.9  257.95
    5162     259  5253.2  262.56  5381.2  269.91  5459.6  275.23  5492.7  278.64
#Mann= 5 ,-1 , 0
  4112.5     .17       0  4775.4     .15       0  4981.9     .09       0
  5017.9     .15       0    5162     .17       0
Bank Sta=4981.9,5017.9
XS Rating Curve= 0 ,0
Exp/Cntr=0.3,0.1

Type RM Length L Ch R = 1 ,8939    ,571,571,571
BEGIN DESCRIPTION:
ANTHONY BRANCH 16.0
END DESCRIPTION:
XS GIS Cut Line= 3
      3753246.19      10187049.5      3752877.56     10186677.51
      3752392.21     10186321.03
#Sta/Elev= 30
  4476.3  274.54  4495.2  274.31  4509.4  272.87  4558.8  271.75  4565.9  272.35
  4636.7  269.32  4721.5  267.51  4792.2  263.79  4841.7  262.67  4891.2  259.15
  4954.8  256.78  4983.1  258.49  4996.2  254.66    5000  254.66  5001.7  251.21
  5018.8  252.94    5025  258.35  5033.4  259.26  5111.3  258.16  5175.5  259.25
  5219.4  257.78  5240.3  255.74  5254.9  257.35  5297.4   259.2  5325.9  258.69
  5453.4  262.88  5497.2  264.74  5547.4  268.69  5591.3  270.21  5602.2  271.56
#Mann= 4 ,-1 , 0
  4476.3     .17       0  4983.1     .09       0    5025     .15       0
  5453.4     .17       0
Bank Sta=4983.1,5025
XS Rating Curve= 0 ,0
Exp/Cntr=0.3,0.1

Type RM Length L Ch R = 1 ,8368    ,637,637,637
BEGIN DESCRIPTION:
ANTHONY BRANCH 14.0
END DESCRIPTION:
XS GIS Cut Line= 3
      3753528.48     10186935.54      3753255.79     10186379.29
      3752495.69     10186194.66
#Sta/Elev= 30
  4380.5  275.87    4430  275.03  4527.1  270.87  4555.2  270.83  4757.7  265.15
  4898.2  255.24  4982.6  257.61  4988.2  254.83  4996.2  252.71    5000  252.71
  5005.7  249.71  5010.6  249.71  5018.6  256.65  5028.7  257.58  5040.4  257.05
  5138.8  257.62  5152.2  256.71  5264.1  255.62  5378.6  256.28  5430.1  254.86
  5491.8  257.17    5519  257.16  5625.6  261.58  5666.8  264.36  5686.8   263.8
  5697.6  264.86  5707.9  264.13  5738.9  267.91  5775.5  267.94  5782.2  268.92
#Mann= 5 ,-1 , 0
  4380.5     .17       0  4982.6     .09       0  5028.7     .17       0
  5040.4     .15       0    5519     .17       0
Bank Sta=4982.6,5028.7
XS Rating Curve= 0 ,0
Exp/Cntr=0.3,0.1

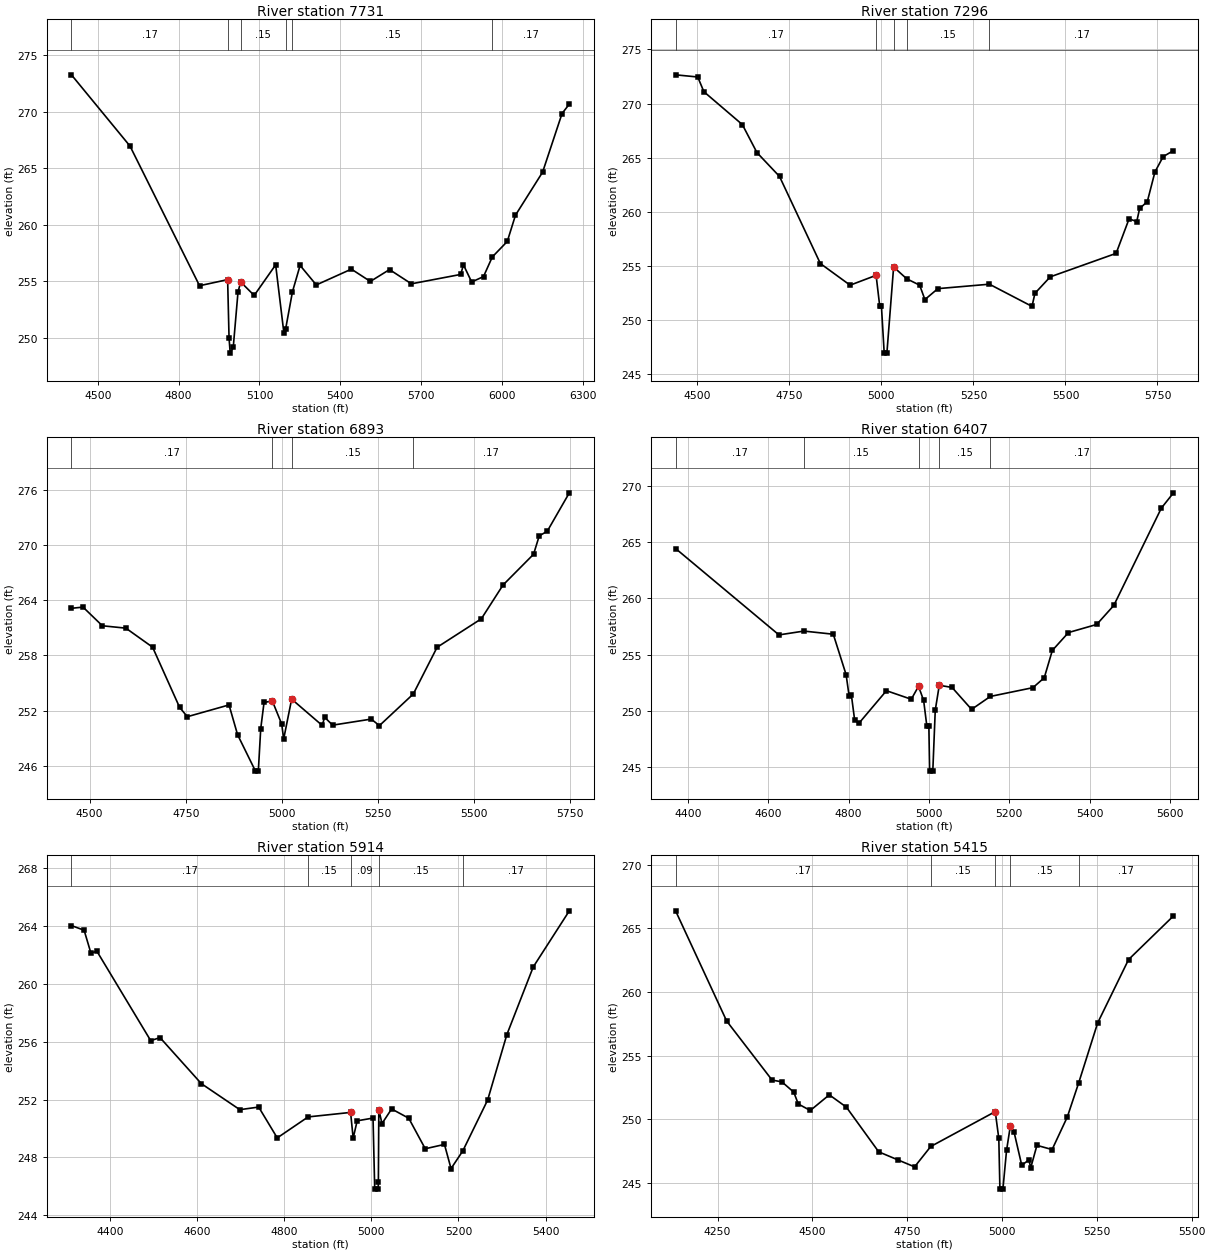
Type RM Length L Ch R = 1 ,7731    ,435,435,435
BEGIN DESCRIPTION:
ANTHONY BRANCH 13.0
END DESCRIPTION:
XS GIS Cut Line= 4
      3753910.61     10186839.15      3753738.23     10186266.84
      3753249.61     10186294.29       3752501.2     10186159.16
#Sta/Elev= 30
  4402.3  273.28  4619.6  266.97  4877.7   254.6  4981.9  255.14  4987.2  249.95
  4991.5  248.63  5002.7  249.13  5020.4  254.04  5030.4  254.93  5080.5  253.74
  5160.1  256.45  5190.7  250.41  5197.3  250.79  5222.5  254.07  5250.8   256.4
  5310.9  254.67  5441.1  256.07  5511.5  254.98  5582.6  256.03  5663.9  254.77
  5846.8   255.6    5857  256.45  5887.5  254.93  5931.4  255.41  5964.1  257.15
  6019.6  258.52  6050.1  260.85  6150.7  264.66  6222.8  269.85  6249.9  270.69
#Mann= 6 ,-1 , 0
  4402.3     .17       0  4981.9     .09       0  5030.4     .15       0
  5197.3     .17       0  5222.5     .15       0  5964.1     .17       0
Bank Sta=4981.9,5030.4
XS Rating Curve= 0 ,0
Exp/Cntr=0.3,0.1

Type RM Length L Ch R = 1 ,7296    ,403,403,403
BEGIN DESCRIPTION:
ANTHONY BRANCH 12.0
END DESCRIPTION:
XS GIS Cut Line= 3
      3753992.17     10186830.75      3754068.23     10186276.84
      3753567.88     10185661.11
#Sta/Elev= 30
  4440.9  272.65  4501.1  272.45  4517.8  271.09  4622.3  268.05    4662  265.46
  4723.2  263.26  4834.2  255.21    4915  253.21  4985.6  254.12  4995.3  251.32
    5000  251.32  5007.6  246.93  5014.9  246.93  5033.2  254.89  5068.8   253.8
  5103.9  253.21  5118.2  251.88  5153.4  252.89  5293.4   253.3  5409.1  251.25
  5417.1  252.46  5458.7  253.98  5637.6  256.15  5672.8  259.34  5693.6  259.09
  5701.5   260.3  5722.3  260.93  5743.1  263.68  5765.4  265.09  5793.4  265.65
#Mann= 5 ,-1 , 0
  4440.9     .17       0  4985.6     .09       0  5033.2     .17       0
  5068.8     .15       0  5293.4     .17       0
Bank Sta=4985.6,5033.2
XS Rating Curve= 0 ,0
Exp/Cntr=0.3,0.1

Type RM Length L Ch R = 1 ,6893    ,486,486,486
BEGIN DESCRIPTION:
ANTHONY BRANCH 11.0
END DESCRIPTION:
XS GIS Cut Line= 3
      3754367.85     10186561.09      3754308.23     10186016.84
      3753867.87     10185411.09
#Sta/Elev= 30
  4452.5  263.13  4482.7  263.26    4533  261.23  4594.3  260.97  4663.8   258.9
  4734.2  252.35  4754.3  251.34  4862.8  252.62  4885.1  249.38  4931.7  245.42
  4939.1  245.42  4945.4  250.05    4954  252.89  4975.6  253.05    5000  250.54
  5005.1  248.91  5025.9  253.25  5105.5  250.39  5111.7  251.28  5132.6  250.42
    5233  251.08  5254.4  250.37  5342.6  253.81  5404.6  258.89  5519.8  261.99
  5576.2  265.66  5655.8  269.01  5670.5  271.01  5691.4  271.51  5748.9  275.69
#Mann= 4 ,-1 , 0
  4452.5     .17       0  4975.6     .09       0  5025.9     .15       0
  5342.6     .17       0
Bank Sta=4975.6,5025.9
XS Rating Curve= 0 ,0
Exp/Cntr=0.3,0.1

Type RM Length L Ch R = 1 ,6407    ,493,493,493
BEGIN DESCRIPTION:
ANTHONY BRANCH 10.0
END DESCRIPTION:
XS GIS Cut Line= 3
      3754417.84      10186611.1      3754628.23     10186016.84
      3754567.85     10185411.05
#Sta/Elev= 30
  4369.6  264.43  4626.9  256.75    4689  257.09  4762.1  256.81    4794  253.22
  4801.7  251.28    4807  251.45  4815.2   249.2  4825.8  248.89  4894.4  251.79
  4956.2  251.03  4974.3  252.18    4987  250.92  4995.1  248.61    5000  248.61
  5001.9  244.64  5009.8  244.64  5015.9  250.05  5025.9  252.27  5057.7  252.08
  5106.3  250.13    5153  251.28    5259  252.06  5287.2  252.94  5307.3  255.37
  5347.5  256.96  5417.8  257.68  5460.3  259.37  5578.6  268.02  5608.8  269.38
#Mann= 5 ,-1 , 0
  4369.6     .17       0    4689     .15       0  4974.3     .09       0
  5025.9     .15       0    5153     .17       0
Bank Sta=4974.3,5025.9
XS Rating Curve= 0 ,0
Exp/Cntr=0.3,0.1

Type RM Length L Ch R = 1 ,5914    ,499,499,499
BEGIN DESCRIPTION:
ANTHONY BRANCH 9.0
END DESCRIPTION:
XS GIS Cut Line= 3
      3754517.83     10186661.11      3754876.29     10186073.41
      3755067.87     10185661.04
#Sta/Elev= 30
  4311.6  264.02  4340.7   263.7  4356.2  262.13  4370.2  262.24  4493.6  256.07
    4515  256.28  4609.8   253.1  4698.2   251.3  4741.5  251.48  4784.1  249.35
    4855   250.8  4952.5  251.11  4958.4  249.33  4967.6  250.53    5004  250.72
  5007.9  245.81  5015.8  245.81  5016.3  246.31  5017.3  251.31  5024.6  250.34
  5046.7  251.35    5086  250.71  5123.9   248.6    5168   248.9  5183.1  247.23
  5210.1  248.45  5267.2  251.97  5311.3  256.49  5371.8  261.16  5454.7  265.04
#Mann= 5 ,-1 , 0
  4311.6     .17       0    4855     .15       0  4952.5     .09       0
  5017.3     .15       0  5210.1     .17       0
Bank Sta=4952.5,5017.3
XS Rating Curve= 0 ,0
Exp/Cntr=0.3,0.1

Type RM Length L Ch R = 1 ,5415    ,952,952,952
BEGIN DESCRIPTION:
ANTHONY BRANCH 8.0
END DESCRIPTION:
XS GIS Cut Line= 3
      3754980.32       10186927.      3755259.94     10186113.09
      3755277.62     10185661.34
#Sta/Elev= 30
  4139.4  266.37  4274.1  257.71  4393.8  253.07  4419.7  252.93    4451  252.12
  4462.9  251.19  4494.6  250.68  4544.7  251.91  4589.8  250.94    4675  247.43
    4727  246.78  4769.5  246.25  4812.1  247.85  4982.2  250.59  4991.6  248.48
  4994.5   244.5  5002.4   244.5    5012  247.54    5022  249.46    5032  248.96
  5052.1  246.37  5070.8   246.8  5075.8  246.18  5092.1  247.94  5132.1  247.61
  5172.2  250.17  5202.3  252.86  5252.2  257.56  5333.7  262.54  5452.1  265.97
#Mann= 5 ,-1 , 0
  4139.4     .17       0  4812.1     .15       0  4982.2     .09       0
    5022     .15       0  5202.3     .17       0
Bank Sta=4982.2,5022
XS Rating Curve= 0 ,0
Exp/Cntr=0.3,0.1