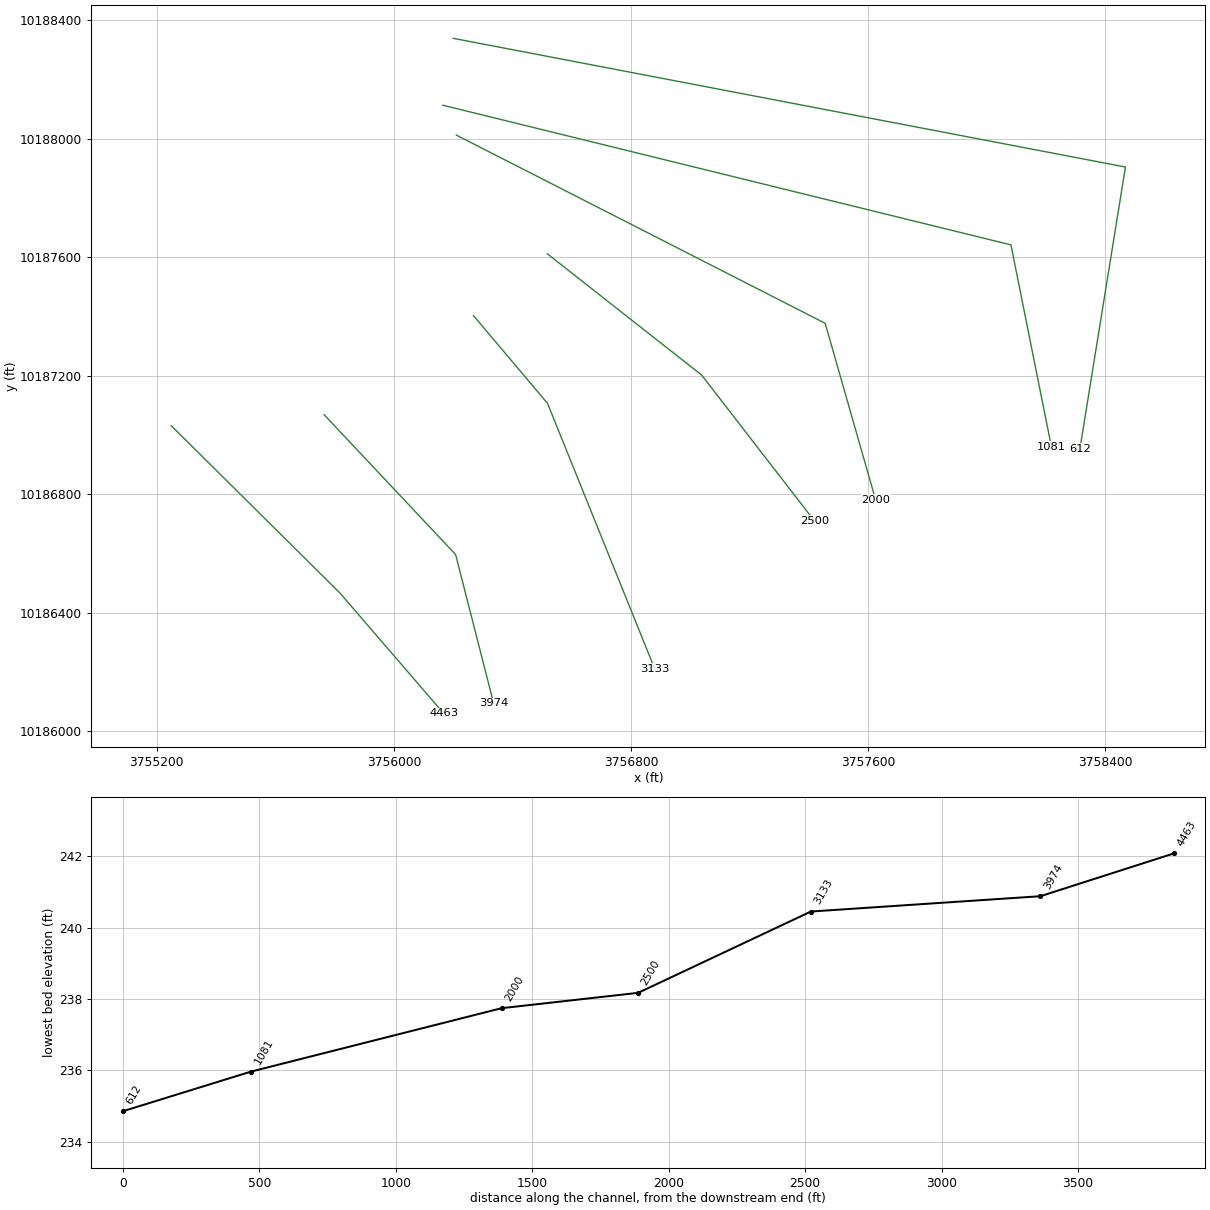
HEC-RAS study ANTHONY BRANCH.prj: ANTHONY BRANCH Base Level Engineering

--- ANTHONY BRANCH.g01 (geometry) --- (continued)

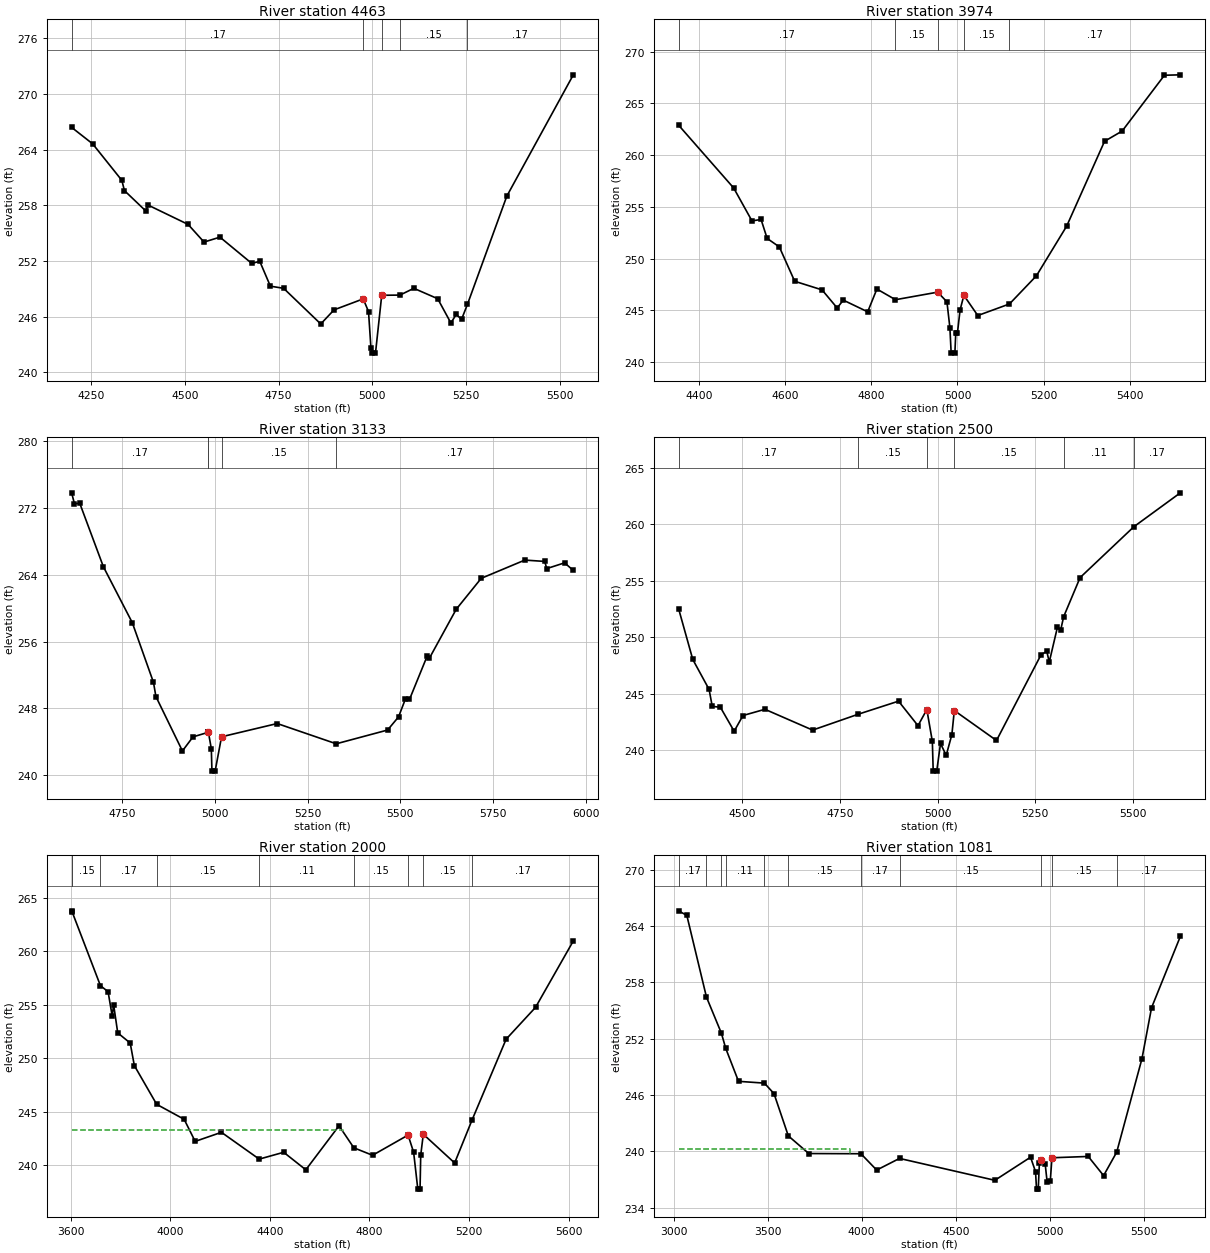
Type RM Length L Ch R = 1 ,4463    ,489,489,489
BEGIN DESCRIPTION:
ANTHONY BRANCH 6.0
END DESCRIPTION:
XS GIS Cut Line= 3
      3755249.01     10187031.39      3755818.23     10186466.84
      3756167.84     10186061.09
#Sta/Elev= 30
  4198.3  266.39  4254.3  264.62  4332.1  260.69  4339.1  259.58  4395.7   257.4
  4402.8  258.01  4508.8  255.94  4551.2  254.04  4593.7  254.57  4678.5  251.74
  4699.8  251.97  4728.1  249.29  4763.4  249.06  4862.4  245.22  4897.8  246.74
  4975.5  247.92  4989.7  246.56  4996.2  242.61  4999.8  242.08  5008.3  242.08
  5024.9  248.31  5073.5  248.33  5110.5  249.06  5174.1  247.94  5209.2  245.33
  5223.5  246.24  5237.7  245.72  5253.3  247.32  5358.4  258.99  5535.6  272.05
#Mann= 5 ,-1 , 0
  4198.3     .17       0  4975.5     .09       0  5024.9     .17       0
  5073.5     .15       0  5253.3     .17       0
Bank Sta=4975.5,5024.9
XS Rating Curve= 0 ,0
Exp/Cntr=0.3,0.1

Type RM Length L Ch R = 1 ,3974    ,841,841,841
BEGIN DESCRIPTION:
ANTHONY BRANCH 5.0
END DESCRIPTION:
XS GIS Cut Line= 3
      3755764.64     10187068.53      3756208.23     10186596.84
      3756336.36     10186095.35
#Sta/Elev= 30
  4352.5  262.89  4480.3  256.83  4522.8  253.65  4543.9  253.79    4558  251.96
  4586.3  251.14    4622  247.82  4685.5  246.99  4720.7  245.24  4734.8     246
  4791.5  244.87  4812.9  247.07  4856.1  246.04  4954.1  246.77  4975.6  245.83
  4982.4  243.34  4985.4  240.88    4994  240.88  4996.1  242.84    5000  242.84
    5006  245.03  5014.9  246.46  5047.2  244.51  5120.8  245.63  5183.4  248.35
  5253.7  253.15  5341.6  261.34  5382.5  262.33  5480.7  267.72  5517.6  267.76
#Mann= 5 ,-1 , 0
  4352.5     .17       0  4856.1     .15       0  4954.1     .09       0
  5014.9     .15       0  5120.8     .17       0
Bank Sta=4954.1,5014.9
XS Rating Curve= 0 ,0
Exp/Cntr=0.3,0.1

Type RM Length L Ch R = 1 ,3133    ,633,633,633
BEGIN DESCRIPTION:
ANTHONY BRANCH 3.0
END DESCRIPTION:
XS GIS Cut Line= 3
      3756268.58     10187402.69      3756518.23     10187106.84
      3756880.17     10186210.68
#Sta/Elev= 30
  4612.9  273.84  4620.5  272.53  4634.8  272.59  4698.6  264.97  4776.6  258.26
  4833.8  251.09  4840.3   249.4  4911.8  242.87  4940.4  244.56  4980.3  245.09
    4982   245.1  4989.8  243.14  4991.5  240.45  5000.1  240.45  5017.4  244.57
  5167.6  246.16  5326.9  243.73  5465.4  245.38    5495  246.96  5513.1  249.06
  5524.5  249.05  5572.8  254.32  5578.2     254  5650.6  259.87    5718  263.58
  5835.7  265.77  5889.4  265.61  5894.8  264.75    5943  265.44  5966.5  264.53
#Mann= 5 ,-1 , 0
  4612.9     .17       0  4980.3     .15       0    4982     .09       0
  5017.4     .15       0  5326.9     .17       0
Bank Sta=4982,5017.4
XS Rating Curve= 0 ,0
Exp/Cntr=0.3,0.1

Type RM Length L Ch R = 1 ,2500    ,500,500,500
BEGIN DESCRIPTION:
ANTHONY BRANCH 5.5
END DESCRIPTION:
XS GIS Cut Line= 3
      3756517.84     10187611.08      3757038.23     10187202.22
      3757417.88     10186711.04
#Sta/Elev= 30
  4338.2  252.52  4374.3  248.05    4416   245.4  4424.1   243.9  4444.9  243.82
  4480.1   241.7  4502.7  243.09  4558.8  243.64  4680.7   241.8  4797.8  243.21
  4900.4  244.36  4950.1  242.19  4972.7  243.62  4986.8   240.8    4989  238.17
    4998  238.17  5007.7  240.62  5022.2  239.56  5036.7   241.4    5043  243.53
  5150.8  240.88  5264.9  248.48  5279.4  248.76  5285.7  247.82  5306.5  250.89
  5314.7  250.62  5322.5  251.83  5364.5  255.29    5502  259.79  5620.8  262.79
#Mann= 6 ,-1 , 0
  4338.2     .17       0  4797.8     .15       0  4972.7     .09       0
    5043     .15       0  5322.5     .11       0    5502     .17       0
Bank Sta=4972.7,5043
XS Rating Curve= 0 ,0
Exp/Cntr=0.3,0.1

Type RM Length L Ch R = 1 ,2000    ,919,919,919
BEGIN DESCRIPTION:
ANTHONY BRANCH 4.0
END DESCRIPTION:
XS GIS Cut Line= 3
      3756210.65     10188011.79      3757454.91     10187376.84
      3757624.95     10186781.45
#Sta/Elev= 30
  3603.1   263.8  3605.9  263.66  3718.9  256.79  3749.6  256.23  3766.2  253.94
  3771.8  255.02  3788.4  252.37  3838.5  251.42  3855.1  249.31  3944.9  245.68
  4055.2  244.28  4099.6  242.21  4205.1  243.06  4356.9  240.55  4455.3  241.19
  4544.2  239.55  4677.7  243.67  4737.2  241.61  4812.5  240.91  4955.2   242.8
  4977.5  241.19  4994.3  237.74  5003.3  237.74    5006  240.92  5016.4  242.88
  5142.3  240.19  5212.4  244.22  5349.2  251.78  5467.4  254.76  5619.2  260.98
#Mann= 9 ,-1 , 0
  3603.1     .17       0  3605.9     .15       0  3718.9     .17       0
  3944.9     .15       0  4356.9     .11       0  4737.2     .15       0
  4955.2     .09       0  5016.4     .15       0  5212.4     .17       0
#XS Ineff= 2 , 0
       0  4694.1  243.29               0
Permanent Ineff=
       T       F
Bank Sta=4955.2,5016.4
XS Rating Curve= 0 ,0
Exp/Cntr=0.3,0.1

Type RM Length L Ch R = 1 ,1081    ,469,469,469
BEGIN DESCRIPTION:
ANTHONY BRANCH 2.0
END DESCRIPTION:
XS GIS Cut Line= 3
      3756165.59     10188112.45      3758081.44     10187641.45
      3758217.85     10186961.09
#Sta/Elev= 30
  3027.1   265.6  3070.6  265.11    3175  256.41  3254.2  252.57  3277.6  250.94
  3345.3  247.44  3482.9  247.25    3534  246.13  3610.1  241.63  3719.1  239.75
  3995.9  239.73  4079.8  237.99  4201.1  239.23    4708   236.9  4897.7  239.36
  4924.2  237.82  4929.5  235.96  4938.6  235.96  4944.8  238.78  4955.1  239.06
  4975.6  238.62    4986  236.69  5002.7  236.84  5011.4   239.3  5204.4  239.44
    5286   237.4  5355.7   239.9  5489.9  249.85  5540.9  255.28  5693.9  262.87
#Mann= 11 ,-1 , 0
  3027.1     .17       0    3175     .11       0  3254.2     .17       0
  3277.6     .11       0  3482.9     .17       0  3610.1     .15       0
  3995.9     .17       0  4201.1     .15       0  4955.1     .09       0
  5011.4     .15       0  5355.7     .17       0
#XS Ineff= 2 , 0
       0  3937.1  240.21               0
Permanent Ineff=
       F       F
Bank Sta=4955.1,5011.4
XS Rating Curve= 0 ,0
Exp/Cntr=0.3,0.1

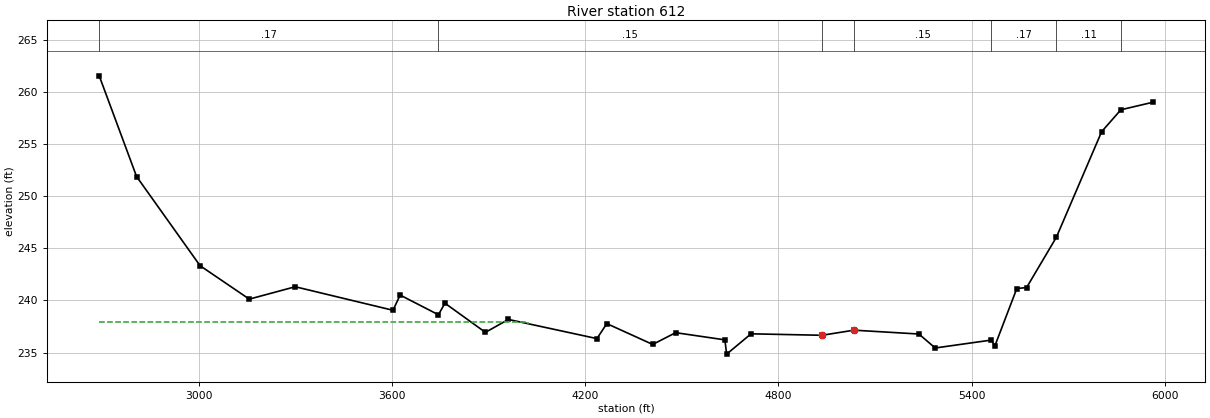
Type RM Length L Ch R = 1 ,612     ,0,0,0
BEGIN DESCRIPTION:
ANTHONY BRANCH 1.0
END DESCRIPTION:
XS GIS Cut Line= 3
      3756200.31     10188338.15      3758467.73     10187904.04
      3758314.28     10186954.45
#Sta/Elev= 30
  2691.4  261.57  2807.4   251.9  3004.5  243.34  3157.3  240.13  3299.8  241.32
  3603.3  239.06  3625.6  240.52  3744.4  238.63  3764.6  239.74  3890.3  236.94
  3961.6  238.18  4236.5  236.34  4267.1  237.78  4409.6  235.78  4480.9  236.91
  4633.6  236.22  4639.2  234.85    4715   236.8    4935  236.66  5034.5  237.15
    5236  236.78  5286.6  235.44  5461.1   236.2  5471.7  235.63  5539.9  241.15
  5570.3  241.24  5662.7  246.07  5803.3  256.21    5863  258.31  5961.9  259.03
#Mann= 7 ,-1 , 0
  2691.4     .17       0  3744.4     .15       0    4935     .09       0
  5034.5     .15       0  5461.1     .17       0  5662.7     .11       0
    5863     .17       0
#XS Ineff= 2 , 0
       0  4022.7  237.91               0
Permanent Ineff=
       F       F
Bank Sta=4935,5034.5
XS Rating Curve= 0 ,0
Exp/Cntr=0.3,0.1

Chan Stop Cuts=-1
Use User Specified Reach Order=0
Composite Channel Slope=5