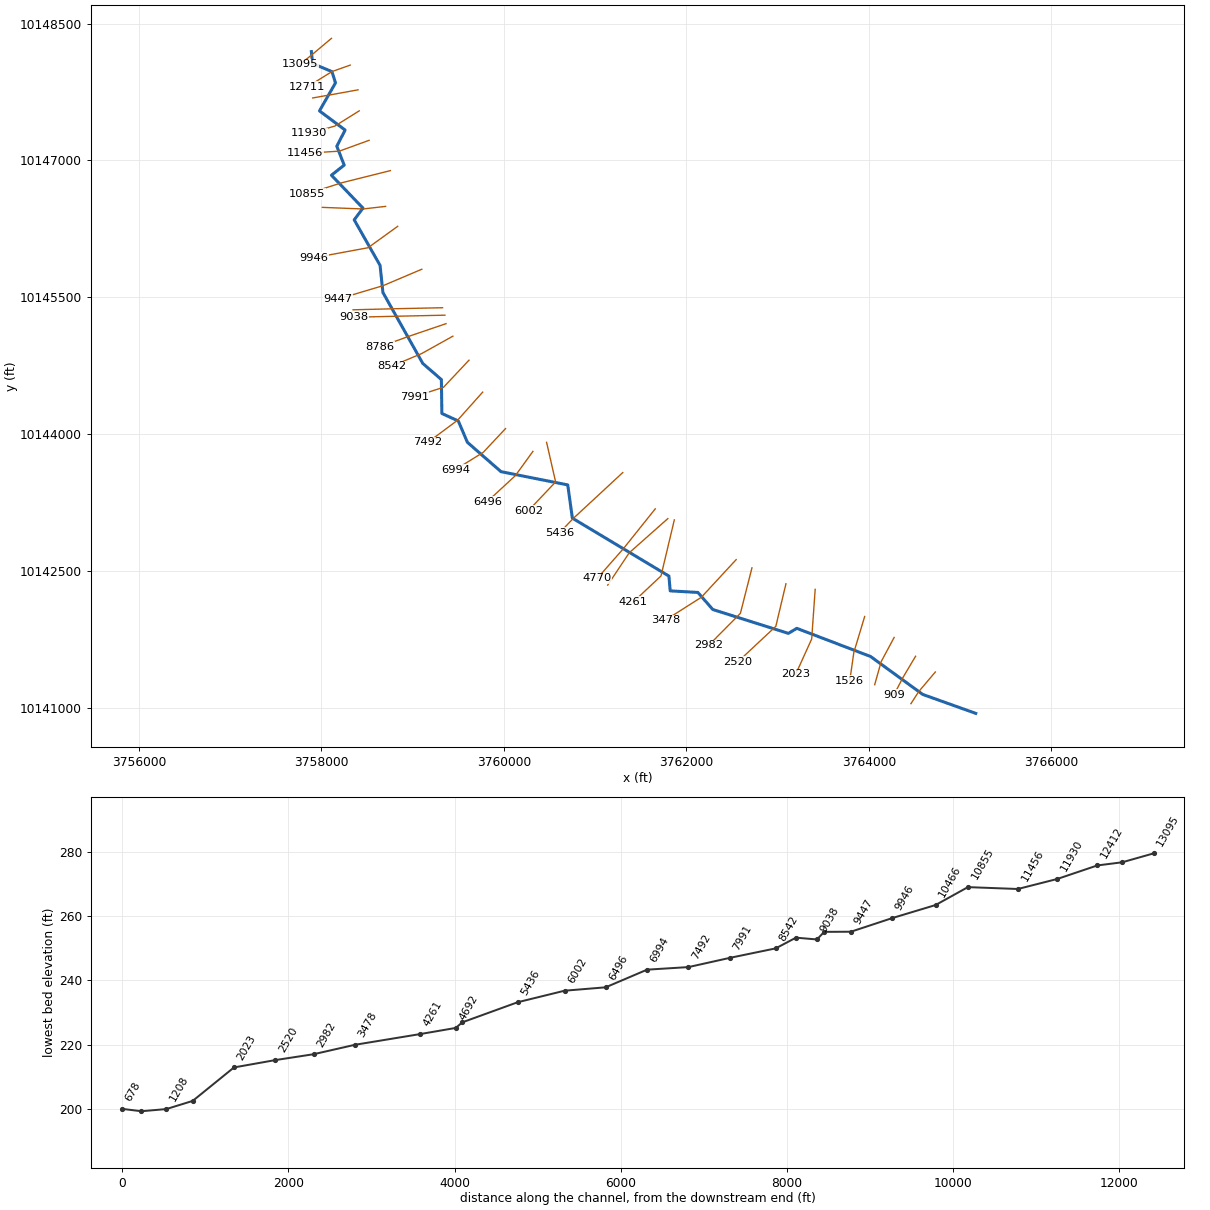
--- ATKINS CREEK.prj (project) ---

Proj Title=ATKINS CREEK Base Level Engineering
Current Plan=p01
Default Exp/Contr=0.3,0.1
English Units
Geom File=g01
Flow File=f01
Flow File=f02
Plan File=p01
Y Axis Title=Elevation
X Axis Title(PF)=Main Channel Distance
X Axis Title(XS)=Station
BEGIN DESCRIPTION:
ATKINS CREEK
END DESCRIPTION:
DSS Export Rating Curves= 0
DSS Export Rating Curve Sorted= 0
DSS Export Volume Flow Curves= 0
DXF OffsetX= 0
DXF OffsetY= 0
DXF ScaleX= 1
DXF ScaleY= 10

--- ATKINS CREEK.p01 (plan) ---

Plan Title=Multiple Run
Short Identifier=Multiple
Geom File=g01
Flow File=f01
Subcritical Flow
K Sum by GR= 0
Std Step Tol= 0.01
Critical Tol= 0.01
Num of Std Step Trials= 20
Max Error Tol= 0.3
Flow Tol Ratio= 0.001
Split Flow NTrial= 30
Split Flow Tol= 0.02
Split Flow Ratio= 0.02
Log Output Level= 0
Friction Slope Method= 1
Unsteady Friction Slope Method= 2
Unsteady Bridges Friction Slope Method= 1
Parabolic Critical Depth
Global Vel Dist=  1 , 1 , 1
Global Log Level= 0
CheckData=True
Encroach Param= -1, 0, 0, 0
BEGIN DESCRIPTION:
Multiple Run
END DESCRIPTION:

--- ATKINS CREEK.f01 (steady flow) ---

Flow Title=Multiple
Program Version=4.10
Number of Profiles= 7
Profile Names=10-year,25-year,50-year,1pct_min,100-year,1pct_plu,500-year
River Rch & RM=ATKINS CREEK,Reach-1         ,13095
     486     648     866     381    1152    3479    2105
River Rch & RM=ATKINS CREEK,Reach-1         ,5436
     818    1124    1534     688    2079    6278    3944
Boundary for River Rch & Prof#=ATKINS CREEK,Reach-1         , 1
Up Type= 0
Dn Type= 3
Dn Slope=0.005
Boundary for River Rch & Prof#=ATKINS CREEK,Reach-1         , 2
Up Type= 0
Dn Type= 3
Dn Slope=0.005
Boundary for River Rch & Prof#=ATKINS CREEK,Reach-1         , 3
Up Type= 0
Dn Type= 3
Dn Slope=0.005
Boundary for River Rch & Prof#=ATKINS CREEK,Reach-1         , 4
Up Type= 0
Dn Type= 3
Dn Slope=0.005
Boundary for River Rch & Prof#=ATKINS CREEK,Reach-1         , 5
Up Type= 0
Dn Type= 3
Dn Slope=0.005
Boundary for River Rch & Prof#=ATKINS CREEK,Reach-1         , 6
Up Type= 0
Dn Type= 3
Dn Slope=0.005
Boundary for River Rch & Prof#=ATKINS CREEK,Reach-1         , 7
Up Type= 0
Dn Type= 3
Dn Slope=0.005
DSS Import GetInterval= 0
DSS Import GetPeak= 0
DSS Import FillOption= 0

--- ATKINS CREEK.f02 (steady flow) ---

Flow Title=Orig_BLE_Flow
Program Version=4.10
Number of Profiles= 7
Profile Names=10-year,25-year,50-year,1pct_min,100-year,1pct_plu,500-year
River Rch & RM=ATKINS CREEK,Reach-1         ,13095
     486     635     753     293     886    2676    1224
River Rch & RM=ATKINS CREEK,Reach-1         ,5436
     818    1102    1334     529    1599    4828    2293
Boundary for River Rch & Prof#=ATKINS CREEK,Reach-1         , 1
Up Type= 0
Dn Type= 3
Dn Slope=0.005
Boundary for River Rch & Prof#=ATKINS CREEK,Reach-1         , 2
Up Type= 0
Dn Type= 3
Dn Slope=0.005
Boundary for River Rch & Prof#=ATKINS CREEK,Reach-1         , 3
Up Type= 0
Dn Type= 3
Dn Slope=0.005
Boundary for River Rch & Prof#=ATKINS CREEK,Reach-1         , 4
Up Type= 0
Dn Type= 3
Dn Slope=0.005
Boundary for River Rch & Prof#=ATKINS CREEK,Reach-1         , 5
Up Type= 0
Dn Type= 3
Dn Slope=0.005
Boundary for River Rch & Prof#=ATKINS CREEK,Reach-1         , 6
Up Type= 0
Dn Type= 3
Dn Slope=0.005
Boundary for River Rch & Prof#=ATKINS CREEK,Reach-1         , 7
Up Type= 0
Dn Type= 3
Dn Slope=0.005
DSS Import GetInterval= 0
DSS Import GetPeak= 0
DSS Import FillOption= 0

--- ATKINS CREEK.g01 (geometry) ---

Geom Title=Existing Conditions
Program Version=4.10

River Reach=ATKINS CREEK    ,Reach-1
Reach XY= 30
      3757890.35     10148192.53      3757903.88     10148061.39
      3758115.81     10147973.23      3758154.88     10147849.53
      3757979.22     10147542.72      3758260.35     10147332.61
       3758169.2     10147155.52      3758249.93     10146948.49
      3758110.21     10146837.66      3758455.77     10146477.43
      3758359.92     10146348.57      3758643.16     10145850.02
      3758674.41     10145552.66      3759111.26     10144775.25
      3759315.11     10144598.44      3759320.37     10144226.76
      3759500.52     10144144.76      3759600.27     10143910.86
      3759968.34     10143589.34      3760699.83     10143443.94
      3760750.38     10143080.01      3761808.27     10142445.19
      3761822.65     10142283.06       3762125.8     10142265.69
      3762289.03     10142078.85      3763117.62     10141817.21
      3763209.91     10141872.31      3764017.67     10141564.16
      3764589.78     10141148.32      3765170.94     10140940.59

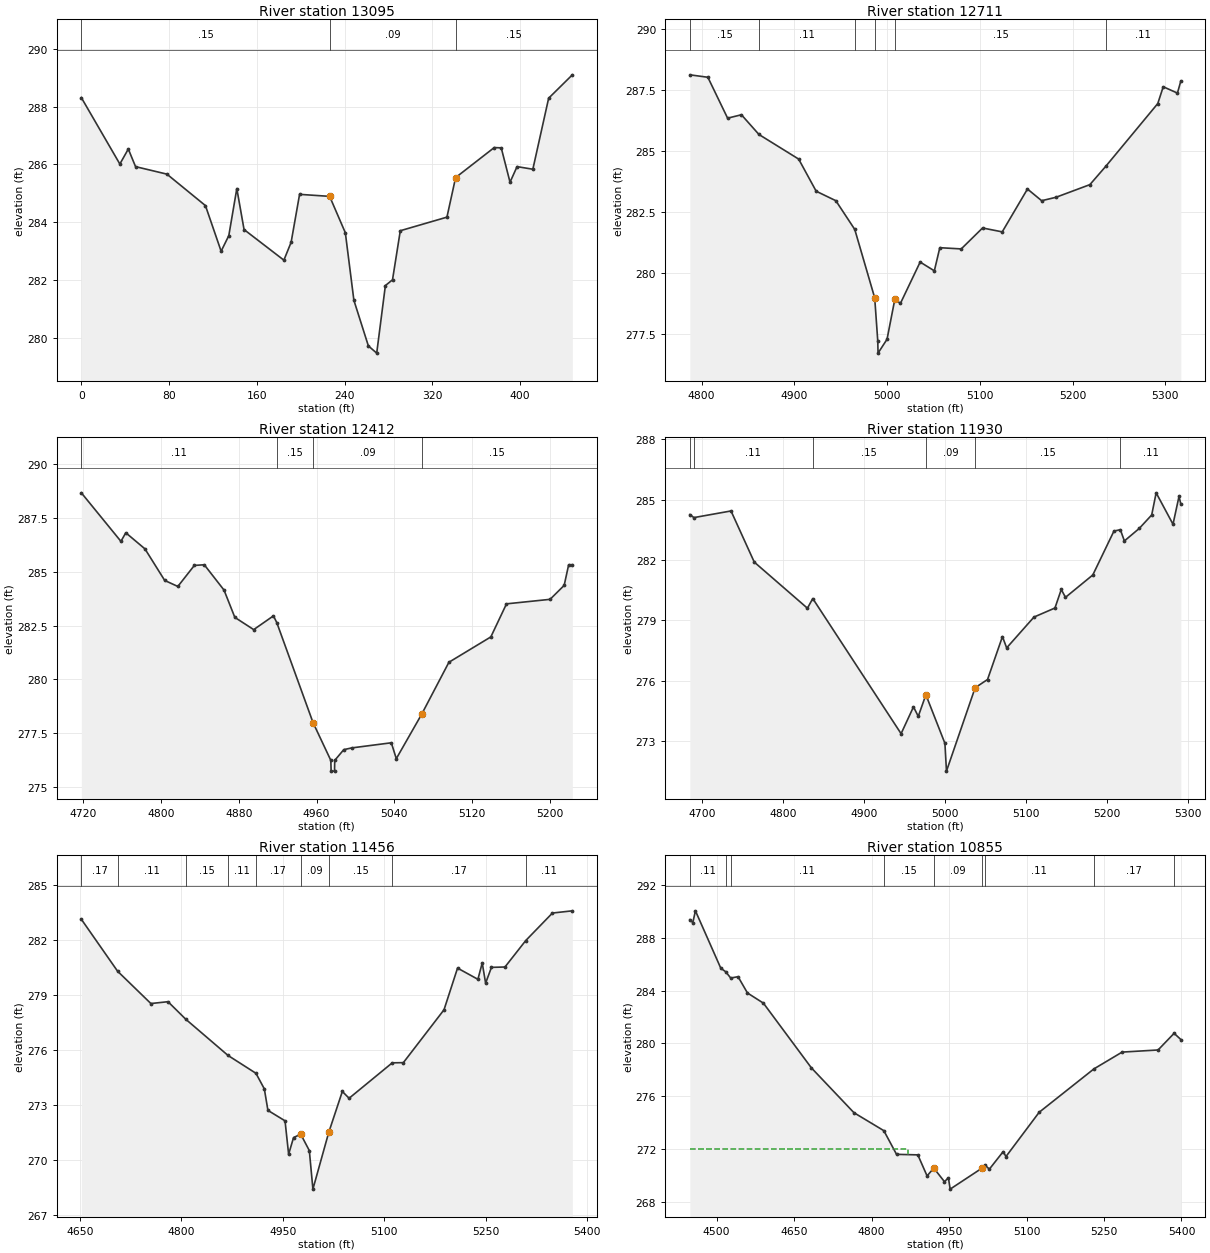
Type RM Length L Ch R = 1 ,13095   ,378,378,378
XS GIS Cut Line= 3
      3758110.79     10148337.71      3757908.02     10148167.49
      3757765.94      10148052.6
#Sta/Elev= 30
       0  288.31    35.1  286.01    42.8  286.53    49.4  285.92      78  285.66
   113.1  284.57   127.4  282.99   134.4  283.53   141.7  285.16   148.3  283.74
   184.6  282.68   191.2   283.3   198.9  284.96   226.3  284.89   240.6  283.63
   248.4  281.29   261.6  279.71   269.2  279.46   277.1   281.8   283.6     282
   290.7   283.7   333.2  284.17   341.1  285.54   376.3  286.58   382.7  286.57
   390.7  285.38   397.1  285.92   411.5  285.83   425.9  288.29   447.5   289.1
#Mann= 3 , 0 , 0
       0     .15       0   226.3     .09       0   341.1     .15       0
Bank Sta=226.3,341.1
XS Rating Curve= 0 ,0
Exp/Cntr=0.3,0.1

Type RM Length L Ch R = 1 ,12711   ,299,299,299
BEGIN DESCRIPTION:
ATKINS CREEK 27.0
END DESCRIPTION:
XS GIS Cut Line= 3
      3758316.17     10148044.33      3758115.81     10147973.23
      3757846.74     10147806.01
#Sta/Elev= 30
  4787.4  288.13  4806.8  288.03  4828.1  286.35    4843  286.49  4861.9  285.68
  4904.7  284.67  4923.6  283.35  4944.8  282.96  4965.2  281.78  4986.7  278.97
    4990   277.2  4990.3   276.7    5000  277.27  5008.5  278.93  5014.4  278.74
  5035.7  280.44    5051  280.08  5056.9  281.03    5080  280.98    5103  281.84
  5124.2  281.68  5151.4  283.44  5166.7  282.96  5182.1   283.1  5218.7  283.62
    5236  284.38  5291.9  286.95  5297.8  287.64  5313.1  287.38  5316.8  287.88
#Mann= 6 ,-1 , 0
  4787.4     .15       0  4861.9     .11       0  4965.2     .15       0
  4986.7     .09       0  5008.5     .15       0    5236     .11       0
Bank Sta=4986.7,5008.5
XS Rating Curve= 0 ,0
Exp/Cntr=0.3,0.1

Type RM Length L Ch R = 1 ,12412   ,482,482,482
BEGIN DESCRIPTION:
ATKINS CREEK 26.0
END DESCRIPTION:
XS GIS Cut Line= 3
      3758402.22     10147773.43      3758124.93     10147723.23
      3757905.32     10147684.47
#Sta/Elev= 30
  4718.2  288.68  4758.9  286.42  4763.9  286.82  4783.6  286.07  4803.9   284.6
  4817.4  284.32  4834.4   285.3  4844.6  285.33  4864.9  284.15    4876  282.88
  4895.4  282.31  4915.7  282.95  4919.1  282.64  4956.4  277.98  4974.7  276.22
    4975  275.72  4978.5  275.72  4978.7  276.22    4988  276.72    4996   276.8
  5036.9  277.04    5042   276.3  5068.1  278.37  5096.1  280.79  5139.2  281.97
  5155.3  283.51  5200.1  283.72  5214.6  284.37  5219.2  285.33    5223  285.33
#Mann= 4 ,-1 , 0
  4718.2     .11       0  4919.1     .15       0  4956.4     .09       0
  5068.1     .15       0
Bank Sta=4956.4,5068.1
XS Rating Curve= 0 ,0
Exp/Cntr=0.3,0.1

Type RM Length L Ch R = 1 ,11930   ,474,474,474
BEGIN DESCRIPTION:
ATKINS CREEK 25.0
END DESCRIPTION:
XS GIS Cut Line= 3
      3758415.27      10147543.4      3758148.36     10147376.49
      3757868.49     10147296.03
#Sta/Elev= 30
  4685.2  284.26  4690.2  284.11    4736  284.44  4764.7   281.9  4830.3  279.61
  4836.9  280.09  4945.9  273.38  4961.2  274.71  4967.1  274.24  4976.5  275.31
    5000   272.9  5001.9  271.52  5037.3  275.66  5052.6  276.07    5071   278.2
  5076.2  277.64  5109.9  279.17  5135.8  279.62  5143.6  280.54  5148.8  280.15
  5182.5  281.26  5208.6  283.44  5216.5  283.51  5221.5  282.95  5239.8  283.57
  5255.2  284.24  5260.7  285.34  5281.5  283.78  5288.9  285.16  5291.2  284.78
#Mann= 6 ,-1 , 0
  4685.2     .17       0  4690.2     .11       0  4836.9     .15       0
  4976.5     .09       0  5037.3     .15       0  5216.5     .11       0
Bank Sta=4976.5,5037.3
XS Rating Curve= 0 ,0
Exp/Cntr=0.3,0.1

Type RM Length L Ch R = 1 ,11456   ,601,601,601
BEGIN DESCRIPTION:
ATKINS CREEK 24.0
END DESCRIPTION:
XS GIS Cut Line= 3
      3758522.67     10147220.04      3758195.76      10147101.3
      3757818.49     10147077.91
#Sta/Elev= 30
  4652.2  283.11  4705.8  280.28    4755  278.52  4780.3  278.62  4806.7  277.66
  4869.1  275.69  4910.3  274.72  4922.7  273.87    4928   272.7  4953.3  272.13
  4958.6  270.31  4965.9  271.22  4976.5   271.4  4989.2  270.51  4994.5  268.41
  5017.9   271.5    5038  273.73    5048  273.36  5111.8  275.29  5128.2   275.3
  5188.3  278.18  5208.3  280.45  5238.4  279.84  5244.8  280.73  5249.8  279.63
  5258.4  280.49  5278.4  280.51  5309.1  281.95  5348.6  283.45    5378  283.57
#Mann= 9 ,-1 , 0
  4652.2     .17       0  4705.8     .11       0  4806.7     .15       0
  4869.1     .11       0  4910.3     .17       0  4976.5     .09       0
  5017.9     .15       0  5111.8     .17       0  5309.1     .11       0
Bank Sta=4976.5,5017.9
XS Rating Curve= 0 ,0
Exp/Cntr=0.3,0.1

Type RM Length L Ch R = 1 ,10855   ,389,389,389
BEGIN DESCRIPTION:
ATKINS CREEK 23.0
END DESCRIPTION:
XS GIS Cut Line= 3
        3758756.     10146888.03      3758220.77     10146754.25
      3757840.99     10146632.55
#Sta/Elev= 30
  4448.3  289.36    4454  289.14  4459.1  290.03  4508.2  285.69  4517.5  285.43
  4527.4  284.95  4541.6  285.05  4559.8  283.82  4590.7  283.05  4683.5  278.16
  4765.9  274.77  4823.8  273.41  4848.4  271.62  4889.6  271.58  4907.5  269.99
  4920.5  270.58  4941.2  269.55  4948.8  269.85  4952.2  268.99  5013.6  270.57
  5019.5  270.81  5028.1   270.5  5054.9  271.83  5060.2  271.45  5124.5   274.8
  5230.5  278.08  5285.1  279.35  5354.7  279.51  5385.7  280.77  5398.8   280.3
#Mann= 9 ,-1 , 0
  4448.3     .11       0  4517.5     .17       0  4527.4     .11       0
  4823.8     .15       0  4920.5     .09       0  5013.6     .15       0
  5019.5     .11       0  5230.5     .17       0  5385.7     .11       0
#XS Ineff= 2 , 0
       0  4871.5  272.06  5054.9       0  271.83
Permanent Ineff=
       F       F
Bank Sta=4920.5,5013.6
XS Rating Curve= 0 ,0
Exp/Cntr=0.3,0.1

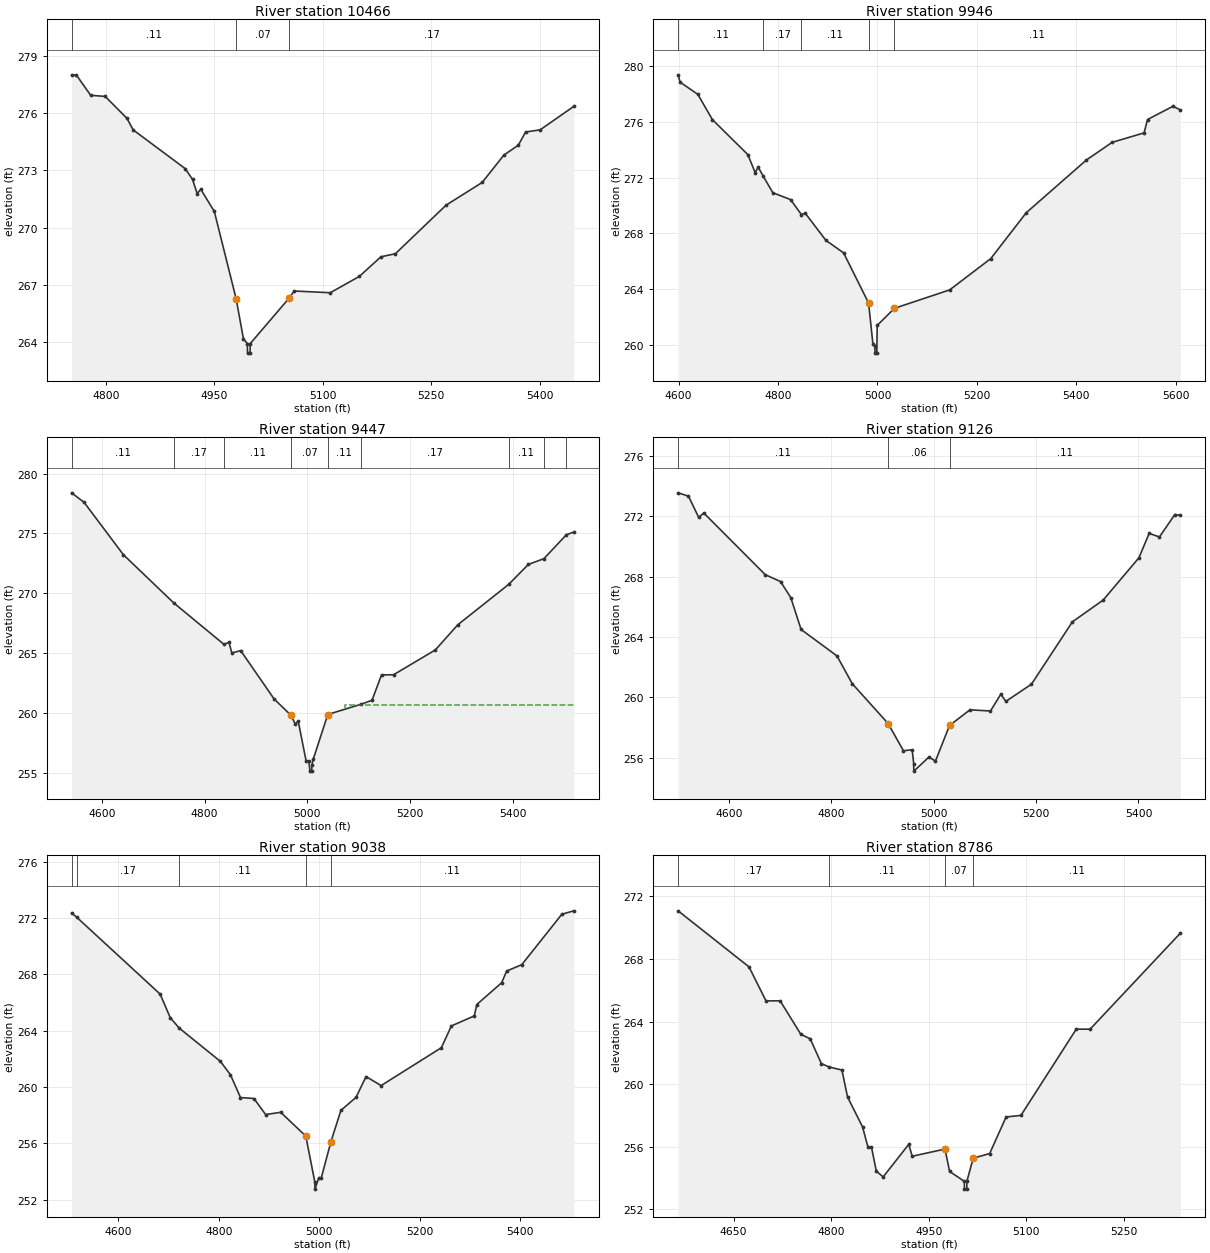
Type RM Length L Ch R = 1 ,10466   ,520,520,520
BEGIN DESCRIPTION:
ATKINS CREEK 22.0
END DESCRIPTION:
XS GIS Cut Line= 3
      3758703.95     10146496.32      3758458.21      10146467.7
      3758011.16      10146485.4
#Sta/Elev= 30
  4752.6  277.99  4759.3  277.97  4778.9  276.92    4799  276.86  4829.2  275.71
  4837.7  275.11  4909.8  273.08  4919.8  272.52  4926.2  271.78  4931.3     272
    4950  270.84  4980.2  266.27  4990.3  264.17  4995.7  263.93  4995.9  263.43
  4999.4  263.43  4999.7  263.93    5054  266.33  5060.4  266.68  5110.4  266.59
  5150.5  267.44  5180.5  268.47  5200.5  268.63  5270.6  271.17  5320.6  272.36
  5350.6  273.79  5370.6  274.31  5380.7     275  5400.7  275.11  5447.4  276.34
#Mann= 3 ,-1 , 0
  4752.6     .11       0  4980.2     .07       0    5054     .17       0
Bank Sta=4980.2,5054
XS Rating Curve= 0 ,0
Exp/Cntr=0.3,0.1

Type RM Length L Ch R = 1 ,9946    ,499,499,499
BEGIN DESCRIPTION:
ATKINS CREEK 21.0
END DESCRIPTION:
XS GIS Cut Line= 3
      3758836.72       10146278.      3758511.84     10146043.11
      3757913.07      10145932.5
#Sta/Elev= 30
  4599.1  279.38  4603.1  278.85  4638.7  277.98  4668.1  276.16  4739.3  273.65
    4754  272.36  4760.1  272.75  4770.5  272.08  4789.6  270.91  4825.1  270.42
  4847.1  269.34  4854.5  269.45  4896.3  267.49  4931.9  266.59  4982.1  262.99
  4990.7  260.08  4994.8  259.89  4995.1  259.39  4998.6  259.39  4999.4  261.38
  5034.1  262.61  5145.1  263.93  5227.8  266.18    5299  269.47    5420  273.26
  5471.8  274.53  5536.1  275.21    5543  276.17  5594.1  277.12  5608.9  276.86
#Mann= 5 ,-1 , 0
  4599.1     .11       0  4770.5     .17       0  4847.1     .11       0
  4982.1     .07       0  5034.1     .11       0
Bank Sta=4982.1,5034.1
XS Rating Curve= 0 ,0
Exp/Cntr=0.3,0.1

Type RM Length L Ch R = 1 ,9447    ,321,321,321
BEGIN DESCRIPTION:
ATKINS CREEK 20.0
END DESCRIPTION:
XS GIS Cut Line= 3
      3759100.61     10145807.51      3758678.31     10145628.18
      3758181.62     10145479.73
#Sta/Elev= 30
  4541.2  278.39  4565.5  277.59  4641.9  273.22  4740.2  269.18  4837.6  265.73
  4847.4   265.9  4852.9  265.01  4870.1  265.21  4935.3  261.16  4967.9  259.81
  4976.6  259.05    4982  259.33  4997.5  255.98  5002.9  255.98  5004.8  255.14
  5008.3  255.14  5008.5  255.64  5011.7  256.18  5039.6  259.87  5104.4  260.73
  5125.7  261.06  5144.2  263.18  5167.5  263.19  5248.8  265.26  5292.7  267.37
  5391.6  270.74    5430  272.41  5460.2  272.89  5503.9  274.89  5518.4  275.11
#Mann= 9 ,-1 , 0
  4541.2     .11       0  4740.2     .17       0  4837.6     .11       0
  4967.9     .07       0  5039.6     .11       0  5104.4     .17       0
  5391.6     .11       0  5460.2     .17       0  5503.9     .11       0
#XS Ineff= 2 , 0
       0                  5072.8       0   260.7
Permanent Ineff=
       F       F
Bank Sta=4967.9,5039.6
XS Rating Curve= 0 ,0
Exp/Cntr=0.3,0.1

Type RM Length L Ch R = 1 ,9126    ,88,88,88
BEGIN DESCRIPTION:
Mapping XS 363fe447
END DESCRIPTION:
XS GIS Cut Line= 3
      3759328.05     10145385.64      3758828.04     10145375.22
      3758347.11     10145363.07
#Sta/Elev= 30
  4500.5  273.57  4520.7  273.35  4540.7  271.94  4550.7  272.23  4670.7  268.14
  4700.7  267.68  4720.7  266.61  4740.8   264.5  4810.8  262.75  4840.8   260.9
  4910.8  258.26  4940.8  256.45  4957.8  256.52  4960.8   255.6    4961   255.1
  4990.8  256.04  5003.2  255.76  5030.8  258.13  5070.8  259.17  5110.8  259.09
  5130.9   260.2  5140.9  259.73  5190.9  260.87  5270.9  265.01  5330.9  266.45
  5400.9  269.26  5420.9  270.88  5440.9  270.64    5471  272.13  5481.7  272.08
#Mann= 3 , 0 , 0
  4500.5     .11       0  4910.8     .06       0  5030.8     .11       0
Bank Sta=4910.8,5030.8
XS Rating Curve= 0 ,0
Exp/Cntr=0.3,0.1

Type RM Length L Ch R = 1 ,9038    ,252,252,252
BEGIN DESCRIPTION:
ATKINS CREEK 19.0
END DESCRIPTION:
XS GIS Cut Line= 3
      3759354.11     10145304.04      3758860.93     10145293.27
      3758354.07     10145281.47
#Sta/Elev= 30
  4506.7  272.37  4516.6  272.07    4683   266.6    4703  264.93  4720.8  264.19
    4803  261.82    4823  260.87    4843  259.25  4869.8  259.18  4893.1  258.04
  4923.1   258.2  4973.1  256.51  4991.1  253.24  4991.3  252.74    4999  253.55
    5004  253.55  5023.1  256.11  5043.1  258.34  5073.1  259.26  5093.1  260.74
  5123.1   260.1  5243.1  262.79  5263.1  264.34  5308.7  265.05  5313.7  265.86
  5363.2  267.41  5373.2  268.24  5403.2  268.69  5483.2  272.28    5507  272.52
#Mann= 5 ,-1 , 0
  4506.7     .11       0  4516.6     .17       0  4720.8     .11       0
  4973.1     .07       0  5023.1     .11       0
Bank Sta=4973.1,5023.1
XS Rating Curve= 0 ,0
Exp/Cntr=0.3,0.1

Type RM Length L Ch R = 1 ,8786    ,244,244,244
BEGIN DESCRIPTION:
ATKINS CREEK 18.5
END DESCRIPTION:
XS GIS Cut Line= 3
      3759366.37     10145211.08      3758954.26     10145070.91
      3758637.49     10144955.91
#Sta/Elev= 30
  4564.7  271.08  4673.7   267.5  4699.8  265.33  4721.6  265.33  4753.3   263.2
  4767.9   262.9    4785  261.32  4797.1   261.1  4816.6  260.91  4825.3  259.18
  4848.3  257.28  4856.7  255.98    4862     256  4869.5  254.45    4880  254.08
  4919.4  256.16  4924.7   255.4  4975.1  255.86  4982.2  254.43  5004.8   253.8
  5005.1   253.3  5008.6   253.3  5008.8   253.8  5018.5  255.28  5043.8  255.57
  5069.1  257.91  5091.9  258.01    5177  263.52  5198.3  263.52    5337  269.65
#Mann= 4 ,-1 , 0
  4564.7     .17       0  4797.1     .11       0  4975.1     .07       0
  5018.5     .11       0
Bank Sta=4975.1,5018.5
XS Rating Curve= 0 ,0
Exp/Cntr=0.3,0.1

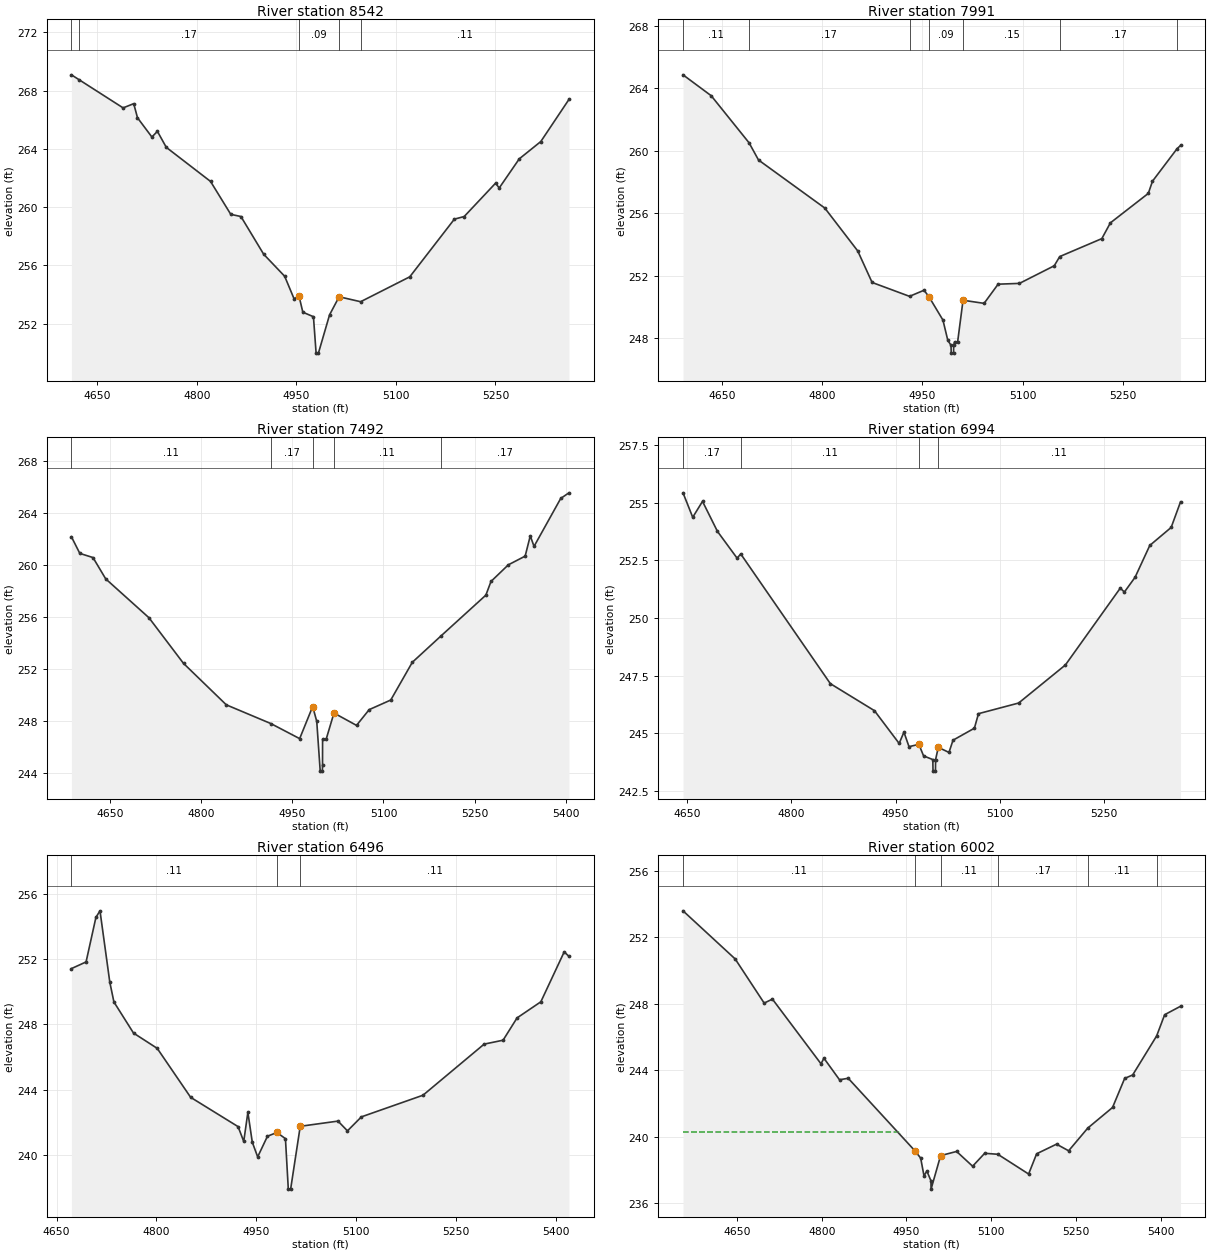
Type RM Length L Ch R = 1 ,8542    ,551,551,551
BEGIN DESCRIPTION:
ATKINS CREEK 18.0
END DESCRIPTION:
XS GIS Cut Line= 3
      3759441.02      10145073.9      3759101.12     10144884.52
      3758768.84     10144743.92
#Sta/Elev= 30
  4610.9  269.08  4622.6  268.74  4688.8  266.81  4704.8   267.1  4710.5  266.13
  4732.2  264.81  4740.5   265.2  4753.9   264.1  4820.6  261.76  4851.1   259.5
  4866.4  259.35  4900.7  256.76  4932.3  255.25  4946.5   253.7    4954  253.88
  4959.7  252.78  4975.7  252.47  4979.7  249.97  4983.2  249.97    5000   252.6
  5014.4  253.84  5046.8   253.5  5120.9  255.21  5188.1  259.17  5202.9  259.35
  5250.2  261.64  5255.7  261.31  5285.9  263.31  5318.4   264.5  5360.8  267.39
#Mann= 5 ,-1 , 0
  4610.9     .11       0  4622.6     .17       0    4954     .09       0
  5014.4     .17       0  5046.8     .11       0
Bank Sta=4954,5014.4
XS Rating Curve= 0 ,0
Exp/Cntr=0.3,0.1

Type RM Length L Ch R = 1 ,7991    ,499,499,499
BEGIN DESCRIPTION:
ATKINS CREEK 17.0
END DESCRIPTION:
XS GIS Cut Line= 3
      3759617.82     10144811.04      3759338.34     10144513.66
      3759017.86     10144411.07
#Sta/Elev= 30
  4591.9  264.87  4634.1  263.53  4690.8  260.51  4704.9  259.41  4804.1  256.33
  4853.4  253.58  4874.9  251.56  4930.9  250.67  4952.6  251.06  4959.9  250.65
  4980.9  249.15  4988.2  247.85    4993  247.53  4993.3  247.03  4996.8  247.03
    4997  247.53  4998.3  247.75  5002.9  247.75    5011  250.42  5042.5  250.22
  5063.5  251.45  5095.4   251.5  5147.5  252.63  5155.7  253.22  5218.7  254.37
  5231.5  255.38  5288.3  257.27  5294.5  258.05  5331.4  260.14  5336.5  260.34
#Mann= 7 ,-1 , 0
  4591.9     .11       0  4690.8     .17       0  4930.9     .15       0
  4959.9     .09       0    5011     .15       0  5155.7     .17       0
  5331.4     .11       0
Bank Sta=4959.9,5011
XS Rating Curve= 0 ,0
Exp/Cntr=0.3,0.1

Type RM Length L Ch R = 1 ,7492    ,498,498,498
BEGIN DESCRIPTION:
ATKINS CREEK 16.0
END DESCRIPTION:
XS GIS Cut Line= 3
      3759767.84     10144461.06      3759492.76     10144152.87
      3759167.86     10143911.08
#Sta/Elev= 30
  4586.9  262.19  4600.7  260.91  4622.4  260.59  4643.3  258.95  4714.4  255.96
  4771.2  252.45  4841.6  249.26  4914.8  247.82  4962.2  246.66  4983.6  249.13
  4990.3  247.99    4996  244.16  4999.5  244.16  4999.8  244.66  4999.9   246.6
  5005.7   246.6  5018.6  248.63  5055.7  247.68  5076.5  248.89    5112  249.63
  5147.4  252.53  5193.9  254.53  5268.4   257.7  5276.8  258.75  5305.3  260.03
    5333   260.7  5341.4  262.26  5347.6  261.45  5391.5  265.14    5405  265.57
#Mann= 5 ,-1 , 0
  4586.9     .11       0  4914.8     .17       0  4983.6     .09       0
  5018.6     .11       0  5193.9     .17       0
Bank Sta=4983.6,5018.6
XS Rating Curve= 0 ,0
Exp/Cntr=0.3,0.1

Type RM Length L Ch R = 1 ,6994    ,498,498,498
BEGIN DESCRIPTION:
ATKINS CREEK 15.0
END DESCRIPTION:
XS GIS Cut Line= 3
      3760017.88      10144061.1       3759774.3     10143801.19
      3759467.88     10143611.09
#Sta/Elev= 30
  4643.8  255.42  4657.8  254.36  4671.9  255.05  4693.4  253.75  4721.7  252.59
    4727  252.77  4856.1  247.15  4919.6  245.98  4955.2  244.56  4962.1  245.05
  4969.4  244.42  4983.6  244.52  4990.4  244.02  5003.7  243.86    5004  243.36
  5007.5  243.36  5007.7  243.86  5011.6  244.39    5027  244.17  5032.8   244.7
  5063.6  245.22  5069.5  245.85  5127.3  246.31  5194.7  247.96  5273.8  251.29
  5279.7  251.12  5295.1  251.76  5316.3  253.14  5347.1  253.92  5360.6  255.03
#Mann= 4 ,-1 , 0
  4643.8     .17       0    4727     .11       0  4983.6     .06       0
  5011.6     .11       0
Bank Sta=4983.6,5011.6
XS Rating Curve= 0 ,0
Exp/Cntr=0.3,0.1

Type RM Length L Ch R = 1 ,6496    ,494,494,494
BEGIN DESCRIPTION:
ATKINS CREEK 14.0
END DESCRIPTION:
XS GIS Cut Line= 3
      3760317.85     10143811.07      3760125.78     10143545.55
      3759817.87     10143261.09
#Sta/Elev= 30
  4672.3  251.43  4694.3  251.84  4709.1  254.58  4715.2  254.98  4729.9   250.6
  4736.1  249.38  4765.5  247.47  4801.1  246.53  4851.3  243.52  4922.5  241.72
    4931  240.81  4937.2   242.6  4943.8  240.77  4951.9  239.86  4966.6  241.13
  4980.8  241.36  4993.6  240.98  4997.9  237.88  5001.4  237.88  5015.8  241.74
  5072.5  242.06  5086.7  241.46  5107.6  242.32  5200.1  243.65  5291.9  246.79
  5320.3  247.03  5341.3   248.4    5377  249.39  5412.1  252.46  5419.2  252.18
#Mann= 3 , 0 , 0
  4672.3     .11       0  4980.8     .07       0  5015.8     .11       0
Bank Sta=4980.8,5015.8
XS Rating Curve= 0 ,0
Exp/Cntr=0.3,0.1

Type RM Length L Ch R = 1 ,6002    ,566,566,566
BEGIN DESCRIPTION:
ATKINS CREEK 13.0
END DESCRIPTION:
XS GIS Cut Line= 3
      3760467.85     10143911.08      3760566.91     10143476.84
      3760267.86     10143161.08
#Sta/Elev= 30
  4554.6   253.6  4646.9   250.7  4698.2  248.04  4712.8  248.28  4798.8  244.38
  4803.9  244.72  4831.5  243.42  4846.9  243.51  4964.9  239.14  4975.1   238.7
    4981  237.63  4986.1  237.92  4993.3  237.33  4993.5  236.83  5010.4  238.85
  5038.7   239.1    5067  238.21  5088.4  238.99  5111.6  238.93  5166.1  237.74
  5180.3  238.96  5215.5  239.54  5236.9  239.14  5270.8  240.51  5314.6  241.75
    5336   243.5  5350.2  243.71  5392.6  246.06  5406.8  247.34  5434.9  247.85
#Mann= 6 ,-1 , 0
  4554.6     .11       0  4964.9     .07       0  5010.4     .11       0
  5111.6     .17       0  5270.8     .11       0  5392.6     .17       0
#XS Ineff= 2 , 0
       0    4938  240.26               0
Permanent Ineff=
       F       F
Bank Sta=4964.9,5010.4
XS Rating Curve= 0 ,0
Exp/Cntr=0.3,0.1

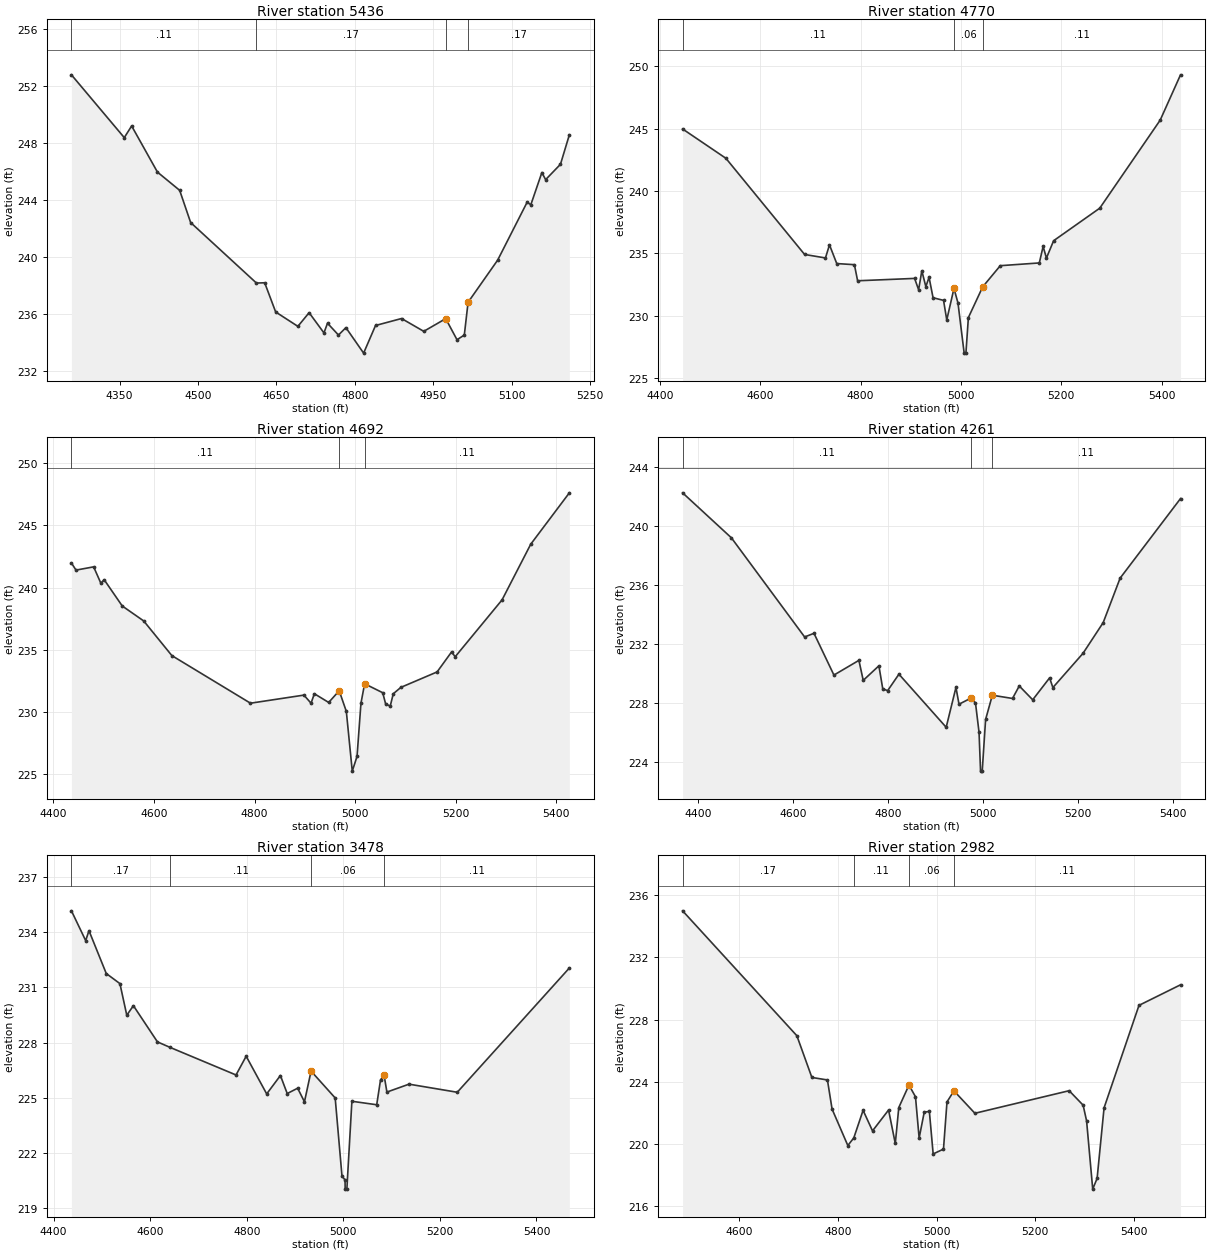
Type RM Length L Ch R = 1 ,5436    ,666,666,666
BEGIN DESCRIPTION:
ATKINS CREEK 12.0
END DESCRIPTION:
XS GIS Cut Line= 3
      3761302.33     10143579.08      3760758.06     10143074.47
      3760612.36      10142922.4
#Sta/Elev= 30
  4257.8  252.78  4358.9  248.37    4373  249.19  4422.4  245.95  4464.9  244.67
  4485.9  242.41  4611.8  238.16  4627.6  238.18  4648.6  236.13  4691.1  235.12
  4712.6  236.08    4741  234.66  4747.8  235.34  4768.8  234.51    4783  235.03
  4816.9  233.24  4839.7  235.18  4889.5  235.67    4932  234.77    4974  235.66
  4995.6  234.18  5009.6  234.51  5016.8  236.81  5073.4  239.77  5129.7  243.83
  5136.9  243.66    5158  245.92  5165.2  245.42  5193.6   246.5  5210.6  248.57
#Mann= 4 ,-1 , 0
  4257.8     .11       0  4611.8     .17       0    4974     .07       0
  5016.8     .17       0
Bank Sta=4974,5016.8
XS Rating Curve= 0 ,0
Exp/Cntr=0.3,0.1

Type RM Length L Ch R = 1 ,4770    ,78,78,78
BEGIN DESCRIPTION:
ATKINS CREEK 11.0
END DESCRIPTION:
XS GIS Cut Line= 3
      3761658.45     10143181.42      3761311.76     10142748.02
      3761022.85     10142419.36
#Sta/Elev= 30
    4445  244.97  4531.3  242.62  4688.2  234.91  4729.8  234.63  4737.8  235.68
  4752.3  234.18  4787.5  234.09  4793.9   232.8  4907.5  232.99  4915.5  232.08
  4921.9   233.6  4929.9  232.33  4936.3  233.08  4944.3  231.44  4965.2  231.23
  4971.6  229.66    4986  232.19    4994  231.01  5006.3     227  5009.8     227
  5014.7  229.85  5043.2  232.31  5078.3  234.01  5156.1  234.23  5163.7  235.55
  5170.3  234.62  5184.6  236.01  5276.6  238.62  5397.1  245.68  5437.6  249.31
#Mann= 3 , 0 , 0
    4445     .11       0    4986     .06       0  5043.2     .11       0
#XS Ineff= 2 , 0
       0  4921.9   233.6  5078.3       0  234.01
Permanent Ineff=
       T       T
Bank Sta=4986,5043.2
XS Rating Curve= 0 ,0
Exp/Cntr=0.3,0.1

Type RM Length L Ch R = 1 ,4692    ,431,431,431
BEGIN DESCRIPTION:
ATKINS CREEK 10.0
END DESCRIPTION:
XS GIS Cut Line= 3
      3761796.54      10143074.9       3761373.9     10142700.52
      3761137.61     10142346.08
#Sta/Elev= 30
  4435.8  241.97  4444.9   241.4    4480  241.66  4494.3  240.35  4500.9  240.63
  4536.9  238.52  4579.6  237.32  4635.6  234.54    4792  230.72  4898.3  231.37
  4912.5  230.72  4919.1  231.48  4947.6  230.78  4968.5  231.72  4982.7  230.06
  4994.5  225.27    5004  226.45  5011.8  230.72  5019.1  232.28  5055.1  231.56
  5061.1  230.63  5070.1   230.5  5076.1  231.48  5091.2  231.99  5163.3  233.23
    5192  234.83  5199.3  234.45  5292.5  239.01  5349.6  243.48  5426.4   247.6
#Mann= 3 , 0 , 0
  4435.8     .11       0  4968.5     .07       0  5019.1     .11       0
#XS Ineff= 2 , 0
       0                  5019.1       0  232.28
Permanent Ineff=
       F       T
Bank Sta=4968.5,5019.1
XS Rating Curve= 0 ,0
Exp/Cntr=0.3,0.1

Type RM Length L Ch R = 1 ,4261    ,783,783,783
BEGIN DESCRIPTION:
ATKINS CREEK 9.0
END DESCRIPTION:
XS GIS Cut Line= 3
      3761867.86     10143061.11       3761721.6     10142446.26
      3761417.89     10142161.11
#Sta/Elev= 30
    4368  242.27  4470.8  239.21    4625  232.47  4644.7  232.72  4686.7  229.88
  4739.3  230.88  4748.4  229.52  4781.4  230.51  4789.5  228.95  4799.8  228.82
  4823.6  229.94  4923.1  226.33  4943.7  229.04  4950.1   227.9  4974.5   228.3
  4984.8  227.99  4992.3  225.99  4995.5  223.35    4999  223.35  5006.1  226.86
  5020.3  228.51  5062.8  228.29    5077  229.14  5105.3   228.2  5140.9  229.69
  5147.8  229.03  5211.3  231.36  5253.8  233.45  5289.4  236.47  5416.6  241.88
#Mann= 3 , 0 , 0
    4368     .11       0  4974.5     .06       0  5020.3     .11       0
#XS Ineff= 2 , 0
       0  4781.4  230.51               0
Permanent Ineff=
       T       F
Bank Sta=4974.5,5020.3
XS Rating Curve= 0 ,0
Exp/Cntr=0.3,0.1

Type RM Length L Ch R = 1 ,3478    ,496,496,496
BEGIN DESCRIPTION:
ATKINS CREEK 7.0
END DESCRIPTION:
XS GIS Cut Line= 3
      3762545.26     10142625.21      3762162.91     10142212.09
      3761767.82     10141961.05
#Sta/Elev= 30
  4437.1  235.17  4466.6  233.55  4473.4  234.09  4509.2  231.76  4537.5  231.21
  4551.7  229.49  4565.4  230.01  4615.2  228.04  4641.4  227.74  4777.9  226.24
  4798.9  227.26  4841.4  225.21  4869.8  226.21  4883.9  225.23  4905.5  225.52
  4919.6  224.78  4933.3  226.45  4983.2  224.99  4997.3  220.74  5003.6  220.53
  5003.9  220.03  5007.4  220.03  5017.8  224.81  5069.2  224.62  5077.1  225.97
  5084.4  226.24  5090.3  225.31  5136.1  225.74    5236   225.3  5468.1  232.06
#Mann= 4 ,-1 , 0
  4437.1     .17       0  4641.4     .11       0  4933.3     .06       0
  5084.4     .11       0
#XS Ineff= 2 , 0
       0  4933.3  226.45  5084.4       0  226.24
Permanent Ineff=
       T       T
Bank Sta=4933.3,5084.4
XS Rating Curve= 0 ,0
Exp/Cntr=0.3,0.1

Type RM Length L Ch R = 1 ,2982    ,462,462,462
BEGIN DESCRIPTION:
ATKINS CREEK 6.0
END DESCRIPTION:
XS GIS Cut Line= 3
      3762718.44     10142535.35      3762591.82     10142036.98
      3762244.11     10141685.94
#Sta/Elev= 30
  4485.8  234.98  4717.2  226.96  4747.6  224.28  4779.1  224.12  4788.5  222.25
  4820.4  219.91  4832.5   220.4  4851.3  222.17  4870.4  220.85  4902.9  222.19
  4916.5  220.04  4923.6  222.35  4944.2  223.79  4957.4  223.04  4964.8  220.39
  4975.1  222.05  4985.5   222.1  4993.2  219.37  5014.1  219.68  5021.2  222.71
  5035.3  223.42  5077.7  221.98  5268.6  223.43  5296.9   222.5  5303.9  221.49
  5316.3  217.11  5325.2   217.8  5339.3  222.33    5410  228.91  5494.1  230.23
#Mann= 4 ,-1 , 0
  4485.8     .17       0  4832.5     .11       0  4944.2     .06       0
  5035.3     .11       0
#XS Ineff= 2 , 0
       0  4944.2  223.79  5035.3       0  223.42
Permanent Ineff=
       T       T
Bank Sta=4944.2,5035.3
XS Rating Curve= 0 ,0
Exp/Cntr=0.3,0.1

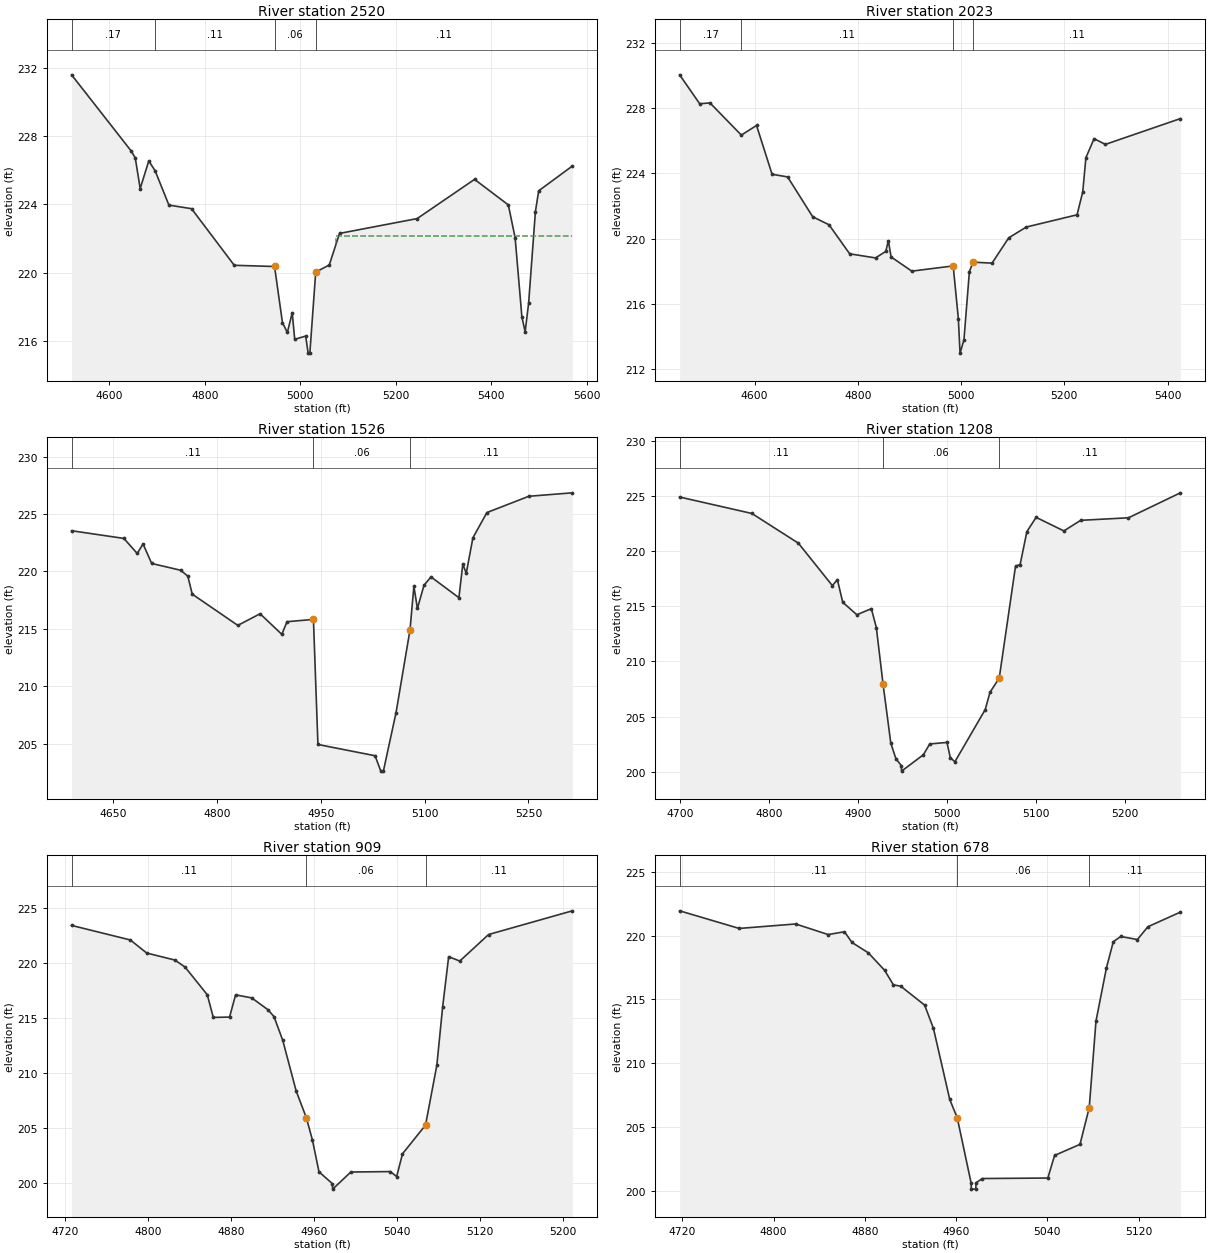
Type RM Length L Ch R = 1 ,2520    ,497,497,497
BEGIN DESCRIPTION:
ATKINS CREEK 5.0
END DESCRIPTION:
XS GIS Cut Line= 3
      3763090.83     10142360.86       3762980.1     10141894.63
      3762563.86     10141505.66
#Sta/Elev= 30
  4520.8   231.6  4645.5  227.14  4654.2  226.73  4664.5  224.93  4682.5  226.55
  4695.7  225.98  4724.7  223.96  4772.1  223.75  4861.6  220.43    4946  220.36
  4962.5  217.07  4972.8  216.49    4983  217.65  4988.2  216.09  5011.2  216.28
  5016.3  215.28  5019.9  215.28  5032.2  220.03  5060.6  220.45  5082.1   222.3
  5244.7  223.17  5364.9  225.47  5435.7  223.97  5449.9  222.05  5464.1   217.4
  5470.9  216.53  5478.2  218.21  5492.4  223.58  5499.3   224.8  5569.7  226.25
#Mann= 4 ,-1 , 0
  4520.8     .17       0  4695.7     .11       0    4946     .06       0
  5032.2     .11       0
#XS Ineff= 2 , 0
       0                  5074.7       0  222.12
Permanent Ineff=
       F       F
Bank Sta=4946,5032.2
XS Rating Curve= 0 ,0
Exp/Cntr=0.3,0.1

Type RM Length L Ch R = 1 ,2023    ,497,497,497
BEGIN DESCRIPTION:
ATKINS CREEK 4.0
END DESCRIPTION:
XS GIS Cut Line= 3
      3763411.15     10142299.73      3763372.97     10141755.77
      3763197.62     10141368.73
#Sta/Elev= 30
  4454.7  230.04  4493.5  228.27  4513.5  228.32  4574.2  226.35  4603.7  226.94
  4633.8  223.95  4663.9  223.79  4712.5  221.35  4744.1  220.86  4784.2  219.08
  4834.3  218.83  4854.1  219.23  4859.1  219.88  4864.4  218.89  4904.5  218.02
  4984.7  218.34  4994.7  215.12    4998     213  5005.5   213.8  5016.1  217.99
  5023.1  218.57    5060  218.51  5092.3  220.06  5126.4  220.72  5224.7  221.47
  5235.7  222.87  5241.9  224.97  5257.7  226.13  5279.6  225.78  5424.9  227.36
#Mann= 4 ,-1 , 0
  4454.7     .17       0  4574.2     .11       0  4984.7     .06       0
  5023.1     .11       0
#XS Ineff= 2 , 0
       0  4859.1  219.88               0
Permanent Ineff=
       F       F
Bank Sta=4984.7,5023.1
XS Rating Curve= 0 ,0
Exp/Cntr=0.3,0.1

Type RM Length L Ch R = 1 ,1526    ,318,318,318
BEGIN DESCRIPTION:
ATKINS CREEK 3.0
END DESCRIPTION:
XS GIS Cut Line= 3
      3763953.68     10142001.92      3763834.91     10141609.19
      3763790.49     10141298.85
#Sta/Elev= 30
  4589.7  223.54  4665.3  222.87  4684.6  221.56    4693  222.39  4705.5  220.69
  4747.3   220.1  4757.7  219.59  4764.1  218.02    4830   215.3  4862.2  216.31
  4893.6  214.52  4901.1  215.62  4939.3  215.82  4945.8  204.93  5028.4  203.95
  5036.7  202.61  5040.4  202.61  5058.7   207.7  5078.9  214.91  5084.5   218.7
  5089.6  216.77  5099.1  218.79  5109.2  219.52  5149.6  217.71  5155.2  220.63
  5160.2  219.84  5169.8  222.92    5190  225.12  5250.6  226.54  5313.5  226.84
#Mann= 3 , 0 , 0
  4589.7     .11       0  4939.3     .06       0  5078.9     .11       0
Bank Sta=4939.3,5078.9
XS Rating Curve= 0 ,0
Exp/Cntr=0.3,0.1

Type RM Length L Ch R = 1 ,1208    ,299,299,299
BEGIN DESCRIPTION:
ATKINS CREEK 2.0
END DESCRIPTION:
XS GIS Cut Line= 3
      3764276.58     10141772.75      3764134.43     10141507.66
      3764063.39     10141254.86
#Sta/Elev= 30
  4699.2  224.89  4780.5   223.4  4832.8  220.71    4871  216.87  4876.7   217.4
  4882.7  215.36  4898.6  214.23  4914.9  214.78  4920.5  213.07  4928.1  207.93
  4936.8   202.6  4942.5   201.2  4948.6  200.57  4948.9  200.07  4973.4  201.55
  4980.6  202.53    5000  202.67  5003.7  201.29  5008.9  200.92    5043  205.64
  5048.4  207.21  5058.8   208.5  5077.1  218.62  5082.3  218.78  5089.9  221.76
  5100.3  223.05  5131.5  221.82  5150.4  222.78  5204.2  223.01  5262.6  225.27
#Mann= 3 , 0 , 0
  4699.2     .11       0  4928.1     .06       0  5058.8     .11       0
Bank Sta=4928.1,5058.8
XS Rating Curve= 0 ,0
Exp/Cntr=0.3,0.1

Type RM Length L Ch R = 1 ,909     ,231,231,231
BEGIN DESCRIPTION:
ATKINS CREEK 2.5
END DESCRIPTION:
XS GIS Cut Line= 3
        3764511.     10141566.23      3764371.32     10141330.74
      3764275.32      10141145.2
#Sta/Elev= 30
  4726.2  223.45  4782.9  222.12  4798.6  220.93  4825.8  220.29  4835.6  219.65
    4857  217.13  4862.8  215.06  4878.5  215.09  4884.3  217.12  4899.9  216.84
  4915.5  215.76  4921.3  215.14  4929.8  212.96  4942.7  208.35  4952.5  205.91
  4958.4  203.87  4964.7  200.98  4977.6   199.9  4977.9   199.4  4995.4  200.96
  5033.4     201  5039.6  200.55  5045.2  202.62  5067.4  205.24  5078.3  210.69
  5083.9  216.01  5089.7   220.6  5100.4   220.2  5128.2  222.62  5208.9  224.78
#Mann= 3 , 0 , 0
  4726.2     .11       0  4952.5     .06       0  5067.4     .11       0
Bank Sta=4952.5,5067.4
XS Rating Curve= 0 ,0
Exp/Cntr=0.3,0.1

Type RM Length L Ch R = 1 ,678     ,262,262,262
BEGIN DESCRIPTION:
ATKINS CREEK 1.0
END DESCRIPTION:
XS GIS Cut Line= 3
      3764727.98      10141394.3      3764545.58     10141178.71
      3764460.66     10141047.13
#Sta/Elev= 30
  4717.6  221.94  4769.8  220.56  4819.3  220.91  4847.8  220.08  4862.1   220.3
  4868.7  219.46    4883  218.65  4897.3  217.28    4905  216.14  4911.5  216.03
  4932.4  214.55  4940.1  212.73  4954.4  207.16    4961  205.71  4973.1  200.63
  4973.4  200.13  4977.2  200.13  4977.5  200.63    4983  200.96  5040.4     201
  5046.3  202.77  5068.6  203.64  5076.7  206.52  5082.6  213.29  5091.8  217.48
  5097.8  219.52  5104.3  219.93  5118.9  219.69  5128.1  220.69  5156.6  221.84
#Mann= 3 ,-1 , 0
  4717.6     .11       0    4961     .06       0  5076.7     .11       0
Bank Sta=4961,5076.7
XS Rating Curve= 0 ,0
Exp/Cntr=0.3,0.1