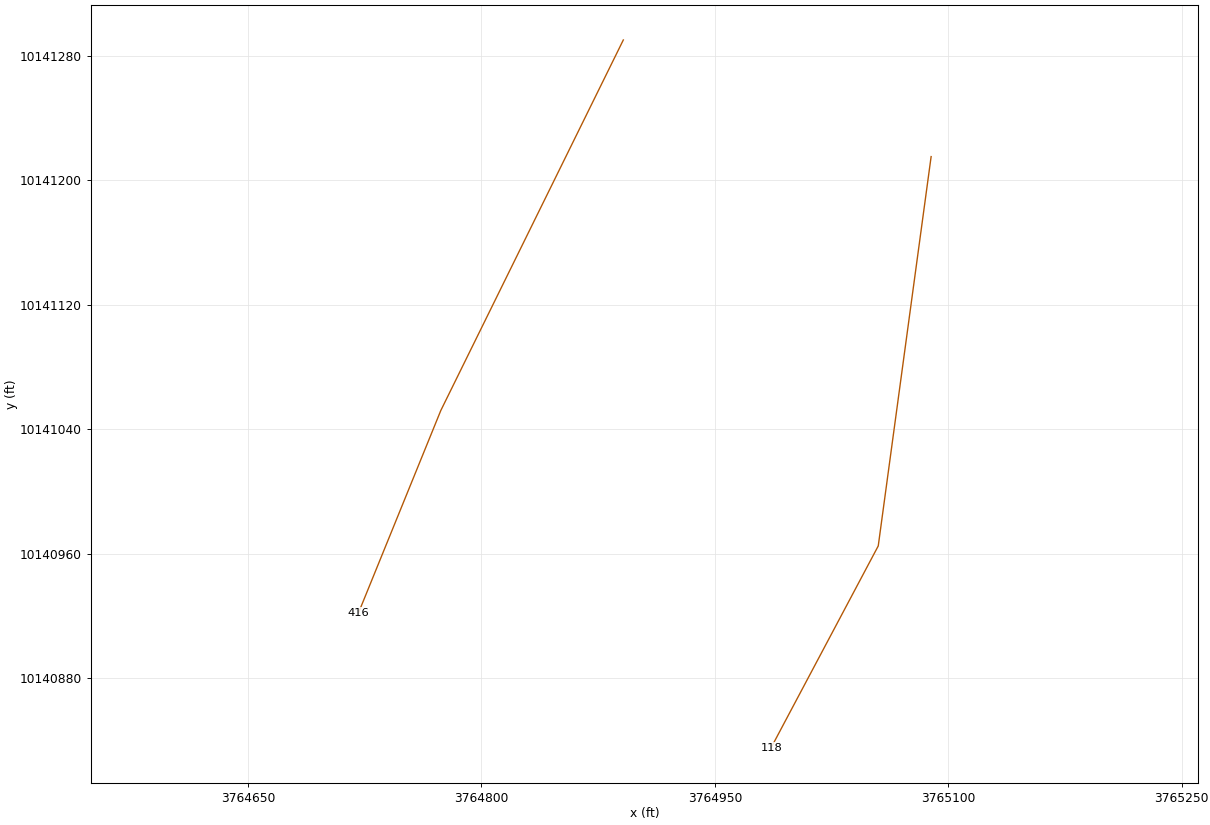
HEC-RAS study ATKINS CREEK.prj: ATKINS CREEK Base Level Engineering

--- ATKINS CREEK.g01 (geometry) --- (continued)

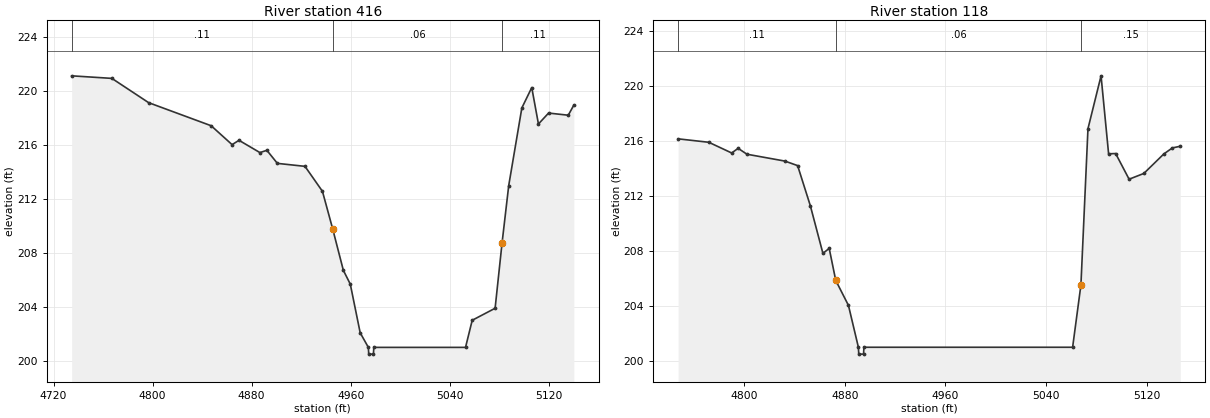
Type RM Length L Ch R = 1 ,416     ,298,298,298
BEGIN DESCRIPTION:
ATKINS CREEK 1.5
END DESCRIPTION:
XS GIS Cut Line= 3
       3764891.2     10141290.18      3764773.93      10141052.1
      3764721.07     10140922.14
#Sta/Elev= 30
  4734.6  221.13  4767.1  220.94  4796.8  219.14  4847.3  217.43  4864.2  216.03
  4869.8  216.35  4886.7  215.44  4892.3  215.61  4900.8  214.64  4923.1  214.42
  4937.2  212.57  4945.4  209.81  4954.1  206.71  4959.7  205.69  4967.7  202.08
  4974.3     201  4974.6   200.5  4978.4   200.5  4978.7     201  5052.8     201
  5058.2  203.01  5076.7   203.9  5082.3  208.73  5087.7     213  5098.3  218.75
  5106.3  220.26  5111.7  217.56  5119.9  218.37  5135.8  218.21  5140.3  218.96
#Mann= 3 , 0 , 0
  4734.6     .11       0  4945.4     .06       0  5082.3     .11       0
Bank Sta=4945.4,5082.3
XS Rating Curve= 0 ,0
Exp/Cntr=0.3,0.1

Type RM Length L Ch R = 1 ,118     ,0,0,0
BEGIN DESCRIPTION:
ATKINS CREEK 28.0
END DESCRIPTION:
XS GIS Cut Line= 3
        3765089.     10141215.24      3765055.02     10140965.04
      3764986.22     10140835.47
#Sta/Elev= 27
  4747.5  216.18  4771.9  215.93  4790.1  215.15  4795.2  215.49  4802.2  215.06
  4832.4  214.56  4842.5  214.23  4852.6  211.31  4862.6  207.84  4867.6   208.2
  4872.8  205.87  4882.9  204.05  4890.8     201  4891.1   200.5  4894.9   200.5
  4895.2     201  5061.1     201  5067.7  205.54  5073.3  216.92  5083.7  220.77
  5089.7  215.09  5095.3  215.11    5106  213.24  5117.7  213.66  5133.6  215.08
  5140.4  215.52  5146.7  215.64
#Mann= 3 , 0 , 0
  4747.5     .11       0  4872.8     .06       0  5067.7     .15       0
Bank Sta=4872.8,5067.7
XS Rating Curve= 0 ,0
Exp/Cntr=0.3,0.1

Chan Stop Cuts=-1
Use User Specified Reach Order=0
Composite Channel Slope=5