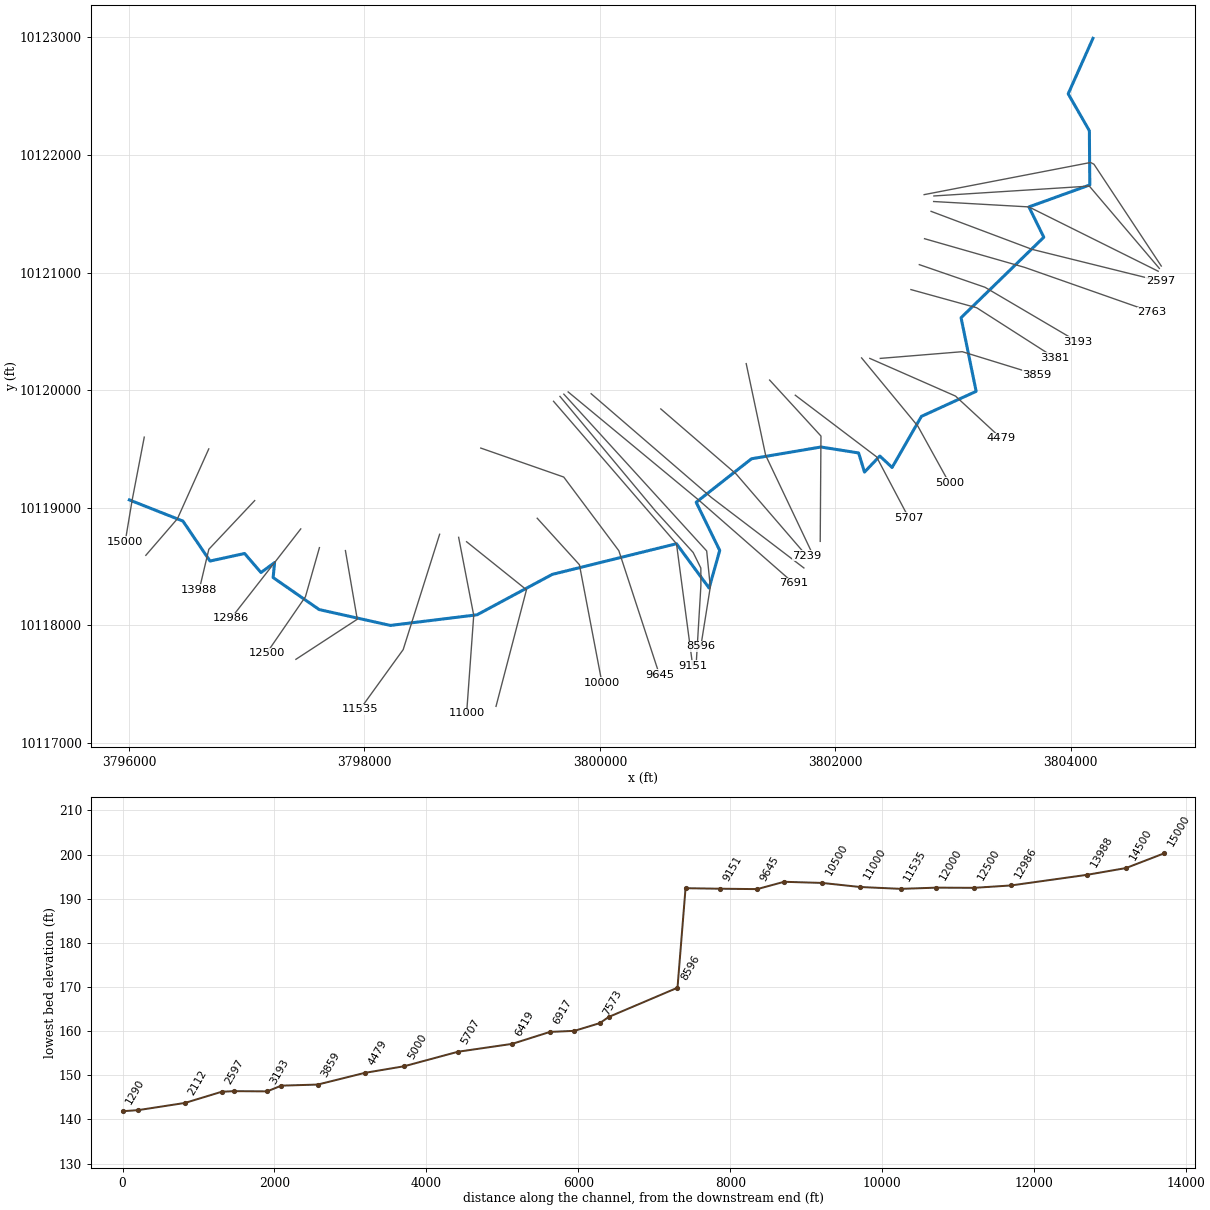
--- BASE CREEK.prj (project) ---

Proj Title=BASE CREEK Base Level Engineering
Current Plan=p01
Default Exp/Contr=0.3,0.1
English Units
Geom File=g01
Flow File=f01
Flow File=f02
Plan File=p01
Y Axis Title=Elevation
X Axis Title(PF)=Main Channel Distance
X Axis Title(XS)=Station
BEGIN DESCRIPTION:
BASE CREEK
END DESCRIPTION:
DSS Export Rating Curves= 0
DSS Export Rating Curve Sorted= 0
DSS Export Volume Flow Curves= 0
DXF OffsetX= 0
DXF OffsetY= 0
DXF ScaleX= 1
DXF ScaleY= 10

--- BASE CREEK.p01 (plan) ---

Plan Title=Multiple Run
Short Identifier=Multiple
Geom File=g01
Flow File=f01
Subcritical Flow
K Sum by GR= 0
Std Step Tol= 0.01
Critical Tol= 0.01
Num of Std Step Trials= 20
Max Error Tol= 0.3
Flow Tol Ratio= 0.001
Split Flow NTrial= 30
Split Flow Tol= 0.02
Split Flow Ratio= 0.02
Log Output Level= 0
Friction Slope Method= 1
Unsteady Friction Slope Method= 2
Unsteady Bridges Friction Slope Method= 1
Parabolic Critical Depth
Global Vel Dist=  1 , 1 , 1
Global Log Level= 0
CheckData=True
Encroach Param= -1, 0, 0, 0
BEGIN DESCRIPTION:
Multiple Run
END DESCRIPTION:

--- BASE CREEK.f01 (steady flow) ---

Flow Title=Multiple
Program Version=4.10
Number of Profiles= 7
Profile Names=10-year,25-year,50-year,1pct_min,100-year,1pct_plu,500-year
River Rch & RM=BASE CREEK,Reach-1         ,15000
     761    1041    1417     634    1915    5783    3617
River Rch & RM=BASE CREEK,Reach-1         ,13988
    1283    1800    2491    1132    3419   10325    6663
River Rch & RM=BASE CREEK,Reach-1         ,5707
    1263    1756    2415    1089    3290    9936    6318
Boundary for River Rch & Prof#=BASE CREEK,Reach-1         , 1
Up Type= 0
Dn Type= 3
Dn Slope=0.005
Boundary for River Rch & Prof#=BASE CREEK,Reach-1         , 2
Up Type= 0
Dn Type= 3
Dn Slope=0.005
Boundary for River Rch & Prof#=BASE CREEK,Reach-1         , 3
Up Type= 0
Dn Type= 3
Dn Slope=0.005
Boundary for River Rch & Prof#=BASE CREEK,Reach-1         , 4
Up Type= 0
Dn Type= 3
Dn Slope=0.005
Boundary for River Rch & Prof#=BASE CREEK,Reach-1         , 5
Up Type= 0
Dn Type= 3
Dn Slope=0.005
Boundary for River Rch & Prof#=BASE CREEK,Reach-1         , 6
Up Type= 0
Dn Type= 3
Dn Slope=0.005
Boundary for River Rch & Prof#=BASE CREEK,Reach-1         , 7
Up Type= 0
Dn Type= 3
Dn Slope=0.005
DSS Import GetInterval= 0
DSS Import GetPeak= 0
DSS Import FillOption= 0

--- BASE CREEK.f02 (steady flow) ---

Flow Title=Orig_BLE_Flow
Program Version=4.10
Number of Profiles= 7
Profile Names=10-year,25-year,50-year,1pct_min,100-year,1pct_plu,500-year
River Rch & RM=BASE CREEK,Reach-1         ,15000
     761    1021    1232     488    1473    4449    2103
River Rch & RM=BASE CREEK,Reach-1         ,13988
    1283    1765    2166     871    2630    7944    3874
River Rch & RM=BASE CREEK,Reach-1         ,5707
    1263    1722    2100     838    2531    7643    3673
Boundary for River Rch & Prof#=BASE CREEK,Reach-1         , 1
Up Type= 0
Dn Type= 3
Dn Slope=0.005
Boundary for River Rch & Prof#=BASE CREEK,Reach-1         , 2
Up Type= 0
Dn Type= 3
Dn Slope=0.005
Boundary for River Rch & Prof#=BASE CREEK,Reach-1         , 3
Up Type= 0
Dn Type= 3
Dn Slope=0.005
Boundary for River Rch & Prof#=BASE CREEK,Reach-1         , 4
Up Type= 0
Dn Type= 3
Dn Slope=0.005
Boundary for River Rch & Prof#=BASE CREEK,Reach-1         , 5
Up Type= 0
Dn Type= 3
Dn Slope=0.005
Boundary for River Rch & Prof#=BASE CREEK,Reach-1         , 6
Up Type= 0
Dn Type= 3
Dn Slope=0.005
Boundary for River Rch & Prof#=BASE CREEK,Reach-1         , 7
Up Type= 0
Dn Type= 3
Dn Slope=0.005
DSS Import GetInterval= 0
DSS Import GetPeak= 0
DSS Import FillOption= 0

--- BASE CREEK.g01 (geometry) ---

Geom Title=Existing Conditions
Program Version=4.10

River Reach=BASE CREEK      ,Reach-1
Reach XY= 30
      3796003.23     10119066.84      3796458.23     10118886.84
      3796688.23     10118546.84       3796981.9     10118611.23
      3797121.36     10118449.39      3797236.71     10118533.75
      3797224.66     10118406.35      3797615.48     10118134.32
      3798220.24      10117999.3      3798956.35     10118089.58
      3799595.24     10118433.33      3800650.81     10118694.26
      3800928.23     10118316.84      3801018.23     10118636.84
      3800818.23     10119046.84      3801288.23     10119416.84
      3801878.23     10119516.84       3802198.1     10119466.32
      3802248.01     10119303.55      3802378.22     10119440.27
      3802482.39     10119342.62      3802731.65     10119777.43
      3803196.44      10119990.3      3803068.35     10120616.62
      3803771.17     10121301.12      3803644.61     10121558.99
      3804161.93     10121745.67      3804158.23     10122206.84
      3803978.42     10122520.86      3804188.83     10122992.77

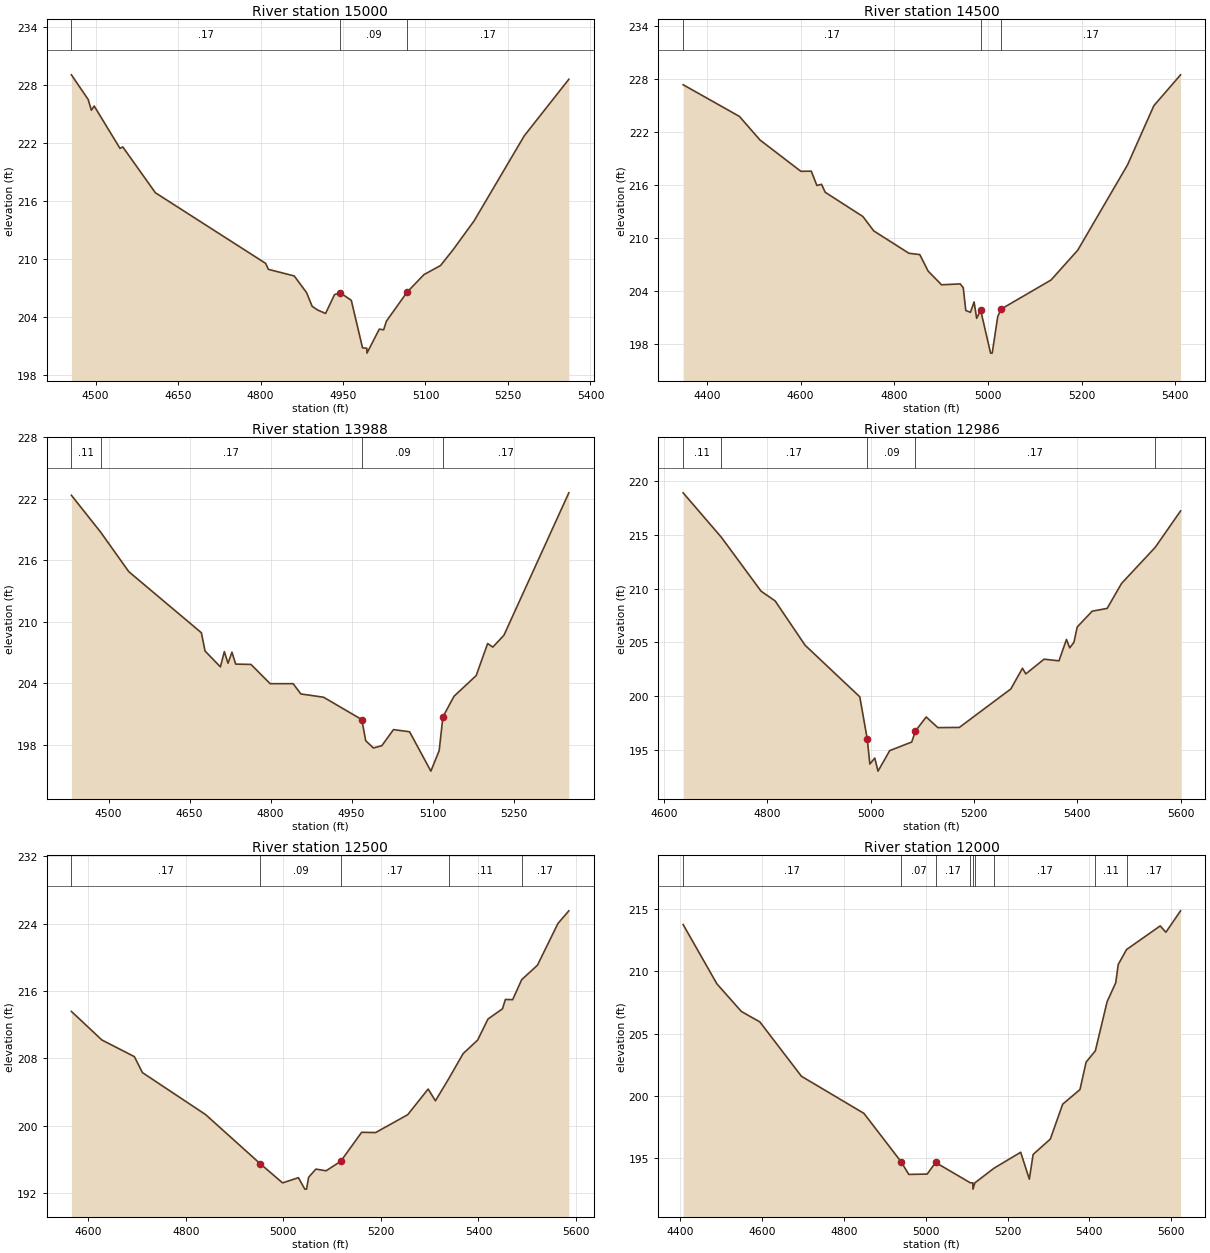
Type RM Length L Ch R = 1 ,15000   ,500,500,500
BEGIN DESCRIPTION:
BASE CREEK 28.0
END DESCRIPTION:
XS GIS Cut Line= 3
      3796129.84     10119600.98      3796027.25     10119066.84
      3795967.85     10118711.07
#Sta/Elev= 30
  4456.1  229.04  4486.6  226.49  4492.4  225.38  4497.5  225.82  4544.4  221.44
  4549.5  221.59  4608.8  216.85  4809.3  209.55  4814.4  208.93  4861.3  208.25
  4883.7  206.53  4893.9  205.11  4904.1  204.72  4918.3  204.37  4934.6  206.32
  4944.8  206.51  4965.1  205.73  4985.5  200.82  4993.3  200.77  4993.6  200.27
    5016  202.75  5023.9  202.68    5029  203.58  5066.7  206.58  5097.1  208.38
  5127.5  209.33  5150.5  210.98  5188.3  213.93  5279.6  222.73  5360.7  228.58
#Mann= 3 ,-1 , 0
  4456.1     .17       0  4944.8     .09       0  5066.7     .17       0
Bank Sta=4944.8,5066.7
XS Rating Curve= 0 ,0
Exp/Cntr=0.3,0.1

Type RM Length L Ch R = 1 ,14500   ,512,512,512
BEGIN DESCRIPTION:
BASE CREEK 27.0
END DESCRIPTION:
XS GIS Cut Line= 3
      3796677.75     10119500.78      3796411.69     10118906.84
       3796143.2     10118595.66
#Sta/Elev= 30
  4349.2  227.35  4469.4  223.76  4513.3  221.09  4600.6  217.54  4622.8  217.56
  4634.7  215.94  4644.7  216.07  4652.5  215.17    4733  212.42  4756.2  210.79
  4831.2  208.26  4854.4  208.11  4872.1  206.25  4900.8  204.69  4940.6  204.79
  4947.1  204.37  4952.6  201.78  4962.5  201.57  4970.3  202.75  4975.8  200.89
  4984.4   201.8  5005.5  196.95    5009  196.95  5020.8   201.1  5028.1  201.94
  5134.5  205.23  5191.6  208.61    5298  218.29    5354  224.97    5411  228.47
#Mann= 3 , 0 , 0
  4349.2     .17       0  4984.4     .09       0  5028.1     .17       0
Bank Sta=4984.4,5028.1
XS Rating Curve= 0 ,0
Exp/Cntr=0.3,0.1

Type RM Length L Ch R = 1 ,13988   ,1002,1002,1002
BEGIN DESCRIPTION:
BASE CREEK 26.0
END DESCRIPTION:
XS GIS Cut Line= 3
      3797067.87     10119061.09      3796678.23     10118646.84
      3796597.22     10118304.19
#Sta/Elev= 30
  4431.3  222.33  4485.5  218.73  4537.5  214.88  4671.9  208.92  4678.7  207.14
  4707.1  205.59  4714.4  207.08  4721.2  205.95  4728.5  207.02  4735.4  205.86
  4763.7  205.83  4799.3  203.95  4841.8  203.95    4856  202.95  4898.1  202.63
  4968.8  200.45  4976.1  198.39  4990.3  197.68  5005.9   197.9  5027.5  199.47
  5057.3  199.26  5096.7  195.42  5112.1  197.42    5119  200.71  5139.5  202.72
  5180.6  204.74  5201.8  207.87  5211.4  207.52    5232  208.68  5352.1  222.57
#Mann= 4 ,-1 , 0
  4431.3     .11       0  4485.5     .17       0  4968.8     .09       0
    5119     .17       0
#XS Ineff= 2 , 0
       0  4728.5  207.02               0
Permanent Ineff=
       F       F
Bank Sta=4968.8,5119
XS Rating Curve= 0 ,0
Exp/Cntr=0.3,0.1

Type RM Length L Ch R = 1 ,12986   ,486,486,486
BEGIN DESCRIPTION:
BASE CREEK 25.0
END DESCRIPTION:
XS GIS Cut Line= 3
      3797459.21     10118820.31      3797236.71     10118533.75
      3796867.83     10118061.05
#Sta/Elev= 30
  4637.2  218.92  4710.9   214.8  4788.1  209.76  4815.2  208.86  4873.2  204.73
    4979  199.93  4993.5  195.99  4998.5  193.67    5008  194.23  5014.3  193.01
  5036.9  194.92  5079.5  195.72  5086.7  196.75  5107.5  198.05  5130.1  197.06
  5171.7  197.08  5271.2  200.66  5293.8  202.59  5300.2  202.06  5335.5  203.43
  5364.4  203.28  5378.9  205.27  5385.2  204.49  5393.3     205  5399.7  206.43
  5428.6   207.9  5457.6  208.16  5485.4  210.48  5550.7  213.85  5599.6  217.23
#Mann= 5 ,-1 , 0
  4637.2     .11       0  4710.9     .17       0  4993.5     .09       0
  5086.7     .17       0  5550.7     .11       0
#XS Ineff= 2 , 0
       0                  5335.5       0  203.43
Permanent Ineff=
       F       F
Bank Sta=4993.5,5086.7
XS Rating Curve= 0 ,0
Exp/Cntr=0.3,0.1

Type RM Length L Ch R = 1 ,12500   ,500,500,500
BEGIN DESCRIPTION:
BASE CREEK 24.0
END DESCRIPTION:
XS GIS Cut Line= 3
      3797617.86     10118661.11       3797499.1     10118243.46
      3797167.84     10117761.05
#Sta/Elev= 30
  4565.8  213.58  4628.2  210.19  4694.8  208.21  4711.4  206.31  4840.7  201.33
  4952.7  195.49  4998.6  193.21    5031  193.83  5044.1  192.47  5047.7  192.47
  5051.9  193.87  5066.8  194.85  5087.8  194.65  5117.6  195.77  5160.6  199.22
  5189.3  199.19    5255  201.31  5296.9  204.36  5311.8  202.96  5339.6  205.64
  5368.6  208.57  5398.4  210.18  5419.4  212.67  5449.2  213.89  5455.2     215
  5470.1  214.98  5488.6  217.35  5520.9  219.07  5562.8  224.02  5585.2  225.53
#Mann= 5 ,-1 , 0
  4565.8     .17       0  4952.7     .09       0  5117.6     .17       0
  5339.6     .11       0  5488.6     .17       0
Bank Sta=4952.7,5117.6
XS Rating Curve= 0 ,0
Exp/Cntr=0.3,0.1

Type RM Length L Ch R = 1 ,12000   ,465,465,465
BEGIN DESCRIPTION:
BASE CREEK 23.0
END DESCRIPTION:
XS GIS Cut Line= 3
      3797838.61     10118635.94      3797939.21     10118051.84
      3797417.89      10117711.1
#Sta/Elev= 30
  4407.3  213.75  4489.8  208.99  4549.7  206.77  4594.9  205.93  4696.4  201.57
  4849.2  198.59  4939.9  194.71  4958.8  193.69  5003.8  193.72  5024.2  194.65
    5109  193.02  5115.3  193.01  5115.6  192.51  5120.1  193.01    5167  194.19
  5232.2  195.47  5253.3  193.31  5262.5  195.29  5304.6  196.53  5334.8  199.33
    5377   200.5  5392.1  202.71  5414.6  203.61  5443.4  207.56  5464.5  209.08
  5470.5  210.54  5490.8  211.74  5573.1  213.64    5587  213.13  5622.8  214.85
#Mann= 9 ,-1 , 0
  4407.3     .17       0  4939.9     .07       0  5024.2     .17       0
    5109     .11       0  5115.3     .11       0  5120.1     .11       0
    5167     .17       0  5414.6     .11       0  5490.8     .17       0
Bank Sta=4939.9,5024.2
XS Rating Curve= 0 ,0
Exp/Cntr=0.3,0.1

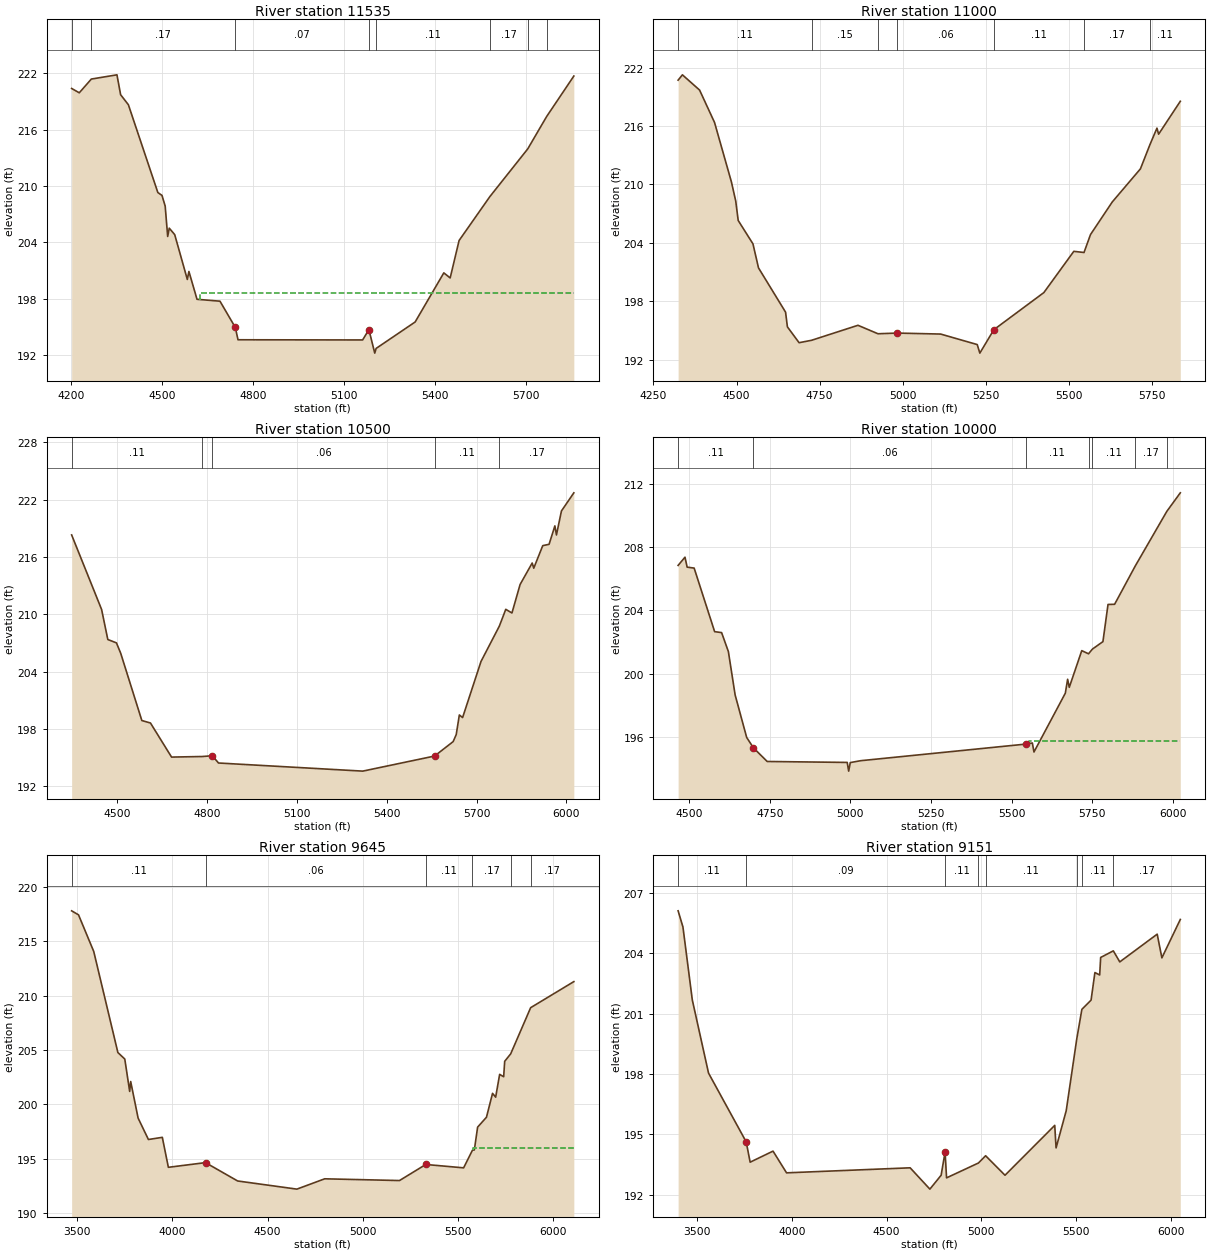
Type RM Length L Ch R = 1 ,11535   ,535,535,535
BEGIN DESCRIPTION:
BASE CREEK 22.0
END DESCRIPTION:
XS GIS Cut Line= 3
      3798638.93     10118774.75      3798329.21     10117793.61
      3797963.67      10117287.1
#Sta/Elev= 30
  4202.9  220.37    4228  219.91  4267.7  221.37  4352.1  221.82  4364.1  219.71
  4389.7  218.64  4486.7  209.31  4500.4     209  4510.9  207.86  4519.1  204.64
  4524.3  205.52  4542.3  204.83  4583.8  200.07    4589  200.92  4615.7  197.96
  4691.3  197.76  4741.6  194.98  4750.7  193.66    5161  193.64  5181.6  194.74
  5200.9  192.24  5205.4  192.74  5333.9  195.55  5428.3  200.77  5449.2  200.23
  5478.6  204.21    5580  208.88  5704.7  213.95  5766.7  217.38  5856.4  221.69
#Mann= 8 ,-1 , 0
  4202.9     .11       0  4267.7     .17       0  4741.6     .07       0
  5181.6     .11       0  5205.4     .11       0    5580     .17       0
  5704.7     .11       0  5766.7     .17       0
#XS Ineff= 2 ,-1
  4626.6  4605.2  198.65  4691.3  4626.6  197.76
Permanent Ineff=
       F       F
Bank Sta=4741.6,5181.6
XS Rating Curve= 0 ,0
Exp/Cntr=0.3,0.1

Type RM Length L Ch R = 1 ,11000   ,500,500,500
BEGIN DESCRIPTION:
BASE CREEK 21.0
END DESCRIPTION:
XS GIS Cut Line= 3
      3798800.41      10118748.7      3798928.51     10118085.16
      3798868.11     10117251.34
#Sta/Elev= 30
  4324.2  220.71  4337.1  221.26  4388.9  219.69  4433.8  216.37  4484.7  210.25
  4497.7  208.28  4505.1  206.29  4549.5  203.89  4566.2  201.42  4647.7  196.87
  4653.2  195.36  4688.4  193.73    4726  193.98  4865.6  195.52  4925.9  194.65
  4983.8  194.72  5114.4  194.62  5224.7  193.54  5232.5  192.66  5274.8  195.07
  5425.2  198.88  5515.4  203.12  5546.1     203  5565.6  204.84  5631.3   208.2
    5716   211.6  5744.5  214.08  5765.7  215.78  5770.7  215.16    5836  218.54
#Mann= 7 ,-1 , 0
  4324.2     .11       0    4726     .15       0  4925.9     .11       0
  4983.8     .06       0  5274.8     .11       0  5546.1     .17       0
  5744.5     .11       0
Bank Sta=4983.8,5274.8
XS Rating Curve= 0 ,0
Exp/Cntr=0.3,0.1

Type RM Length L Ch R = 1 ,10500   ,500,500,500
BEGIN DESCRIPTION:
BASE CREEK 20.0
END DESCRIPTION:
XS GIS Cut Line= 3
      3798867.84     10118711.08      3799376.68     10118302.62
      3799117.85     10117311.05
#Sta/Elev= 30
  4347.5  218.31  4447.5  210.51  4468.3  207.36  4497.1  207.01  4511.5  205.91
  4581.9  198.88  4610.7  198.62  4681.2  195.05  4784.3  195.11  4817.2  195.19
    4838  194.43  5319.8  193.58  5559.7  195.16  5621.7  196.67    5632  197.41
  5642.4  199.46  5653.3  199.19  5714.7  205.06  5776.1  208.77  5797.4  210.52
  5818.1  210.14  5845.3  213.12  5885.7  215.37  5890.9  214.83    5921  217.19
  5942.1  217.33  5961.5  219.26  5966.7  218.31  5983.4  220.82  6024.8  222.72
#Mann= 5 ,-1 , 0
  4347.5     .11       0  4784.3     .15       0  4817.2     .06       0
  5559.7     .11       0  5776.1     .17       0
Bank Sta=4817.2,5559.7
XS Rating Curve= 0 ,0
Exp/Cntr=0.3,0.1

Type RM Length L Ch R = 1 ,10000   ,355,355,355
BEGIN DESCRIPTION:
BASE CREEK 19.5
END DESCRIPTION:
XS GIS Cut Line= 3
      3799467.86     10118911.06      3799826.38     10118515.58
      3800017.85     10117511.06
#Sta/Elev= 30
  4466.2  206.85  4487.5  207.37  4494.2  206.74  4515.9  206.68  4579.4  202.66
    4601   202.6    4622   201.4  4642.9  198.66  4678.7  195.97  4699.7  195.31
  4742.3  194.45  4990.3  194.39  4994.8  193.84  4999.7  194.38  5032.3   194.5
  5544.1  195.55    5564  195.62  5569.1  195.05  5666.3  198.77  5673.4  199.65
  5678.5  199.14  5717.2  201.46  5738.1  201.26  5750.4  201.56  5782.8  202.03
  5798.6  204.38    5819  204.39  5882.9  206.81  5980.9  210.27  6022.6  211.44
#Mann= 7 ,-1 , 0
  4466.2     .11       0  4699.7     .06       0  5544.1     .11       0
  5738.1     .17       0  5750.4     .11       0  5882.9     .17       0
  5980.9     .11       0
#XS Ineff= 2 , 0
       0                  5554.3       0  195.73
Permanent Ineff=
       F       F
Bank Sta=4699.7,5544.1
XS Rating Curve= 0 ,0
Exp/Cntr=0.3,0.1

Type RM Length L Ch R = 1 ,9645    ,494,494,494
BEGIN DESCRIPTION:
BASE CREEK 19.0
END DESCRIPTION:
XS GIS Cut Line= 4
      3798988.37     10119507.85       3799693.2     10119261.34
      3800161.21     10118634.72      3800505.69     10117580.79
#Sta/Elev= 30
  3471.2  217.81  3507.3  217.44  3587.2  214.07    3714  204.76  3750.3  204.16
    3776  201.18  3781.3  202.09  3820.3  198.72  3874.4  196.75  3947.4  196.95
  3979.2  194.19  4174.2  194.62    4343  192.93  4654.2  192.18  4800.4  193.13
  5193.2  192.97  5331.2  194.45  5529.9  194.14  5576.2  195.76  5586.2  195.79
  5603.5  197.89  5649.9   198.8  5681.8     201  5698.2  200.65  5719.2  202.75
  5740.3  202.53  5745.6  203.95  5777.2  204.64    5882  208.89  6108.8  211.29
#Mann= 6 ,-1 , 0
  3471.2     .11       0  4174.2     .06       0  5331.2     .11       0
  5576.2     .17       0  5777.2     .11       0    5882     .17       0
#XS Ineff= 2 , 0
       0                  5580.9       0  195.95
Permanent Ineff=
       F       F
Bank Sta=4174.2,5331.2
XS Rating Curve= 0 ,0
Exp/Cntr=0.3,0.1

Type RM Length L Ch R = 1 ,9151    ,449,449,449
BEGIN DESCRIPTION:
BASE CREEK 18.0
END DESCRIPTION:
XS GIS Cut Line= 3
      3799606.55     10119905.71      3800650.81     10118694.26
       3800788.8     10117654.68
#Sta/Elev= 30
  3400.6  206.11    3426  205.31  3475.4  201.68    3561  198.04  3759.6  194.62
  3780.4  193.61  3901.1  194.16  3972.4  193.08  4624.1  193.33  4728.2  192.27
  4787.5  192.96  4808.4  194.12  4816.1  192.83  4984.4  193.57  5022.1  193.93
  5124.3  192.96  5386.6  195.44  5393.6  194.32  5447.1  196.17  5502.7  199.74
  5529.7  201.21  5578.2  201.67  5598.4  203.04  5623.6  202.92  5628.7  203.79
  5695.5  204.12  5729.5  203.57  5926.9  204.95  5951.5  203.77  6048.7  205.68
#Mann= 8 ,-1 , 0
  3400.6     .11       0  3759.6     .09       0  4808.4     .11       0
  4984.4     .15       0  5022.1     .11       0  5502.7     .17       0
  5529.7     .11       0  5695.5     .17       0
#XS Ineff= 2 , 0
       0                  5386.6       0  195.44
Permanent Ineff=
       F       F
Bank Sta=3759.6,4808.4
XS Rating Curve= 0 ,0
Exp/Cntr=0.3,0.1

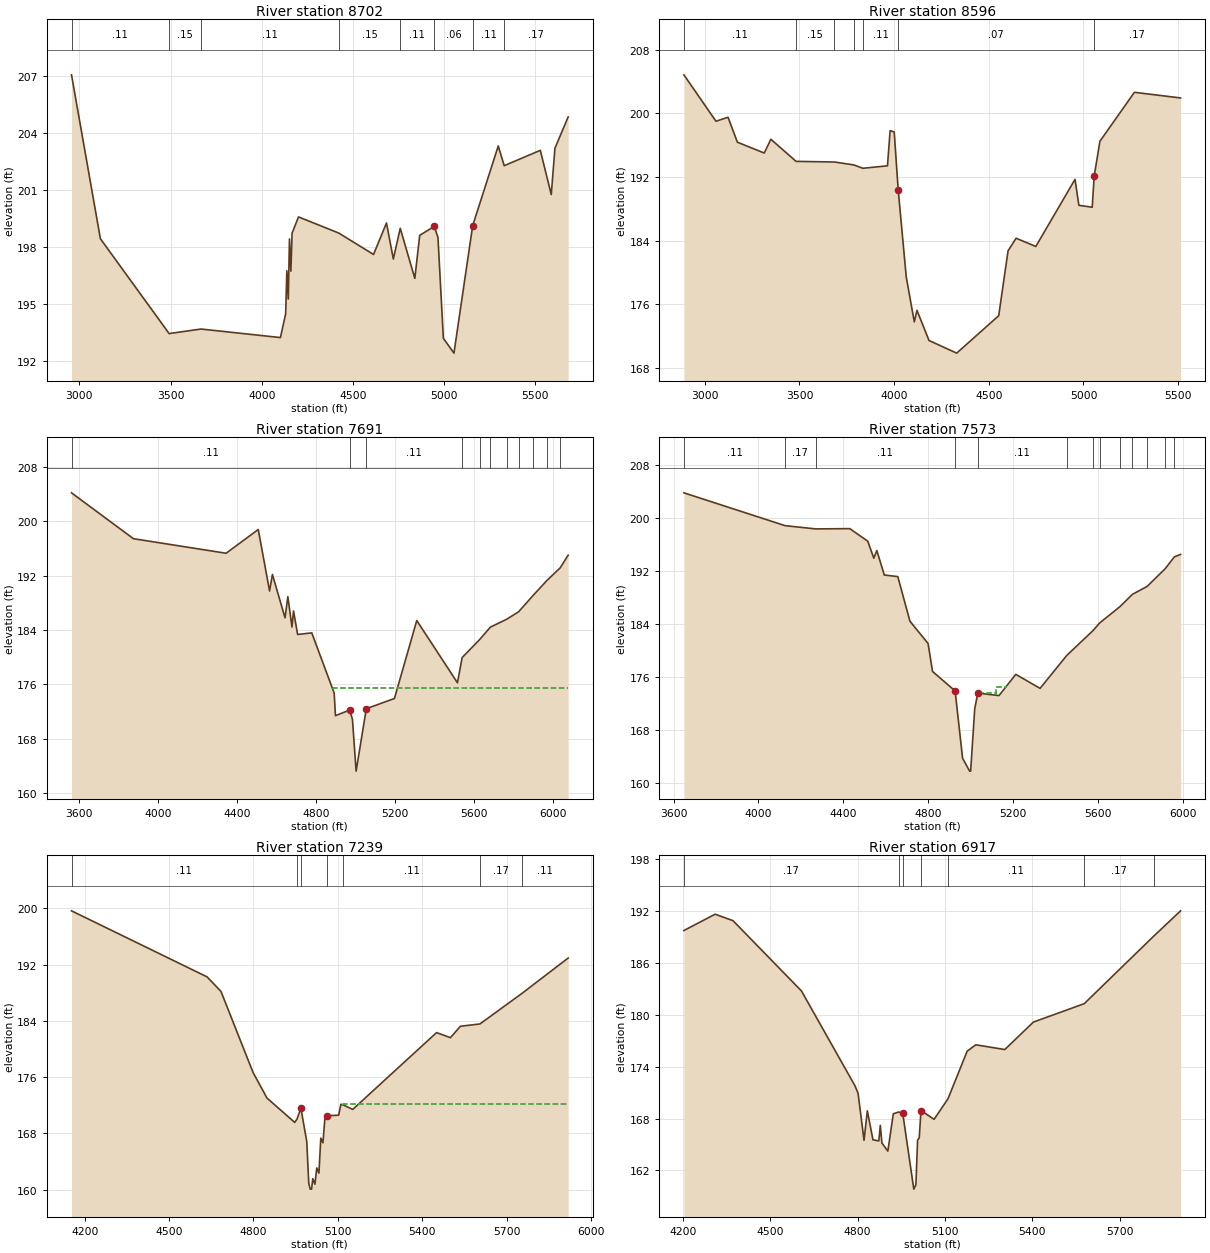
Type RM Length L Ch R = 1 ,8702    ,106,106,106
BEGIN DESCRIPTION:
BASE CREEK 16.5
END DESCRIPTION:
XS GIS Cut Line= 6
      3799661.07     10119947.22      3800474.74     10118969.86
      3800792.41     10118620.07      3800857.79     10118487.41
      3800858.23     10118336.84      3800817.62     10117658.56
#Sta/Elev= 30
  2957.3  207.06  3115.7  198.42  3492.5  193.42  3666.8  193.66  4102.4  193.21
  4131.1  194.46  4137.6  196.73  4145.4  195.24  4151.9  198.41  4159.7  196.71
  4166.2  198.71  4201.4  199.57    4422  198.72  4612.7  197.59  4683.6  199.25
  4721.2  197.35  4759.1  198.97    4839  196.33  4865.8   198.6  4945.8  199.07
  4965.8  198.49  4995.4  193.17  5053.5  192.39  5156.1  199.11  5296.3  203.31
  5328.9  202.27  5526.7  203.08  5586.8  200.75  5606.9  203.19  5679.5  204.84
#Mann= 8 ,-1 , 0
  2957.3     .11       0  3492.5     .15       0  3666.8     .11       0
    4422     .15       0  4759.1     .11       0  4945.8     .06       0
  5156.1     .11       0  5328.9     .17       0
Bank Sta=4945.8,5156.1
XS Rating Curve= 0 ,0
Exp/Cntr=0.3,0.1

Type RM Length L Ch R = 1 ,8596    ,905,905,905
BEGIN DESCRIPTION:
BASE CREEK 17.0
END DESCRIPTION:
XS GIS Cut Line= 4
      3799694.01     10119966.37      3800907.37     10118632.93
      3800938.23     10118326.84      3800857.46     10117820.24
#Sta/Elev= 30
  2889.5  204.86  3058.9  199.02  3122.6  199.52    3172  196.38  3313.9  195.02
    3349  196.75    3482  193.97  3684.9  193.89  3787.3  193.52  3834.9   193.1
  3964.8  193.41  3978.7  197.84  4000.4  197.67  4021.3  190.42  4063.9  179.43
  4106.5  173.77  4120.6  175.23  4184.2  171.43  4330.5  169.84  4552.4  174.55
  4601.7  182.71  4644.3   184.3  4748.3  183.26  4955.5  191.71  4975.7  188.44
  5046.4   188.2  5056.5  192.08  5086.9   196.5  5269.1  202.66    5513  201.95
#Mann= 7 ,-1 , 0
  2889.5     .11       0    3482     .15       0  3684.9     .11       0
  3787.3     .15       0  3834.9     .11       0  4021.3     .07       0
  5056.5     .17       0
Bank Sta=4021.3,5056.5
XS Rating Curve= 0 ,0
Exp/Cntr=0.3,0.1

Type RM Length L Ch R = 1 ,7691    ,118,118,118
BEGIN DESCRIPTION:
BASE CREEK 16.0
END DESCRIPTION:
XS GIS Cut Line= 3
      3799730.54      10119985.4      3800838.23     10119066.84
      3801646.14     10118358.44
#Sta/Elev= 30
    3561  204.17  3874.5  197.42  4343.4  195.28  4506.1  198.77  4563.4  189.73
  4577.8  192.16  4641.6  185.78  4655.9  188.89  4676.7  184.43  4684.6  186.78
  4705.4  183.33    4777  183.56  4890.3  174.71  4896.8  171.38  4968.5   172.2
  4982.8  170.86  5001.3  163.22    5053   172.4  5195.3  173.91  5308.3  185.38
  5514.2  176.22  5537.9  179.93  5627.1   182.6  5680.8  184.41  5762.9  185.56
  5823.7  186.67  5898.6  189.12  5966.6  191.26  6034.4  193.14  6074.5     195
#Mann= 11 ,-1 , 0
    3561     .11       0  4968.5     .06       0    5053     .11       0
  5537.9     .17       0  5627.1     .11       0  5680.8     .17       0
  5762.9     .11       0  5823.7     .17       0  5898.6     .11       0
  5966.6     .17       0  6034.4     .11       0
#XS Ineff= 4 ,-1
  4882.6  4869.5  175.39  4968.5  4882.6   172.2    5053  5159.3   172.4
  5308.3  5882.4  185.38
Permanent Ineff=
       F       F       F       F
Bank Sta=4968.5,5053
XS Rating Curve= 0 ,0
Exp/Cntr=0.3,0.1

Type RM Length L Ch R = 1 ,7573    ,334,334,334
BEGIN DESCRIPTION:
BASE CREEK 15.0
END DESCRIPTION:
XS GIS Cut Line= 3
      3799925.84     10119970.13      3800948.23     10119086.84
      3801733.21      10118488.2
#Sta/Elev= 30
  3648.9  203.78  4125.2  198.83  4269.2  198.34  4429.9  198.38  4514.4  196.49
  4542.9  193.93  4557.2  195.07  4592.3  191.39  4655.9  191.15    4713  184.43
  4798.5  181.06  4819.4  176.85  4925.8  173.91  4960.9  163.77  4994.1  161.82
  4998.8  161.82  5018.1  171.24  5032.6  173.58  5132.4  173.21  5211.3  176.41
  5325.7   174.3  5451.6  179.27  5574.6     183    5606  184.15  5702.4  186.64
  5760.3  188.47  5830.2  189.68  5914.7  192.34  5958.1  194.13  5987.2  194.49
#Mann= 13 ,-1 , 0
  3648.9     .11       0  4125.2     .17       0  4269.2     .11       0
  4925.8     .06       0  5032.6     .11       0  5451.6     .17       0
  5574.6     .11       0    5606     .17       0  5702.4     .11       0
  5760.3     .17       0  5830.2     .11       0  5914.7     .17       0
  5958.1     .11       0
#XS Ineff= 2 ,-1
  5032.6  5117.9  173.58  5117.9  5167.7  174.57
Permanent Ineff=
       F       F
Bank Sta=4925.8,5032.6
XS Rating Curve= 0 ,0
Exp/Cntr=0.3,0.1

Type RM Length L Ch R = 1 ,7239    ,322,322,322
BEGIN DESCRIPTION:
BASE CREEK 13.5
END DESCRIPTION:
XS GIS Cut Line= 3
      3800517.71     10119840.74      3801158.23     10119286.84
       3801757.3     10118590.73
#Sta/Elev= 30
  4153.2  199.63  4635.1  190.24  4684.5  188.17  4798.5  176.65  4847.9  173.02
  4946.6  169.55    4955  170.06  4968.5  171.58  4989.4  166.82  4996.4  160.91
  5001.6  160.07  5006.5  160.07  5010.6  161.56  5018.3  160.77  5024.9  163.08
  5032.6  162.35  5039.2  167.32  5046.8  166.66  5053.4  169.93  5060.4  170.51
  5102.8  170.58  5110.5  172.13  5119.8  172.02  5152.7   171.4  5450.6  182.32
    5500   181.6  5535.3  183.22  5604.8  183.55  5755.1  187.92  5918.4  192.92
#Mann= 7 ,-1 , 0
  4153.2     .11       0    4955     .15       0  4968.5     .09       0
  5060.4     .15       0  5119.8     .11       0  5604.8     .17       0
  5755.1     .11       0
#XS Ineff= 2 , 0
       0                  5117.1       0  172.14
Permanent Ineff=
       F       F
Bank Sta=4968.5,5060.4
XS Rating Curve= 0 ,0
Exp/Cntr=0.3,0.1

Type RM Length L Ch R = 1 ,6917    ,498,498,498
BEGIN DESCRIPTION:
BASE CREEK 14.0
END DESCRIPTION:
XS GIS Cut Line= 3
      3801243.15     10120226.05      3801408.23     10119446.84
       3801797.7     10118625.84
#Sta/Elev= 30
  4203.5  189.77  4310.8  191.66  4372.1  190.91  4607.2  182.77  4791.2  171.77
  4801.5  170.91  4821.9  165.48  4833.3  168.89  4852.6  165.54  4872.7  165.41
  4877.8  167.21  4883.2  165.18  4903.7  164.23  4922.4  168.55  4940.9  168.76
  4954.8  168.61  4992.8  159.83    5000  160.33  5005.8   165.5  5011.4  165.77
  5017.5  168.93  5062.4  167.91  5110.2  170.29    5176   175.8  5205.6  176.54
  5305.2  175.99  5403.4  179.17  5577.9   181.3  5816.9  189.13  5908.7  192.05
#Mann= 7 ,-1 , 0
  4203.5     .17       0  4940.9     .15       0  4954.8     .09       0
  5017.5     .15       0  5110.2     .11       0  5577.9     .17       0
  5816.9     .11       0
Bank Sta=4954.8,5017.5
XS Rating Curve= 0 ,0
Exp/Cntr=0.3,0.1

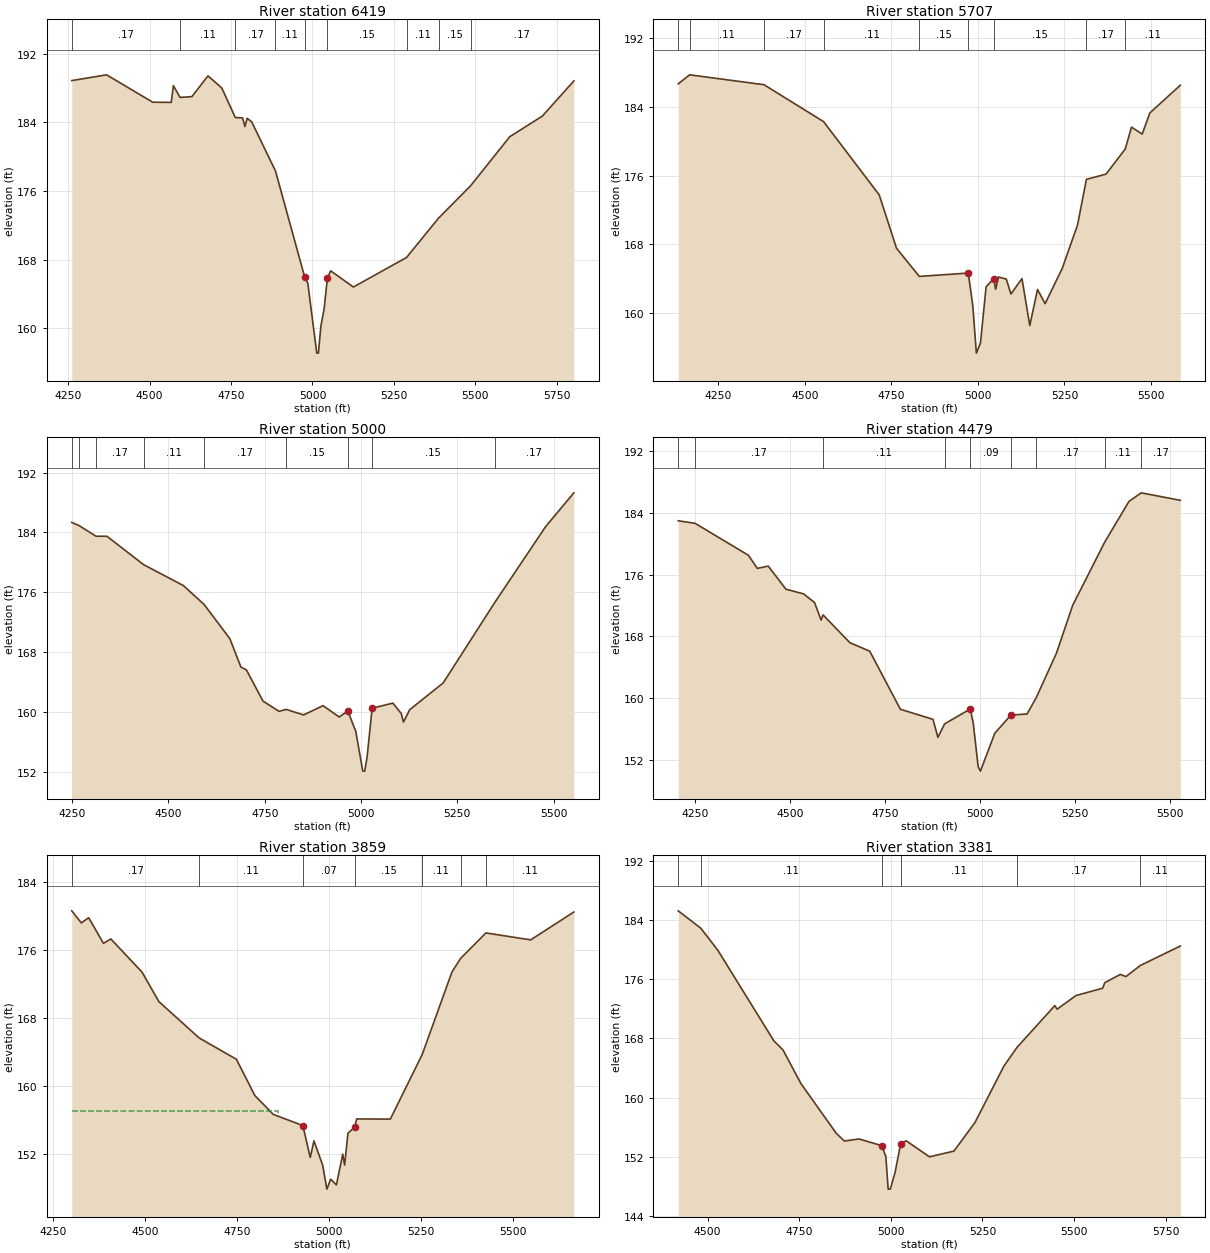
Type RM Length L Ch R = 1 ,6419    ,712,712,712
BEGIN DESCRIPTION:
BASE CREEK 13.0
END DESCRIPTION:
XS GIS Cut Line= 3
      3801442.13     10120086.36      3801878.22     10119610.04
      3801871.88     10118714.26
#Sta/Elev= 30
    4261  188.87  4367.8  189.54  4509.6  186.35  4566.4  186.33  4573.1  188.28
  4593.4  186.91  4629.9     187  4679.2  189.42  4721.8     188  4763.1  184.56
  4785.3  184.53  4792.7  183.52  4799.5  184.48  4813.6  184.05  4886.5  178.34
  4975.8  166.03  4985.8  165.24  5013.3  157.12  5018.3  157.12  5025.8  160.23
  5035.8  162.26  5045.8  165.82  5055.8  166.71  5125.8  164.82  5288.8  168.26
  5387.1  172.84  5485.5  176.61  5605.8  182.33  5705.8  184.73  5802.6  188.83
#Mann= 9 ,-1 , 0
    4261     .17       0  4593.4     .11       0  4763.1     .17       0
  4886.5     .11       0  4975.8     .09       0  5045.8     .15       0
  5288.8     .11       0  5387.1     .15       0  5485.5     .17       0
Bank Sta=4975.8,5045.8
XS Rating Curve= 0 ,0
Exp/Cntr=0.3,0.1

Type RM Length L Ch R = 1 ,5707    ,707,707,707
BEGIN DESCRIPTION:
BASE CREEK 11.0
END DESCRIPTION:
XS GIS Cut Line= 3
      3801660.14     10119957.25      3802350.01     10119433.76
      3802623.02     10118916.37
#Sta/Elev= 30
    4134  186.69    4167  187.74  4381.8  186.59  4554.1  182.29  4714.9  173.76
  4764.8  167.55  4830.8  164.27  4972.2  164.66  4985.3  160.87  4995.6  155.34
  5007.4  156.51  5023.8  163.07  5045.8     164  5051.4  162.78  5059.6   164.2
  5082.2  163.96  5095.5  162.22  5127.4  164.02    5150  158.55  5172.3  162.75
  5194.3   161.1    5244  165.23    5288  170.26  5313.6  175.57  5370.4  176.18
  5425.8   179.1    5444  181.65  5474.9  180.84  5496.9   183.3    5585  186.53
#Mann= 9 ,-1 , 0
    4134     .17       0    4167     .11       0  4381.8     .17       0
  4554.1     .11       0  4830.8     .15       0  4972.2     .09       0
  5045.8     .15       0  5313.6     .17       0  5425.8     .11       0
Bank Sta=4972.2,5045.8
XS Rating Curve= 0 ,0
Exp/Cntr=0.3,0.1

Type RM Length L Ch R = 1 ,5000    ,521,521,521
BEGIN DESCRIPTION:
BASE CREEK 10.0
END DESCRIPTION:
XS GIS Cut Line= 3
       3802223.3     10120274.72      3802700.87       10119695.
      3802967.86     10119211.06
#Sta/Elev= 30
  4248.9  185.33  4267.1  184.94  4311.9  183.49  4340.2  183.49  4435.4  179.69
  4538.7  176.89  4592.6  174.36  4659.4  169.79  4688.1  165.99  4702.5   165.6
  4745.5  161.43  4787.1  160.06  4805.8  160.32    4851  159.58  4901.4  160.82
  4943.5   159.3  4965.7  160.12  4986.5  157.36  5004.6  152.06  5009.7  152.06
  5015.9  153.98  5028.9  160.48  5082.8  161.16  5104.6  159.76  5110.3  158.62
  5126.4  160.28  5213.4  163.86  5346.9  174.59  5479.3  184.77  5552.7   189.3
#Mann= 9 ,-1 , 0
  4248.9     .17       0  4267.1     .11       0  4311.9     .17       0
  4435.4     .11       0  4592.6     .17       0  4805.8     .15       0
  4965.7     .09       0  5028.9     .15       0  5346.9     .17       0
Bank Sta=4965.7,5028.9
XS Rating Curve= 0 ,0
Exp/Cntr=0.3,0.1

Type RM Length L Ch R = 1 ,4479    ,620,620,620
BEGIN DESCRIPTION:
BASE CREEK 9.0
END DESCRIPTION:
XS GIS Cut Line= 3
      3802293.12     10120270.53        3803021.     10119950.08
      3803408.76     10119590.98
#Sta/Elev= 30
  4204.7  182.98  4249.2  182.65  4389.8  178.51  4413.2  176.81    4442  177.11
  4488.6  174.12  4535.3  173.51  4564.1  172.39  4581.4  170.12  4586.5  170.79
  4657.4  167.18  4709.6  166.09  4790.5  158.56  4876.4  157.26  4889.3  154.93
  4907.1  156.67  4974.7   158.6  4982.6  156.75  4995.5  151.14  5001.5  150.55
  5039.4  155.46  5081.9  157.81  5124.4  157.95  5148.7  160.07  5202.1  165.85
  5244.6  172.01  5329.1  180.21  5393.2  185.49  5425.4   186.6  5528.5  185.63
#Mann= 9 ,-1 , 0
  4204.7     .11       0  4249.2     .17       0  4586.5     .11       0
  4907.1     .15       0  4974.7     .09       0  5081.9     .15       0
  5148.7     .17       0  5329.1     .11       0  5425.4     .17       0
Bank Sta=4974.7,5081.9
XS Rating Curve= 0 ,0
Exp/Cntr=0.3,0.1

Type RM Length L Ch R = 1 ,3859    ,478,478,478
BEGIN DESCRIPTION:
BASE CREEK 8.0
END DESCRIPTION:
XS GIS Cut Line= 3
      3802382.08     10120270.52      3803078.34     10120327.57
      3803714.23     10120131.26
#Sta/Elev= 30
  4301.4  180.65  4327.3  179.23  4347.3  179.84  4387.5  176.82  4407.5  177.34
  4492.3  173.44    4538  169.97  4647.2   165.7  4748.7  163.18  4798.8  158.91
    4849  156.69  4929.3  155.38  4949.3  151.62  4959.4  153.58    4983  150.74
  4994.5   147.9  5004.9  149.07  5020.4   148.4  5037.6  152.02  5042.8  150.73
  5051.8  154.48  5070.2  155.21  5075.4  156.16  5166.9  156.14  5253.4  163.73
  5334.4  173.46  5357.9  175.05  5426.6  178.05  5548.2  177.23  5665.5  180.51
#Mann= 7 ,-1 , 0
  4301.4     .17       0  4647.2     .11       0  4929.3     .07       0
  5070.2     .15       0  5253.4     .11       0  5357.9     .17       0
  5426.6     .11       0
#XS Ineff= 2 , 0
       0  4861.6  157.13               0
Permanent Ineff=
       F       F
Bank Sta=4929.3,5070.2
XS Rating Curve= 0 ,0
Exp/Cntr=0.3,0.1

Type RM Length L Ch R = 1 ,3381    ,188,188,188
BEGIN DESCRIPTION:
BASE CREEK 6.0
END DESCRIPTION:
XS GIS Cut Line= 3
      3802642.38     10120855.83      3803201.28     10120701.19
      3803865.96     10120274.78
#Sta/Elev= 30
  4420.1  185.21  4481.6  182.87    4528   179.9  4680.8  167.68  4705.9  166.44
  4754.7  161.91  4851.2  155.19  4873.2  154.15  4913.4  154.43  4975.7  153.52
  4986.5  152.02  4992.8  147.66  4998.5  147.66  5011.6   149.9  5026.8  153.77
    5042  154.18  5105.4  152.02  5172.2  152.79  5229.7  156.66  5308.3  164.24
  5344.5   166.8  5447.4  172.42  5453.6  171.94  5505.2  173.78  5577.9  174.77
  5583.8  175.52  5626.1  176.63  5641.3  176.34  5680.8  177.84  5789.7  180.46
#Mann= 6 ,-1 , 0
  4420.1     .17       0  4481.6     .11       0  4975.7     .09       0
  5026.8     .11       0  5344.5     .17       0  5680.8     .11       0
Bank Sta=4975.7,5026.8
XS Rating Curve= 0 ,0
Exp/Cntr=0.3,0.1

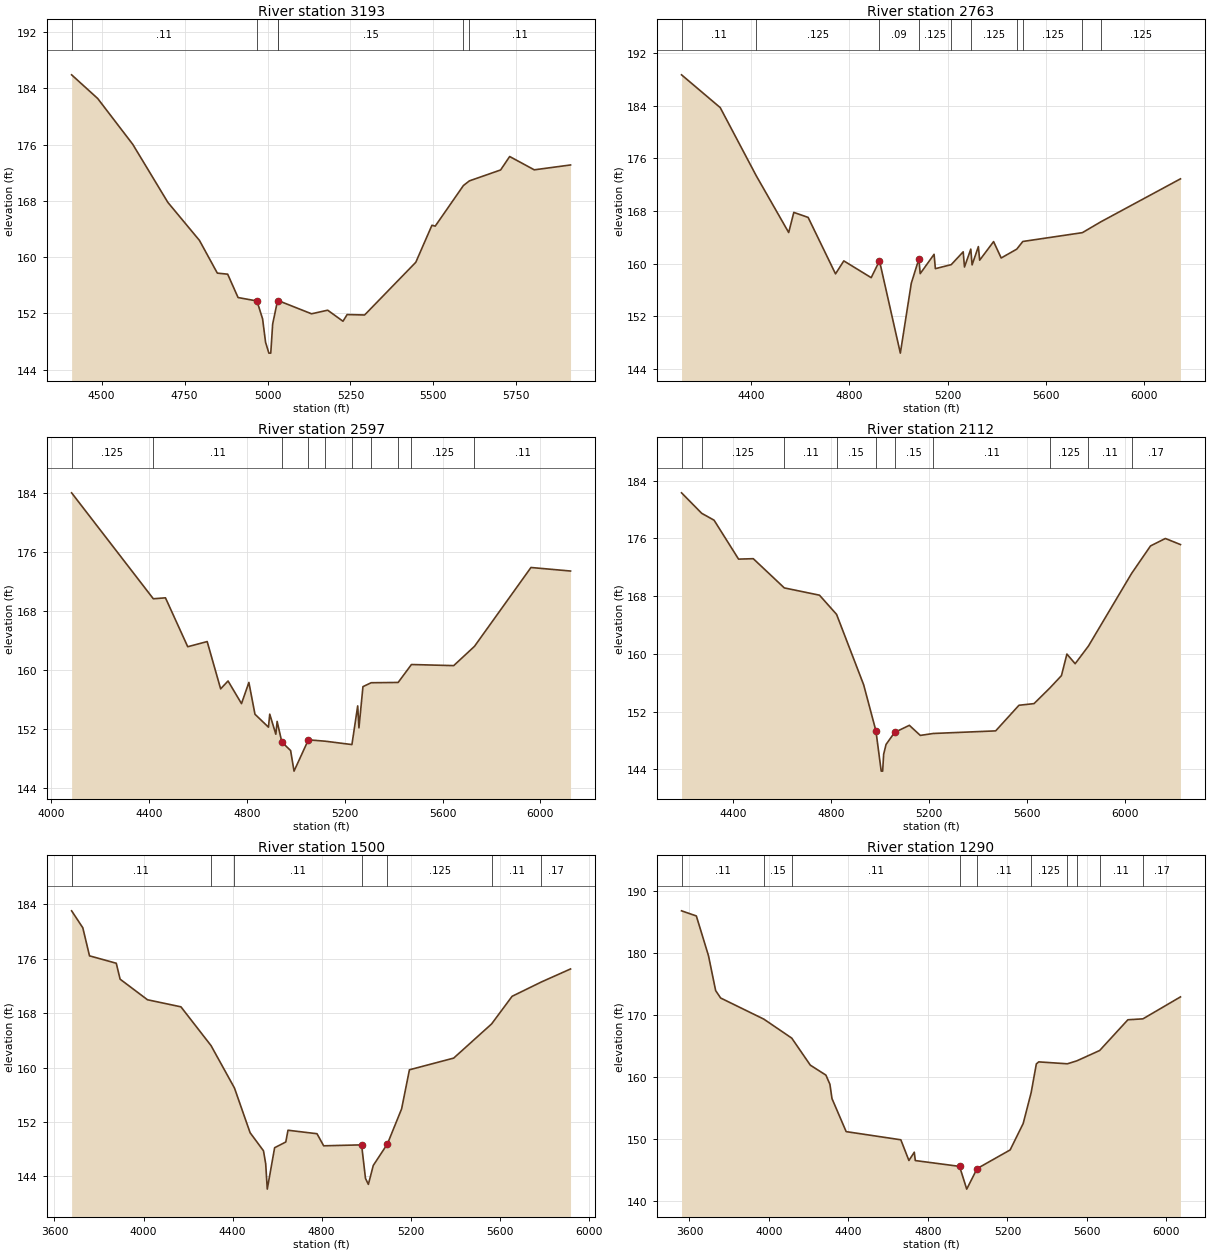
Type RM Length L Ch R = 1 ,3193    ,430,430,430
BEGIN DESCRIPTION:
Mapping XS d4de5b5f
END DESCRIPTION:
XS GIS Cut Line= 3
      3802713.55     10121068.02      3803271.82     10120875.32
      3804058.99     10120411.79
#Sta/Elev= 30
  4409.4  185.91    4488  182.55  4593.8  176.03  4699.6  167.78  4794.8  162.38
  4848.7  157.73  4879.9  157.58  4911.2  154.26  4968.2  153.77  4985.2  151.22
  4994.1   147.9  5004.1  146.36  5009.8  146.36  5015.5  150.49  5030.2  153.81
  5031.4  153.84  5132.7  151.95  5181.4  152.46  5227.5  150.89    5240  151.84
  5292.7  151.78    5447  159.27  5495.7  164.53  5505.6  164.41  5590.6  170.18
  5608.6  170.84  5702.7  172.39    5730   174.3  5804.2  172.41  5913.5   173.1
#Mann= 6 ,-1 , 0
  4409.4     .11       0  4968.2     .07       0  5030.2     .11       0
  5031.4     .15       0  5590.6     .17       0  5608.6     .11       0
Bank Sta=4968.2,5030.2
XS Rating Curve= 0 ,0
Exp/Cntr=0.3,0.1

Type RM Length L Ch R = 1 ,2763    ,166,166,166
BEGIN DESCRIPTION:
BASE CREEK 5.0
END DESCRIPTION:
XS GIS Cut Line= 3
      3802758.08     10121288.58      3803608.22     10121044.83
      3804692.03     10120663.61
#Sta/Elev= 30
  4115.6  188.71  4273.2  183.73  4419.6   173.4  4552.3  164.74  4573.1   167.8
  4631.5  167.04  4743.1  158.46  4776.9  160.43  4888.5  157.88  4922.3  160.44
  5007.3  146.41  5051.9  157.03  5082.9  160.73  5088.2  158.49  5144.8  161.43
  5150.1  159.25  5214.7  159.86  5263.4  161.81  5268.7   159.5  5294.4  162.22
  5299.7  159.82  5325.3   162.6  5330.6  160.54  5387.3  163.36  5418.3  160.87
  5481.9  162.22  5506.4  163.38  5749.1  164.72  5824.5  166.37  6148.9   172.9
#Mann= 10 ,-1 , 0
  4115.6     .11       0  4419.6    .125       0  4922.3     .09       0
  5082.9    .125       0  5214.7     .11       0  5294.4    .125       0
  5481.9     .11       0  5506.4    .125       0  5749.1     .11       0
  5824.5    .125       0
Bank Sta=4922.3,5082.9
XS Rating Curve= 0 ,0
Exp/Cntr=0.3,0.1

Type RM Length L Ch R = 1 ,2597    ,485,485,485
BEGIN DESCRIPTION:
BASE CREEK 4.0
END DESCRIPTION:
XS GIS Cut Line= 3
      3802813.56     10121521.25      3803671.68     10121197.95
      3804761.52     10120927.48
#Sta/Elev= 30
    4083     184  4417.1  169.64  4466.7  169.77  4557.8  163.14  4637.3  163.84
  4692.3  157.43  4722.6   158.5  4777.6  155.43  4807.8   158.3  4832.7  153.99
  4887.8  152.24  4893.1     154    4918  151.28  4923.3  153.02  4942.5  150.22
  4978.4  149.07  4992.4  146.28    5051  150.52  5118.9  150.34  5229.1  149.88
  5252.7  155.12  5257.8  152.15  5274.2  157.73  5307.8  158.26  5418.1   158.3
  5472.5  160.73  5645.2  160.58  5730.1  163.19  5961.1  173.88  6122.9   173.4
#Mann= 10 ,-1 , 0
    4083    .125       0  4417.1     .11       0  4942.5     .06       0
    5051     .15       0  5118.9    .125       0  5229.1     .11       0
  5307.8    .125       0  5418.1     .11       0  5472.5    .125       0
  5730.1     .11       0
Bank Sta=4942.5,5051
XS Rating Curve= 0 ,0
Exp/Cntr=0.3,0.1

Type RM Length L Ch R = 1 ,2112    ,612,612,612
BEGIN DESCRIPTION:
BASE CREEK 3.0
END DESCRIPTION:
XS GIS Cut Line= 3
      3802835.31     10121604.86      3803644.61     10121558.99
      3804742.97     10121011.83
#Sta/Elev= 30
  4189.4  182.32  4271.8  179.48  4322.2  178.53  4422.3  173.13  4482.4  173.19
  4609.1  169.14  4752.8  168.13  4822.6  165.47  4933.1  155.72  4983.2  149.34
  5004.9  143.74  5010.8  143.74  5014.8  146.08  5024.7  147.44  5059.5   149.1
  5119.8  150.09  5164.6  148.69  5217.7  148.96  5472.4  149.32  5567.5  152.87
  5629.1   153.1  5694.1  155.28    5741  156.98  5763.3  159.97    5797  158.63
  5851.4  161.09  6027.6  171.15  6104.8  174.96  6165.5  175.99  6227.1  175.15
#Mann= 10 ,-1 , 0
  4189.4     .11       0  4271.8    .125       0  4609.1     .11       0
  4822.6     .15       0  4983.2     .09       0  5059.5     .15       0
  5217.7     .11       0  5694.1    .125       0  5851.4     .11       0
  6027.6     .17       0
Bank Sta=4983.2,5059.5
XS Rating Curve= 0 ,0
Exp/Cntr=0.3,0.1

Type RM Length L Ch R = 1 ,1500    ,210,210,210
BEGIN DESCRIPTION:
BASE CREEK 3.5
END DESCRIPTION:
XS GIS Cut Line= 3
      3802837.61     10121652.12      3804157.95       10121736.
      3804752.72     10121035.95
#Sta/Elev= 30
    3677  183.05  3727.3  180.56  3757.4  176.43  3877.6  175.34  3894.9     173
  4017.9  169.97  4168.2  168.93  4303.4  163.23  4408.7  156.99  4478.9  150.42
    4539  147.76    4549  145.86  4556.1  142.12  4589.1  148.21  4639.2  149.05
  4649.2  150.78  4779.5  150.27  4809.5  148.49  4979.9  148.63  4997.4  143.69
  5010.3  142.82  5032.3   145.6    5096  148.78  5159.7  153.93  5194.8  159.67
  5393.6  161.39  5564.1  166.42  5656.1  170.48  5787.8  172.59  5918.6   174.5
#Mann= 7 ,-1 , 0
    3677     .11       0  4303.4     .15       0  4408.7     .11       0
  4979.9     .07       0    5096    .125       0  5564.1     .11       0
  5787.8     .17       0
Bank Sta=4979.9,5096
XS Rating Curve= 0 ,0
Exp/Cntr=0.3,0.1

Type RM Length L Ch R = 1 ,1290    ,378,378,378
BEGIN DESCRIPTION:
Mapping XS d960720b
END DESCRIPTION:
XS GIS Cut Line= 4
      3802754.74      10121663.4      3804168.23     10121936.84
      3804197.32      10121921.8      3804769.09       10121056.
#Sta/Elev= 30
  3560.3  186.87  3634.8  186.04  3695.9  179.61  3731.9  173.97    3757  172.77
  3974.5  169.35  4114.8  166.28  4208.2  161.91  4286.6   160.3  4306.7  158.82
  4317.2   156.5  4388.5  151.16  4663.5  149.84  4704.2  146.49  4731.2  147.83
  4736.3  146.48  4958.9  145.54    4995  141.86  5047.2  145.18  5213.4   148.2
    5279  152.47  5319.3  157.49  5345.2  162.11  5357.2  162.44  5501.4  162.13
  5549.1  162.61  5663.8  164.28  5805.8  169.25  5881.5   169.4  6070.3  172.95
#Mann= 10 ,-1 , 0
  3560.3     .11       0  3974.5     .15       0  4114.8     .11       0
  4958.9     .06       0  5047.2     .11       0  5319.3    .125       0
  5501.4     .11       0  5549.1    .125       0  5663.8     .11       0
  5881.5     .17       0
Bank Sta=4958.9,5047.2
XS Rating Curve= 0 ,0
Exp/Cntr=0.3,0.1