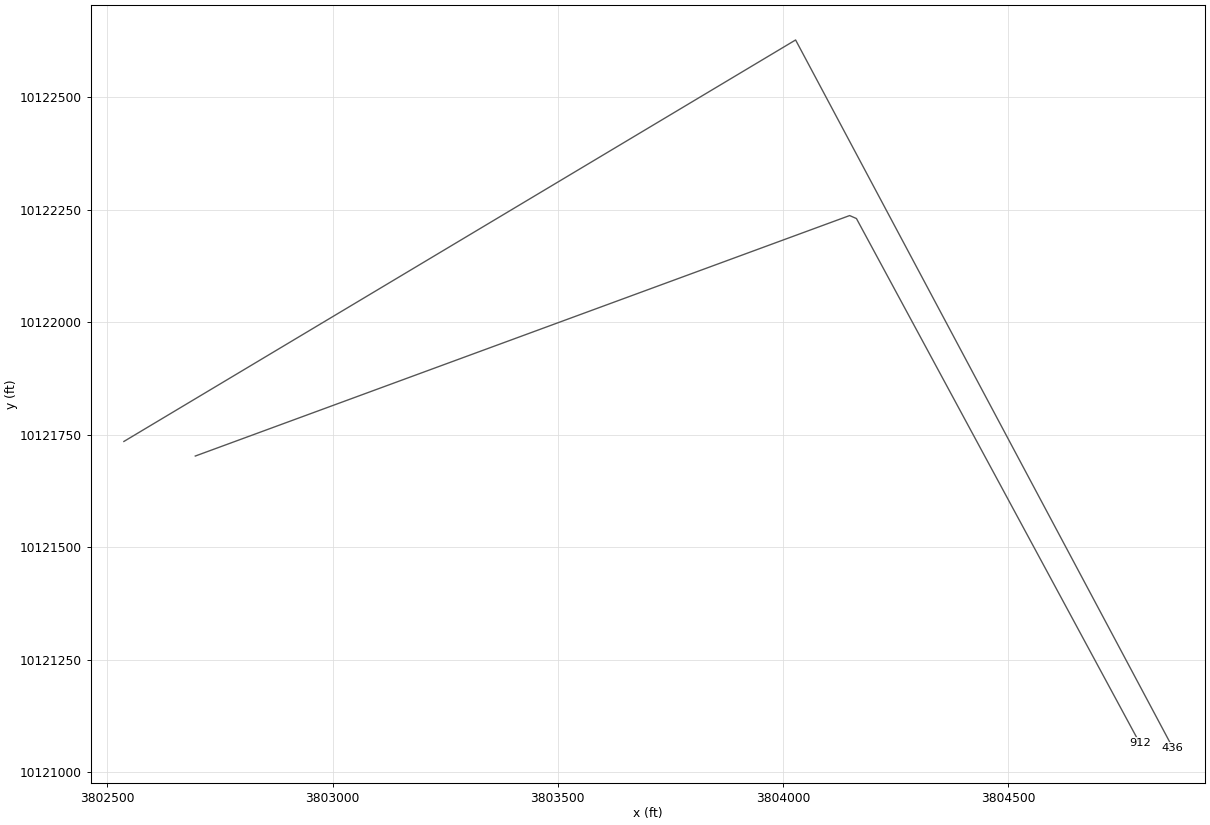
HEC-RAS study BASE CREEK.prj: BASE CREEK Base Level Engineering

--- BASE CREEK.g01 (geometry) --- (continued)

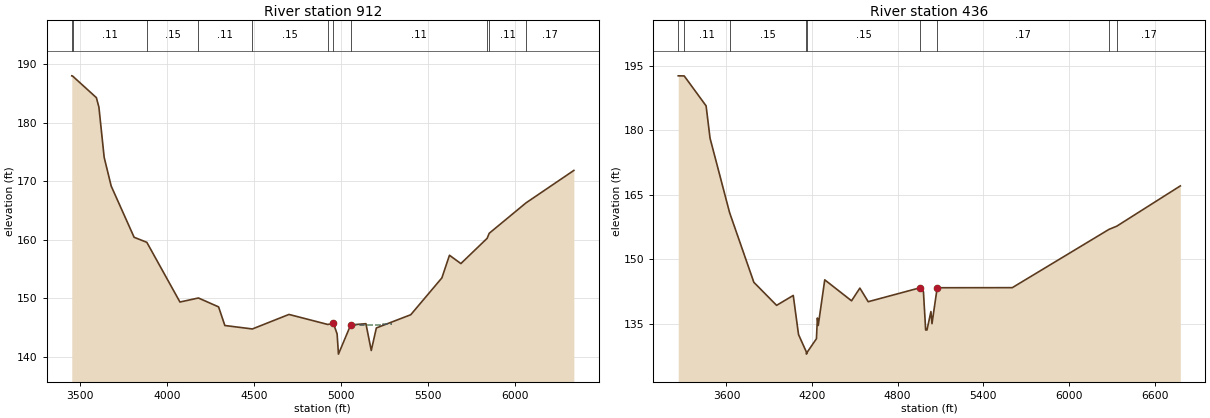
Type RM Length L Ch R = 1 ,912     ,476,476,476
BEGIN DESCRIPTION:
BASE CREEK 2.0
END DESCRIPTION:
XS GIS Cut Line= 4
      3802694.96     10121702.76      3804148.23     10122236.84
      3804163.35     10122230.24      3804792.34     10121065.53
#Sta/Elev= 30
  3451.7  188.02  3456.2  187.99  3593.3  184.29  3607.8  182.68  3638.2  174.08
  3678.5  169.19  3810.4  160.44  3883.5  159.58  4074.1  149.38  4180.3  150.07
  4296.4  148.55  4332.4  145.37  4490.8  144.78  4701.3  147.26  4924.4  145.55
    4957  145.73  4978.3  143.93  4985.9  140.48  5056.4  145.47    5144  145.68
  5174.7   141.1    5204  144.95    5402  147.21  5580.9   153.5  5624.7  157.37
  5690.3  155.95  5841.3  160.26  5853.3  161.12  6064.7  166.31  6340.2  171.86
#Mann= 11 ,-1 , 0
  3451.7    .125       0  3456.2     .11       0  3883.5     .15       0
  4180.3     .11       0  4490.8     .15       0  4924.4     .11       0
    4957     .06       0  5056.4     .11       0  5841.3     .17       0
  5853.3     .11       0  6064.7     .17       0
#XS Ineff= 4 ,-1
  4701.3  4301.9  147.26    4957  4762.9  145.73  5056.4  5242.1  145.47
  5242.1  5291.5  145.58
Permanent Ineff=
       F       F       F       F
Bank Sta=4957,5056.4
XS Rating Curve= 0 ,0
Exp/Cntr=0.3,0.1

Type RM Length L Ch R = 1 ,436     ,0,0,0
BEGIN DESCRIPTION:
BASE CREEK 1.0
END DESCRIPTION:
XS GIS Cut Line= 3
      3802536.41     10121735.15      3804028.23     10122626.84
      3804865.73     10121055.27
#Sta/Elev= 30
    3262  192.66  3303.8  192.64  3457.3  185.67    3485  178.14  3621.9  160.83
  3791.9  144.61  3951.4  139.24  4068.1  141.55  4105.1  132.45    4160  128.39
  4160.5  127.89    4167  128.39  4230.6  131.48  4237.4   136.3  4243.2  134.57
  4288.9  145.18  4476.7   140.3    4535  143.26  4593.4  140.09    4953   143.3
  4980.5  142.42  4996.1  133.51  5005.4  133.51    5033   137.8  5040.5  134.98
  5076.9  143.34  5603.3  143.36  6280.7  156.92    6335  157.66  6780.8  167.04
#Mann= 9 ,-1 , 0
    3262     .15       0  3303.8     .11       0  3621.9     .15       0
    4160     .12       0    4167     .15       0    4953     .07       0
  5076.9     .17       0  6280.7     .11       0    6335     .17       0
#XS Ineff= 2 , 0
       0    4953   143.3               0
Permanent Ineff=
       T       F
Bank Sta=4953,5076.9
XS Rating Curve= 0 ,0
Exp/Cntr=0.3,0.1

Chan Stop Cuts=-1
Use User Specified Reach Order=0
Composite Channel Slope=5