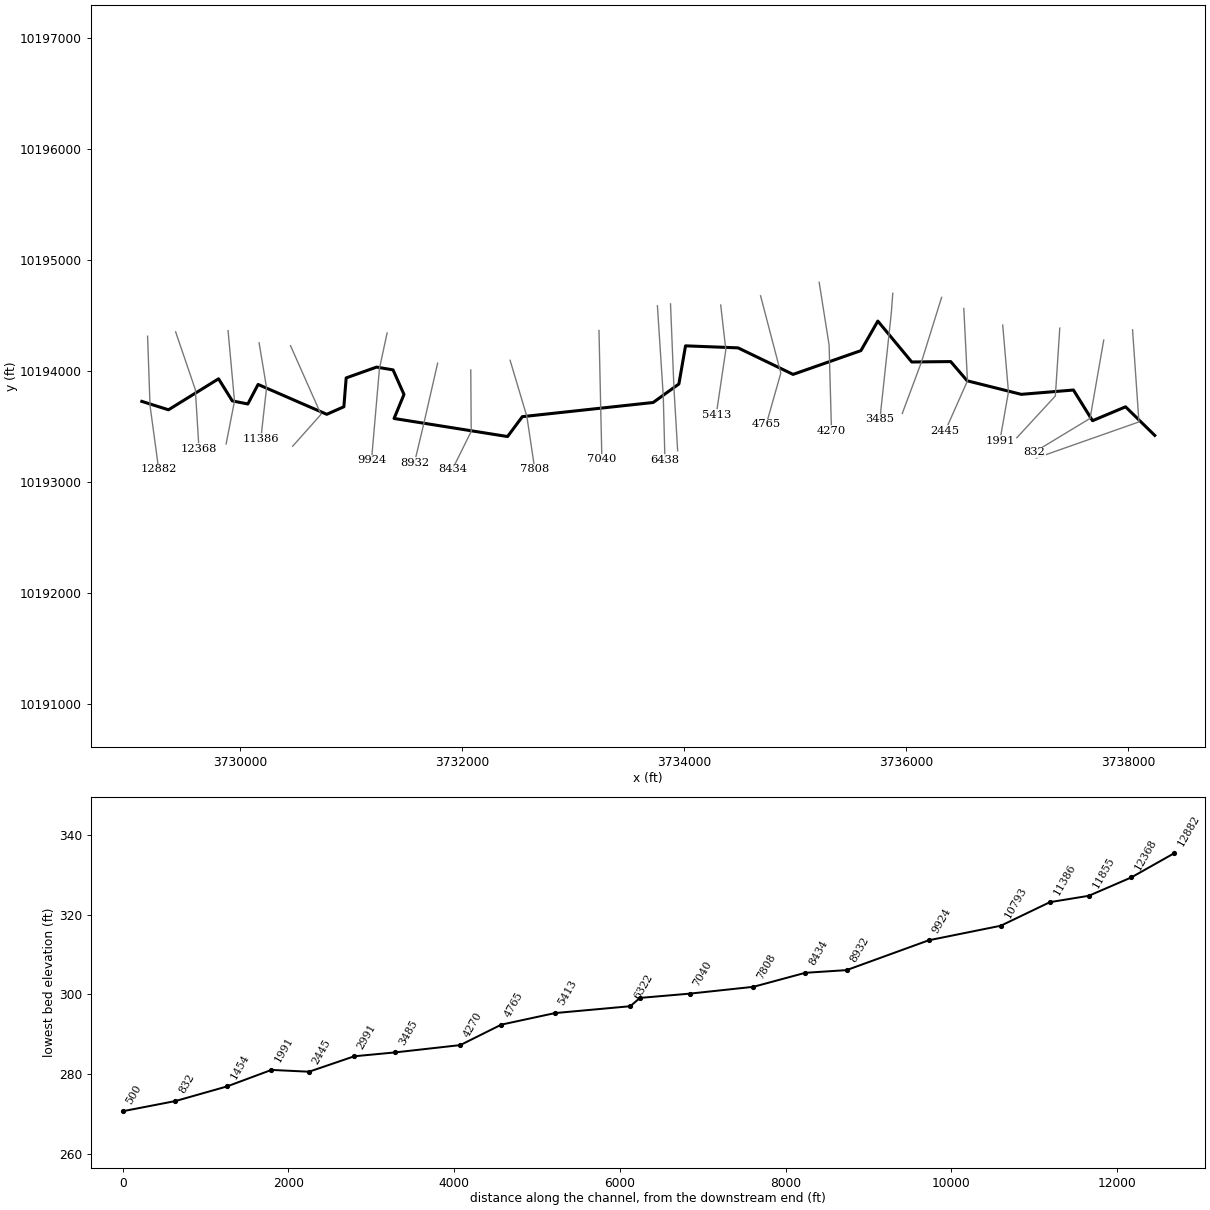
--- BAY BRANCH TRIBUTARY NO 1.prj (project) ---

Proj Title=BAY BRANCH TRIBUTARY NO 1 Base Level Engineering
Current Plan=p01
Default Exp/Contr=0.3,0.1
English Units
Geom File=g01
Flow File=f01
Flow File=f02
Plan File=p01
Y Axis Title=Elevation
X Axis Title(PF)=Main Channel Distance
X Axis Title(XS)=Station
BEGIN DESCRIPTION:
BAY BRANCH TRIBUTARY NO 1
END DESCRIPTION:
DSS File=dss
DSS Export Rating Curves= 0
DSS Export Rating Curve Sorted= 0
DSS Export Volume Flow Curves= 0
DXF OffsetX= 0
DXF OffsetY= 0
DXF ScaleX= 1
DXF ScaleY= 10

--- BAY BRANCH TRIBUTARY NO 1.p01 (plan) ---

Plan Title=Multiple Run
Program Version=4.10
Short Identifier=Multiple Run
Geom File=g01
Flow File=f01
Subcritical Flow
K Sum by GR= 0
Std Step Tol= 0.01
Critical Tol= 0.01
Num of Std Step Trials= 20
Max Error Tol= 0.3
Flow Tol Ratio= 0.001
Split Flow NTrial= 30
Split Flow Tol= 0.02
Split Flow Ratio= 0.02
Log Output Level= 0
Friction Slope Method= 1
Unsteady Friction Slope Method= 2
Unsteady Bridges Friction Slope Method= 1
Parabolic Critical Depth
Global Vel Dist= 1 , 1 , 1
Global Log Level= 0
CheckData=True
Encroach Param=-1 ,0,0, 0
BEGIN DESCRIPTION:
Multiple Run
END DESCRIPTION:
Computation Interval=1HOUR
Output Interval=1HOUR
Run HTab= 0
Run UNet= 0
Run PostProcess= 0
Run WQNet= 0
UNET Theta= 1
UNET Theta Warmup= 1
UNET ZTol= 0.02
UNET ZSATol= 0.05
UNET MxIter= 20
UNET MaxInSteps= 0
UNET DtIC= 0
UNET DtMin= 0
UNET MaxCRTS= 20
UNET WFStab= 2
UNET SFStab= 1
UNET WFX= 1
UNET SFX= 1
UNET DSS MLevel= 4
UNET DZMax Abort= 100
UNET Convert EG Bridges= 0
UNET Use Existing IB Tables=-1
UNET Froude Reduction=False
UNET Froude Limit= 1
UNET Froude Power= 10
UNET Time Slicing=0,0, 5
UNET Junction Losses=0
Instantaneous Interval=1HOUR
DSS File=dss
Write IC File= 0
Write IC File at Sim End=0
Echo Input=False
Echo Parameters=False
Echo Output=False
Write Detailed= 0
WQ AD Non Conservative
WQ ULTIMATE=-1
WQ Max Comp Step=1HOUR
WQ Output Interval=15MIN
WQ Output Selected Increments= 0
WQ Output face flow=0
WQ Output face velocity=0
WQ Output face area=0
WQ Output face dispersion=0
WQ Output cell volume=0
WQ Output cell surface area=0
WQ Output cell continuity=0
WQ Output cumulative cell continuity=0
WQ Output face conc=0
WQ Output face dconc_dx=0
WQ Output face courant=0
WQ Output face peclet=0
WQ Output face adv mass=0
WQ Output face disp mass=0
WQ Output cell mass=0
WQ Output cell source sink temp=0
WQ Output cell source sink nsm=0
WQ Output MaxMinRange=-1
WQ Daily Max Min Mean=-1
WQ Daily Range=0
WQ Daily Time=0
WQ Create Restart=0
WQ Fixed Restart=0
WQ System Summary=0
WQ Use Fixed Temperature=0
Sorting and Armoring Iterations= 10
XS Update Threshold= 0.02
Hydraulics Update Threshold= 0.02
Energy Slope Method= 1
Volume Change Method= 0
XS Weighting Method= 0
Number of US Weighted Cross Sections= 1
Number of DS Weighted Cross Sections= 1
Upstream XS Weight=0.25
Main XS Weight=0.5
Downstream XS Weight=0.25
Number of DS XS's Weighted with US Boundary= 1
Upstream Boundary Weight= 1
Weight of XSs Associated with US Boundary= 0
Number of US XS's Weighted with DS Boundary= 1
Downstream Boundary Weight= 0.5
Weight of XSs Associated with DS Boundary= 0.5
Sediment Output Level= 4
Mass or Volume Output= 0
Output Increment Type= 1
Profile and TS Output Increment= 10
XS Output Flag= 0
XS Output Increment= 10
Disregard all LS=0
Disregard all Conn=0
Disregard all Breaches=0
Disregard all Pumps=0

--- BAY BRANCH TRIBUTARY NO 1.f01 (steady flow) ---

Flow Title=Multiple
Program Version=4.10
Number of Profiles= 7
Profile Names=10-year,25-year,50-year,1pct_min,100-year,1pct_plu,500-year
River Rch & RM=BAY BRANCH TRIBU,Reach-1         ,12882
     473     633     850     376    1135    3428    2090
River Rch & RM=BAY BRANCH TRIBU,Reach-1         ,8434
     683     929    1258     561    1694    5116    3172
River Rch & RM=BAY BRANCH TRIBU,Reach-1         ,3485
     757    1034    1408     629    1899    5735    3581
Boundary for River Rch & Prof#=BAY BRANCH TRIBU,Reach-1         , 1
Up Type= 0
Dn Type= 3
Dn Slope=0.006
Boundary for River Rch & Prof#=BAY BRANCH TRIBU,Reach-1         , 2
Up Type= 0
Dn Type= 3
Dn Slope=0.006
Boundary for River Rch & Prof#=BAY BRANCH TRIBU,Reach-1         , 3
Up Type= 0
Dn Type= 3
Dn Slope=0.006
Boundary for River Rch & Prof#=BAY BRANCH TRIBU,Reach-1         , 4
Up Type= 0
Dn Type= 3
Dn Slope=0.006
Boundary for River Rch & Prof#=BAY BRANCH TRIBU,Reach-1         , 5
Up Type= 0
Dn Type= 3
Dn Slope=0.006
Boundary for River Rch & Prof#=BAY BRANCH TRIBU,Reach-1         , 6
Up Type= 0
Dn Type= 3
Dn Slope=0.006
Boundary for River Rch & Prof#=BAY BRANCH TRIBU,Reach-1         , 7
Up Type= 0
Dn Type= 3
Dn Slope=0.006
DSS Import GetInterval= 0
DSS Import GetPeak= 0
DSS Import FillOption= 0

--- BAY BRANCH TRIBUTARY NO 1.f02 (steady flow) ---

Flow Title=Orig_BLE_Flow
Program Version=4.10
Number of Profiles= 7
Profile Names=10-year,25-year,50-year,1pct_min,100-year,1pct_plu,500-year
River Rch & RM=BAY BRANCH TRIBU,Reach-1         ,12882
     473     621     739     289     873    2637    1215
River Rch & RM=BAY BRANCH TRIBU,Reach-1         ,8434
     683     911    1094     431    1303    3934    1844
River Rch & RM=BAY BRANCH TRIBU,Reach-1         ,3485
     757    1014    1224     484    1461    4412    2082
Boundary for River Rch & Prof#=BAY BRANCH TRIBU,Reach-1         , 1
Up Type= 0
Dn Type= 3
Dn Slope=0.006
Boundary for River Rch & Prof#=BAY BRANCH TRIBU,Reach-1         , 2
Up Type= 0
Dn Type= 3
Dn Slope=0.006
Boundary for River Rch & Prof#=BAY BRANCH TRIBU,Reach-1         , 3
Up Type= 0
Dn Type= 3
Dn Slope=0.006
Boundary for River Rch & Prof#=BAY BRANCH TRIBU,Reach-1         , 4
Up Type= 0
Dn Type= 3
Dn Slope=0.006
Boundary for River Rch & Prof#=BAY BRANCH TRIBU,Reach-1         , 5
Up Type= 0
Dn Type= 3
Dn Slope=0.006
Boundary for River Rch & Prof#=BAY BRANCH TRIBU,Reach-1         , 6
Up Type= 0
Dn Type= 3
Dn Slope=0.006
Boundary for River Rch & Prof#=BAY BRANCH TRIBU,Reach-1         , 7
Up Type= 0
Dn Type= 3
Dn Slope=0.006
DSS Import GetInterval= 0
DSS Import GetPeak= 0
DSS Import FillOption= 0

--- BAY BRANCH TRIBUTARY NO 1.g01 (geometry) ---

Geom Title=Existing Conditions
Program Version=4.10

River Reach=BAY BRANCH TRIBU,Reach-1
Reach XY= 30
       3729115.9      10193723.7      3729355.92     10193647.94
      3729807.01     10193927.11      3729930.58      10193728.1
       3730070.6     10193700.35      3730163.02     10193876.26
      3730781.14     10193607.26      3730935.33     10193675.22
      3730956.12     10193935.18      3731229.75     10194032.61
      3731378.19      10194007.5      3731476.72     10193786.17
      3731387.44     10193569.59      3732409.31     10193406.83
      3732542.45     10193586.02      3733720.39     10193713.72
      3733952.16     10193880.39      3734012.06     10194224.14
      3734484.82     10194205.98      3734980.17     10193966.93
      3735591.38     10194181.04      3735743.69     10194447.27
      3736048.98     10194078.74       3736399.7     10194082.31
       3736548.2     10193909.19      3737035.32      10193787.1
      3737505.14     10193826.04      3737676.95      10193549.7
      3737974.51      10193674.7      3738237.42     10193417.04

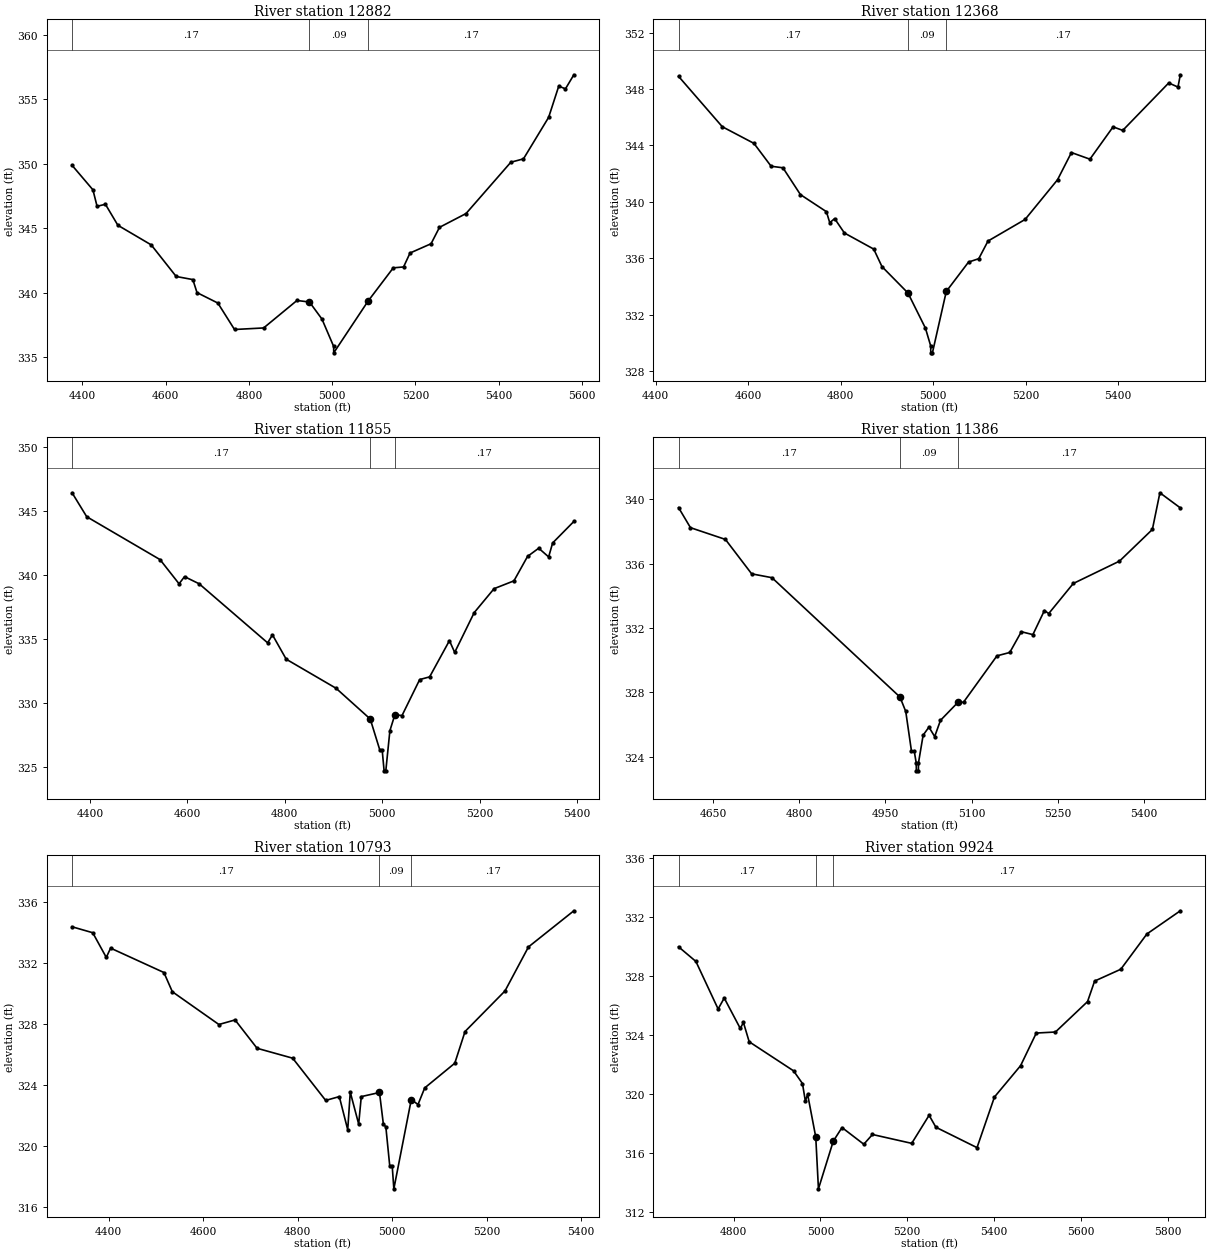
Type RM Length L Ch R = 1 ,12882   ,514,514,514
BEGIN DESCRIPTION:
BAY BRANCH TRIBUTARY NO 1 23.0
END DESCRIPTION:
XS GIS Cut Line= 3
      3729167.85     10194311.11      3729189.89      10193686.6
      3729267.85     10193111.05
#Sta/Elev= 30
  4375.1  349.87  4425.2  347.97  4435.2  346.69  4455.2  346.85  4485.2  345.22
  4565.3   343.7  4625.3  341.25  4665.3  341.01  4675.3     340  4725.4  339.19
  4765.4  337.14  4835.4  337.26  4915.5  339.39  4945.5  339.27  4975.5  337.95
  5003.6  335.83  5003.8  335.33  5086.3  339.34  5146.9  341.92  5171.6  341.99
  5187.2  343.07  5237.7  343.79  5257.9  345.06  5321.7  346.13  5429.4  350.11
  5459.7  350.37  5520.2  353.59  5544.5  356.01  5560.6   355.8  5580.8  356.89
#Mann= 3 , 0 , 0
  4375.1     .17       0  4945.5     .09       0  5086.3     .17       0
Bank Sta=4945.5,5086.3
XS Rating Curve= 0 ,0
Exp/Cntr=0.3,0.1

Type RM Length L Ch R = 1 ,12368   ,513,513,513
BEGIN DESCRIPTION:
BAY BRANCH TRIBUTARY NO 1 22.0
END DESCRIPTION:
XS GIS Cut Line= 3
      3729420.25      10194350.6        3729598.     10193829.27
      3729630.74     10193295.97
#Sta/Elev= 30
  4449.2   348.9  4543.8  345.33  4612.3  344.15  4649.4  342.53    4675  342.42
  4712.8  340.52    4769  339.31  4776.2  338.53  4786.8  338.82  4807.9   337.8
  4871.3  336.66  4889.1  335.42  4945.3  333.55  4983.1  331.06  4994.4  329.81
  4994.7  329.31  4998.2  329.31  5028.2  333.66  5076.3  335.74  5098.4  335.98
  5118.4  337.23  5198.6  338.76  5268.7  341.57  5298.8   343.5  5338.8  343.03
  5388.9  345.32  5409.8  345.07  5509.2  348.43  5529.2  348.14  5534.3  349.01
#Mann= 3 , 0 , 0
  4449.2     .17       0  4945.3     .09       0  5028.2     .17       0
Bank Sta=4945.3,5028.2
XS Rating Curve= 0 ,0
Exp/Cntr=0.3,0.1

Type RM Length L Ch R = 1 ,11855   ,469,469,469
BEGIN DESCRIPTION:
BAY BRANCH TRIBUTARY NO 1 21.0
END DESCRIPTION:
XS GIS Cut Line= 3
      3729892.46     10194361.07      3729950.54     10193726.62
      3729875.11     10193340.21
#Sta/Elev= 30
  4362.9  346.43    4393  344.56  4543.6  341.21  4582.7  339.32  4593.9  339.88
    4624  339.32  4764.6  334.71  4774.6  335.33  4802.8  333.43  4905.2  331.16
  4975.4  328.76  4995.3  326.31    5000  326.31  5003.9  324.71  5007.4  324.71
  5015.8  327.85    5026  329.09  5040.7  329.03    5077  331.84  5097.4  332.05
  5138.1  334.88  5148.9  333.96    5189  337.07  5229.8  338.94  5270.6  339.55
  5298.6  341.46  5321.5   342.1  5341.9  341.42  5350.1  342.51  5393.7  344.19
#Mann= 3 , 0 , 0
  4362.9     .17       0  4975.4     .09       0    5026     .17       0
Bank Sta=4975.4,5026
XS Rating Curve= 0 ,0
Exp/Cntr=0.3,0.1

Type RM Length L Ch R = 1 ,11386   ,593,593,593
BEGIN DESCRIPTION:
BAY BRANCH TRIBUTARY NO 1 20.0
END DESCRIPTION:
XS GIS Cut Line= 3
      3730171.98     10194251.63      3730239.19     10193846.57
      3730187.65     10193385.74
#Sta/Elev= 30
  4589.4  339.49  4610.2  338.24  4671.1  337.51  4716.8  335.37  4752.2  335.13
  4975.2  327.71  4985.3  326.81  4995.2  324.36    5000  324.36  5003.5  323.62
  5003.8  323.12  5007.3  323.12  5007.5  323.62  5015.6  325.34  5025.7  325.84
  5035.7  325.25  5045.8  326.26    5076  327.37    5086  327.39  5144.2  330.27
  5166.5  330.48  5186.7  331.77  5206.8  331.59  5226.9  333.09  5234.4   332.9
  5277.2  334.77  5357.7  336.16    5415  338.13  5428.1  340.41  5463.7  339.47
#Mann= 3 , 0 , 0
  4589.4     .17       0  4975.2     .09       0    5076     .17       0
Bank Sta=4975.2,5076
XS Rating Curve= 0 ,0
Exp/Cntr=0.3,0.1

Type RM Length L Ch R = 1 ,10793   ,869,869,869
BEGIN DESCRIPTION:
BAY BRANCH TRIBUTARY NO 1 19.0
END DESCRIPTION:
XS GIS Cut Line= 3
      3730454.97     10194225.59      3730729.45     10193606.51
      3730474.05     10193319.35
#Sta/Elev= 30
  4322.8   334.4  4366.5  334.01  4395.2  332.39  4404.3     333  4517.1   331.4
  4534.9  330.14  4633.4  327.99  4667.6  328.29  4714.2  326.43  4789.5  325.78
  4859.3  323.01  4888.1  323.26  4905.9  321.09  4911.3  323.55  4929.1  321.46
  4934.6  323.26  4973.1  323.53  4981.2  321.49  4986.6  321.26  4994.8  318.72
    5000  318.72  5003.5  317.21  5040.4  323.07  5054.6  322.74  5068.8  323.83
  5132.4  325.45  5154.1  327.53  5238.6  330.19  5288.3  333.08  5384.3  335.45
#Mann= 3 , 0 , 0
  4322.8     .17       0  4973.1     .09       0  5040.4     .17       0
Bank Sta=4973.1,5040.4
XS Rating Curve= 0 ,0
Exp/Cntr=0.3,0.1

Type RM Length L Ch R = 1 ,9924    ,992,992,992
BEGIN DESCRIPTION:
BAY BRANCH TRIBUTARY NO 1 18.0
END DESCRIPTION:
XS GIS Cut Line= 3
      3731324.76     10194340.22      3731255.88     10194020.56
      3731184.28     10193194.36
#Sta/Elev= 30
    4673  329.96    4713  328.97  4764.2  325.75  4778.3  326.49  4815.3  324.43
  4822.5  324.84  4835.8  323.53  4938.1  321.56  4958.6   320.7  4965.3   319.5
  4970.4  319.98  4989.2  317.08  4995.4  313.57  5029.6   316.8  5049.7  317.72
  5099.9  316.59  5119.9  317.25  5210.3  316.65  5250.4  318.55  5266.1  317.74
  5360.8  316.36    5401  319.79  5461.2  321.91  5497.4  324.12  5541.5  324.19
  5615.5  326.25  5631.8  327.64  5692.1  328.44  5752.3  330.83  5829.3   332.4
#Mann= 3 , 0 , 0
    4673     .17       0  4989.2     .09       0  5029.6     .17       0
Bank Sta=4989.2,5029.6
XS Rating Curve= 0 ,0
Exp/Cntr=0.3,0.1

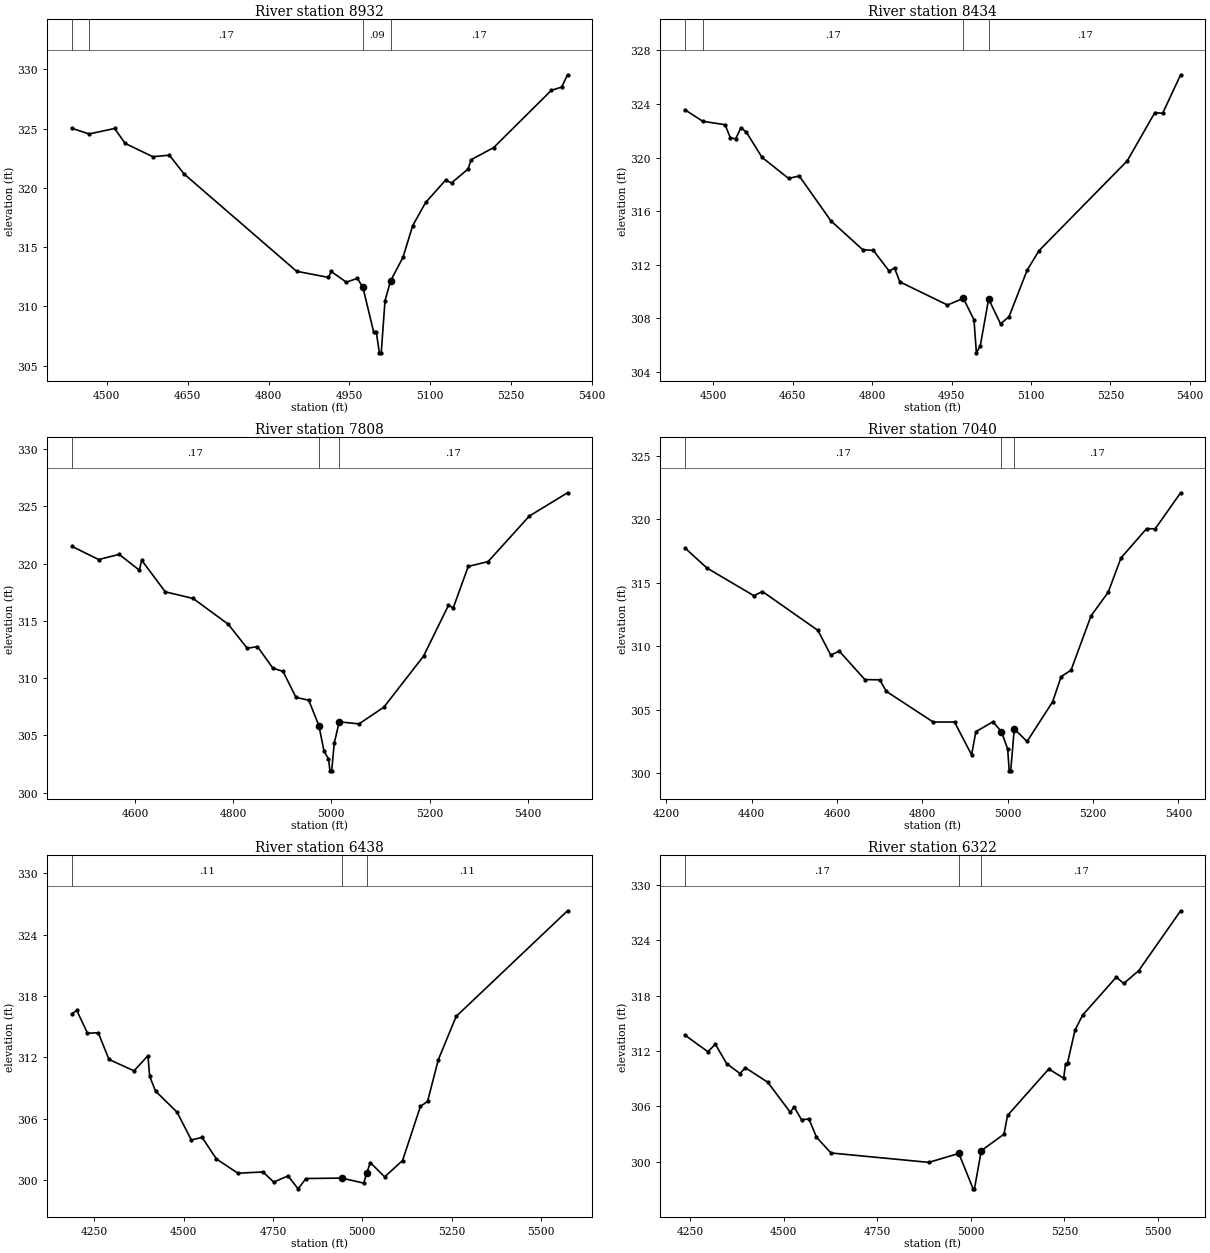
Type RM Length L Ch R = 1 ,8932    ,498,498,498
BEGIN DESCRIPTION:
BAY BRANCH TRIBUTARY NO 1 17.0
END DESCRIPTION:
XS GIS Cut Line= 3
      3731779.63     10194067.66       3731653.7     10193516.77
      3731571.28     10193171.78
#Sta/Elev= 30
  4434.9  325.03  4467.1  324.55  4514.4  325.01    4534  323.75  4585.3  322.63
    4616  322.76  4643.2  321.18    4852  312.97  4911.2  312.45  4916.3  312.95
  4944.3  312.05  4964.8  312.37  4975.1  311.61  4995.2  307.82    5000  307.82
  5005.6  306.09  5009.1  306.09  5016.1  310.49  5026.4  312.16  5049.4  314.14
  5067.5  316.82  5091.5  318.77  5128.4  320.65  5139.5  320.42  5170.4   321.6
  5175.6  322.37  5217.7   323.4  5324.6  328.22    5344  328.51  5354.7  329.54
#Mann= 4 ,-1 , 0
  4434.9     .11       0  4467.1     .17       0  4975.1     .09       0
  5026.4     .17       0
Bank Sta=4975.1,5026.4
XS Rating Curve= 0 ,0
Exp/Cntr=0.3,0.1

Type RM Length L Ch R = 1 ,8434    ,626,626,626
BEGIN DESCRIPTION:
BAY BRANCH TRIBUTARY NO 1 16.0
END DESCRIPTION:
XS GIS Cut Line= 3
      3732078.23     10194006.86      3732082.01     10193453.38
      3731912.23     10193110.63
#Sta/Elev= 30
  4446.5  323.57  4480.1  322.71  4522.3  322.45  4532.3  321.48  4542.3  321.39
  4552.3  322.23  4562.3  321.91  4592.3  320.01  4642.3  318.44  4662.3  318.63
  4722.3  315.27  4782.3  313.12  4802.3  313.07  4832.3  311.52  4842.3  311.76
  4852.3  310.72  4942.3  308.99  4972.3  309.49  4992.3  307.89  4996.9  305.42
  5004.1  305.92    5020  309.44  5042.4  307.59  5058.4  308.11  5092.8   311.6
  5115.2  313.05  5281.6  319.75  5333.9  323.36  5348.5   323.3  5382.5  326.18
#Mann= 4 ,-1 , 0
  4446.5     .11       0  4480.1     .17       0  4972.3     .09       0
    5020     .17       0
Bank Sta=4972.3,5020
XS Rating Curve= 0 ,0
Exp/Cntr=0.3,0.1

Type RM Length L Ch R = 1 ,7808    ,768,768,768
BEGIN DESCRIPTION:
BAY BRANCH TRIBUTARY NO 1 15.0
END DESCRIPTION:
XS GIS Cut Line= 3
       3732432.4     10194093.64      3732583.43     10193586.86
      3732654.61     10193111.06
#Sta/Elev= 30
  4471.2  321.52    4526  320.36  4567.8  320.81  4608.6  319.44  4613.8  320.29
  4661.7  317.54  4718.5  316.96    4790  314.71  4828.7  312.61  4849.5  312.76
  4880.8  310.88  4901.7  310.59  4927.9  308.32  4953.9  308.08  4974.7  305.85
  4985.2   303.6  4994.2  302.97  4997.2  301.91  5000.7  301.91  5005.9  304.32
    5016  306.19  5056.4  306.01    5107  307.47  5187.9  311.93  5238.4  316.35
  5248.5  316.16  5278.9  319.76  5319.3  320.18  5403.4  324.16  5481.1  326.19
#Mann= 3 , 0 , 0
  4471.2     .17       0  4974.7     .09       0    5016     .17       0
Bank Sta=4974.7,5016
XS Rating Curve= 0 ,0
Exp/Cntr=0.3,0.1

Type RM Length L Ch R = 1 ,7040    ,602,602,602
BEGIN DESCRIPTION:
BAY BRANCH TRIBUTARY NO 1 13.0
END DESCRIPTION:
XS GIS Cut Line= 3
      3733232.74     10194362.78      3733249.49     10193606.57
      3733258.79     10193201.27
#Sta/Elev= 30
  4243.6  317.74  4295.3  316.16  4405.3  313.98  4425.4  314.31  4555.4  311.25
  4585.4  309.31  4605.4  309.62  4665.4  307.38  4700.4  307.36  4715.4  306.46
  4825.5  304.04  4875.5  304.04  4915.5  301.46  4925.5  303.28  4965.5  304.06
  4985.5  303.28    5000  301.92  5003.7   300.2  5007.2   300.2  5015.5   303.5
  5045.5  302.51  5105.5  305.64  5125.5  307.62  5148.6  308.12  5195.5   312.4
  5235.6  314.25  5265.6  316.95  5325.6  319.26  5345.6  319.24  5405.4  322.08
#Mann= 3 , 0 , 0
  4243.6     .17       0  4985.5     .09       0  5015.5     .17       0
Bank Sta=4985.5,5015.5
XS Rating Curve= 0 ,0
Exp/Cntr=0.3,0.1

Type RM Length L Ch R = 1 ,6438    ,116,116,116
BEGIN DESCRIPTION:
BAY BRANCH TRIBUTARY NO 1 12.0
END DESCRIPTION:
XS GIS Cut Line= 3
      3733758.78       10194585.      3733811.54     10193773.62
      3733826.49     10193199.61
#Sta/Elev= 30
  4186.9  316.23  4200.9  316.58  4230.9  314.35    4261  314.39  4291.1  311.78
  4361.2  310.67    4400  312.15    4405  310.12  4421.3  308.69  4481.5  306.63
  4521.5  303.91  4551.6  304.16  4591.7  302.05  4651.8  300.66    4722  300.78
    4752  299.79  4792.1  300.39  4820.4  299.13  4842.2  300.14  4942.4  300.18
  5003.8  299.69  5012.5  300.71  5022.6  301.69  5062.6   300.3  5112.6   301.9
  5162.6  307.19  5182.6  307.68  5212.6  311.75  5262.6  315.99  5574.2  326.32
#Mann= 3 , 0 , 0
  4186.9     .11       0  4942.4     .06       0  5012.5     .11       0
Bank Sta=4942.4,5012.5
XS Rating Curve= 0 ,0
Exp/Cntr=0.3,0.1

Type RM Length L Ch R = 1 ,6322    ,909,909,909
BEGIN DESCRIPTION:
BAY BRANCH TRIBUTARY NO 1 11.0
END DESCRIPTION:
XS GIS Cut Line= 3
      3733876.84     10194602.39      3733907.89     10193838.72
      3733941.08      10193279.4
#Sta/Elev= 30
  4235.7  313.73  4297.1  311.92  4317.1  312.74  4347.1  310.64  4382.9  309.56
  4397.2  310.19  4457.2  308.61  4517.3  305.35  4527.3  305.94  4547.3  304.55
  4567.3  304.62  4587.3  302.65  4626.1  300.94  4887.6  299.92  4967.6  300.89
  5005.9  297.05  5009.4  297.05  5027.7  301.19  5088.3  302.98  5097.8  305.01
    5208  310.05  5247.8  309.05  5252.8  310.59  5258.1  310.72  5278.1  314.26
  5298.2  315.88  5388.3  320.01  5408.4  319.33  5448.4  320.72  5560.3  327.21
#Mann= 3 , 0 , 0
  4235.7     .17       0  4967.6     .09       0  5027.7     .17       0
Bank Sta=4967.6,5027.7
XS Rating Curve= 0 ,0
Exp/Cntr=0.3,0.1

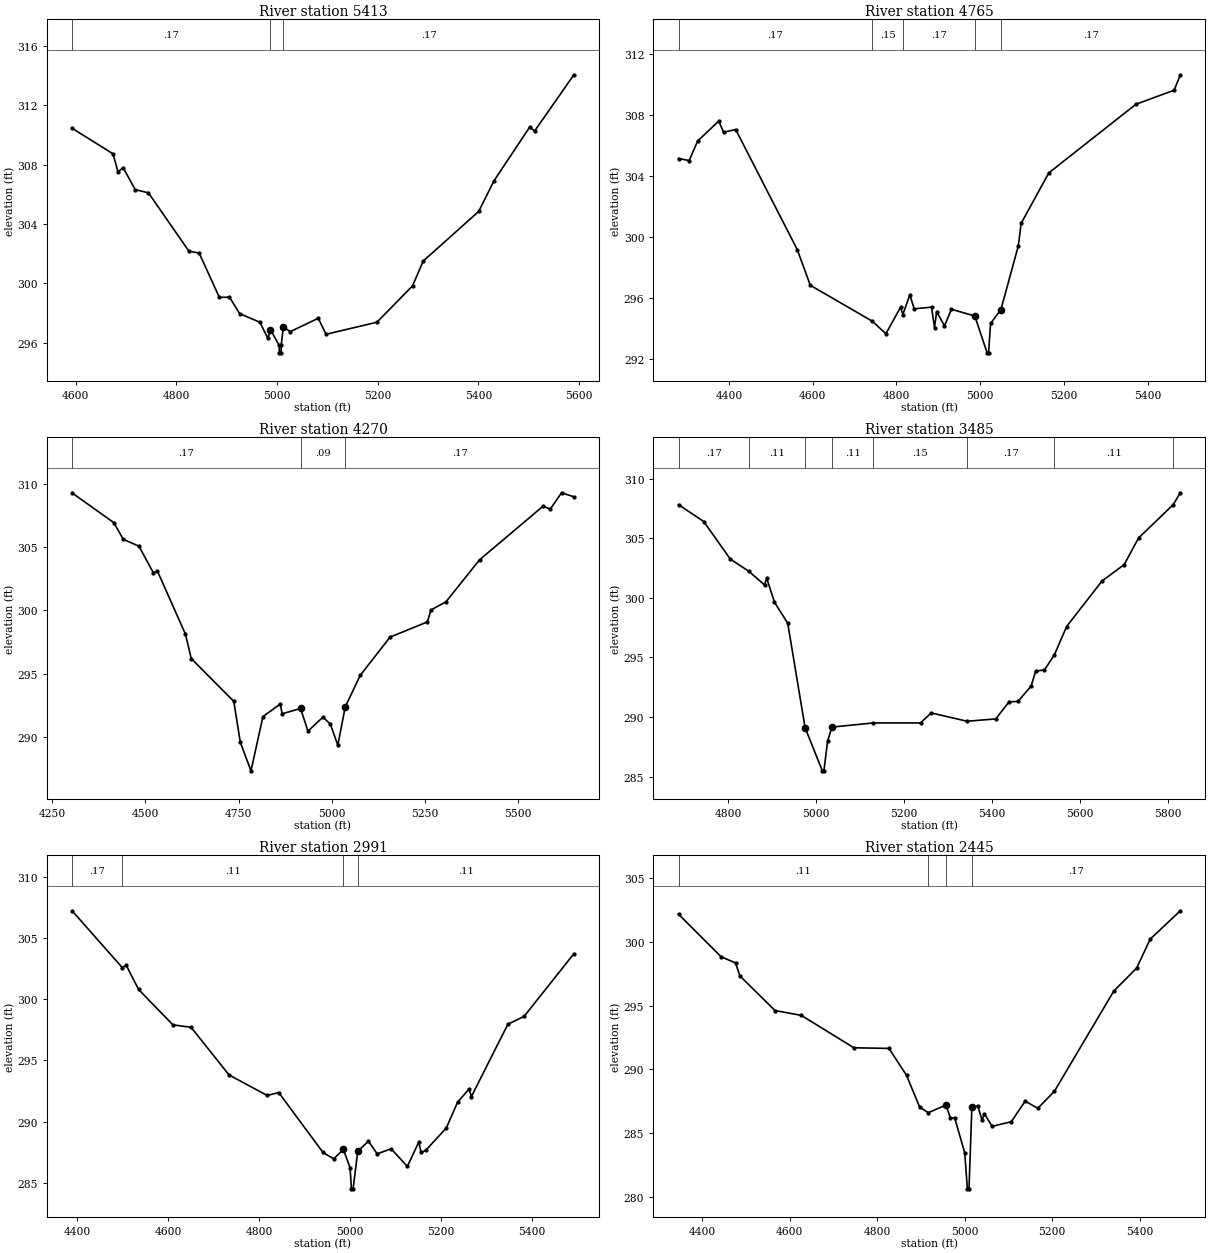
Type RM Length L Ch R = 1 ,5413    ,648,648,648
BEGIN DESCRIPTION:
BAY BRANCH TRIBUTARY NO 1 10.5
END DESCRIPTION:
XS GIS Cut Line= 3
      3734328.81     10194591.81      3734374.84     10194187.22
      3734288.38     10193604.09
#Sta/Elev= 30
  4592.8  310.45  4674.1  308.73  4684.1  307.51  4694.2   307.8  4718.2  306.32
  4744.5   306.1    4825  302.17  4845.2  302.05  4885.4  299.06  4905.5  299.08
  4925.7  297.97  4965.9  297.39  4981.7   296.3  4986.8   296.9  5004.2  295.83
  5004.5  295.33    5008  295.33  5008.2  295.83  5012.4  297.06  5026.4  296.76
  5081.9  297.66  5097.2  296.58  5198.3  297.39  5269.1  299.84  5290.3  301.51
  5400.5  304.85  5430.8  306.91  5501.6  310.52  5511.7  310.27  5589.5  314.05
#Mann= 3 , 0 , 0
  4592.8     .17       0  4986.8     .09       0  5012.4     .17       0
Bank Sta=4986.8,5012.4
XS Rating Curve= 0 ,0
Exp/Cntr=0.3,0.1

Type RM Length L Ch R = 1 ,4765    ,495,495,495
BEGIN DESCRIPTION:
BAY BRANCH TRIBUTARY NO 1 8.0
END DESCRIPTION:
XS GIS Cut Line= 3
       3734687.6     10194675.29      3734869.96     10193978.66
      3734739.68     10193518.97
#Sta/Elev= 30
  4279.9  305.14  4305.4  305.01  4325.6  306.29  4375.9  307.59  4387.6  306.86
  4416.3  307.04  4563.4  299.18  4594.4  296.85  4742.4   294.5  4774.9  293.68
  4810.1  295.42  4815.3  294.93  4832.1  296.22  4842.5  295.31  4883.8  295.42
    4891  294.08  4896.1  295.13  4914.8  294.19  4931.4  295.28  4987.2  294.84
  5016.5  292.43    5020  292.43  5024.8  294.35  5049.5  295.26    5091  299.42
  5097.8   300.9  5163.8   304.2  5371.7  308.69  5463.1  309.61  5477.8  310.62
#Mann= 5 ,-1 , 0
  4279.9     .17       0  4742.4     .15       0  4815.3     .17       0
  4987.2     .09       0  5049.5     .17       0
Bank Sta=4987.2,5049.5
XS Rating Curve= 0 ,0
Exp/Cntr=0.3,0.1

Type RM Length L Ch R = 1 ,4270    ,785,785,785
BEGIN DESCRIPTION:
BAY BRANCH TRIBUTARY NO 1 7.0
END DESCRIPTION:
XS GIS Cut Line= 3
      3735215.38     10194796.79      3735304.78     10194231.98
      3735326.34     10193458.12
#Sta/Elev= 30
  4303.2  309.28  4415.1  306.93  4440.6  305.61  4482.5  305.07  4521.6  302.95
  4531.7  303.13  4607.3  298.12  4622.8  296.19    4737   292.8  4754.5  289.57
  4783.1  287.31  4815.2   291.6  4861.7  292.59  4866.8  291.82    4916  292.24
    4936  290.45    4976  291.55    4996  291.01    5016  289.34    5036  292.37
    5076  294.85  5156.1  297.88  5256.1  299.08  5266.1  300.03  5306.1  300.67
  5396.2  303.99  5566.2  308.22  5586.2  308.01  5616.2  309.29  5649.2  308.97
#Mann= 3 ,-1 , 0
  4303.2     .17       0    4916     .09       0    5036     .17       0
Bank Sta=4916,5036
XS Rating Curve= 0 ,0
Exp/Cntr=0.3,0.1

Type RM Length L Ch R = 1 ,3485    ,494,494,494
BEGIN DESCRIPTION:
BAY BRANCH TRIBUTARY NO 1 6.0
END DESCRIPTION:
XS GIS Cut Line= 3
      3735878.27     10194698.25      3735865.33     10194524.22
      3735762.45     10193564.22
#Sta/Elev= 30
  4687.5  307.81  4744.8   306.4    4805  303.25  4846.9  302.23  4882.8  301.08
  4887.8  301.64  4905.4  299.63  4935.6  297.86    4975   289.1  5014.2  285.48
  5017.8  285.48  5026.1  287.97  5036.1  289.15  5130.3   289.5  5237.3   289.5
  5261.6  290.34  5343.1  289.64  5408.3  289.84  5438.4  291.27  5458.6   291.3
  5488.7   292.6  5498.8  293.85  5518.9  293.95  5541.6  295.23  5569.2  297.59
  5649.6  301.41  5699.9  302.78  5732.5  305.01  5811.4  307.82  5827.5  308.81
#Mann= 8 ,-1 , 0
  4687.5     .17       0  4846.9     .11       0    4975     .07       0
  5036.1     .11       0  5130.3     .15       0  5343.1     .17       0
  5541.6     .11       0  5811.4     .17       0
Bank Sta=4975,5036.1
XS Rating Curve= 0 ,0
Exp/Cntr=0.3,0.1

Type RM Length L Ch R = 1 ,2991    ,546,546,546
BEGIN DESCRIPTION:
BAY BRANCH TRIBUTARY NO 1 5.0
END DESCRIPTION:
XS GIS Cut Line= 3
      3736317.87     10194661.11       3736135.9      10194076.9
      3735963.94     10193615.29
#Sta/Elev= 30
  4388.1  307.23  4498.8  302.58  4507.2  302.79  4534.5   300.8    4610  297.91
    4650  297.71  4733.8  293.81  4817.6  292.14  4842.9  292.38  4940.5  287.48
  4964.2  286.96  4985.2  287.74    5000  286.23    5003  284.51  5006.7  284.51
  5016.9  287.58  5040.5   288.4  5059.6  287.37  5090.5  287.78  5126.1  286.34
  5151.1  288.32  5156.5  287.48  5166.3  287.65  5211.8  289.48  5236.8   291.6
  5261.8  292.66  5267.1  292.05  5347.4  297.96  5383.1   298.6  5492.6  303.72
#Mann= 4 ,-1 , 0
  4388.1     .17       0  4498.8     .11       0  4985.2     .07       0
  5016.9     .11       0
Bank Sta=4985.2,5016.9
XS Rating Curve= 0 ,0
Exp/Cntr=0.3,0.1

Type RM Length L Ch R = 1 ,2445    ,454,454,454
BEGIN DESCRIPTION:
BAY BRANCH TRIBUTARY NO 1 4.0
END DESCRIPTION:
XS GIS Cut Line= 3
      3736517.85     10194561.08      3736550.67     10193908.21
      3736350.78      10193458.2
#Sta/Elev= 30
  4346.3  302.17  4443.7  298.83  4476.5  298.35  4486.5  297.33  4566.6  294.62
  4626.7  294.24  4746.8   291.7  4826.9  291.65    4867  289.54    4897  287.05
  4916.8  286.61  4957.1  287.21  4967.1  286.21  4977.1  286.19    5000  283.46
    5006  280.64  5009.7  280.64  5016.3  287.03  5029.7  287.15  5039.5  286.04
    5045  286.52  5062.5  285.54  5106.3   285.9    5138  287.52  5166.8  286.95
  5204.8  288.29  5340.5  296.15  5392.5  297.94  5423.6  300.22  5492.4  302.44
#Mann= 4 ,-1 , 0
  4346.3     .11       0  4916.8     .17       0  4957.1     .09       0
  5016.3     .17       0
Bank Sta=4957.1,5016.3
XS Rating Curve= 0 ,0
Exp/Cntr=0.3,0.1

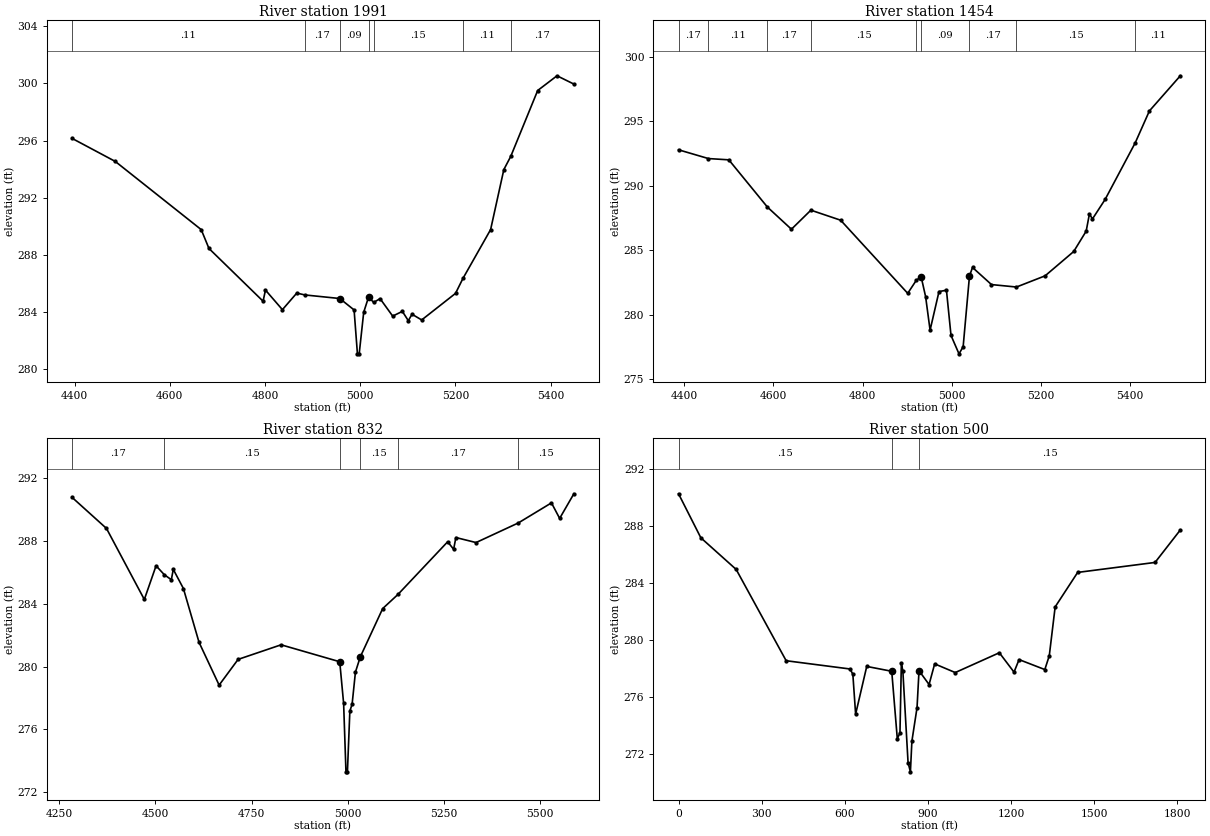
Type RM Length L Ch R = 1 ,1991    ,537,537,537
BEGIN DESCRIPTION:
BAY BRANCH TRIBUTARY NO 1 3.0
END DESCRIPTION:
XS GIS Cut Line= 3
      3736868.16      10194411.4      3736919.91     10193808.42
      3736842.11     10193366.21
#Sta/Elev= 30
  4394.8  296.16  4485.5  294.55  4666.1  289.78  4682.4  288.46  4796.1  284.77
  4801.1  285.55  4836.7  284.18  4866.9  285.34  4883.8  285.21  4957.2  284.96
  4987.3  284.16  4994.3  281.09    4998  281.09  5007.5     284  5017.6  285.05
  5028.5  284.69  5041.9  284.95  5068.4  283.73  5088.7  284.06  5101.2  283.41
    5109  283.86  5129.3  283.46  5200.4  285.32  5215.9  286.36  5274.1  289.78
  5301.9  293.98  5316.4   294.9    5373  299.51  5413.6  300.54    5449  299.96
#Mann= 7 ,-1 , 0
  4394.8     .11       0  4883.8     .17       0  4957.2     .09       0
  5017.6     .17       0  5028.5     .15       0  5215.9     .11       0
  5316.4     .17       0
Bank Sta=4957.2,5017.6
XS Rating Curve= 0 ,0
Exp/Cntr=0.3,0.1

Type RM Length L Ch R = 1 ,1454    ,622,622,622
BEGIN DESCRIPTION:
BAY BRANCH TRIBUTARY NO 1 2.0
END DESCRIPTION:
XS GIS Cut Line= 3
      3737382.05     10194383.56      3737342.18     10193772.45
      3736995.07     10193395.94
#Sta/Elev= 30
  4387.6   292.8  4454.5  292.12  4500.3  292.02  4586.8  288.35  4640.6  286.63
  4684.2  288.11  4750.9  287.33  4901.2  281.65  4920.2  282.65  4931.2  282.95
  4941.3  281.39  4951.3  278.79  4971.3  281.79    4988  281.89  4998.2  278.38
  5016.1  276.95  5025.4   277.5  5039.6     283  5046.4  283.66  5088.9  282.33
  5144.9  282.14  5209.1  283.01  5273.2   284.9  5301.1  286.48  5308.4  287.82
  5315.2  287.43  5343.5  288.94    5411  293.34  5442.8  295.82  5512.1  298.55
#Mann= 9 ,-1 , 0
  4387.6     .17       0  4454.5     .11       0  4586.8     .17       0
  4684.2     .15       0  4920.2     .17       0  4931.2     .09       0
  5039.6     .17       0  5144.9     .15       0    5411     .11       0
Bank Sta=4931.2,5039.6
XS Rating Curve= 0 ,0
Exp/Cntr=0.3,0.1

Type RM Length L Ch R = 1 ,832     ,636,636,636
BEGIN DESCRIPTION:
BAY BRANCH TRIBUTARY NO 1 10.0
END DESCRIPTION:
XS GIS Cut Line= 3
      3737777.89     10194275.98      3737654.79     10193570.34
      3737152.42     10193266.31
#Sta/Elev= 30
  4283.7  290.79  4373.1  288.81  4471.4  284.28  4501.9  286.43  4523.3  285.86
  4541.6  285.54  4546.6   286.2  4572.9  284.98  4613.5  281.55  4665.7  278.82
    4715  280.46  4826.7  281.39    4979  280.31  4989.1  277.66  4995.2  273.29
    4999  273.29  5005.3  277.17  5011.1  277.59  5019.8  279.65  5032.4  280.62
  5090.6   283.7  5130.2   284.6  5259.4  287.96  5274.9  287.48  5280.7  288.23
  5333.1  287.91  5442.9  289.16    5529  290.44  5550.3  289.45  5587.2  291.02
#Mann= 6 ,-1 , 0
  4283.7     .17       0  4523.3     .15       0    4979     .09       0
  5032.4     .15       0  5130.2     .17       0  5442.9     .15       0
Bank Sta=4979,5032.4
XS Rating Curve= 0 ,0
Exp/Cntr=0.3,0.1

Type RM Length L Ch R = 1 ,500     ,0,0,0
XS GIS Cut Line= 3
      3738037.44     10194368.47      3738094.82     10193538.51
      3737170.89     10193213.34
#Sta/Elev= 30
       0  290.26    80.5  287.17   207.9  284.95   388.3  278.54   618.9  277.96
   628.9  277.59   638.9  274.79     679  278.14   769.2   277.8   789.3  273.06
   798.9  273.48   803.9  278.36   809.3  277.83   828.1  271.39   836.6  270.74
   841.9  272.89   860.5  275.25   867.6  277.84   903.9  276.87   924.1  278.32
   998.3  277.71  1157.4   279.1  1210.4  277.74  1228.6  278.62  1321.5  277.92
  1337.6  278.89  1358.8  282.32    1440  284.74  1719.2  285.44  1810.4  287.72
#Mann= 3 , 0 , 0
       0     .15       0   769.2     .09       0   867.6     .15       0
Bank Sta=769.2,867.6
XS Rating Curve= 0 ,0
Exp/Cntr=0.3,0.1

Chan Stop Cuts=-1
Use User Specified Reach Order=0
Composite Channel Slope=5