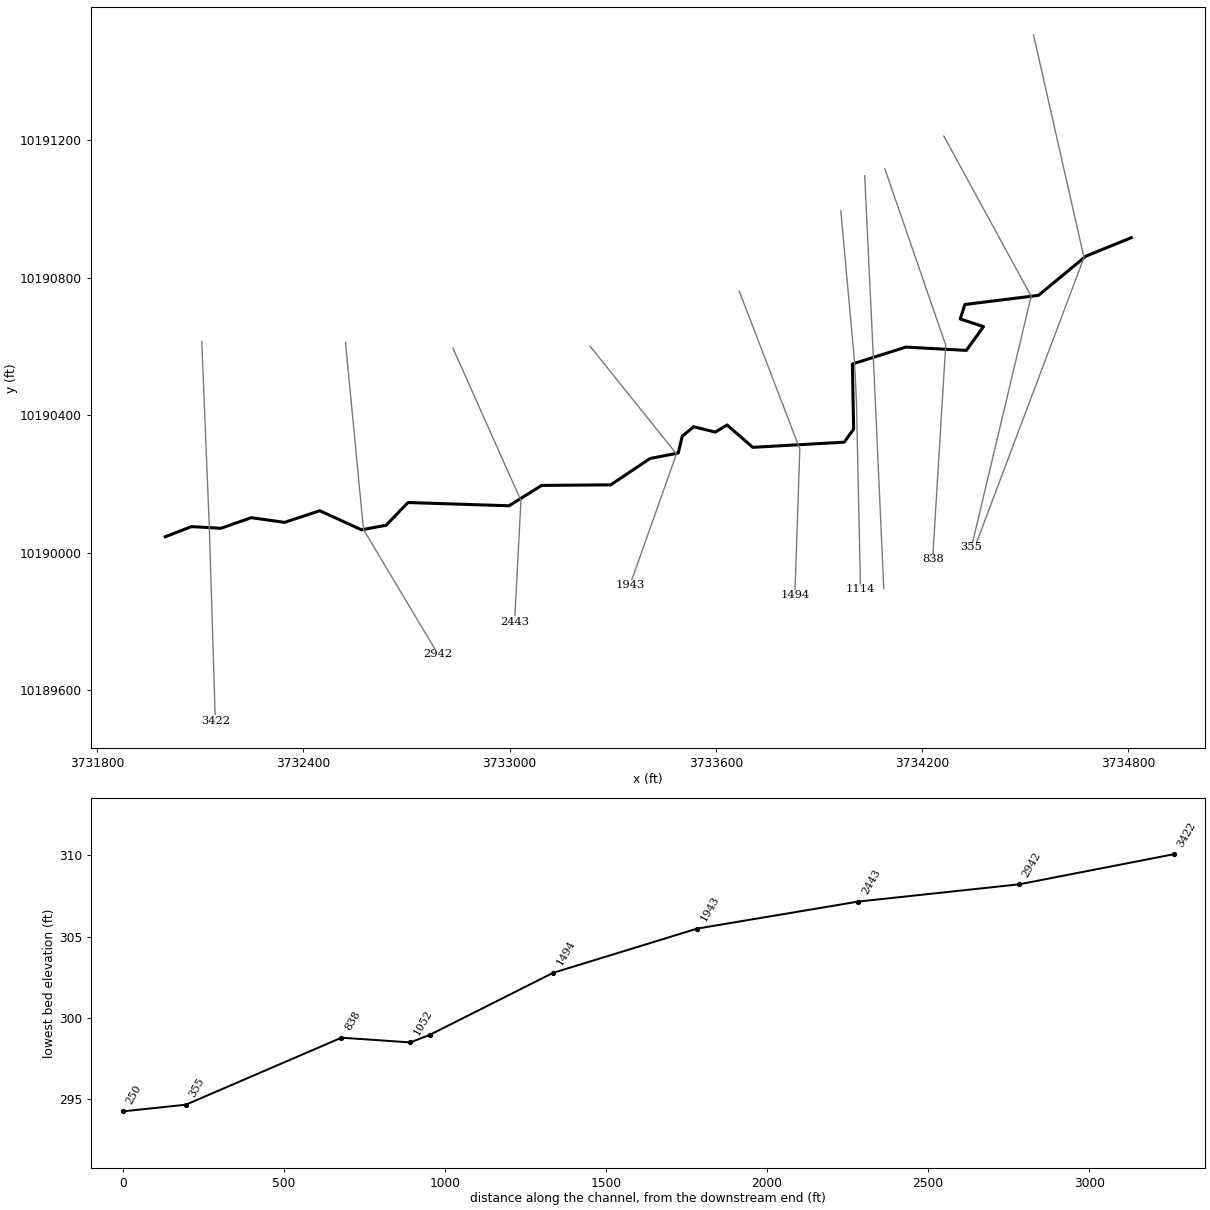
--- BAY BRANCH TRIBUTARY NO 2.prj (project) ---

Proj Title=BAY BRANCH TRIBUTARY NO 2 Base Level Engineering
Current Plan=p01
Default Exp/Contr=0.3,0.1
English Units
Geom File=g01
Flow File=f01
Flow File=f02
Plan File=p01
Y Axis Title=Elevation
X Axis Title(PF)=Main Channel Distance
X Axis Title(XS)=Station
BEGIN DESCRIPTION:
BAY BRANCH TRIBUTARY NO 2
END DESCRIPTION:
DSS File=dss
DSS Export Rating Curves= 0
DSS Export Rating Curve Sorted= 0
DSS Export Volume Flow Curves= 0
DXF OffsetX= 0
DXF OffsetY= 0
DXF ScaleX= 1
DXF ScaleY= 10

--- BAY BRANCH TRIBUTARY NO 2.p01 (plan) ---

Plan Title=Multiple Run
Program Version=4.10
Short Identifier=Multiple Run
Geom File=g01
Flow File=f01
Subcritical Flow
K Sum by GR= 0
Std Step Tol= 0.01
Critical Tol= 0.01
Num of Std Step Trials= 20
Max Error Tol= 0.3
Flow Tol Ratio= 0.001
Split Flow NTrial= 30
Split Flow Tol= 0.02
Split Flow Ratio= 0.02
Log Output Level= 0
Friction Slope Method= 1
Unsteady Friction Slope Method= 2
Unsteady Bridges Friction Slope Method= 1
Parabolic Critical Depth
Global Vel Dist= 1 , 1 , 1
Global Log Level= 0
CheckData=True
Encroach Param=-1 ,0,0, 0
BEGIN DESCRIPTION:
Multiple Run
END DESCRIPTION:
Computation Interval=1HOUR
Output Interval=1HOUR
Run HTab= 0
Run UNet= 0
Run PostProcess= 0
Run WQNet= 0
UNET Theta= 1
UNET Theta Warmup= 1
UNET ZTol= 0.02
UNET ZSATol= 0.05
UNET MxIter= 20
UNET MaxInSteps= 0
UNET DtIC= 0
UNET DtMin= 0
UNET MaxCRTS= 20
UNET WFStab= 2
UNET SFStab= 1
UNET WFX= 1
UNET SFX= 1
UNET DSS MLevel= 4
UNET DZMax Abort= 100
UNET Convert EG Bridges= 0
UNET Use Existing IB Tables=-1
UNET Froude Reduction=False
UNET Froude Limit= 1
UNET Froude Power= 10
UNET Time Slicing=0,0, 5
UNET Junction Losses=0
Instantaneous Interval=1HOUR
DSS File=dss
Write IC File= 0
Write IC File at Sim End=0
Echo Input=False
Echo Parameters=False
Echo Output=False
Write Detailed= 0
WQ AD Non Conservative
WQ ULTIMATE=-1
WQ Max Comp Step=1HOUR
WQ Output Interval=15MIN
WQ Output Selected Increments= 0
WQ Output face flow=0
WQ Output face velocity=0
WQ Output face area=0
WQ Output face dispersion=0
WQ Output cell volume=0
WQ Output cell surface area=0
WQ Output cell continuity=0
WQ Output cumulative cell continuity=0
WQ Output face conc=0
WQ Output face dconc_dx=0
WQ Output face courant=0
WQ Output face peclet=0
WQ Output face adv mass=0
WQ Output face disp mass=0
WQ Output cell mass=0
WQ Output cell source sink temp=0
WQ Output cell source sink nsm=0
WQ Output MaxMinRange=-1
WQ Daily Max Min Mean=-1
WQ Daily Range=0
WQ Daily Time=0
WQ Create Restart=0
WQ Fixed Restart=0
WQ System Summary=0
WQ Use Fixed Temperature=0
Sorting and Armoring Iterations= 10
XS Update Threshold= 0.02
Hydraulics Update Threshold= 0.02
Energy Slope Method= 1
Volume Change Method= 0
XS Weighting Method= 0
Number of US Weighted Cross Sections= 1
Number of DS Weighted Cross Sections= 1
Upstream XS Weight=0.25
Main XS Weight=0.5
Downstream XS Weight=0.25
Number of DS XS's Weighted with US Boundary= 1
Upstream Boundary Weight= 1
Weight of XSs Associated with US Boundary= 0
Number of US XS's Weighted with DS Boundary= 1
Downstream Boundary Weight= 0.5
Weight of XSs Associated with DS Boundary= 0.5
Sediment Output Level= 4
Mass or Volume Output= 0
Output Increment Type= 1
Profile and TS Output Increment= 10
XS Output Flag= 0
XS Output Increment= 10
Disregard all LS=0
Disregard all Conn=0
Disregard all Breaches=0
Disregard all Pumps=0

--- BAY BRANCH TRIBUTARY NO 2.f01 (steady flow) ---

Flow Title=Multiple
Program Version=4.10
Number of Profiles= 7
Profile Names=10-year,25-year,50-year,1pct_min,100-year,1pct_plu,500-year
River Rch & RM=BAY BRANCH TRIBU,Reach-1         ,3422
     494     662     889     393    1187    3585    2186
River Rch & RM=BAY BRANCH TRIBU,Reach-1         ,2942
     619     842    1140     508    1535    4636    2878
Boundary for River Rch & Prof#=BAY BRANCH TRIBU,Reach-1         , 1
Up Type= 0
Dn Type= 3
Dn Slope=0.007
Boundary for River Rch & Prof#=BAY BRANCH TRIBU,Reach-1         , 2
Up Type= 0
Dn Type= 3
Dn Slope=0.007
Boundary for River Rch & Prof#=BAY BRANCH TRIBU,Reach-1         , 3
Up Type= 0
Dn Type= 3
Dn Slope=0.007
Boundary for River Rch & Prof#=BAY BRANCH TRIBU,Reach-1         , 4
Up Type= 0
Dn Type= 3
Dn Slope=0.007
Boundary for River Rch & Prof#=BAY BRANCH TRIBU,Reach-1         , 5
Up Type= 0
Dn Type= 3
Dn Slope=0.007
Boundary for River Rch & Prof#=BAY BRANCH TRIBU,Reach-1         , 6
Up Type= 0
Dn Type= 3
Dn Slope=0.007
Boundary for River Rch & Prof#=BAY BRANCH TRIBU,Reach-1         , 7
Up Type= 0
Dn Type= 3
Dn Slope=0.007
DSS Import GetInterval= 0
DSS Import GetPeak= 0
DSS Import FillOption= 0

--- BAY BRANCH TRIBUTARY NO 2.f02 (steady flow) ---

Flow Title=Orig_BLE_Flow
Program Version=4.10
Number of Profiles= 7
Profile Names=10-year,25-year,50-year,1pct_min,100-year,1pct_plu,500-year
River Rch & RM=BAY BRANCH TRIBU,Reach-1         ,3422
     494     649     773     302     913    2757    1271
River Rch & RM=BAY BRANCH TRIBU,Reach-1         ,2942
     619     825     991     391    1181    3566    1673
Boundary for River Rch & Prof#=BAY BRANCH TRIBU,Reach-1         , 1
Up Type= 0
Dn Type= 3
Dn Slope=0.01
Boundary for River Rch & Prof#=BAY BRANCH TRIBU,Reach-1         , 2
Up Type= 0
Dn Type= 3
Dn Slope=0.01
Boundary for River Rch & Prof#=BAY BRANCH TRIBU,Reach-1         , 3
Up Type= 0
Dn Type= 3
Dn Slope=0.01
Boundary for River Rch & Prof#=BAY BRANCH TRIBU,Reach-1         , 4
Up Type= 0
Dn Type= 3
Dn Slope=0.01
Boundary for River Rch & Prof#=BAY BRANCH TRIBU,Reach-1         , 5
Up Type= 0
Dn Type= 3
Dn Slope=0.01
Boundary for River Rch & Prof#=BAY BRANCH TRIBU,Reach-1         , 6
Up Type= 0
Dn Type= 3
Dn Slope=0.01
Boundary for River Rch & Prof#=BAY BRANCH TRIBU,Reach-1         , 7
Up Type= 0
Dn Type= 3
Dn Slope=0.01
DSS Import GetInterval= 0
DSS Import GetPeak= 0
DSS Import FillOption= 0

--- BAY BRANCH TRIBUTARY NO 2.g01 (geometry) ---

Geom Title=Existing Conditions
Program Version=4.10

River Reach=BAY BRANCH TRIBU,Reach-1
Reach XY= 30
      3731998.23     10190046.84      3732074.35      10190076.3
      3732160.04     10190071.46      3732248.25     10190102.29
      3732344.95     10190088.69      3732447.65      10190122.5
      3732569.12     10190067.03      3732640.64     10190080.34
       3732704.3      10190146.4      3732998.07     10190136.93
      3733093.34     10190196.18       3733293.9     10190197.77
      3733408.27     10190274.44      3733490.48     10190290.36
      3733501.81     10190339.26      3733535.29     10190366.68
       3733598.2     10190351.25       3733632.2     10190372.03
      3733707.13     10190306.93      3733973.16     10190321.95
      3734000.51     10190359.94      3733996.92     10190549.27
      3734152.46     10190598.51      3734328.25     10190588.88
      3734378.32     10190658.06      3734310.59     10190680.31
      3734324.07     10190722.38      3734538.24     10190749.03
      3734676.04     10190863.01      3734808.23     10190916.84

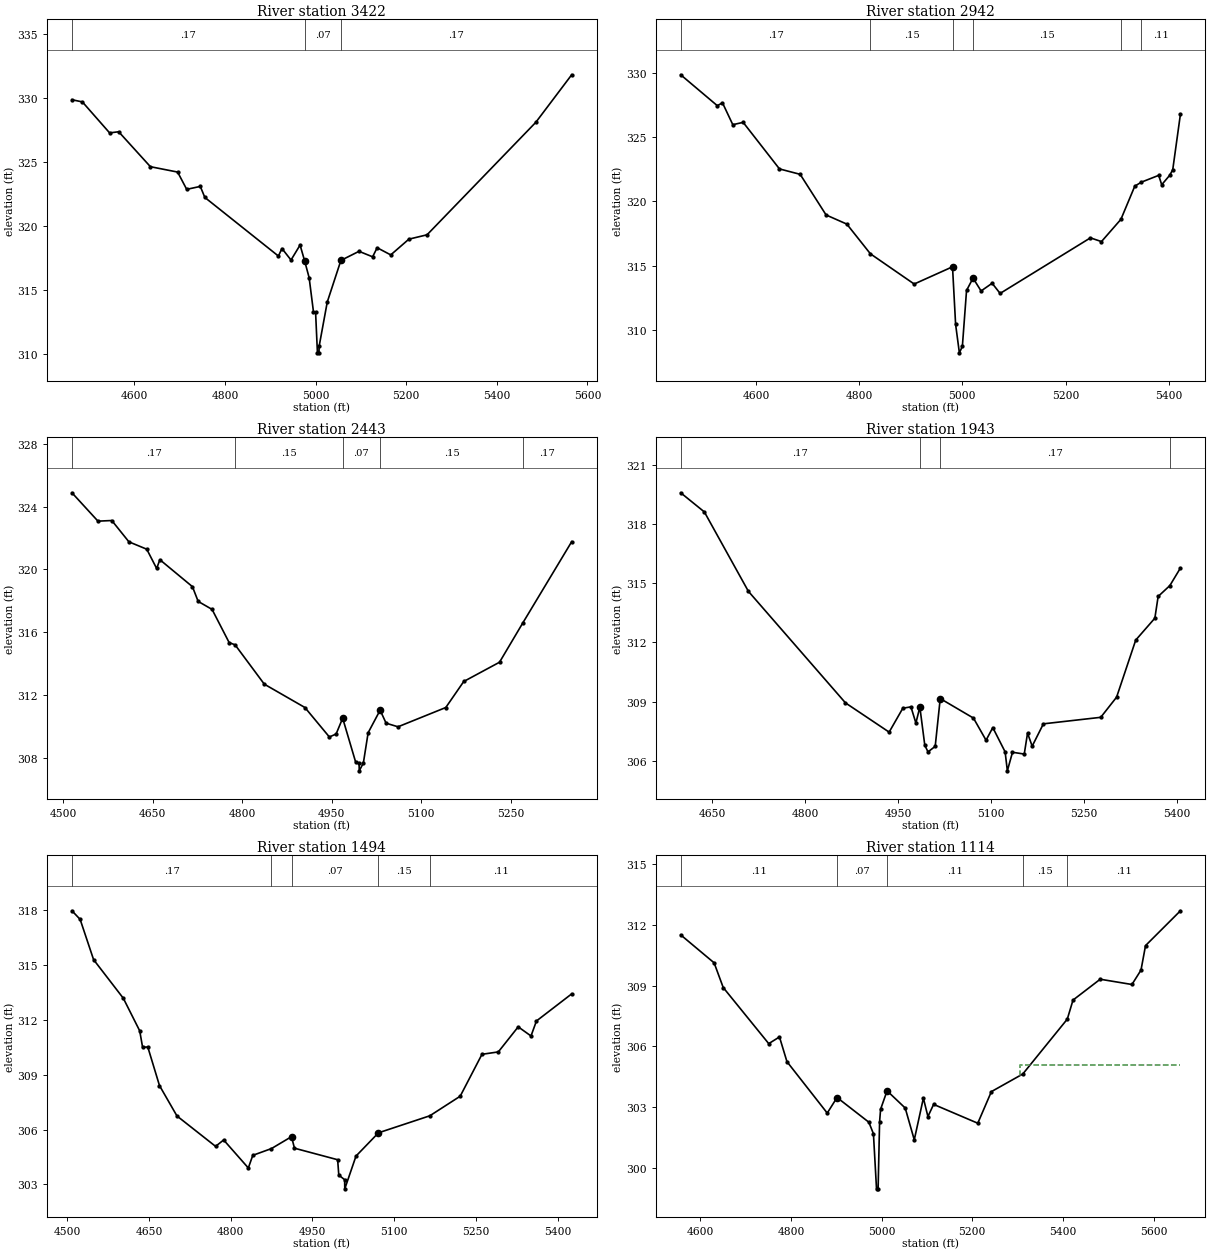
Type RM Length L Ch R = 1 ,3422    ,480,480,480
BEGIN DESCRIPTION:
BAY BRANCH TRIBUTARY NO 2 6.0
END DESCRIPTION:
XS GIS Cut Line= 3
      3732104.46     10190614.06      3732126.29     10190076.91
      3732143.82     10189511.98
#Sta/Elev= 30
  4462.4  329.83  4485.4  329.66  4545.5  327.24  4565.5  327.33  4635.5   324.6
  4695.6  324.18  4715.6  322.83  4745.6  323.06  4755.6   322.2    4918  317.62
  4925.8  318.21  4945.8  317.31  4965.8  318.48  4975.8  317.25  4985.8  315.93
  4995.4  313.25    5000  313.25  5004.1  310.06  5007.6  310.06  5007.8  310.56
  5025.8  314.03  5055.9  317.28  5095.9  317.99  5125.9  317.56  5135.9  318.27
  5165.9  317.71  5205.9  318.94    5246  319.28  5486.1  328.07  5565.2  331.78
#Mann= 3 , 0 , 0
  4462.4     .17       0  4975.8     .07       0  5055.9     .17       0
#XS Ineff= 2 , 0
       0  4965.8  318.48               0
Permanent Ineff=
       F       F
Bank Sta=4975.8,5055.9
XS Rating Curve= 0 ,0
Exp/Cntr=0.3,0.1

Type RM Length L Ch R = 1 ,2942    ,499,499,499
BEGIN DESCRIPTION:
BAY BRANCH TRIBUTARY NO 2 5.0
END DESCRIPTION:
XS GIS Cut Line= 3
      3732522.59     10190611.66      3732574.77     10190068.06
      3732791.57     10189705.07
#Sta/Elev= 30
  4453.9  329.83  4524.8  327.43  4534.9  327.65  4554.9  325.95    4575  326.13
  4645.4  322.51  4685.5  322.09  4735.8  318.93    4776  318.22  4821.7  315.91
  4906.6  313.56  4980.9   314.9  4986.9  310.42  4994.2  308.21    5000  308.71
  5008.1  313.06  5020.7  314.02  5036.3  313.02  5057.7  313.62  5073.2  312.83
  5248.3  317.15  5269.7  316.86  5307.4  318.59  5334.3  321.17    5347  321.48
  5380.7  322.01  5386.5  321.28  5402.1  322.02  5407.9  322.45  5422.8  326.77
#Mann= 6 ,-1 , 0
  4453.9     .17       0  4821.7     .15       0  4980.9     .07       0
  5020.7     .15       0  5307.4     .17       0    5347     .11       0
Bank Sta=4980.9,5020.7
XS Rating Curve= 0 ,0
Exp/Cntr=0.3,0.1

Type RM Length L Ch R = 1 ,2443    ,500,500,500
BEGIN DESCRIPTION:
BAY BRANCH TRIBUTARY NO 2 4.0
END DESCRIPTION:
XS GIS Cut Line= 3
      3732834.97     10190595.59      3733032.76      10190152.1
      3733014.42     10189800.27
#Sta/Elev= 30
  4514.4  324.89    4558  323.08  4581.2  323.12  4609.9  321.76  4639.8  321.29
  4656.4  320.06  4661.8  320.62  4716.4   318.9    4726  317.96  4749.3  317.45
    4778  315.33  4787.9  315.19  4836.9  312.68    4905  311.19    4946  309.31
  4957.3   309.5  4968.3  310.51  4990.2  307.69  4995.8  307.65  4996.1  307.15
    5003  307.65    5011  309.58  5031.1  311.02  5041.1  310.19  5061.1  309.96
  5141.2  311.19  5171.3  312.85  5231.3  314.08  5270.4  316.59  5352.3  321.77
#Mann= 5 ,-1 , 0
  4514.4     .17       0  4787.9     .15       0  4968.3     .07       0
  5031.1     .15       0  5270.4     .17       0
Bank Sta=4968.3,5031.1
XS Rating Curve= 0 ,0
Exp/Cntr=0.3,0.1

Type RM Length L Ch R = 1 ,1943    ,449,449,449
BEGIN DESCRIPTION:
BAY BRANCH TRIBUTARY NO 2 3.0
END DESCRIPTION:
XS GIS Cut Line= 3
      3733234.07     10190600.88      3733485.18     10190287.85
      3733349.63     10189905.47
#Sta/Elev= 30
  4598.7  319.57  4636.9   318.6    4708  314.58  4864.8  308.93  4935.3  307.45
  4957.4  308.66  4970.5  308.73  4978.5  307.91  4984.9  308.72  4992.9  306.78
  4998.1  306.45  5009.7  306.73  5017.8  309.15  5071.5  308.16  5091.8  307.04
  5102.7  307.68  5122.6  306.45  5126.2  305.49  5134.5  306.43  5153.5  306.34
  5158.8   307.4  5166.3  306.74  5184.4  307.87    5277   308.2  5302.6  309.22
  5333.5  312.11  5364.4  313.22  5369.7  314.32  5388.6  314.87  5405.7  315.76
#Mann= 4 ,-1 , 0
  4598.7     .17       0  4984.9     .07       0  5017.8     .17       0
  5388.6     .11       0
Bank Sta=4984.9,5017.8
XS Rating Curve= 0 ,0
Exp/Cntr=0.3,0.1

Type RM Length L Ch R = 1 ,1494    ,380,380,380
BEGIN DESCRIPTION:
BAY BRANCH TRIBUTARY NO 2 2.0
END DESCRIPTION:
XS GIS Cut Line= 3
      3733667.86     10190761.05        3733844.      10190302.2
      3733829.58     10189876.44
#Sta/Elev= 30
  4508.5  317.95  4523.5  317.48  4548.2  315.28  4602.8  313.17  4632.9  311.39
  4638.2  310.49  4647.7  310.51  4669.2   308.4  4701.3  306.74  4772.2  305.08
    4787  305.43  4832.3   303.9  4840.5  304.59  4874.8  304.96  4911.6  305.61
    4917  304.98  4996.3  304.35  4998.4  303.51  5009.1  303.26  5009.4  302.76
    5030  304.55  5071.2  305.82  5165.5  306.75  5221.3  307.82  5261.3  310.11
  5291.3  310.24  5327.8  311.61  5351.3  311.11  5361.3  311.93    5426  313.41
#Mann= 5 ,-1 , 0
  4508.5     .17       0  4874.8     .15       0  4911.6     .07       0
  5071.2     .15       0  5165.5     .11       0
#XS Ineff= 2 , 0
       0                  5071.2       0  305.82
Permanent Ineff=
       F       F
Bank Sta=4911.6,5071.2
XS Rating Curve= 0 ,0
Exp/Cntr=0.3,0.1

Type RM Length L Ch R = 1 ,1114    ,62,62,62
BEGIN DESCRIPTION:
Mapping XS c07ad576
END DESCRIPTION:
XS GIS Cut Line= 4
      3733963.26     10190994.51      3734003.19     10190555.28
      3734008.74     10190440.89      3734020.51     10189894.08
#Sta/Elev= 30
  4556.8  311.51  4630.5  310.13  4650.6  308.91    4751  306.14  4774.7  306.47
  4791.2  305.25  4880.1  302.71  4901.7  303.48  4971.9  302.26    4982  301.69
  4988.8  298.97  4992.3  298.97  4995.6  302.28  4997.8   302.9  5012.1  303.81
  5052.1  302.96  5072.1  301.39  5092.2  303.45  5102.2  302.54  5114.8  303.14
  5212.2  302.21  5242.2  303.77  5311.5  304.64  5409.7  307.35  5422.3  308.29
  5482.3  309.32  5552.3  309.06  5572.3  309.77  5582.3  310.98  5659.3   312.7
#Mann= 5 ,-1 , 0
  4556.8     .11       0  4901.7     .07       0  5012.1     .11       0
  5311.5     .15       0  5409.7     .11       0
#XS Ineff= 2 , 0
       0                  5305.4       0   305.1
Permanent Ineff=
       F       F
Bank Sta=4901.7,5012.1
XS Rating Curve= 0 ,0
Exp/Cntr=0.3,0.1

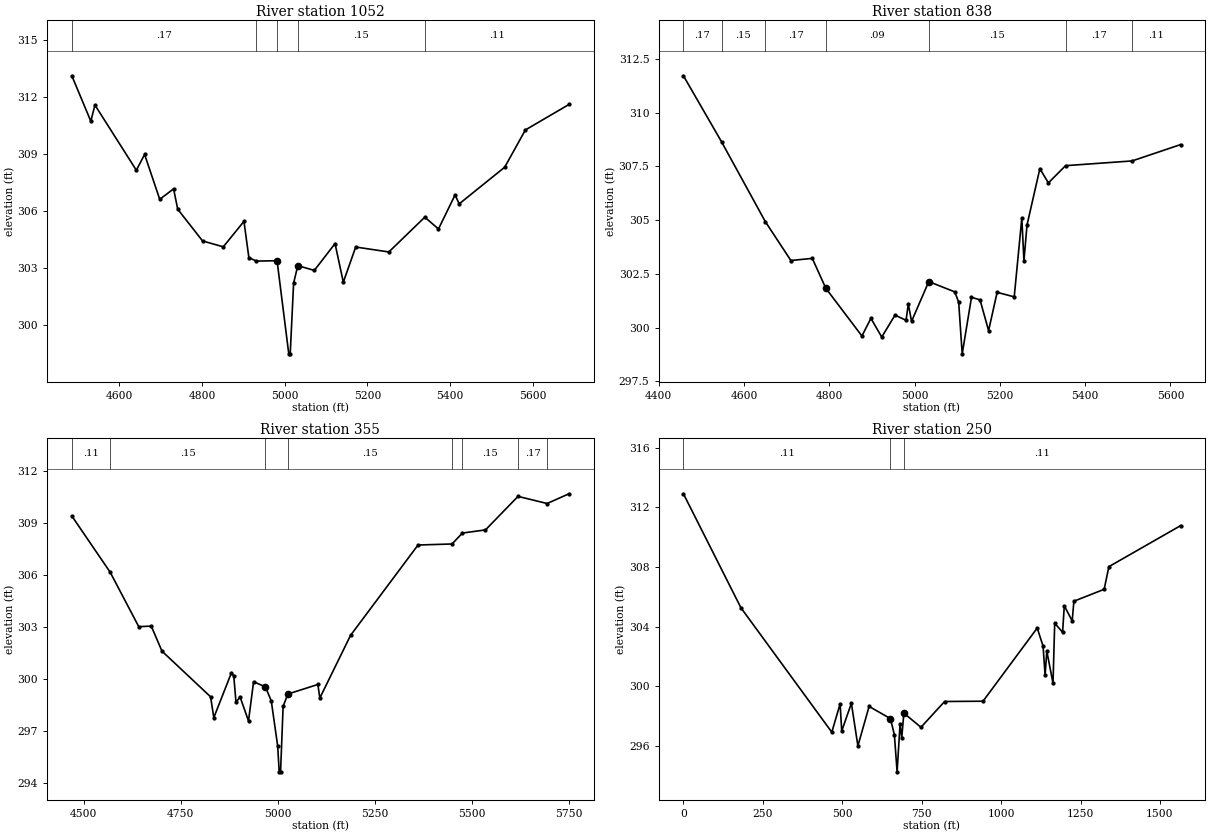
Type RM Length L Ch R = 1 ,1052    ,214,214,214
BEGIN DESCRIPTION:
Mapping XS 891cf9c7
END DESCRIPTION:
XS GIS Cut Line= 3
       3734032.7     10191096.92      3734057.01     10190584.79
      3734088.25      10189895.8
#Sta/Elev= 30
  4485.3  313.12  4531.2  310.73  4541.2  311.58  4641.3  308.15  4661.3  308.98
  4697.9  306.62  4731.4  307.17  4741.4   306.1  4801.5  304.43  4851.6  304.12
  4901.6  305.46  4913.5  303.55  4931.8  303.37  4981.7  303.39    5010  298.49
  5013.5  298.49  5021.7  302.21  5031.8  303.13  5071.8  302.88  5121.9  304.29
  5141.9  302.26  5171.9  304.11    5252  303.85    5339  305.68  5372.1  305.06
  5412.2  306.85  5422.2  306.38  5532.3  308.31  5582.3  310.27  5687.7  311.61
#Mann= 5 ,-1 , 0
  4485.3     .17       0  4931.8     .15       0  4981.7     .07       0
  5031.8     .15       0    5339     .11       0
#XS Ineff= 2 , 0
       0  4901.6  305.46  5121.9       0  304.29
Permanent Ineff=
       F       F
Bank Sta=4981.7,5031.8
XS Rating Curve= 0 ,0
Exp/Cntr=0.3,0.1

Type RM Length L Ch R = 1 ,838     ,483,483,483
BEGIN DESCRIPTION:
Mapping XS 225804f4
END DESCRIPTION:
XS GIS Cut Line= 3
      3734091.42     10191116.72      3734268.36     10190604.32
      3734230.32     10189981.68
#Sta/Elev= 30
  4457.9  311.71  4547.3  308.64  4649.9  304.93  4709.9  303.12  4760.1  303.22
  4791.8  301.83  4876.5  299.61  4897.6  300.43    4923  299.56  4954.1  300.58
    4980  300.34  4985.3   301.1  4992.9  300.29  5033.3  302.14  5094.4  301.66
  5103.4  301.18  5111.7  298.78  5133.5  301.41  5153.5  301.29  5173.6  299.86
  5193.6  301.64  5233.7  301.43  5251.5  305.09  5256.5  303.11  5263.7  304.77
  5293.8  307.39  5313.8  306.73  5354.1  307.53  5510.1  307.75  5623.8  308.51
#Mann= 7 ,-1 , 0
  4457.9     .17       0  4547.3     .15       0  4649.9     .17       0
  4791.8     .09       0  5033.3     .15       0  5354.1     .17       0
  5510.1     .11       0
Bank Sta=4791.8,5033.3
XS Rating Curve= 0 ,0
Exp/Cntr=0.3,0.1

Type RM Length L Ch R = 1 ,355     ,196,196,196
BEGIN DESCRIPTION:
BAY BRANCH TRIBUTARY NO 2 1.0
END DESCRIPTION:
XS GIS Cut Line= 3
      3734262.88     10191212.17      3734516.87     10190746.65
      3734343.16     10190016.42
#Sta/Elev= 30
  4469.7  309.39  4568.3  306.16  4642.1  303.02  4674.4  303.05  4701.9  301.61
  4827.2  298.98  4835.5  297.78    4881  300.37    4887  300.16  4892.7  298.66
  4903.1  298.98  4924.9  297.59    4938  299.85  4968.6  299.55  4983.6  298.74
    5000  296.16    5004  294.66  5007.5  294.66  5014.1  298.43  5026.3  299.14
  5103.6  299.69  5108.7  298.91  5187.9  302.52  5361.7  307.72  5449.4  307.78
  5476.1  308.41  5535.5  308.59  5619.3  310.52  5694.3  310.11  5750.6  310.67
#Mann= 8 ,-1 , 0
  4469.7     .11       0  4568.3     .15       0  4968.6     .07       0
  5026.3     .15       0  5449.4     .17       0  5476.1     .15       0
  5619.3     .17       0  5694.3     .11       0
Bank Sta=4968.6,5026.3
XS Rating Curve= 0 ,0
Exp/Cntr=0.3,0.1

Type RM Length L Ch R = 1 ,250     ,0,0,0
XS GIS Cut Line= 3
      3734523.74     10191506.65      3734670.55     10190858.98
       3734352.1       10190014.
#Sta/Elev= 30
       0  312.91     181  305.26   467.1  296.91   493.2  298.81   498.3  296.99
   528.7  298.85   549.2  295.99   584.5  298.64   651.7  297.82   664.1  296.73
   672.6  294.25   681.9  297.44   687.3  296.55   693.9  298.19   747.7  297.24
   822.2  298.97   943.1  298.99  1113.7   303.9  1132.1  302.69  1138.5  300.74
  1143.9  302.35  1163.4  300.19  1168.7  304.22  1193.6  303.62  1198.9  305.39
  1223.8  304.38  1229.1   305.7  1324.4   306.5  1339.3  308.02  1564.9  310.77
#Mann= 3 , 0 , 0
       0     .11       0   651.7     .06       0   693.9     .11       0
Bank Sta=651.7,693.9
XS Rating Curve= 0 ,0
Exp/Cntr=0.3,0.1

Chan Stop Cuts=-1
Use User Specified Reach Order=0
Composite Channel Slope=5