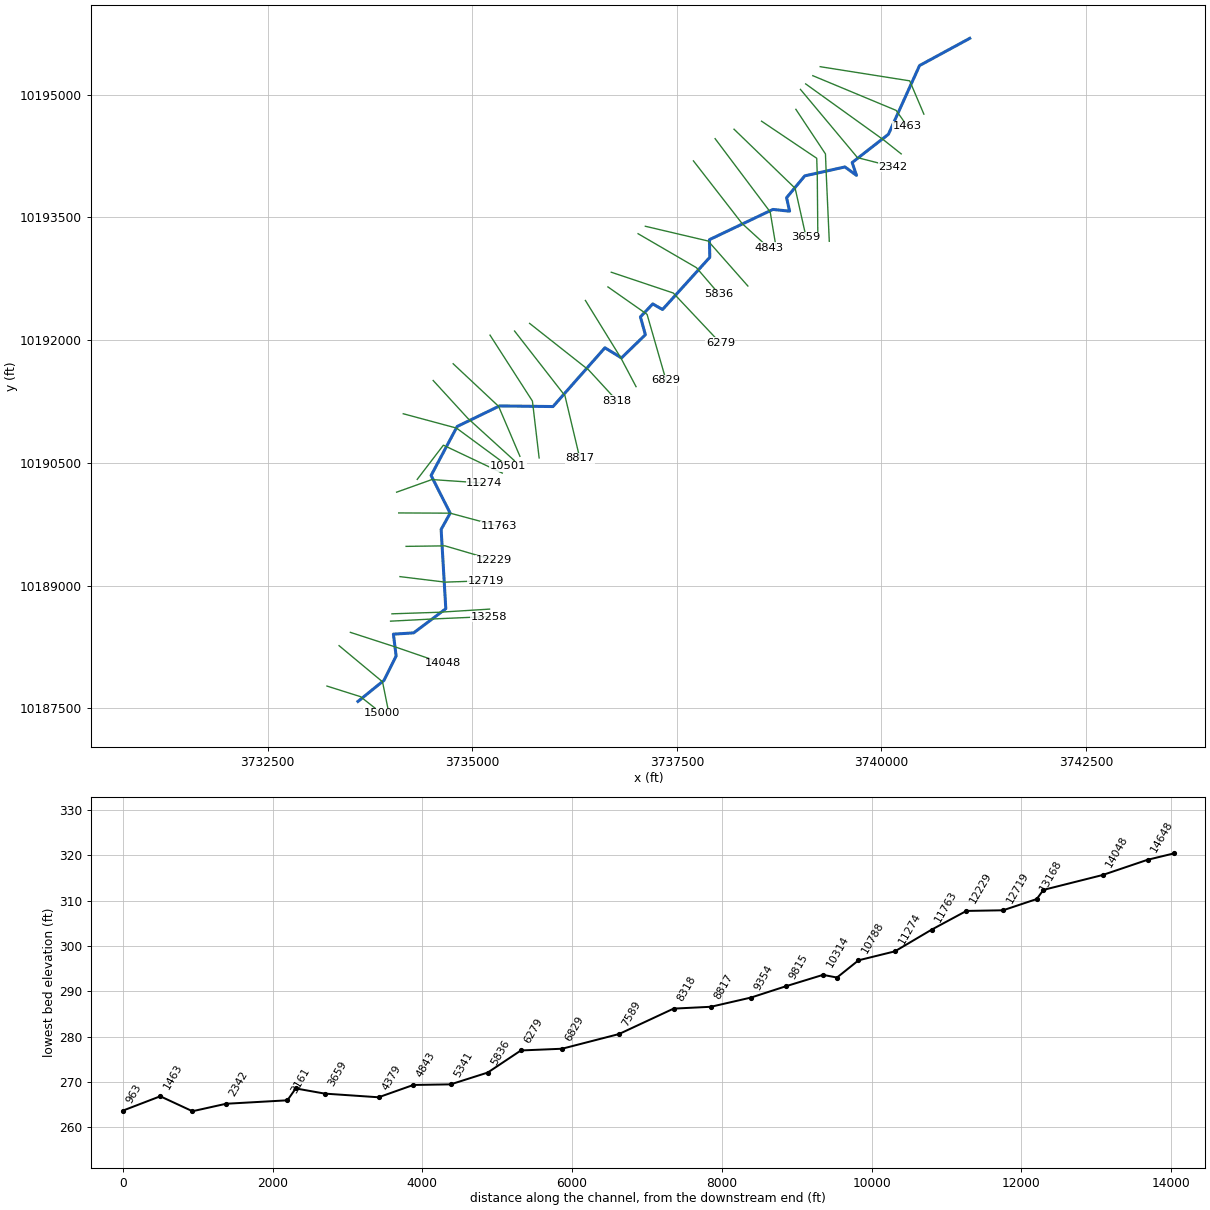
--- BAY BRANCH.prj (project) ---

Proj Title=BAY BRANCH Base Level Engineering
Current Plan=p01
Default Exp/Contr=0.3,0.1
English Units
Geom File=g01
Flow File=f01
Flow File=f02
Plan File=p01
Y Axis Title=Elevation
X Axis Title(PF)=Main Channel Distance
X Axis Title(XS)=Station
BEGIN DESCRIPTION:
BAY BRANCH
END DESCRIPTION:
DSS Export Rating Curves= 0
DSS Export Rating Curve Sorted= 0
DSS Export Volume Flow Curves= 0
DXF OffsetX= 0
DXF OffsetY= 0
DXF ScaleX= 1
DXF ScaleY= 10

--- BAY BRANCH.p01 (plan) ---

Plan Title=Multiple Run
Short Identifier=Multiple
Geom File=g01
Flow File=f01
Subcritical Flow
K Sum by GR= 0
Std Step Tol= 0.01
Critical Tol= 0.01
Num of Std Step Trials= 20
Max Error Tol= 0.3
Flow Tol Ratio= 0.001
Split Flow NTrial= 30
Split Flow Tol= 0.02
Split Flow Ratio= 0.02
Log Output Level= 0
Friction Slope Method= 1
Unsteady Friction Slope Method= 2
Unsteady Bridges Friction Slope Method= 1
Parabolic Critical Depth
Global Vel Dist=  1 , 1 , 1
Global Log Level= 0
CheckData=True
Encroach Param= -1, 0, 0, 0
BEGIN DESCRIPTION:
Multiple Run
END DESCRIPTION:

--- BAY BRANCH.f01 (steady flow) ---

Flow Title=Multiple
Program Version=4.10
Number of Profiles= 7
Profile Names=10-year,25-year,50-year,1pct_min,100-year,1pct_plu,500-year
River Rch & RM=BAY BRANCH,Reach-1         ,15000
     356     466     618     270     814    2458    1462
River Rch & RM=BAY BRANCH,Reach-1         ,14048
     449     596     792     348    1050    3171    1904
River Rch & RM=BAY BRANCH,Reach-1         ,10314
    1104    1544    2130     965    2913    8797    5645
River Rch & RM=BAY BRANCH,Reach-1         ,4843
    1594    2263    3157    1443    4358   13161    8602
Boundary for River Rch & Prof#=BAY BRANCH,Reach-1         , 1
Up Type= 0
Dn Type= 3
Dn Slope=0.003
Boundary for River Rch & Prof#=BAY BRANCH,Reach-1         , 2
Up Type= 0
Dn Type= 3
Dn Slope=0.003
Boundary for River Rch & Prof#=BAY BRANCH,Reach-1         , 3
Up Type= 0
Dn Type= 3
Dn Slope=0.003
Boundary for River Rch & Prof#=BAY BRANCH,Reach-1         , 4
Up Type= 0
Dn Type= 3
Dn Slope=0.003
Boundary for River Rch & Prof#=BAY BRANCH,Reach-1         , 5
Up Type= 0
Dn Type= 3
Dn Slope=0.003
Boundary for River Rch & Prof#=BAY BRANCH,Reach-1         , 6
Up Type= 0
Dn Type= 3
Dn Slope=0.003
Boundary for River Rch & Prof#=BAY BRANCH,Reach-1         , 7
Up Type= 0
Dn Type= 3
Dn Slope=0.003
DSS Import GetInterval= 0
DSS Import GetPeak= 0
DSS Import FillOption= 0

--- BAY BRANCH.f02 (steady flow) ---

Flow Title=Orig_BLE_Flow
Program Version=4.10
Number of Profiles= 7
Profile Names=10-year,25-year,50-year,1pct_min,100-year,1pct_plu,500-year
River Rch & RM=BAY BRANCH,Reach-1         ,15000
     356     457     537     207     626    1891     850
River Rch & RM=BAY BRANCH,Reach-1         ,14048
     449     584     689     267     808    2440    1107
River Rch & RM=BAY BRANCH,Reach-1         ,10314
    1104    1514    1852     742    2241    6769    3282
River Rch & RM=BAY BRANCH,Reach-1         ,4843
    1594    2219    2745    1110    3352   10123    5001
Boundary for River Rch & Prof#=BAY BRANCH,Reach-1         , 1
Up Type= 0
Dn Type= 3
Dn Slope=0.006
Boundary for River Rch & Prof#=BAY BRANCH,Reach-1         , 2
Up Type= 0
Dn Type= 3
Dn Slope=0.006
Boundary for River Rch & Prof#=BAY BRANCH,Reach-1         , 3
Up Type= 0
Dn Type= 3
Dn Slope=0.006
Boundary for River Rch & Prof#=BAY BRANCH,Reach-1         , 4
Up Type= 0
Dn Type= 3
Dn Slope=0.006
Boundary for River Rch & Prof#=BAY BRANCH,Reach-1         , 5
Up Type= 0
Dn Type= 3
Dn Slope=0.006
Boundary for River Rch & Prof#=BAY BRANCH,Reach-1         , 6
Up Type= 0
Dn Type= 3
Dn Slope=0.006
Boundary for River Rch & Prof#=BAY BRANCH,Reach-1         , 7
Up Type= 0
Dn Type= 3
Dn Slope=0.006
DSS Import GetInterval= 0
DSS Import GetPeak= 0
DSS Import FillOption= 0

--- BAY BRANCH.g01 (geometry) ---

Geom Title=Existing Conditions
Program Version=4.10

River Reach=BAY BRANCH      ,Reach-1
Reach XY= 30
      3733604.57      10187586.3      3733922.89     10187844.03
      3734070.98     10188141.34      3734037.56     10188408.27
      3734284.96     10188423.89      3734677.75     10188719.03
      3734620.69     10189687.57      3734730.91     10189886.26
      3734498.23     10190346.84      3734816.54     10190945.18
      3735333.41     10191196.15      3735987.55     10191188.67
      3736621.71     10191906.83      3736823.66     10191782.52
      3737115.69     10192066.12      3737055.19      10192284.2
      3737205.73     10192442.28      3737325.38     10192373.85
      3737902.75     10193011.81       3737898.5     10193227.32
       3738673.2     10193596.58      3738877.63     10193575.22
      3738840.65     10193739.55      3739062.79     10194006.73
      3739553.49     10194115.72      3739694.81     10194013.07
      3739641.78      10194169.4      3740084.65     10194514.52
      3740464.98     10195354.23      3741078.23     10195686.84

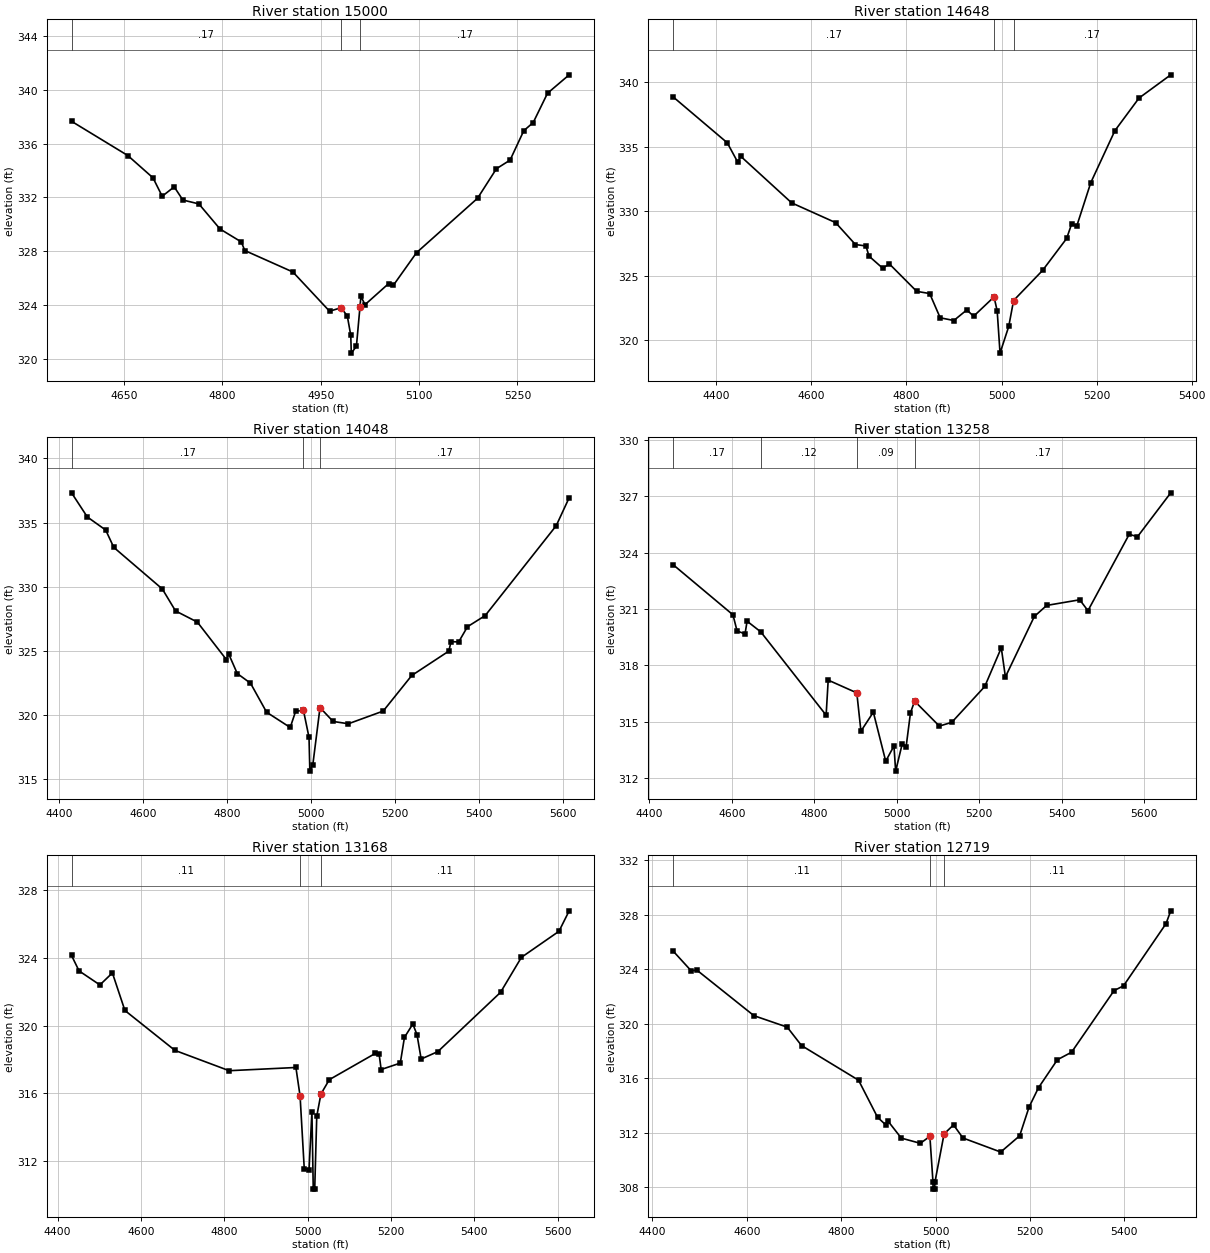
Type RM Length L Ch R = 1 ,15000   ,352,352,352
BEGIN DESCRIPTION:
BAY BRANCH 30.5
END DESCRIPTION:
XS GIS Cut Line= 3
      3733226.04     10187773.99      3733635.98     10187644.52
      3733893.76     10187440.41
#Sta/Elev= 30
  4570.1  337.67  4655.9  335.12  4694.3  333.46  4708.3  332.09  4726.6  332.79
  4739.8  331.81  4764.2  331.52  4796.5  329.65  4828.9  328.69  4834.2  328.05
  4907.6  326.45  4963.5  323.53    4981  323.79  4990.5  323.18  4995.8  321.74
  4996.6  320.41  5004.4  320.91 5009.87  323.86  5011.2  324.63  5017.6  324.02
  5053.4  325.58  5060.9  325.47  5096.1  327.89  5189.1  331.94  5217.9  334.14
  5238.7  334.78  5259.6  336.97    5274  337.58  5295.8  339.76  5328.8  341.13
#Mann= 3 , 0 , 0
  4570.1     .17       0    4981     .09       0 5009.87     .17       0
Bank Sta=4981,5009.87
XS Rating Curve= 0 ,0
Exp/Cntr=0.3,0.1

Type RM Length L Ch R = 1 ,14648   ,600,600,600
BEGIN DESCRIPTION:
BAY BRANCH 30.0
END DESCRIPTION:
XS GIS Cut Line= 3
       3733373.6     10188267.55      3733904.84     10187825.97
      3733975.33     10187477.02
#Sta/Elev= 30
  4309.2  338.87  4423.1  335.31  4444.8  333.83  4451.8  334.25  4558.6  330.65
    4651  329.12  4692.7  327.42  4714.8  327.31  4721.3  326.52  4749.9  325.59
  4764.3  325.91  4821.6  323.79  4848.9  323.62    4871  321.74  4899.7  321.53
    4927  322.35  4941.3  321.86  4984.3  323.36  4990.9  322.27  4996.9     319
  5015.2  321.07  5025.4  323.08  5086.3  325.41    5137  327.89  5147.8  329.05
    5158  328.82  5187.8  332.22  5238.5  336.25  5289.3  338.78    5356  340.58
#Mann= 3 , 0 , 0
  4309.2     .17       0  4984.3     .09       0  5025.4     .17       0
Bank Sta=4984.3,5025.4
XS Rating Curve= 0 ,0
Exp/Cntr=0.3,0.1

Type RM Length L Ch R = 1 ,14048   ,790,790,790
BEGIN DESCRIPTION:
BAY BRANCH 29.0
END DESCRIPTION:
XS GIS Cut Line= 3
      3733512.06     10188430.09      3734055.36     10188253.75
      3734637.05     10188053.79
#Sta/Elev= 30
  4428.8  337.32  4466.4  335.44  4510.2  334.42  4529.5  333.07  4645.2  329.83
  4676.7  328.12  4728.7  327.25  4797.9  324.33  4803.1  324.79  4823.9  323.24
  4855.4  322.49  4893.8  320.23  4950.1  319.04    4963   320.3  4981.6  320.38
  4994.9  318.27  4996.9  315.64    5004  316.14  5021.1  320.59  5052.3  319.51
  5088.8  319.33  5171.8  320.32  5239.8  323.09  5328.2  324.99  5333.5  325.73
  5351.6   325.7  5372.7  326.89    5415  327.76  5584.2  334.76  5615.1  336.94
#Mann= 3 , 0 , 0
  4428.8     .17       0  4981.6     .09       0  5021.1     .17       0
Bank Sta=4981.6,5021.1
XS Rating Curve= 0 ,0
Exp/Cntr=0.3,0.1

Type RM Length L Ch R = 1 ,13258   ,90,90,90
BEGIN DESCRIPTION:
BAY BRANCH 28.0
END DESCRIPTION:
XS GIS Cut Line= 3
      3734002.93     10188566.82      3734544.51      10188594.9
      3735208.48     10188623.62
#Sta/Elev= 30
  4457.7  323.36  4602.8  320.69  4612.8  319.83  4632.1  319.67  4637.1  320.35
  4670.3  319.78  4828.8  315.34  4833.8  317.21  4903.2  316.53  4913.2  314.49
  4943.3   315.5  4973.3  312.89  4993.3   313.7  4997.4  312.36  5013.4  313.82
  5022.8  313.66  5033.4  315.47  5043.4  316.09  5103.4  314.76  5133.5  314.96
  5213.5  316.87  5253.6  318.93  5263.6  317.38  5333.7   320.6  5363.7  321.19
  5443.8  321.49  5463.8  320.91  5563.9  324.98  5583.9  324.85  5664.6  327.19
#Mann= 4 ,-1 , 0
  4457.7     .17       0  4670.3     .12       0  4903.2     .09       0
  5043.4     .17       0
#XS Ineff= 2 , 0
       0  4833.8  317.21               0
Permanent Ineff=
       F       F
Bank Sta=4903.2,5043.4
XS Rating Curve= 0 ,0
Exp/Cntr=0.3,0.1

Type RM Length L Ch R = 1 ,13168   ,449,449,449
BEGIN DESCRIPTION:
BAY BRANCH 27.0
END DESCRIPTION:
XS GIS Cut Line= 3
      3734019.88     10188656.66      3734585.88     10188675.22
      3735212.28     10188713.99
#Sta/Elev= 30
  4433.7  324.15  4451.7  323.24  4501.7  322.41  4531.7  323.12  4561.7   320.9
  4681.8  318.54  4811.9  317.34    4972  317.53    4982  315.84    4992  311.55
  5003.5   311.5  5010.4  314.92  5013.6  310.34  5017.1  310.34    5022  314.65
    5032  315.96  5052.1  316.81  5162.3  318.36  5171.5  318.34  5176.5  317.41
  5222.4  317.79  5232.4  319.31  5252.5   320.1  5262.5  319.47  5272.5  318.03
  5312.6  318.47  5462.9  321.97    5513  324.04  5603.1  325.58  5627.6  326.79
#Mann= 3 , 0 , 0
  4433.7     .11       0    4982     .09       0    5032     .11       0
Bank Sta=4982,5032
XS Rating Curve= 0 ,0
Exp/Cntr=0.3,0.1

Type RM Length L Ch R = 1 ,12719   ,490,490,490
BEGIN DESCRIPTION:
BAY BRANCH 26.0
END DESCRIPTION:
XS GIS Cut Line= 3
      3734117.81     10189111.08        3734670.     10189043.61
      3735167.89     10189061.07
#Sta/Elev= 30
  4443.7  325.32    4482  323.87  4494.1  323.92    4615  320.58  4685.5  319.74
  4715.8  318.39  4836.6  315.85  4876.9  313.13  4894.7  312.56  4899.7  312.82
  4927.3   311.6  4967.6  311.22  4987.8  311.73  4994.4  308.36  4994.6  307.86
  4998.1  307.86  4998.4  308.36  5017.9  311.91  5037.9  312.57  5057.9  311.61
  5137.9  310.58    5178  311.77    5198  313.88    5218   315.3    5258  317.35
    5288   317.9  5378.1  322.42  5398.1  322.77  5488.2  327.33  5498.2  328.27
#Mann= 3 , 0 , 0
  4443.7     .11       0  4987.8     .09       0  5017.9     .11       0
#XS Ineff= 2 , 0
       0  4899.7  312.82               0
Permanent Ineff=
       F       F
Bank Sta=4987.8,5017.9
XS Rating Curve= 0 ,0
Exp/Cntr=0.3,0.1

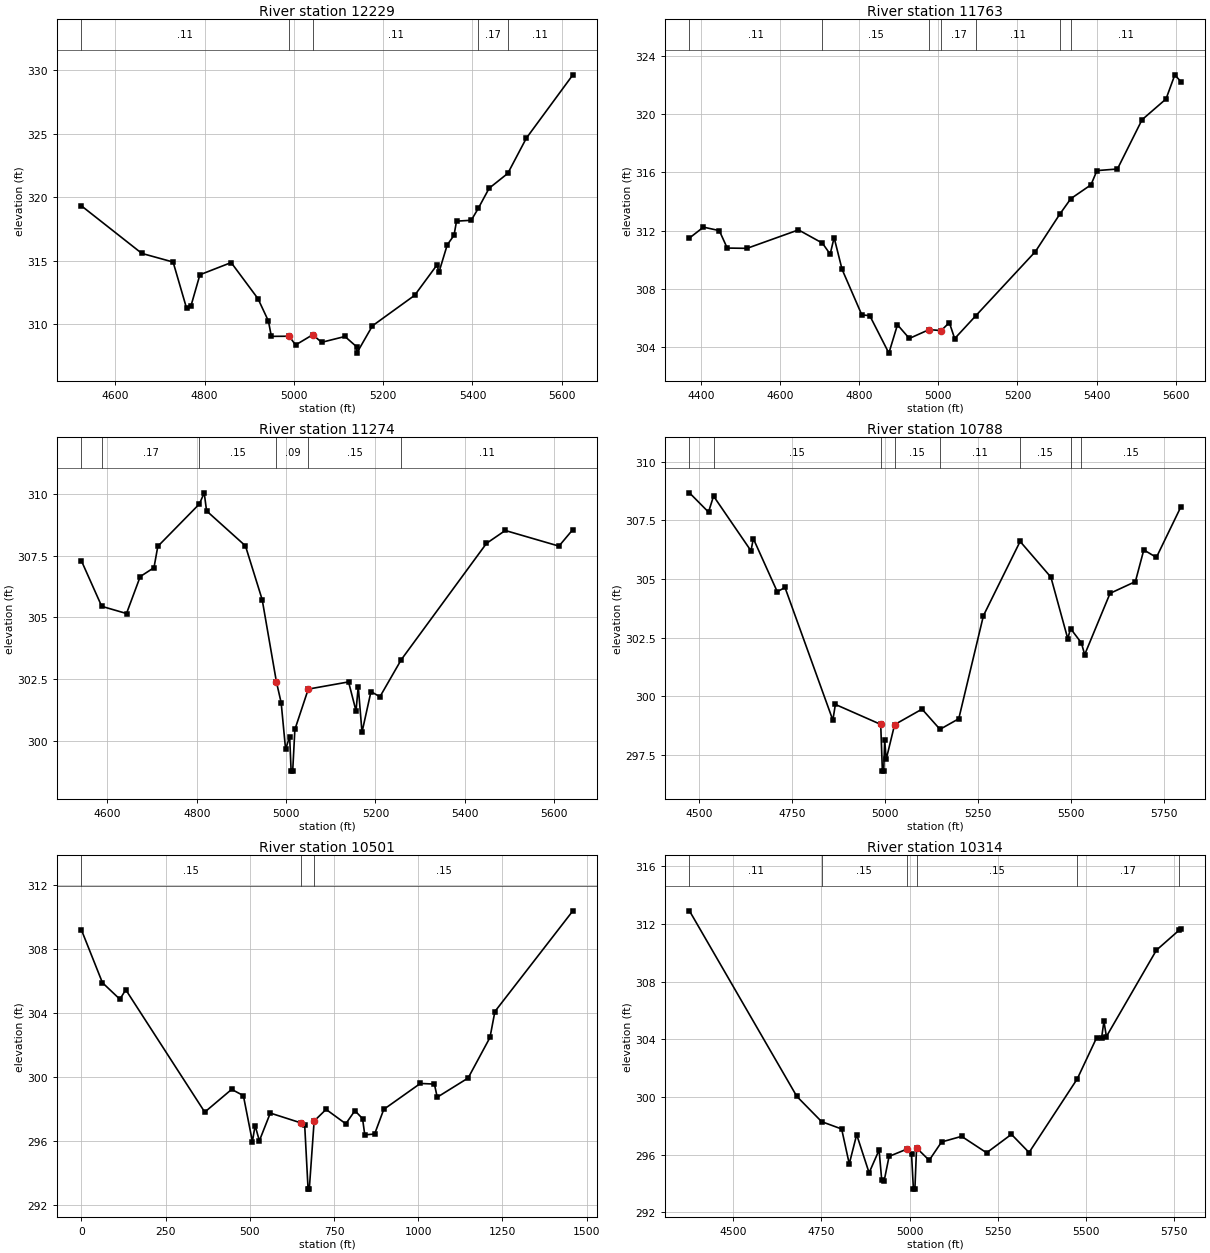
Type RM Length L Ch R = 1 ,12229   ,466,466,466
BEGIN DESCRIPTION:
BAY BRANCH 25.0
END DESCRIPTION:
XS GIS Cut Line= 3
      3734192.67     10189480.57      3734668.23     10189486.84
       3735267.9     10189311.06
#Sta/Elev= 30
  4524.4  319.31  4659.6  315.57  4729.6  314.89  4759.6  311.27  4769.6  311.44
  4789.6  313.89  4859.6  314.85  4919.6  312.01    4943  310.25  4949.6  309.04
  4989.6  309.05  5003.8  308.36  5042.4  309.17  5062.1  308.57  5114.4  309.03
  5140.6  308.22  5140.9  307.72    5176  309.87  5270.5  312.27  5320.1  314.64
  5325.3  314.13  5343.5  316.24  5358.7     317  5364.3  318.11  5397.3  318.18
  5412.9  319.11  5437.3   320.7  5479.1  321.87  5520.6  324.64  5624.9  329.63
#Mann= 5 ,-1 , 0
  4524.4     .11       0  4989.6     .09       0  5042.4     .11       0
  5412.9     .17       0  5479.1     .11       0
Bank Sta=4989.6,5042.4
XS Rating Curve= 0 ,0
Exp/Cntr=0.3,0.1

Type RM Length L Ch R = 1 ,11763   ,489,489,489
BEGIN DESCRIPTION:
BAY BRANCH 24.0
END DESCRIPTION:
XS GIS Cut Line= 3
      3734102.42     10189888.96      3734730.91     10189886.26
      3735322.53      10189727.3
#Sta/Elev= 30
  4371.5  311.49  4406.9  312.24  4446.9     312  4466.9   310.8  4516.9  310.78
  4646.9  312.05  4707.3  311.14  4726.9  310.38  4736.9  311.52  4756.9  309.34
  4806.9   306.2  4826.9  306.15  4875.2  303.57  4896.9  305.52  4926.9  304.58
  4976.9  305.19  5007.2  305.12  5027.9  305.67  5041.4  304.57  5094.3  306.13
  5245.3  310.56  5306.8  313.13  5334.8   314.2  5385.6  315.15  5400.7  316.13
  5452.4  316.24  5514.6  319.63  5575.2  321.06  5597.4  322.72  5612.6  322.25
#Mann= 7 ,-1 , 0
  4371.5     .11       0  4707.3     .15       0  4976.9     .09       0
  5007.2     .17       0  5094.3     .11       0  5306.8     .17       0
  5334.8     .11       0
Bank Sta=4976.9,5007.2
XS Rating Curve= 0 ,0
Exp/Cntr=0.3,0.1

Type RM Length L Ch R = 1 ,11274   ,486,486,486
BEGIN DESCRIPTION:
BAY BRANCH 23.0
END DESCRIPTION:
XS GIS Cut Line= 3
      3734076.91      10190142.5      3734508.23     10190296.84
      3735148.94      10190253.1
#Sta/Elev= 30
  4541.9  307.28  4587.2  305.45  4642.7  305.16  4673.4  306.65  4704.2  307.01
  4712.8  307.87  4805.9  309.58  4816.7  310.03    4822   309.3    4909  307.89
  4946.5  305.72  4978.4   302.4    4989  301.56  4998.9  299.68    5008  300.19
  5011.3   298.8  5014.8   298.8  5019.7  300.48  5049.7  302.11  5139.9   302.4
  5156.6  301.23  5161.6  302.21    5170  300.37  5190.1  302.01  5210.1   301.8
    5258   303.3  5448.7  307.99  5490.8  308.51    5611  307.88  5642.2  308.55
#Mann= 6 ,-1 , 0
  4541.9     .11       0  4587.2     .17       0  4805.9     .15       0
  4978.4     .09       0  5049.7     .15       0    5258     .11       0
Bank Sta=4978.4,5049.7
XS Rating Curve= 0 ,0
Exp/Cntr=0.3,0.1

Type RM Length L Ch R = 1 ,10788   ,287,287,287
BEGIN DESCRIPTION:
BAY BRANCH 22.0
END DESCRIPTION:
XS GIS Cut Line= 3
      3734328.78     10190299.08      3734648.23     10190716.84
      3735367.94     10190375.86
#Sta/Elev= 30
  4474.1  308.67  4525.4  307.85    4539  308.53  4639.7   306.2    4646  306.72
  4710.4  304.46  4731.2  304.64    4860  298.99  4866.8  299.66  4988.8  298.81
  4993.3  296.82  4996.8  296.82  4999.5  298.14  5003.5  297.32  5026.2   298.8
    5100  299.46  5148.3   298.6  5198.8  299.05  5265.2  303.44  5363.9   306.6
  5446.7  305.08  5492.1  302.46  5499.6  302.89  5528.8  302.28  5537.6  301.78
  5605.9  304.39  5674.1  304.89  5696.7  306.24  5730.6  305.92  5796.4  308.07
#Mann= 8 ,-1 , 0
  4474.1     .17       0    4539     .15       0  4988.8     .11       0
  5026.2     .15       0  5148.3     .11       0  5363.9     .15       0
  5499.6     .11       0  5528.8     .15       0
Bank Sta=4988.8,5026.2
XS Rating Curve= 0 ,0
Exp/Cntr=0.3,0.1

Type RM Length L Ch R = 1 ,10501   ,187,187,187
XS GIS Cut Line= 3
      3734157.81     10191100.75      3734808.17     10190925.72
      3735440.57     10190459.68
#Sta/Elev= 30
       0   309.2    62.2  305.91     114  304.88   131.5  305.47     366  297.83
   445.9  299.25   480.7  298.86   507.5  295.99   515.5  296.99   528.2  296.04
   560.6  297.77   652.5  297.15   662.8     297   672.8  293.02   676.4  293.02
   690.8  297.27   726.2     298   784.8   297.1   811.9  297.92   834.6  297.42
   841.1  296.41   870.4  296.46   897.5     298  1006.2  299.62  1047.9  299.58
  1056.3  298.76  1148.1  299.96  1212.9  302.49  1227.5  304.11  1459.1   310.4
#Mann= 3 , 0 , 0
       0     .15       0   652.5     .11       0   690.8     .15       0
Bank Sta=652.5,690.8
XS Rating Curve= 0 ,0
Exp/Cntr=0.3,0.1

Type RM Length L Ch R = 1 ,10314   ,499,499,499
BEGIN DESCRIPTION:
BAY BRANCH 21.0
END DESCRIPTION:
XS GIS Cut Line= 3
      3734523.73     10191506.66      3734945.12      10191046.3
      3735513.99      10190529.3
#Sta/Elev= 30
  4375.9  312.91  4680.3  300.04  4750.5  298.29  4807.3  297.78  4828.9  295.36
  4849.9  297.39  4885.1  294.74  4913.4  296.32  4920.8  294.27  4927.6  294.16
  4941.7  295.88  4991.7  296.38  5005.4  296.03  5010.7  293.61  5014.9  293.61
  5019.6  296.47  5055.4  295.61  5090.5  296.88  5147.3  297.27  5218.2  296.13
  5288.5  297.41  5338.5  296.15  5475.2  301.26  5529.8   304.1    5544  304.08
  5550.7  305.25  5557.7  304.19  5699.4  310.18    5763  311.55  5768.7  311.64
#Mann= 6 ,-1 , 0
  4375.9     .11       0  4750.5     .15       0  4991.7     .11       0
  5019.6     .15       0  5475.2     .17       0    5763     .11       0
Bank Sta=4991.7,5019.6
XS Rating Curve= 0 ,0
Exp/Cntr=0.3,0.1

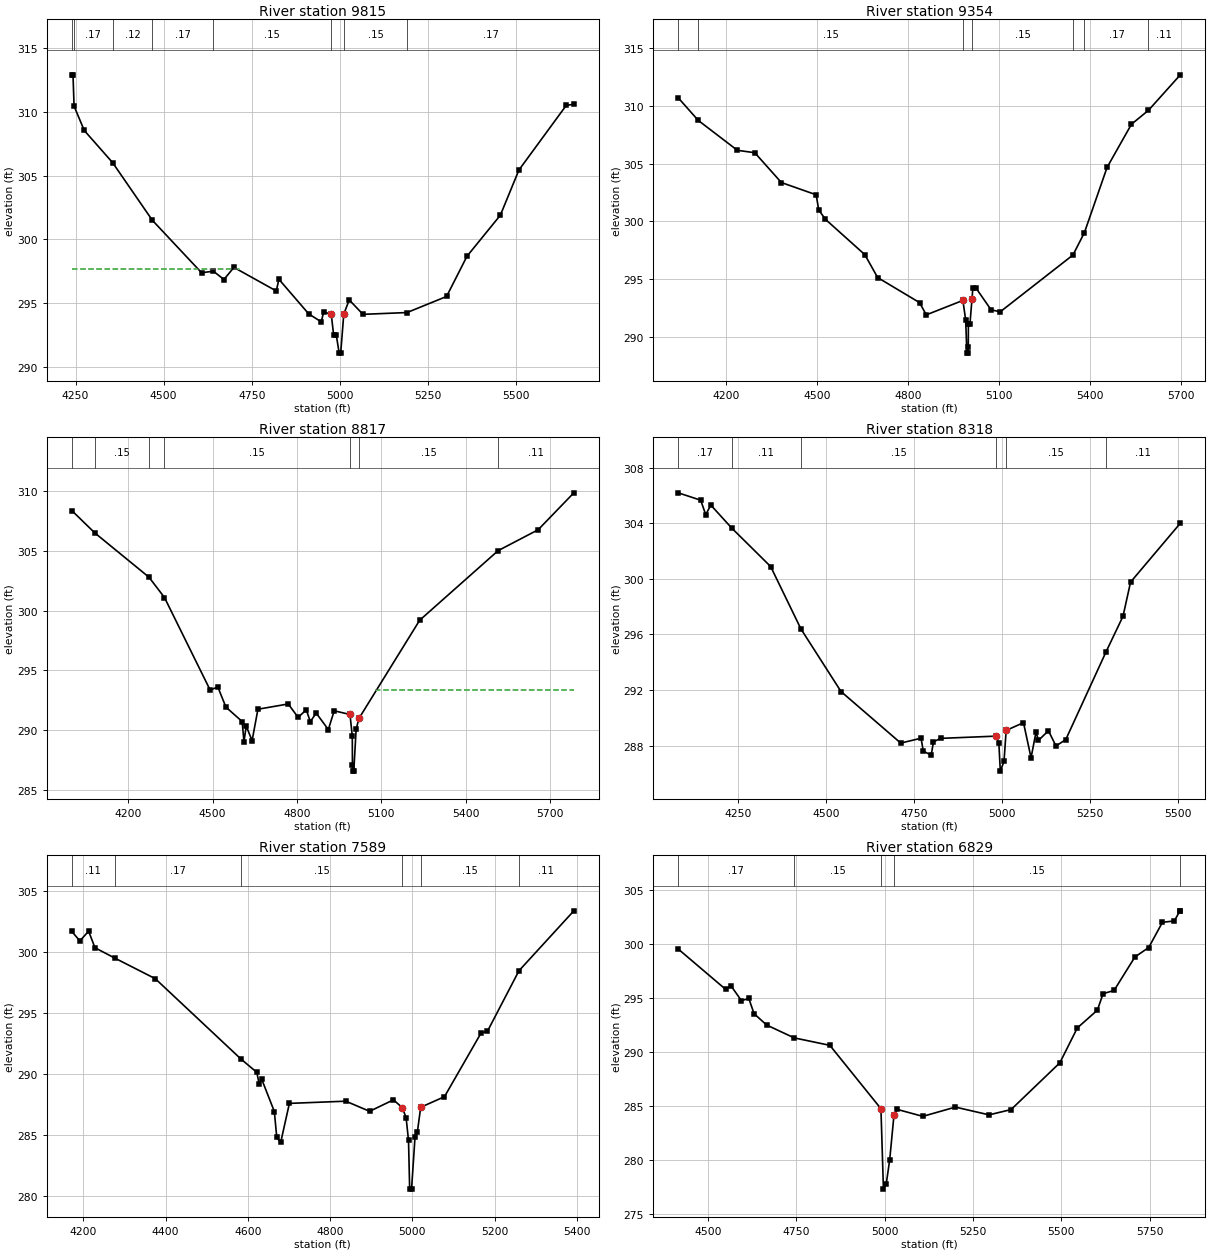
Type RM Length L Ch R = 1 ,9815    ,461,461,461
BEGIN DESCRIPTION:
BAY BRANCH 20.0
END DESCRIPTION:
XS GIS Cut Line= 3
      3734767.83     10191711.09      3735322.91      10191191.1
      3735583.12     10190580.86
#Sta/Elev= 30
  4239.4  312.89  4242.9  312.89  4245.9  310.44  4274.8  308.53  4355.2  306.01
  4467.7   301.5  4607.5  297.38  4641.1   297.5    4671  296.85  4699.3   297.8
  4819.5  295.95  4826.8  296.87  4911.3  294.16    4947  293.53  4953.8   294.3
  4975.3  294.13  4982.2  292.48  4989.5  292.52  4997.8  291.08  5002.1  291.08
  5010.9  294.14  5026.3  295.25  5065.3  294.12  5190.3  294.26  5302.4  295.52
  5360.5  298.68    5455  301.89  5507.6  305.43    5642   310.5  5663.4  310.58
#Mann= 8 ,-1 , 0
  4239.4     .12       0  4245.9     .17       0  4355.2     .12       0
  4467.7     .17       0  4641.1     .15       0  4975.3     .11       0
  5010.9     .15       0  5190.3     .17       0
#XS Ineff= 2 , 0
       0  4713.5  297.67               0
Permanent Ineff=
       F       F
Bank Sta=4975.3,5010.9
XS Rating Curve= 0 ,0
Exp/Cntr=0.3,0.1

Type RM Length L Ch R = 1 ,9354    ,537,537,537
BEGIN DESCRIPTION:
BAY BRANCH 19.0
END DESCRIPTION:
XS GIS Cut Line= 3
      3735217.86     10192061.05      3735736.04     10191255.17
      3735817.85     10190561.07
#Sta/Elev= 30
  4041.9   310.7  4108.2  308.74    4237  306.16  4294.5  305.95  4382.3  303.37
  4497.2  302.31  4505.5     301  4527.6  300.19  4657.7  297.13    4700  295.15
  4838.4  292.98  4860.5  291.92  4981.3  293.17  4990.6  291.47  4994.4  288.61
  4998.7  288.61  4999.1  289.11  4999.5  291.11  5004.6  291.11  5011.2  293.26
  5014.2  294.21  5024.3  294.25  5074.6  292.35  5104.8  292.19  5344.6   297.1
  5382.3  299.03  5457.2  304.68  5537.8  308.42  5593.8  309.62  5698.9  312.69
#Mann= 7 ,-1 , 0
  4041.9     .11       0  4108.2     .15       0  4981.3     .11       0
  5011.2     .15       0  5344.6     .11       0  5382.3     .17       0
  5593.8     .11       0
Bank Sta=4981.3,5011.2
XS Rating Curve= 0 ,0
Exp/Cntr=0.3,0.1

Type RM Length L Ch R = 1 ,8817    ,499,499,499
BEGIN DESCRIPTION:
BAY BRANCH 18.0
END DESCRIPTION:
XS GIS Cut Line= 3
      3735517.82     10192111.11      3736133.11     10191321.16
      3736314.71     10190557.55
#Sta/Elev= 30
  3998.7  308.38  4080.4  306.51  4273.3   302.8  4328.5   301.1  4490.9  293.36
  4518.4  293.61    4547  291.93  4604.9  290.72  4611.3  289.04  4619.4  290.34
  4640.2  289.12    4661  291.75  4768.7  292.19    4804  291.07  4832.9   291.7
  4847.4  290.71  4868.2  291.43  4911.4  290.05  4932.4  291.62  4988.5  291.31
  4996.7   289.5  4997.2  287.07  4997.6  286.57    5002  286.57  5010.4  290.09
  5020.6  290.99  5236.5   299.2  5515.4  305.02  5657.9  306.77  5784.9  309.86
#Mann= 7 ,-1 , 0
  3998.7     .11       0  4080.4     .15       0  4273.3     .17       0
  4328.5     .15       0  4988.5     .12       0  5020.6     .15       0
  5515.4     .11       0
#XS Ineff= 2 , 0
       0                  5081.2       0  293.32
Permanent Ineff=
       F       F
Bank Sta=4988.5,5020.6
XS Rating Curve= 0 ,0
Exp/Cntr=0.3,0.1

Type RM Length L Ch R = 1 ,8318    ,729,729,729
BEGIN DESCRIPTION:
BAY BRANCH 17.0
END DESCRIPTION:
XS GIS Cut Line= 3
      3735701.48     10192204.54      3736424.59     10191633.65
      3736767.85     10191261.07
#Sta/Elev= 30
  4078.7   306.2  4142.5  305.67  4156.9  304.63  4171.3  305.32  4230.9  303.66
  4341.6  300.89  4427.6   296.4  4541.7  291.89  4711.5  288.18  4769.3  288.53
  4775.7  287.59  4798.2  287.32  4804.6  288.28  4825.8  288.52  4982.5  288.68
  4990.6  288.17  4994.7  286.16  5005.2  286.86  5011.3  289.09  5060.6  289.65
  5082.1  287.12  5096.3  288.98  5103.1  288.37  5131.5  289.07    5153  287.97
  5180.8  288.43    5295  294.73  5343.6  297.31  5365.1  299.77  5506.6  304.01
#Mann= 6 ,-1 , 0
  4078.7     .17       0  4230.9     .11       0  4427.6     .15       0
  4982.5     .09       0  5011.3     .15       0    5295     .11       0
Bank Sta=4982.5,5011.3
XS Rating Curve= 0 ,0
Exp/Cntr=0.3,0.1

Type RM Length L Ch R = 1 ,7589    ,760,760,760
BEGIN DESCRIPTION:
BAY BRANCH 16.0
END DESCRIPTION:
XS GIS Cut Line= 3
      3736383.33     10192484.18      3736818.27     10191779.15
      3737001.84     10191431.65
#Sta/Elev= 30
  4171.6  301.71  4191.3  300.93  4212.6  301.73    4228  300.37  4276.8  299.51
  4374.7  297.83  4582.9  291.24  4621.7  290.14  4627.7  289.16  4633.6  289.58
  4664.4  286.92  4670.3  284.79  4679.8  284.38    4701  287.59  4838.2  287.77
  4896.2  286.94  4954.1  287.88  4975.4  287.25  4984.9  286.43  4990.8  284.55
  4993.6  280.55  4998.2  280.55  5006.6  284.82  5012.3  285.23  5020.4  287.27
  5078.3  288.14  5167.5  293.38  5182.8  293.51  5259.5  298.48    5393   303.4
#Mann= 6 ,-1 , 0
  4171.6     .11       0  4276.8     .17       0  4582.9     .15       0
  4975.4     .09       0  5020.4     .15       0  5259.5     .11       0
Bank Sta=4975.4,5020.4
XS Rating Curve= 0 ,0
Exp/Cntr=0.3,0.1

Type RM Length L Ch R = 1 ,6829    ,550,550,550
BEGIN DESCRIPTION:
BAY BRANCH 14.0
END DESCRIPTION:
XS GIS Cut Line= 3
       3736658.4     10192650.06      3737136.54     10192314.74
      3737367.85     10191511.06
#Sta/Elev= 30
    4416  299.55  4550.3  295.81  4565.1  296.15  4594.8  294.77  4615.7  294.97
  4630.5  293.56  4666.2  292.51  4744.1  291.32  4844.9  290.63  4989.4  284.76
  4996.5  277.31  5004.5  277.81  5014.2  280.03  5026.3  284.17    5035   284.7
  5107.9  284.05    5200  284.91  5295.2  284.19  5357.6  284.68  5495.5  289.01
  5544.9  292.24  5601.7  293.89  5617.8  295.41    5649  295.72    5708  298.82
  5746.9  299.69  5785.8  302.03  5819.4  302.15  5835.2  303.09  5836.3  303.09
#Mann= 5 ,-1 , 0
    4416     .17       0  4744.1     .15       0  4989.4     .09       0
  5026.3     .15       0  5835.2     .11       0
Bank Sta=4989.4,5026.3
XS Rating Curve= 0 ,0
Exp/Cntr=0.3,0.1

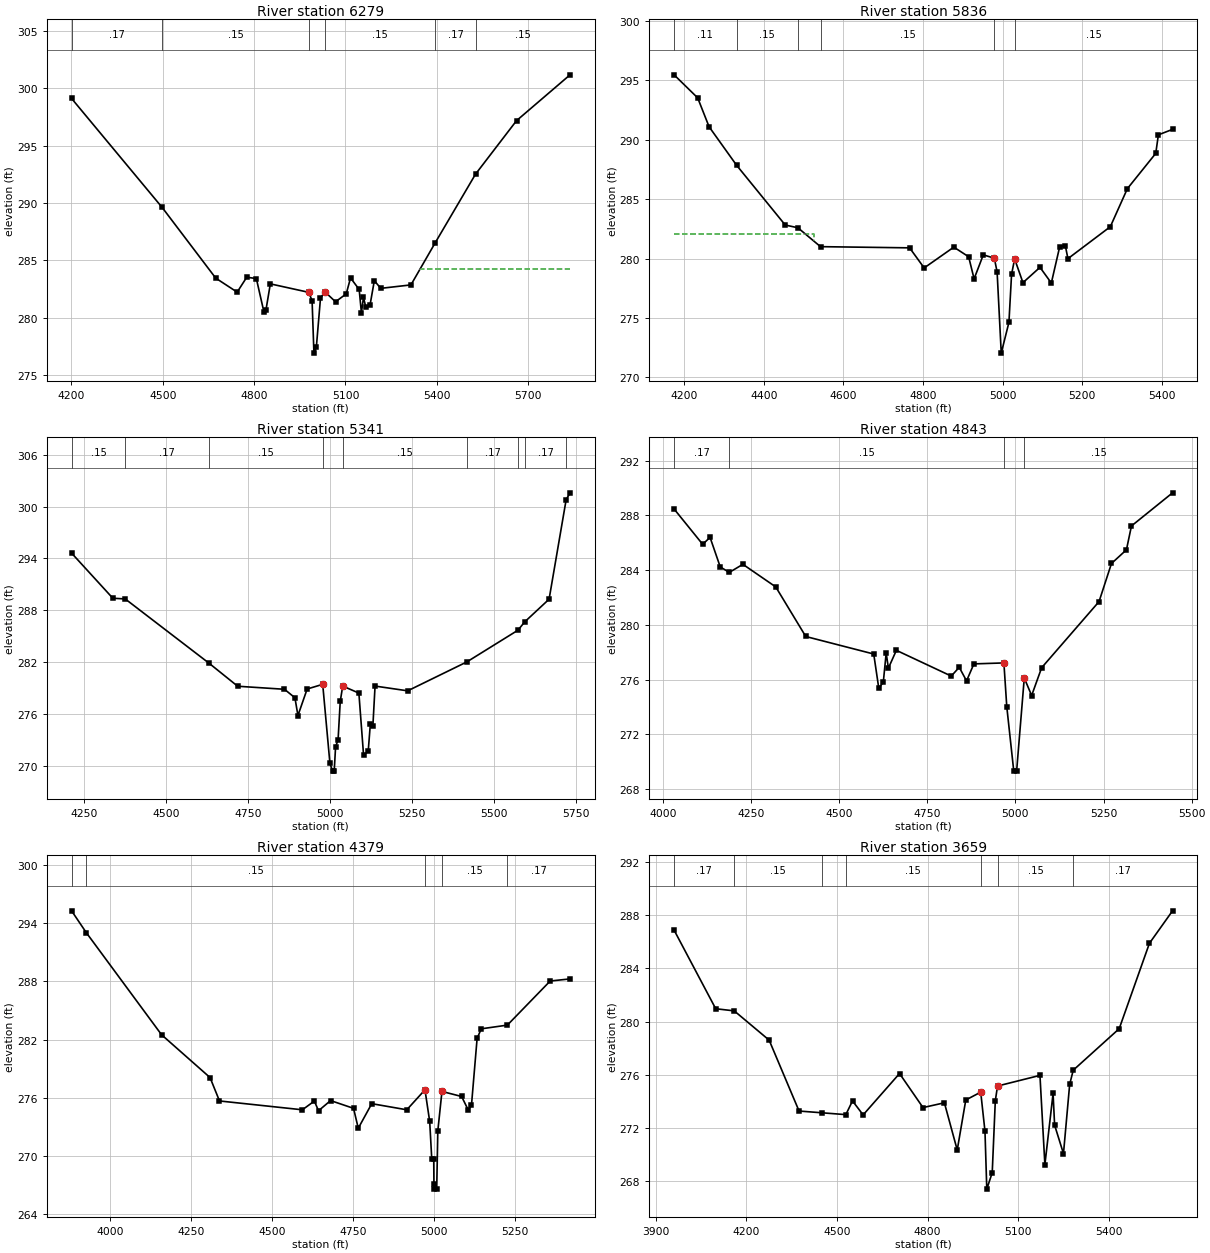
Type RM Length L Ch R = 1 ,6279    ,443,443,443
BEGIN DESCRIPTION:
BAY BRANCH 13.0
END DESCRIPTION:
XS GIS Cut Line= 3
       3736699.3     10192829.64      3737456.86     10192575.35
      3738031.22     10191965.96
#Sta/Elev= 30
  4200.9   299.1  4498.3  289.61  4674.1  283.46  4744.5  282.24    4776  283.54
  4807.5  283.42  4832.3  280.52  4839.1   280.7  4853.4  282.96    4980  282.22
  4990.5  281.48  4996.5  276.93  5004.4  277.43    5018   281.7  5032.2  282.28
  5067.4   281.4  5102.6  282.09  5116.7  283.48  5145.1  282.47  5152.4  280.44
  5159.2  281.78  5166.5  280.97  5180.7  281.11  5194.8  283.24  5215.9  282.57
    5315  282.87  5395.2  286.56    5527  292.51  5661.7  297.17  5837.4  301.16
#Mann= 6 ,-1 , 0
  4200.9     .17       0  4498.3     .15       0    4980     .09       0
  5032.2     .15       0  5395.2     .17       0    5527     .15       0
#XS Ineff= 2 , 0
       0                  5343.3       0  284.22
Permanent Ineff=
       F       F
Bank Sta=4980,5032.2
XS Rating Curve= 0 ,0
Exp/Cntr=0.3,0.1

Type RM Length L Ch R = 1 ,5836    ,495,495,495
BEGIN DESCRIPTION:
BAY BRANCH 12.0
END DESCRIPTION:
XS GIS Cut Line= 3
      3737026.59     10193300.16      3737739.85     10192884.97
      3738017.82      10192561.1
#Sta/Elev= 30
  4174.7  295.47    4234  293.53  4262.6   291.1  4331.7  287.86  4453.9  282.83
  4485.7   282.6  4542.5  281.01  4766.3  280.91  4802.9  279.22  4877.4  280.97
  4914.6  280.16  4928.3   278.3  4951.4  280.32  4979.1  280.04  4986.1  278.89
  4996.5  272.05  5015.8  274.64  5022.4  278.67  5030.1  279.98    5051  277.98
  5093.8  279.27  5122.3  277.95  5143.2  280.99  5157.4   281.1    5164     280
  5270.5  282.69  5313.3  285.89  5384.6  288.86  5391.2  290.42  5426.8  290.88
#Mann= 6 ,-1 , 0
  4174.7     .11       0  4331.7     .15       0  4485.7     .17       0
  4542.5     .15       0  4979.1     .09       0  5030.1     .15       0
#XS Ineff= 2 , 0
       0  4524.9   282.1               0
Permanent Ineff=
       F       F
Bank Sta=4979.1,5030.1
XS Rating Curve= 0 ,0
Exp/Cntr=0.3,0.1

Type RM Length L Ch R = 1 ,5341    ,498,498,498
BEGIN DESCRIPTION:
BAY BRANCH 11.0
END DESCRIPTION:
XS GIS Cut Line= 3
       3737115.3     10193391.06       3737882.9     10193210.74
      3738367.84     10192661.08
#Sta/Elev= 30
  4211.5  294.62  4337.4  289.41  4375.2  289.33  4630.7  281.92  4718.5  279.25
  4861.3   278.9  4893.2  277.92  4902.4  275.87  4930.5  278.93    4978  279.47
    5000  270.36  5008.2  269.45  5013.1  269.45  5017.3  272.25  5024.9  273.06
  5031.5   277.5  5039.1  279.27  5088.4  278.46  5102.7  271.31  5116.9  271.74
  5123.5  274.94  5131.1  274.63  5137.8  279.27  5237.3  278.72    5418  282.06
    5574  285.72  5594.3  286.67    5669   289.3  5721.1  300.79    5733  301.58
#Mann= 9 ,-1 , 0
  4211.5     .15       0  4375.2     .17       0  4630.7     .15       0
    4978     .09       0  5039.1     .15       0    5418     .17       0
    5574     .11       0  5594.3     .17       0  5721.1     .11       0
Bank Sta=4978,5039.1
XS Rating Curve= 0 ,0
Exp/Cntr=0.3,0.1

Type RM Length L Ch R = 1 ,4843    ,464,464,464
BEGIN DESCRIPTION:
BAY BRANCH 10.0
END DESCRIPTION:
XS GIS Cut Line= 3
      3737702.79     10194189.79      3738296.64     10193425.22
      3738626.18     10193124.98
#Sta/Elev= 30
  4031.9  288.46    4113  285.88  4133.9  286.39  4162.8  284.23  4188.5  283.83
  4227.1  284.42  4320.3  282.77  4405.4  279.15  4598.2  277.87  4612.6  275.36
  4625.4  275.83  4633.5  277.94  4639.8  276.84  4662.4  278.14  4818.1  276.26
  4840.7   276.9  4861.5  275.91  4882.3  277.15  4967.4  277.22  4975.6  274.02
  4995.4  269.32  5003.5  269.32  5025.2  276.12  5046.1  274.84  5074.5  276.87
  5237.3   281.7  5272.5  284.48    5315  285.48  5329.2  287.22  5445.8  289.64
#Mann= 4 ,-1 , 0
  4031.9     .17       0  4188.5     .15       0  4967.4     .09       0
  5025.2     .15       0
Bank Sta=4967.4,5025.2
XS Rating Curve= 0 ,0
Exp/Cntr=0.3,0.1

Type RM Length L Ch R = 1 ,4379    ,720,720,720
BEGIN DESCRIPTION:
BAY BRANCH 9.0
END DESCRIPTION:
XS GIS Cut Line= 3
      3737967.85     10194461.08      3738640.39     10193566.11
      3738709.75     10193150.46
#Sta/Elev= 30
  3880.5  295.26  3925.8  293.02  4158.6   282.5  4308.5  278.09  4337.7  275.68
  4593.9  274.77    4631  275.67  4643.8  274.67  4681.1  275.72  4752.1  274.92
  4766.7  272.87  4808.4   275.4  4916.7  274.77  4972.9  276.83  4987.5  273.57
  4993.8  269.75    5000  269.75  5000.6   267.1  5001.1   266.6  5009.2   266.6
  5012.6  272.59  5025.4  276.66  5086.2  276.14  5106.5  274.76  5116.6  275.22
  5134.1  282.13    5147  283.11  5227.6  283.49  5359.9  288.03  5421.4  288.25
#Mann= 5 ,-1 , 0
  3880.5     .17       0  3925.8     .15       0  4972.9     .09       0
  5025.4     .15       0  5227.6     .17       0
Bank Sta=4972.9,5025.4
XS Rating Curve= 0 ,0
Exp/Cntr=0.3,0.1

Type RM Length L Ch R = 1 ,3659    ,387,387,387
BEGIN DESCRIPTION:
BAY BRANCH 8.0
END DESCRIPTION:
XS GIS Cut Line= 3
      3738198.77      10194576.6      3738945.45     10193854.69
      3739078.99     10193258.87
#Sta/Elev= 30
  3961.4  286.88  4099.1  280.97  4160.4  280.81  4275.9  278.61  4374.9  273.28
  4449.6  273.15  4529.6  273.01  4551.7  274.04  4586.9  272.99  4707.3   276.1
    4785  273.54  4855.7   273.9  4898.2  270.35  4926.5  274.11  4975.9   274.7
    4990  271.76    4996  267.41    5014  268.65  5024.2  274.06  5031.6  275.16
  5171.9  275.96  5188.2  269.25  5215.3   274.6  5220.4  272.22  5249.7  270.08
  5270.2  275.28    5282  276.35  5434.1  279.47  5534.1  285.89  5610.6  288.33
#Mann= 7 ,-1 , 0
  3961.4     .17       0  4160.4     .15       0  4449.6     .17       0
  4529.6     .15       0  4975.9     .09       0  5031.6     .15       0
    5282     .17       0
Bank Sta=4975.9,5031.6
XS Rating Curve= 0 ,0
Exp/Cntr=0.3,0.1

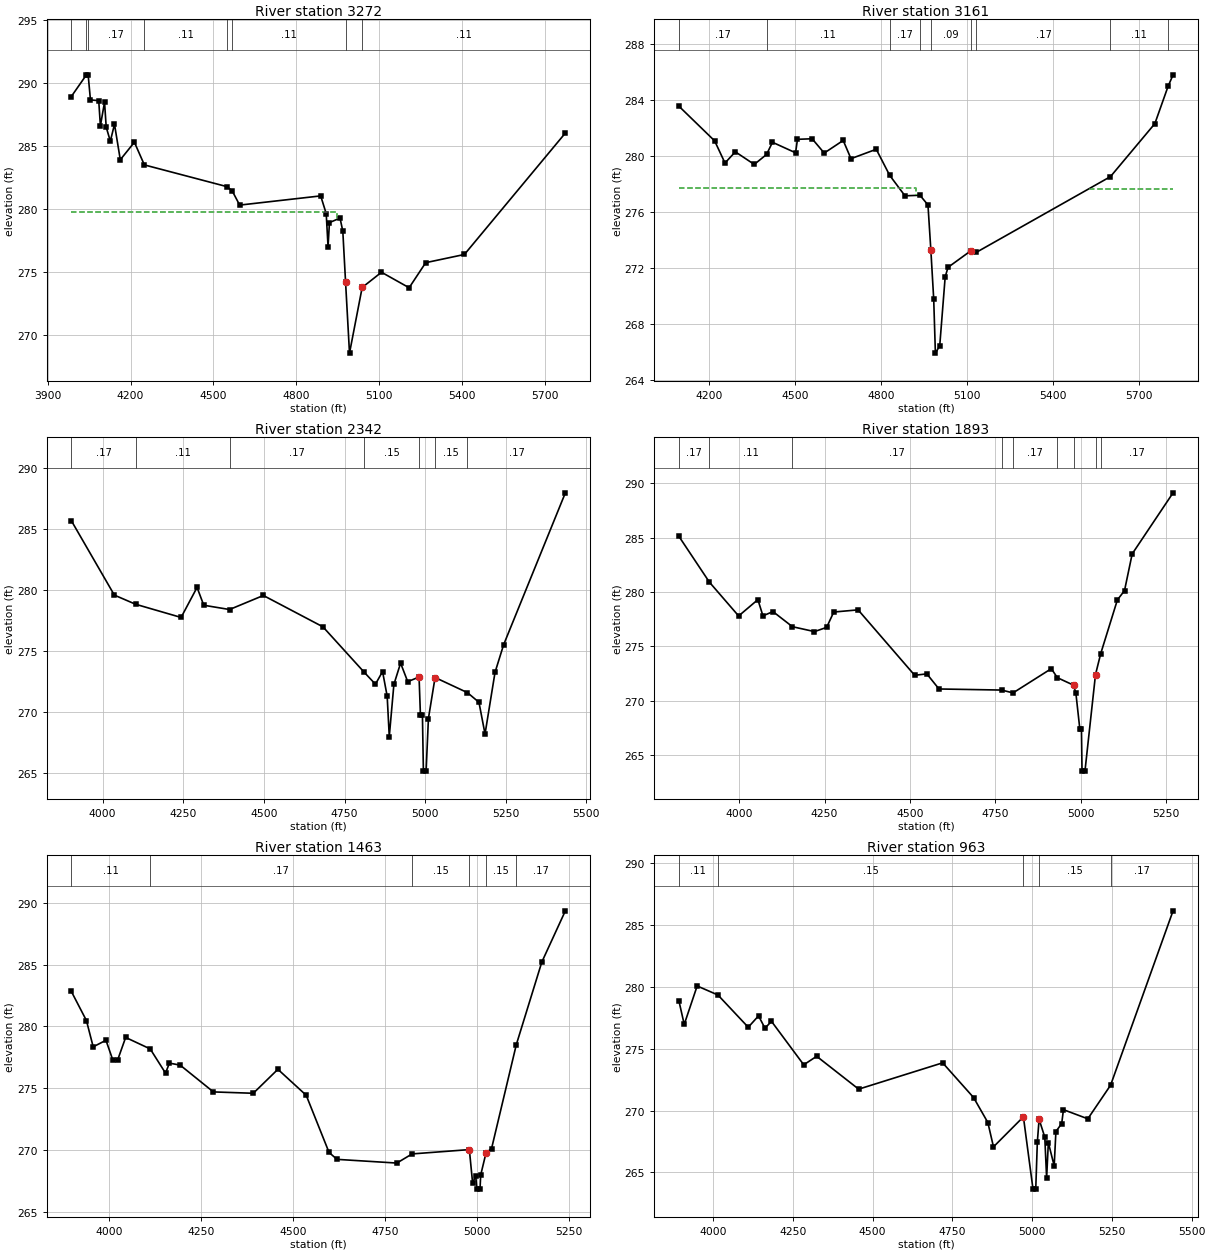
Type RM Length L Ch R = 1 ,3272    ,111,111,111
BEGIN DESCRIPTION:
BAY BRANCH 7.0
END DESCRIPTION:
XS GIS Cut Line= 4
      3738534.97     10194674.69       3739208.9     10194221.72
      3739215.62     10194019.24      3739222.78     10193245.68
#Sta/Elev= 30
  3985.4  288.91  4040.3  290.64  4046.6  290.63  4054.9  288.65  4084.9  288.59
  4090.9  286.59  4105.9  288.47  4111.9  286.49  4126.9  285.37  4141.9  286.72
  4162.9   283.9  4213.9  285.29    4250  283.49  4549.8  281.76  4568.3  281.41
  4594.9   280.3  4888.1  281.03  4908.1  279.63  4914.8     277  4919.8  278.91
  4958.1  279.27  4968.2  278.23  4978.2  274.17  4992.4  268.55  5038.2  273.76
  5108.2  274.97  5208.2  273.74  5268.2  275.73  5408.2  276.38  5773.6  286.02
#Mann= 8 ,-1 , 0
  3985.4     .17       0  4040.3     .11       0  4046.6     .17       0
    4250     .11       0  4549.8     .17       0  4568.3     .11       0
  4978.2     .06       0  5038.2     .11       0
#XS Ineff= 2 , 0
       0  4948.1  279.78               0
Permanent Ineff=
       F       F
Bank Sta=4978.2,5038.2
XS Rating Curve= 0 ,0
Exp/Cntr=0.3,0.1

Type RM Length L Ch R = 1 ,3161    ,819,819,819
BEGIN DESCRIPTION:
BAY BRANCH 6.0
END DESCRIPTION:
XS GIS Cut Line= 4
      3738954.11     10194819.75      3739315.59     10194275.06
      3739325.53     10194024.18      3739362.49     10193207.72
#Sta/Elev= 30
  4095.2  283.54  4219.6  281.07  4255.7  279.49  4291.7  280.29  4357.7  279.39
  4400.6   280.1  4421.1  280.97  4501.7  280.22  4508.3  281.18  4559.4  281.22
  4601.5   280.2  4667.7   281.1  4694.7   279.8  4782.9  280.47  4829.7  278.61
    4883  277.15  4935.2  277.19  4963.1   276.5  4973.1   273.3  4983.1  269.79
    4989  265.93  5004.1  266.45  5023.1  271.37  5033.1  272.05  5113.2  273.24
  5131.8  273.12  5599.2  278.52  5753.9   282.3  5799.8  284.95  5817.3  285.78
#Mann= 9 ,-1 , 0
  4095.2     .17       0  4400.6     .11       0  4829.7     .17       0
  4935.2     .15       0  4973.1     .09       0  5113.2     .15       0
  5131.8     .17       0  5599.2     .11       0  5799.8     .17       0
#XS Ineff= 2 , 0
       0  4923.1  277.73  5523.6       0  277.67
Permanent Ineff=
       F       F
Bank Sta=4973.1,5113.2
XS Rating Curve= 0 ,0
Exp/Cntr=0.3,0.1

Type RM Length L Ch R = 1 ,2342    ,449,449,449
BEGIN DESCRIPTION:
BAY BRANCH 5.0
END DESCRIPTION:
XS GIS Cut Line= 3
       3739010.5     10195062.72      3739706.76     10194229.65
      3740139.11     10194118.63
#Sta/Elev= 30
  3902.6   285.7  4036.3  279.59  4102.3  278.84  4243.2  277.76  4292.7  280.22
  4313.5  278.76  4393.5  278.41  4498.3  279.56  4683.1  276.99  4810.3  273.29
  4845.8  272.29  4867.9  273.33  4882.2  271.31  4888.7     268    4903  272.27
  4923.8  274.02  4945.9   272.5  4981.1  272.88  4985.3  269.78  4991.5  269.78
  4994.5  265.17  5002.9  265.17  5010.1  269.48  5030.7  272.84  5131.1   271.6
  5166.8  270.81  5185.6  268.21  5216.6  273.26  5243.2  275.52  5434.7  287.97
#Mann= 7 ,-1 , 0
  3902.6     .17       0  4102.3     .11       0  4393.5     .17       0
  4810.3     .15       0  4981.1     .09       0  5030.7     .15       0
  5131.1     .17       0
#XS Ineff= 2 , 0
       0  4668.8  277.05               0
Permanent Ineff=
       F       F
Bank Sta=4981.1,5030.7
XS Rating Curve= 0 ,0
Exp/Cntr=0.3,0.1

Type RM Length L Ch R = 1 ,1893    ,430,430,430
BEGIN DESCRIPTION:
BAY BRANCH 4.0
END DESCRIPTION:
XS GIS Cut Line= 3
      3739073.79     10195130.11      3740029.02     10194443.48
      3740241.01     10194275.14
#Sta/Elev= 30
  3823.6  285.12  3912.8  280.91  3998.4   277.8  4054.8   279.3  4069.6  277.81
    4099   278.2    4156  276.81  4220.6  276.36  4256.2  276.75    4277  278.16
  4348.3  278.36    4514  272.34  4549.6  272.47  4585.2  271.08  4768.6  270.98
  4802.1  270.72  4914.2  272.95  4931.8  272.12  4979.3  271.43  4986.2  270.67
  4997.8  267.36  5002.4  267.36  5004.1  263.52  5012.7  263.52  5043.6  272.41
  5058.8  274.33  5107.7  279.28  5128.5  280.13    5151  283.51  5270.7  289.13
#Mann= 9 ,-1 , 0
  3823.6     .17       0  3912.8     .11       0    4156     .17       0
  4768.6     .15       0  4802.1     .17       0  4931.8     .15       0
  4979.3     .09       0  5043.6     .15       0  5058.8     .17       0
Bank Sta=4979.3,5043.6
XS Rating Curve= 0 ,0
Exp/Cntr=0.3,0.1

Type RM Length L Ch R = 1 ,1463    ,500,500,500
BEGIN DESCRIPTION:
BAY BRANCH 3.0
END DESCRIPTION:
XS GIS Cut Line= 3
      3739161.39     10195230.48      3740178.61     10194806.87
      3740317.87     10194611.04
#Sta/Elev= 30
  3898.1  282.84  3939.3  280.47  3957.7  278.34  3992.4  278.87  4010.8  277.29
  4024.3  277.29  4045.9   279.1  4112.6  278.17  4154.2  276.21  4164.7  277.02
  4193.9  276.86  4284.2  274.69  4392.6  274.58  4459.4  276.52  4536.3  274.42
  4598.4  269.79    4620  269.23  4782.5  268.93    4824  269.67  4979.5  270.02
  4988.3  267.33  4996.9  267.87  4999.9  266.82  5008.5  266.82  5010.3  267.96
    5025  269.78  5039.8   270.1  5107.1  278.52  5176.3   285.2  5240.3  289.35
#Mann= 6 ,-1 , 0
  3898.1     .11       0  4112.6     .17       0    4824     .15       0
  4979.5     .09       0    5025     .15       0  5107.1     .17       0
Bank Sta=4979.5,5025
XS Rating Curve= 0 ,0
Exp/Cntr=0.3,0.1

Type RM Length L Ch R = 1 ,963     ,490,490,490
BEGIN DESCRIPTION:
BAY BRANCH 2.0
END DESCRIPTION:
XS GIS Cut Line= 3
      3739251.42     10195340.51      3740344.92     10195167.52
      3740517.85     10194761.07
#Sta/Elev= 30
  3892.9  278.87  3909.5  276.98    3950  280.09  4015.1  279.36  4110.1  276.75
  4142.4  277.67  4162.6  276.67  4182.9  277.23  4284.1  273.71  4324.6   274.4
  4456.2  271.74  4719.5  273.87  4816.5  271.06  4861.2  269.04  4878.8  267.07
  4972.6   269.5  5002.7  263.65  5011.3  263.65  5016.3  267.46  5021.8   269.3
  5039.6  267.86  5045.4  264.55  5050.8  267.42  5069.1  265.53  5074.5  268.31
  5092.7  268.96  5098.1  270.08  5174.5  269.34  5245.9  272.06  5441.7  286.17
#Mann= 5 ,-1 , 0
  3892.9     .11       0  4015.1     .15       0  4972.6     .09       0
  5021.8     .15       0  5245.9     .17       0
#XS Ineff= 2 , 0
       0  4719.5  273.87               0
Permanent Ineff=
       F       F
Bank Sta=4972.6,5021.8
XS Rating Curve= 0 ,0
Exp/Cntr=0.3,0.1