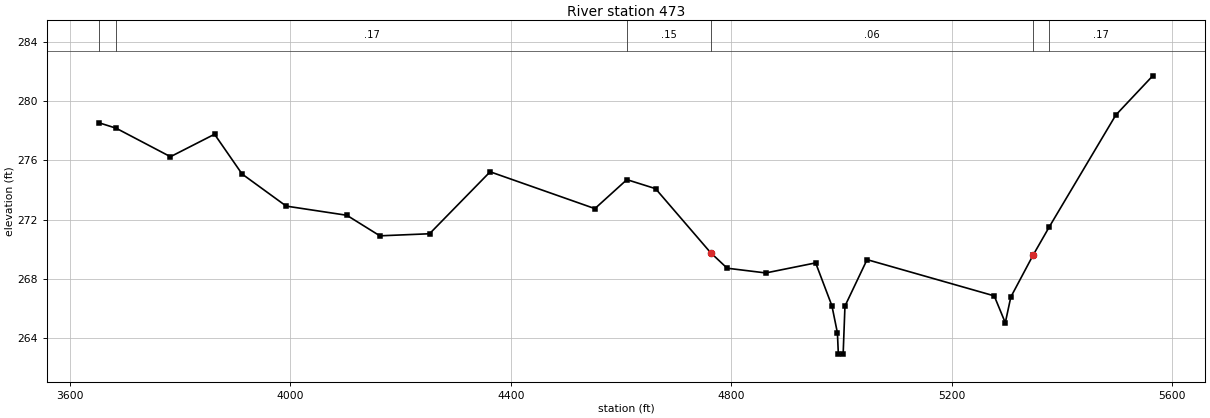
HEC-RAS study BAY BRANCH.prj: BAY BRANCH Base Level Engineering

--- BAY BRANCH.g01 (geometry) --- (continued)

Type RM Length L Ch R = 1 ,473     ,0,0,0
BEGIN DESCRIPTION:
BAY BRANCH 1.0
END DESCRIPTION:
XS GIS Cut Line= 3
      3739348.64     10195416.89      3740694.92     10195457.62
      3740741.37     10194894.33
#Sta/Elev= 30
  3653.1  278.54  3683.7  278.18  3782.4  276.25  3862.4  277.77  3912.4  275.08
  3992.5  272.91  4102.5  272.29  4162.5   270.9  4252.6  271.04  4362.6  275.23
  4552.7  272.74  4610.8   274.7  4662.8  274.09  4762.8  269.76  4792.8  268.71
  4862.9  268.39  4953.4  269.07  4982.9  266.17  4992.9  264.34  4994.6   262.9
  5003.3   262.9  5006.6  266.15  5046.7  269.29  5277.5  266.84  5297.6  265.02
  5307.6  266.76  5347.7  269.57  5377.8  271.53  5498.2  279.07  5565.2  281.72
#Mann= 6 ,-1 , 0
  3653.1     .11       0  3683.7     .17       0  4610.8     .15       0
  4762.8     .06       0  5347.7     .15       0  5377.8     .17       0
Bank Sta=4762.8,5347.7
XS Rating Curve= 0 ,0
Exp/Cntr=0.3,0.1

Chan Stop Cuts=-1
Use User Specified Reach Order=0
Composite Channel Slope=5