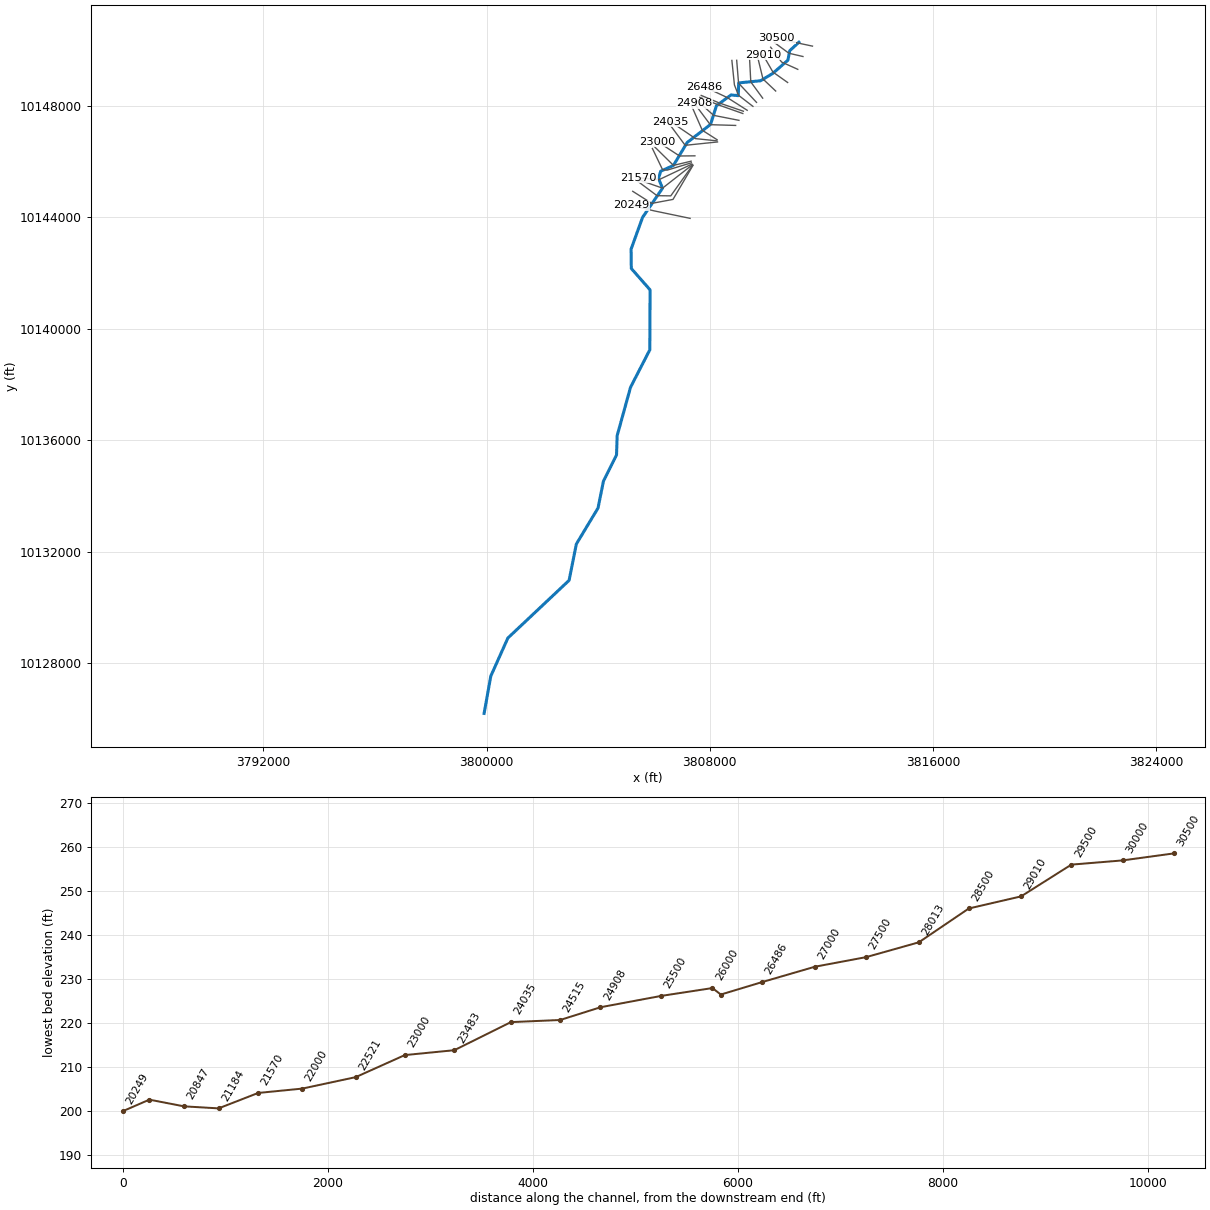
--- BELL CREEK.prj (project) ---

Proj Title=BELL CREEK Base Level Engineering
Current Plan=p01
Default Exp/Contr=0.3,0.1
English Units
Geom File=g01
Flow File=f01
Flow File=f02
Plan File=p01
Y Axis Title=Elevation
X Axis Title(PF)=Main Channel Distance
X Axis Title(XS)=Station
BEGIN DESCRIPTION:
BELL CREEK
END DESCRIPTION:
DSS Export Rating Curves= 0
DSS Export Rating Curve Sorted= 0
DSS Export Volume Flow Curves= 0
DXF OffsetX= 0
DXF OffsetY= 0
DXF ScaleX= 1
DXF ScaleY= 10

--- BELL CREEK.p01 (plan) ---

Plan Title=Multiple Run
Short Identifier=Multiple
Geom File=g01
Flow File=f01
Subcritical Flow
K Sum by GR= 0
Std Step Tol= 0.01
Critical Tol= 0.01
Num of Std Step Trials= 20
Max Error Tol= 0.3
Flow Tol Ratio= 0.001
Split Flow NTrial= 30
Split Flow Tol= 0.02
Split Flow Ratio= 0.02
Log Output Level= 0
Friction Slope Method= 1
Unsteady Friction Slope Method= 2
Unsteady Bridges Friction Slope Method= 1
Parabolic Critical Depth
Global Vel Dist=  1 , 1 , 1
Global Log Level= 0
CheckData=True
Encroach Param= -1, 0, 0, 0
BEGIN DESCRIPTION:
Multiple Run
END DESCRIPTION:

--- BELL CREEK.f01 (steady flow) ---

Flow Title=Multiple
Program Version=4.10
Number of Profiles= 7
Profile Names=10-year,25-year,50-year,1pct_min,100-year,1pct_plu,500-year
River Rch & RM=BELL CREEK,Reach-1         ,30500
     266     341     444     191     577    1743    1008
River Rch & RM=BELL CREEK,Reach-1         ,30000
     761    1036    1406     627    1895    5723    3560
River Rch & RM=BELL CREEK,Reach-1         ,22000
     892    1219    1656     739    2232    6741    4192
River Rch & RM=BELL CREEK,Reach-1         ,20249
    2023    2895    4058    1865    5633   17011   11228
River Rch & RM=BELL CREEK,Reach-1         ,20151
    2023    2895    4058    1865    5633   17011   11228
River Rch & RM=BELL CREEK,Reach-1         ,19500
    2023    2895    4058    1865    5633   17011   11228
River Rch & RM=BELL CREEK,Reach-1         ,19071
    2023    2895    4058    1865    5633   17011   11228
River Rch & RM=BELL CREEK,Reach-1         ,18500
    2023    2895    4058    1865    5633   17011   11228
River Rch & RM=BELL CREEK,Reach-1         ,18000
    2023    2895    4058    1865    5633   17011   11228
River Rch & RM=BELL CREEK,Reach-1         ,17500
    2023    2895    4058    1865    5633   17011   11228
River Rch & RM=BELL CREEK,Reach-1         ,15500
    2464    3530    4953    2275    6871   20750   13679
River Rch & RM=BELL CREEK,Reach-1         ,9500
    2443    3471    4843    2211    6676   20161   13125
River Rch & RM=BELL CREEK,Reach-1         ,7000
    2750    3933    5512    2527    7630   23042   15131
River Rch & RM=BELL CREEK,Reach-1         ,4500
    2334    3275    4529    2047    6183   18672   11926
Boundary for River Rch & Prof#=BELL CREEK,Reach-1         , 1
Up Type= 0
Dn Type= 3
Dn Slope=0.005
Boundary for River Rch & Prof#=BELL CREEK,Reach-1         , 2
Up Type= 0
Dn Type= 3
Dn Slope=0.005
Boundary for River Rch & Prof#=BELL CREEK,Reach-1         , 3
Up Type= 0
Dn Type= 3
Dn Slope=0.005
Boundary for River Rch & Prof#=BELL CREEK,Reach-1         , 4
Up Type= 0
Dn Type= 3
Dn Slope=0.005
Boundary for River Rch & Prof#=BELL CREEK,Reach-1         , 5
Up Type= 0
Dn Type= 3
Dn Slope=0.005
Boundary for River Rch & Prof#=BELL CREEK,Reach-1         , 6
Up Type= 0
Dn Type= 3
Dn Slope=0.005
Boundary for River Rch & Prof#=BELL CREEK,Reach-1         , 7
Up Type= 0
Dn Type= 3
Dn Slope=0.005
DSS Import GetInterval= 0
DSS Import GetPeak= 0
DSS Import FillOption= 0

--- BELL CREEK.f02 (steady flow) ---

Flow Title=Orig_BLE_Flow
Program Version=4.10
Number of Profiles= 7
Profile Names=10-year,25-year,50-year,1pct_min,100-year,1pct_plu,500-year
River Rch & RM=BELL CREEK,Reach-1         ,30500
     266     334     386     147     444    1342     586
River Rch & RM=BELL CREEK,Reach-1         ,30000
     761    1016    1223     483    1458    4404    2070
River Rch & RM=BELL CREEK,Reach-1         ,22000
     892    1195    1440     568    1717    5184    2437
River Rch & RM=BELL CREEK,Reach-1         ,20249
    2023    2838    3529    1435    4333   13086    6528
River Rch & RM=BELL CREEK,Reach-1         ,20151
    2023    2838    3529    1435    4333   13086    6528
River Rch & RM=BELL CREEK,Reach-1         ,19500
    2023    2838    3529    1435    4333   13086    6528
River Rch & RM=BELL CREEK,Reach-1         ,19071
    2023    2838    3529    1435    4333   13086    6528
River Rch & RM=BELL CREEK,Reach-1         ,18500
    2023    2838    3529    1435    4333   13086    6528
River Rch & RM=BELL CREEK,Reach-1         ,18000
    2023    2838    3529    1435    4333   13086    6528
River Rch & RM=BELL CREEK,Reach-1         ,17500
    2023    2838    3529    1435    4333   13086    6528
River Rch & RM=BELL CREEK,Reach-1         ,15500
    2464    3461    4307    1750    5285   15960    7953
River Rch & RM=BELL CREEK,Reach-1         ,9500
    2443    3403    4211    1700    5135   15507    7631
River Rch & RM=BELL CREEK,Reach-1         ,7000
    2750    3856    4793    1943    5869   17725    8797
River Rch & RM=BELL CREEK,Reach-1         ,4500
    2334    3211    3938    1575    4756   14363    6934
Boundary for River Rch & Prof#=BELL CREEK,Reach-1         , 1
Up Type= 0
Dn Type= 3
Dn Slope=0.005
Boundary for River Rch & Prof#=BELL CREEK,Reach-1         , 2
Up Type= 0
Dn Type= 3
Dn Slope=0.005
Boundary for River Rch & Prof#=BELL CREEK,Reach-1         , 3
Up Type= 0
Dn Type= 3
Dn Slope=0.005
Boundary for River Rch & Prof#=BELL CREEK,Reach-1         , 4
Up Type= 0
Dn Type= 3
Dn Slope=0.005
Boundary for River Rch & Prof#=BELL CREEK,Reach-1         , 5
Up Type= 0
Dn Type= 3
Dn Slope=0.005
Boundary for River Rch & Prof#=BELL CREEK,Reach-1         , 6
Up Type= 0
Dn Type= 3
Dn Slope=0.005
Boundary for River Rch & Prof#=BELL CREEK,Reach-1         , 7
Up Type= 0
Dn Type= 3
Dn Slope=0.005
DSS Import GetInterval= 0
DSS Import GetPeak= 0
DSS Import FillOption= 0

--- BELL CREEK.g01 (geometry) ---

Geom Title=Existing Conditions
Program Version=4.10

River Reach=BELL CREEK      ,Reach-1
Reach XY= 30
      3811195.05     10150274.62      3810866.57     10149970.71
       3810800.6     10149630.08      3810254.42     10149153.35
      3809818.31     10148891.93      3809036.27     10148814.85
      3809021.43     10148358.08      3808761.79      10148383.6
      3808238.23     10147996.84      3808028.23     10147326.84
      3807188.23     10146676.84      3806698.23     10145856.84
       3806241.8     10145648.65      3806159.86     10145389.59
      3806306.76     10145040.41      3805591.44     10143994.03
      3805179.59     10142855.02      3805186.36     10142159.13
       3805859.4     10141392.05      3805850.15     10139242.02
      3805159.25     10137898.31      3804679.49     10136163.13
      3804656.85     10135469.88      3804187.29     10134529.45
      3803994.17      10133567.4      3803216.24     10132274.62
       3802956.1     10130971.97      3800761.07     10128903.18
       3800149.2      10127537.4      3799909.58     10126201.31

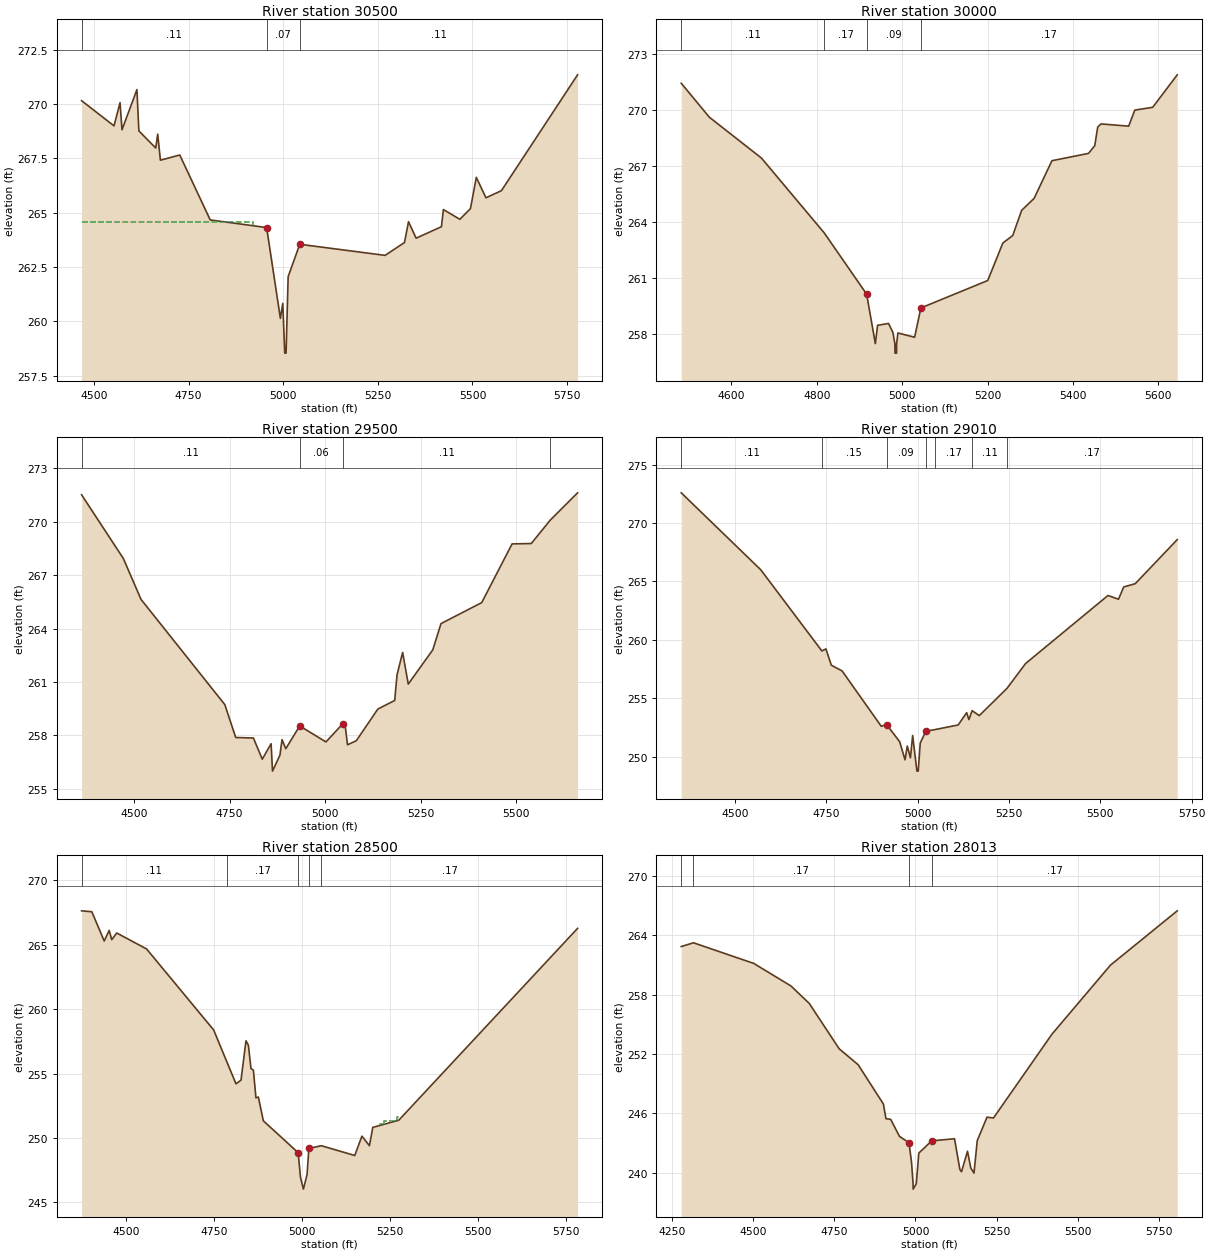
Type RM Length L Ch R = 1 ,30500   ,500,500,500
BEGIN DESCRIPTION:
BELL CREEK 61.0
END DESCRIPTION:
XS GIS Cut Line= 3
      3811681.55     10150134.86      3811160.62     10150245.24
      3810401.58     10150414.12
#Sta/Elev= 30
  4467.5  270.16  4553.1     269  4569.1  270.07  4574.2  268.82  4613.7  270.67
  4618.8  268.77  4663.4  267.98  4668.5  268.62  4675.7  267.42  4726.8  267.66
  4807.3  264.67  4956.3  264.32  4992.6  260.14  4998.9  260.83  5004.1  258.54
  5007.6  258.54  5013.1  262.06  5043.8  263.55  5269.2  263.04  5320.4  263.63
    5331  264.59  5351.1  263.83    5418  264.36  5423.1  265.15  5466.6   264.7
  5494.6  265.19  5510.1  266.63  5535.6  265.69  5576.5  266.02  5777.6  271.35
#Mann= 3 , 0 , 0
  4467.5     .11       0  4956.3     .07       0  5043.8     .11       0
#XS Ineff= 2 , 0
       0  4921.1  264.56    5331       0  264.59
Permanent Ineff=
       F       F
Bank Sta=4956.3,5043.8
XS Rating Curve= 0 ,0
Exp/Cntr=0.3,0.1

Type RM Length L Ch R = 1 ,30000   ,500,500,500
BEGIN DESCRIPTION:
BELL CREEK 60.0
END DESCRIPTION:
XS GIS Cut Line= 3
      3811340.91     10149762.11      3810836.72     10149879.15
      3810317.83     10150261.09
#Sta/Elev= 30
  4482.4  271.41  4548.2  269.59  4670.3   267.4  4817.4  263.39  4916.7  260.11
  4937.1  257.46  4942.3  258.44    4968  258.54  4978.3  258.05  4982.9  257.45
  4983.2  256.95  4986.7  256.95  4986.9  257.45    4990  258.03  5029.1   257.8
  5043.7  259.37  5200.4  260.84  5235.8  262.85  5258.9  263.25  5279.8   264.6
    5309  265.24  5350.8  267.26  5436.4  267.65    5451  268.06    5458  269.06
  5465.7  269.23  5530.5  269.11  5544.9  269.97  5586.8  270.12  5644.3  271.86
#Mann= 4 ,-1 , 0
  4482.4     .11       0  4817.4     .17       0  4916.7     .09       0
  5043.7     .17       0
Bank Sta=4916.7,5043.7
XS Rating Curve= 0 ,0
Exp/Cntr=0.3,0.1

Type RM Length L Ch R = 1 ,29500   ,490,490,490
BEGIN DESCRIPTION:
BELL CREEK 59.0
END DESCRIPTION:
XS GIS Cut Line= 3
      3811154.49     10149302.04      3810574.15     10149564.19
       3810182.7     10150095.94
#Sta/Elev= 30
  4363.2  271.52  4472.4  267.94  4518.7  265.64  4737.7  259.73  4766.3  257.88
  4812.6  257.85  4835.7  256.66  4858.8  257.53  4862.5  255.99  4881.9  256.89
  4887.4  257.76  4897.2  257.25  4933.6  258.53  5002.3  257.63  5045.8  258.64
  5052.4  258.57  5058.6  257.47  5081.7   257.7    5138  259.48    5182  259.96
  5188.2  261.41  5202.8  262.66  5217.5  260.88  5281.7  262.81  5303.1  264.28
  5409.6  265.46    5489  268.76  5539.1  268.78    5589   270.1  5660.3  271.63
#Mann= 4 ,-1 , 0
  4363.2     .11       0  4933.6     .06       0  5045.8     .11       0
    5589     .17       0
Bank Sta=4933.6,5045.8
XS Rating Curve= 0 ,0
Exp/Cntr=0.3,0.1

Type RM Length L Ch R = 1 ,29010   ,510,510,510
BEGIN DESCRIPTION:
BELL CREEK 58.0
END DESCRIPTION:
XS GIS Cut Line= 3
       3810790.5     10148830.31       3810263.1     10149204.73
       3809908.2     10149820.36
#Sta/Elev= 30
  4353.2  272.58  4570.8     266    4738  259.06  4749.1  259.23  4763.9  257.84
  4793.4  257.35  4900.4  252.62  4915.2  252.76  4950.9   251.3  4965.6  249.75
  4971.8  250.92  4980.4  249.92  4986.5  251.83  4998.2  248.78  5001.7  248.78
  5007.3  251.18  5022.6   252.2  5048.9  252.34  5111.2  252.73  5134.3  253.78
  5140.4  253.19  5149.3  253.95  5168.9  253.53  5244.7  255.86  5295.5  257.98
    5521   263.8  5549.8  263.48  5564.1  264.53  5595.7  264.81  5710.6  268.58
#Mann= 7 ,-1 , 0
  4353.2     .11       0    4738     .15       0  4915.2     .09       0
  5022.6     .15       0  5048.9     .17       0  5149.3     .11       0
  5244.7     .17       0
Bank Sta=4915.2,5022.6
XS Rating Curve= 0 ,0
Exp/Cntr=0.3,0.1

Type RM Length L Ch R = 1 ,28500   ,487,487,487
BEGIN DESCRIPTION:
BELL CREEK 57.0
END DESCRIPTION:
XS GIS Cut Line= 3
      3810362.43     10148524.57      3809907.14     10148955.08
      3809722.13     10149717.24
#Sta/Elev= 30
  4373.4  267.63  4402.5  267.56  4437.7  265.29  4451.9  266.11  4459.2  265.39
  4473.3  265.91  4558.3  264.67  4749.2  258.38  4785.8  255.96  4812.7   254.2
  4826.9  254.49    4841  257.54  4847.9   257.2  4855.2  255.39  4862.1  255.26
  4869.4  253.11  4876.2  253.18  4890.4  251.33  4989.5  248.86  4996.1  246.94
  5004.4  246.03  5014.8  247.17  5019.9  249.19  5055.6   249.4  5150.4  248.64
  5170.8  250.14  5192.2   249.4  5201.7  250.82  5275.7  251.38  5784.3  266.27
#Mann= 5 ,-1 , 0
  4373.4     .11       0  4785.8     .17       0  4989.5     .09       0
  5019.9     .15       0  5055.6     .17       0
#XS Ineff= 3 ,-1
  5222.3  5233.9   251.1  5233.9  5270.6  251.31  5270.6    5284  251.66
Permanent Ineff=
       F       F       F
Bank Sta=4989.5,5019.9
XS Rating Curve= 0 ,0
Exp/Cntr=0.3,0.1

Type RM Length L Ch R = 1 ,28013   ,513,513,513
BEGIN DESCRIPTION:
BELL CREEK 56.0
END DESCRIPTION:
XS GIS Cut Line= 3
      3809896.55     10148268.29      3809470.13     10148850.79
      3809427.76     10149656.67
#Sta/Elev= 30
  4278.1  262.86  4315.8  263.24  4501.4  261.16  4616.2  258.88  4672.8  257.11
  4764.9  252.53  4823.4  250.92  4901.2  246.95  4909.1  245.47  4923.7   245.4
  4950.8  243.68  4980.1  243.04    4988  241.05  4992.8  238.85    4993  238.35
  5002.6  238.89  5010.3  241.99  5050.4  243.23  5120.5  243.44    5137  240.33
    5142  240.11  5160.5  242.18  5170.5   240.5  5180.5  239.97  5190.5  243.25
  5220.6  245.62  5240.6  245.54  5420.9  254.01  5601.1  260.98    5807  266.47
#Mann= 4 ,-1 , 0
  4278.1     .11       0  4315.8     .17       0  4980.1     .09       0
  5050.4     .17       0
#XS Ineff= 2 , 0
       0                  5220.6       0  245.62
Permanent Ineff=
       F       F
Bank Sta=4980.1,5050.4
XS Rating Curve= 0 ,0
Exp/Cntr=0.3,0.1

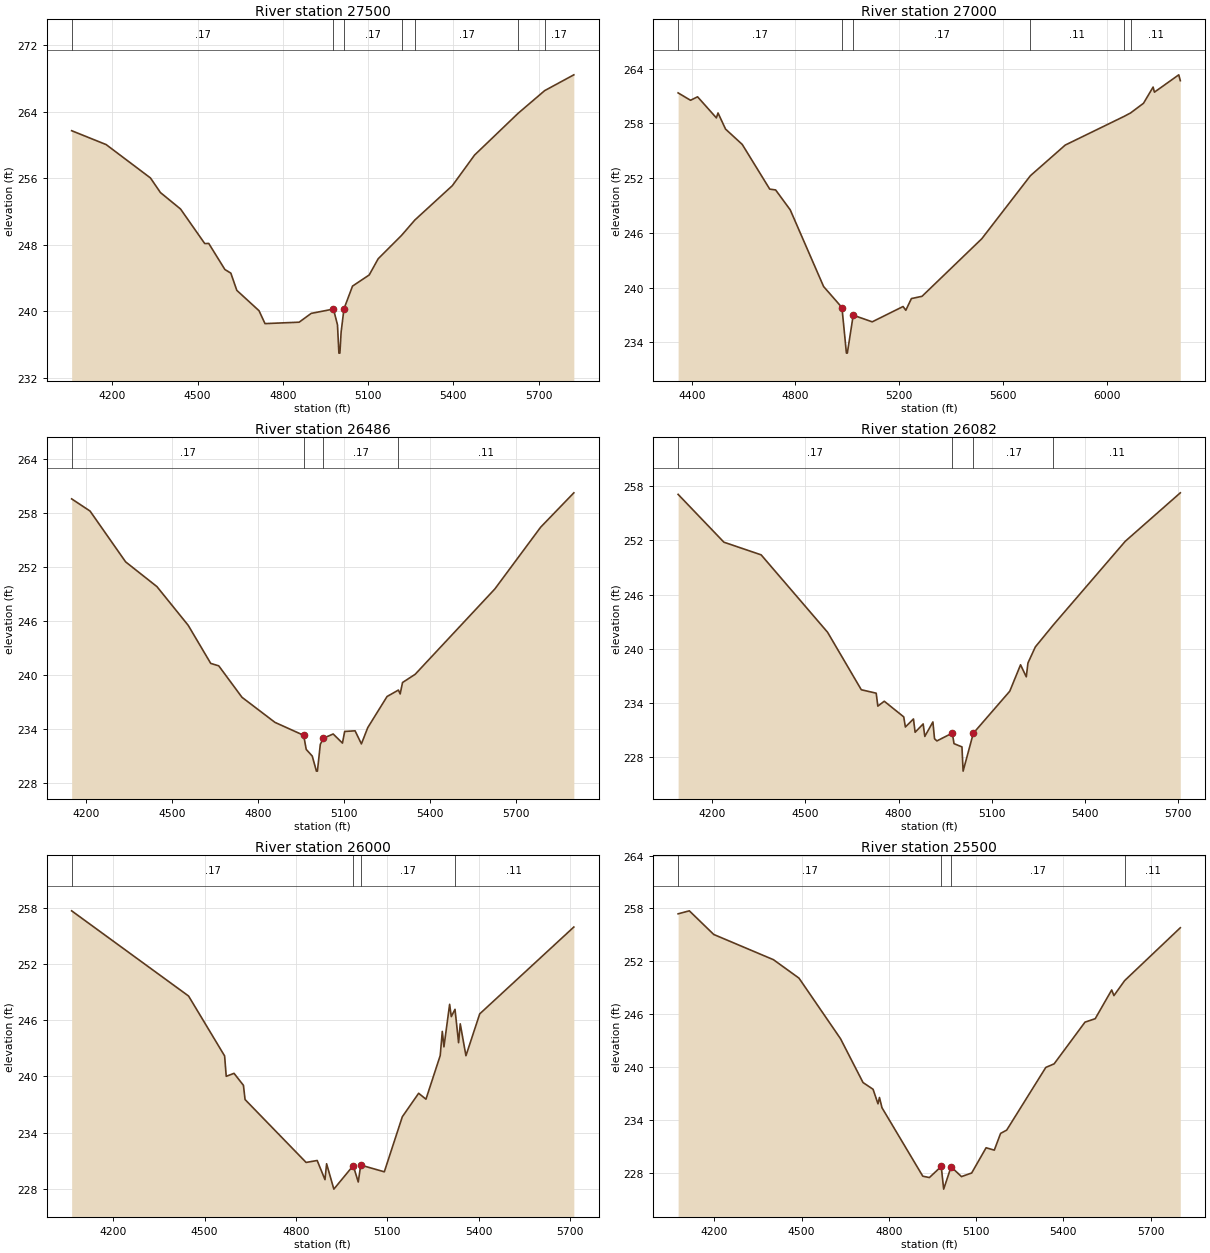
Type RM Length L Ch R = 1 ,27500   ,500,500,500
BEGIN DESCRIPTION:
BELL CREEK 55.0
END DESCRIPTION:
XS GIS Cut Line= 3
      3809675.25     10148116.85      3809031.54     10148805.97
      3808964.81     10149627.17
#Sta/Elev= 30
    4057  261.74  4178.4  260.07  4334.2  256.06  4369.4   254.3  4440.2  252.32
  4525.2  248.17  4539.4  248.18  4596.1  245.05  4617.1  244.61  4638.1  242.54
  4716.3  240.09  4737.3  238.54  4857.4  238.71  4899.9  239.77  4978.1  240.29
  4992.3   238.4  4997.3  234.99  5000.8  234.99  5005.1  237.52  5015.1  240.31
  5045.2  243.05  5103.9  244.39  5135.5  246.34  5217.7  249.15  5264.3  250.99
  5396.4  255.13  5474.6  258.81  5628.1  263.84  5721.3  266.56  5823.9  268.46
#Mann= 7 ,-1 , 0
    4057     .17       0  4978.1     .09       0  5015.1     .17       0
  5217.7     .11       0  5264.3     .17       0  5628.1     .11       0
  5721.3     .17       0
Bank Sta=4978.1,5015.1
XS Rating Curve= 0 ,0
Exp/Cntr=0.3,0.1

Type RM Length L Ch R = 1 ,27000   ,514,514,514
BEGIN DESCRIPTION:
BELL CREEK 54.0
END DESCRIPTION:
XS GIS Cut Line= 4
      3809547.15     10147974.15       3809029.7     10148371.48
      3808883.19     10148742.93      3808792.27     10149622.24
#Sta/Elev= 30
  4347.6  261.34  4395.4  260.53  4422.6  260.91  4495.1   258.6  4501.4  259.14
  4530.5  257.37  4594.8  255.69  4700.8  250.79  4723.5   250.7  4779.7  248.52
  4908.4  240.11  4979.1  237.81  4996.3  232.81  4999.8  232.81  5022.6  236.97
  5095.7  236.24  5214.7  237.92  5225.3  237.51  5246.8  238.79  5287.8  239.04
  5518.1  245.35  5705.5  252.26  5839.8  255.62  6067.8  258.78  6091.6  259.14
  6141.4   260.2  6178.5  261.98  6183.5  261.42  6277.4  263.32  6283.3  262.68
#Mann= 6 ,-1 , 0
  4347.6     .17       0  4979.1     .09       0  5022.6     .17       0
  5705.5     .11       0  6067.8     .17       0  6091.6     .11       0
Bank Sta=4979.1,5022.6
XS Rating Curve= 0 ,0
Exp/Cntr=0.3,0.1

Type RM Length L Ch R = 1 ,26486   ,404,404,404
BEGIN DESCRIPTION:
BELL CREEK 53.0
END DESCRIPTION:
XS GIS Cut Line= 3
      3809340.85     10147834.06      3808623.23     10148291.84
      3807806.12     10148674.34
#Sta/Elev= 30
  4148.8  259.53    4213  258.18  4337.3  252.54  4446.5   249.8  4555.6  245.51
  4634.4  241.28  4662.4  241.01  4743.5  237.52  4858.6  234.74  4958.9   233.3
  4967.8  231.74  4988.9     231  5003.4  229.33  5006.9  229.33    5017   232.3
    5028  232.98  5061.9  233.45  5094.3  232.44  5102.1  233.73  5138.4   233.8
  5160.5  232.35  5182.6  234.15  5250.1  237.61  5289.7  238.32  5295.8  237.89
  5304.1  239.16  5348.2  240.07  5626.5  249.54  5786.4  256.39  5902.2   260.2
#Mann= 4 ,-1 , 0
  4148.8     .17       0  4958.9     .09       0    5028     .17       0
  5289.7     .11       0
Bank Sta=4958.9,5028
XS Rating Curve= 0 ,0
Exp/Cntr=0.3,0.1

Type RM Length L Ch R = 1 ,26082   ,82,82,82
BEGIN DESCRIPTION:
Mapping XS eb4e5b1c
END DESCRIPTION:
XS GIS Cut Line= 3
      3809205.37     10147799.43      3808343.71     10148094.65
      3807693.32     10148365.85
#Sta/Elev= 30
    4091   257.1  4238.3  251.81  4358.1  250.41  4571.8  241.85  4680.3  235.49
  4728.2  235.11  4733.5  233.68  4754.2  234.22  4816.8  232.49  4822.1  231.37
  4848.1  232.26  4853.4  230.79  4879.3  231.71  4884.6  230.33  4910.6  231.93
  4915.9  230.07  4923.5  229.83  4973.2   230.7  4978.5  229.53  5004.1  229.17
  5007.8  226.49  5040.7  230.68  5157.9  235.33  5192.6  238.25    5211  236.92
  5216.4  238.45  5240.2  240.23  5298.3  242.67  5529.4  251.91  5706.5  257.27
#Mann= 4 ,-1 , 0
    4091     .17       0  4973.2     .09       0  5040.7     .17       0
  5298.3     .11       0
#XS Ineff= 2 , 0
       0  4754.2  234.22               0
Permanent Ineff=
       F       F
Bank Sta=4973.2,5040.7
XS Rating Curve= 0 ,0
Exp/Cntr=0.3,0.1

Type RM Length L Ch R = 1 ,26000   ,500,500,500
BEGIN DESCRIPTION:
BELL CREEK 52.0
END DESCRIPTION:
XS GIS Cut Line= 3
      3809183.76     10147717.83      3808301.34     10148029.95
      3807641.68     10148298.17
#Sta/Elev= 30
    4064  257.69  4447.7  248.59    4566  242.19  4571.3  240.01  4596.9  240.33
  4627.8  239.05  4633.1  237.53  4833.5  230.81  4869.8  231.02  4895.4  228.97
  4900.7  230.67  4924.5  227.96  4988.1  230.47  5004.6  228.72  5012.7  230.53
  5090.1  229.81  5149.2  235.69  5202.8   238.2  5226.8  237.57  5273.6  242.23
  5280.4  244.81  5285.8  243.16  5304.5   247.7  5309.9  246.39  5322.1  247.17
  5333.9   243.6  5339.3  245.62    5358  242.21  5403.2  246.68  5712.1  255.96
#Mann= 4 ,-1 , 0
    4064     .17       0  4988.1     .09       0  5012.7     .17       0
  5322.1     .11       0
Bank Sta=4988.1,5012.7
XS Rating Curve= 0 ,0
Exp/Cntr=0.3,0.1

Type RM Length L Ch R = 1 ,25500   ,592,592,592
BEGIN DESCRIPTION:
BELL CREEK 51.0
END DESCRIPTION:
XS GIS Cut Line= 3
       3809045.7     10147472.94      3808138.23     10147651.66
      3807538.78     10148184.75
#Sta/Elev= 30
  4075.1  257.39  4113.7  257.73  4197.6  255.05    4403  252.19  4490.8   250.1
  4633.5  243.24  4711.1  238.26  4745.6   237.5  4762.5  235.85  4767.6  236.57
  4776.2  235.41  4916.5  227.65  4939.2  227.49    4980  228.75  4988.4  226.18
  5013.9  228.71  5049.6   227.6  5084.7  228.01  5134.3  230.87  5162.5   230.6
  5184.2   232.5  5205.1  232.87  5339.7  239.98  5368.2  240.38  5474.4  245.11
  5509.5   245.5  5566.3  248.76  5573.9  248.12  5610.8  249.82  5802.2  255.81
#Mann= 4 ,-1 , 0
  4075.1     .17       0    4980     .09       0  5013.9     .17       0
  5610.8     .11       0
Bank Sta=4980,5013.9
XS Rating Curve= 0 ,0
Exp/Cntr=0.3,0.1

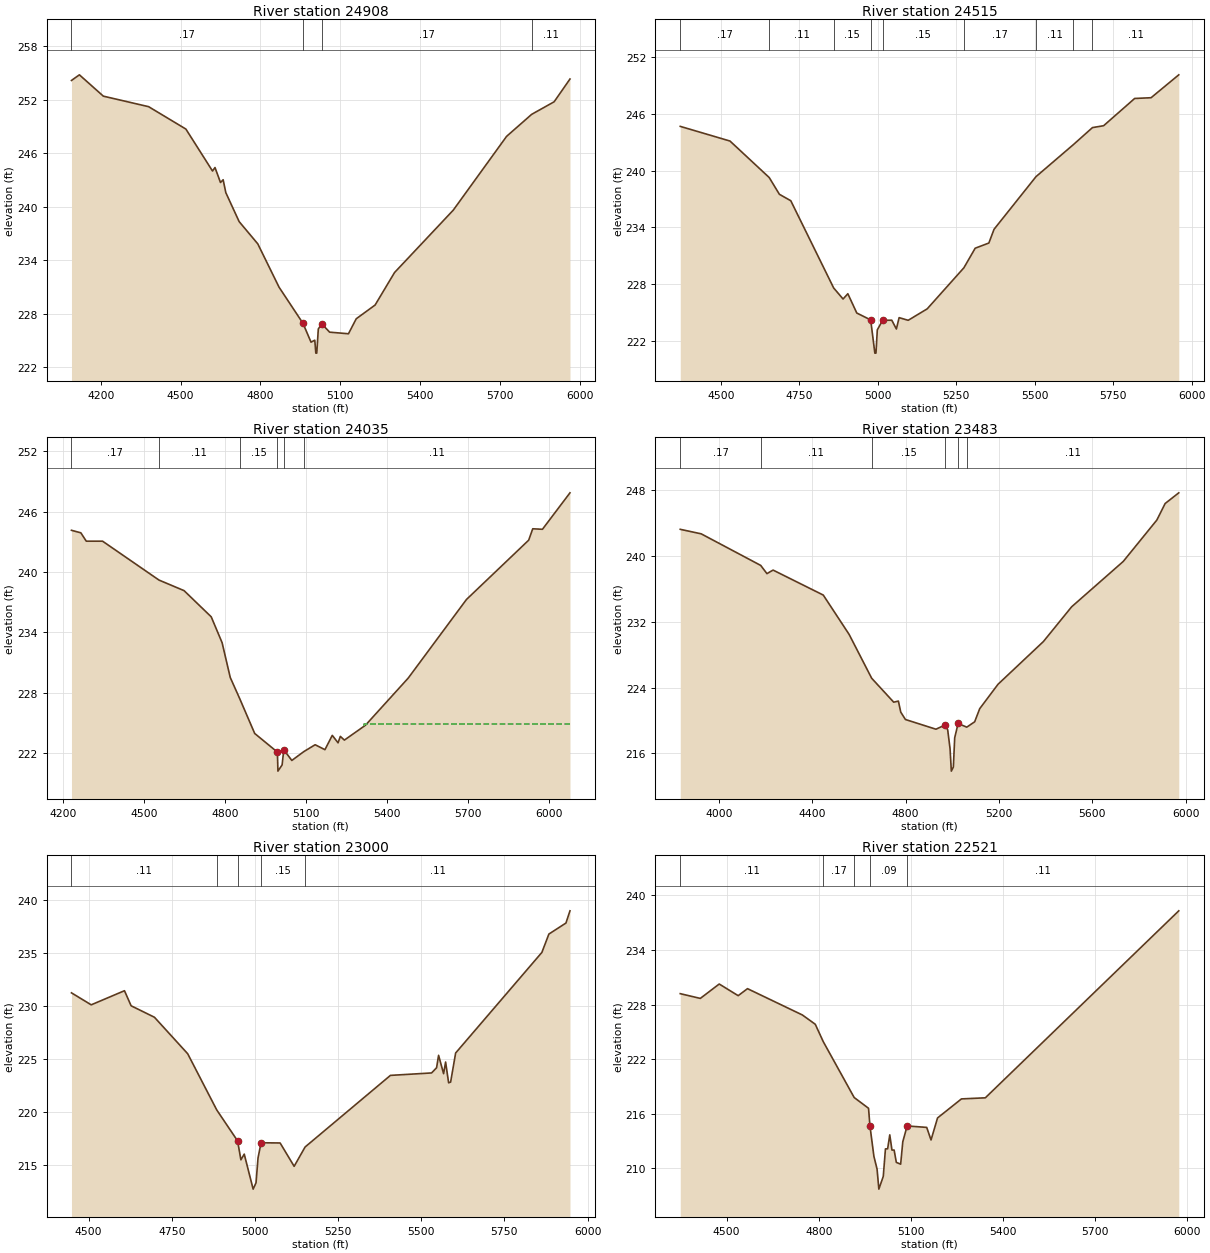
Type RM Length L Ch R = 1 ,24908   ,393,393,393
BEGIN DESCRIPTION:
BELL CREEK 50.0
END DESCRIPTION:
XS GIS Cut Line= 3
      3808927.64     10147290.06      3808018.23     10147316.84
      3807441.55     10148088.71
#Sta/Elev= 30
  4090.2  254.16    4120  254.79    4210   252.4  4380.1  251.22  4520.2  248.71
  4620.2  244.01  4629.6   244.4  4650.2  242.72  4660.2  243.03  4670.2  241.59
  4720.3  238.34  4790.3  235.85  4870.3  230.99  4960.4  226.93  4990.4  224.83
  5004.5  225.05  5008.5   223.6    5012   223.6  5017.8  226.31  5031.1  226.87
  5060.3  225.95  5131.1  225.77  5160.3  227.45  5231.2  228.99  5304.2  232.63
  5525.1  239.63  5725.2  247.89  5819.5  250.36    5904  251.77  5963.5  254.32
#Mann= 4 ,-1 , 0
  4090.2     .17       0  4960.4     .09       0  5031.1     .17       0
  5819.5     .11       0
Bank Sta=4960.4,5031.1
XS Rating Curve= 0 ,0
Exp/Cntr=0.3,0.1

Type RM Length L Ch R = 1 ,24515   ,480,480,480
BEGIN DESCRIPTION:
BELL CREEK 49.0
END DESCRIPTION:
XS GIS Cut Line= 3
      3808261.68     10146777.62       3807731.4     10147116.84
      3807346.75     10147995.43
#Sta/Elev= 30
  4370.5  244.68    4529  243.13    4654  239.27  4686.4   237.5  4722.7  236.82
  4859.3   227.6  4889.3  226.43  4904.5  226.99    4933  224.95  4977.3  224.22
  4990.6  220.71  4994.1  220.71  4998.4  223.17  5015.5  224.18  5044.5  224.19
  5059.2  223.26  5067.9  224.46  5096.8  224.18  5157.4  225.39  5274.3  229.73
  5310.3   231.8  5353.9  232.35  5370.4   233.8  5504.2  239.37  5623.5  242.76
    5684  244.55  5719.6  244.75  5818.5  247.63  5870.8  247.71  5959.1  250.13
#Mann= 9 ,-1 , 0
  4370.5     .17       0    4654     .11       0  4859.3     .15       0
  4977.3     .09       0  5015.5     .15       0  5274.3     .17       0
  5504.2     .11       0  5623.5     .17       0    5684     .11       0
Bank Sta=4977.3,5015.5
XS Rating Curve= 0 ,0
Exp/Cntr=0.3,0.1

Type RM Length L Ch R = 1 ,24035   ,552,552,552
BEGIN DESCRIPTION:
BELL CREEK 48.0
END DESCRIPTION:
XS GIS Cut Line= 3
      3808252.32     10146737.47      3807488.23     10146816.84
      3806598.79     10147423.62
#Sta/Elev= 30
  4231.8  244.14  4266.5  243.89  4286.6  243.06  4346.9  243.06  4555.6   239.2
  4648.5  238.15    4749  235.55  4789.3  232.98  4819.4  229.53  4854.4  227.43
  4909.9  223.97  4993.9  222.12  4995.9  220.23  5011.4  220.85  5017.5  222.35
  5047.3  221.29  5091.8  222.17  5133.6  222.85  5169.9  222.36    5197  223.78
  5218.4  223.04  5226.9  223.68  5241.8  223.31  5319.6  224.78  5478.2  229.47
  5693.6  237.27  5923.9  243.16  5938.9  244.29  5974.8  244.24  6076.7  247.86
#Mann= 6 ,-1 , 0
  4231.8     .17       0  4555.6     .11       0  4854.4     .15       0
  4993.9     .09       0  5017.5     .15       0  5091.8     .11       0
#XS Ineff= 2 , 0
       0                  5313.6       0  224.86
Permanent Ineff=
       F       F
Bank Sta=4993.9,5017.5
XS Rating Curve= 0 ,0
Exp/Cntr=0.3,0.1

Type RM Length L Ch R = 1 ,23483   ,483,483,483
BEGIN DESCRIPTION:
BELL CREEK 47.0
END DESCRIPTION:
XS GIS Cut Line= 3
      3808277.09     10146697.28      3807118.23     10146576.84
      3806540.01     10147355.67
#Sta/Elev= 30
  3834.9  243.27  3924.6  242.72  4179.4  238.88  4206.1  237.88  4232.4  238.31
  4447.4  235.27    4558  230.49  4654.7  225.15    4749  222.24  4769.1  222.37
  4779.2  221.03  4799.3  220.13    4930  218.95  4970.2  219.48  4980.3  218.86
  4990.3   216.6  4995.9  213.85  5004.5  214.35  5010.3  217.91  5024.9  219.65
  5061.9   219.2  5095.8  219.85  5117.4  221.45  5195.9  224.42    5390  229.61
    5511  233.84  5732.1  239.36  5876.1   244.4  5911.6  246.41    5970  247.71
#Mann= 6 ,-1 , 0
  3834.9     .17       0  4179.4     .11       0  4654.7     .15       0
  4970.2     .09       0  5024.9     .15       0  5061.9     .11       0
Bank Sta=4970.2,5024.9
XS Rating Curve= 0 ,0
Exp/Cntr=0.3,0.1

Type RM Length L Ch R = 1 ,23000   ,479,479,479
BEGIN DESCRIPTION:
BELL CREEK 46.0
END DESCRIPTION:
XS GIS Cut Line= 3
      3807467.29     10146199.66      3806915.62     10146194.23
      3806122.81     10146712.72
#Sta/Elev= 30
  4448.3  231.24  4507.7  230.11  4607.7  231.44  4627.7  230.02  4697.8  228.94
  4797.8   225.5  4885.2   220.2  4947.8  217.29  4957.8   215.5  4967.8  216.04
  4994.6  212.74  5003.3  213.34  5009.3  215.68  5018.4  217.11  5075.7  217.09
  5117.9  214.89  5150.8  216.71  5407.4  223.46  5531.1  223.69  5546.2  224.18
  5552.2  225.35  5567.3  223.62  5573.3  224.72  5582.4  222.76  5588.4  222.83
  5603.5  225.57  5862.8  235.05  5883.9  236.78  5935.2  237.82  5947.3  238.97
#Mann= 5 ,-1 , 0
  4448.3     .11       0  4885.2     .15       0  4947.8     .09       0
  5018.4     .15       0  5150.8     .11       0
Bank Sta=4947.8,5018.4
XS Rating Curve= 0 ,0
Exp/Cntr=0.3,0.1

Type RM Length L Ch R = 1 ,22521   ,521,521,521
BEGIN DESCRIPTION:
BELL CREEK 45.0
END DESCRIPTION:
XS GIS Cut Line= 3
      3807331.33     10146008.03      3806698.23     10145856.84
      3806005.33     10146539.65
#Sta/Elev= 30
  4349.1   229.2  4414.4  228.68    4476  230.26  4537.7  228.98  4568.1  229.75
  4746.8  226.86  4788.8  225.84    4815  223.92  4915.6  217.79  4962.3  216.61
 4966.88  214.68  4979.8  211.33  4990.1  209.93  4995.9  207.73  5010.3  209.13
  5017.4  212.15  5024.5  212.16  5031.5  213.69  5038.6  212.02  5045.7  212.02
  5052.8  210.67  5066.9  210.47  5073.9  212.94  5088.1  214.67  5151.8  214.51
  5165.9  213.13  5187.1  215.55  5264.9  217.64  5342.7  217.76  5972.8   238.3
#Mann= 5 ,-1 , 0
  4349.1     .11       0    4815     .17       0  4915.6     .15       0
 4966.88     .09       0  5088.1     .11       0
Bank Sta=4966.88,5088.1
XS Rating Curve= 0 ,0
Exp/Cntr=0.3,0.1

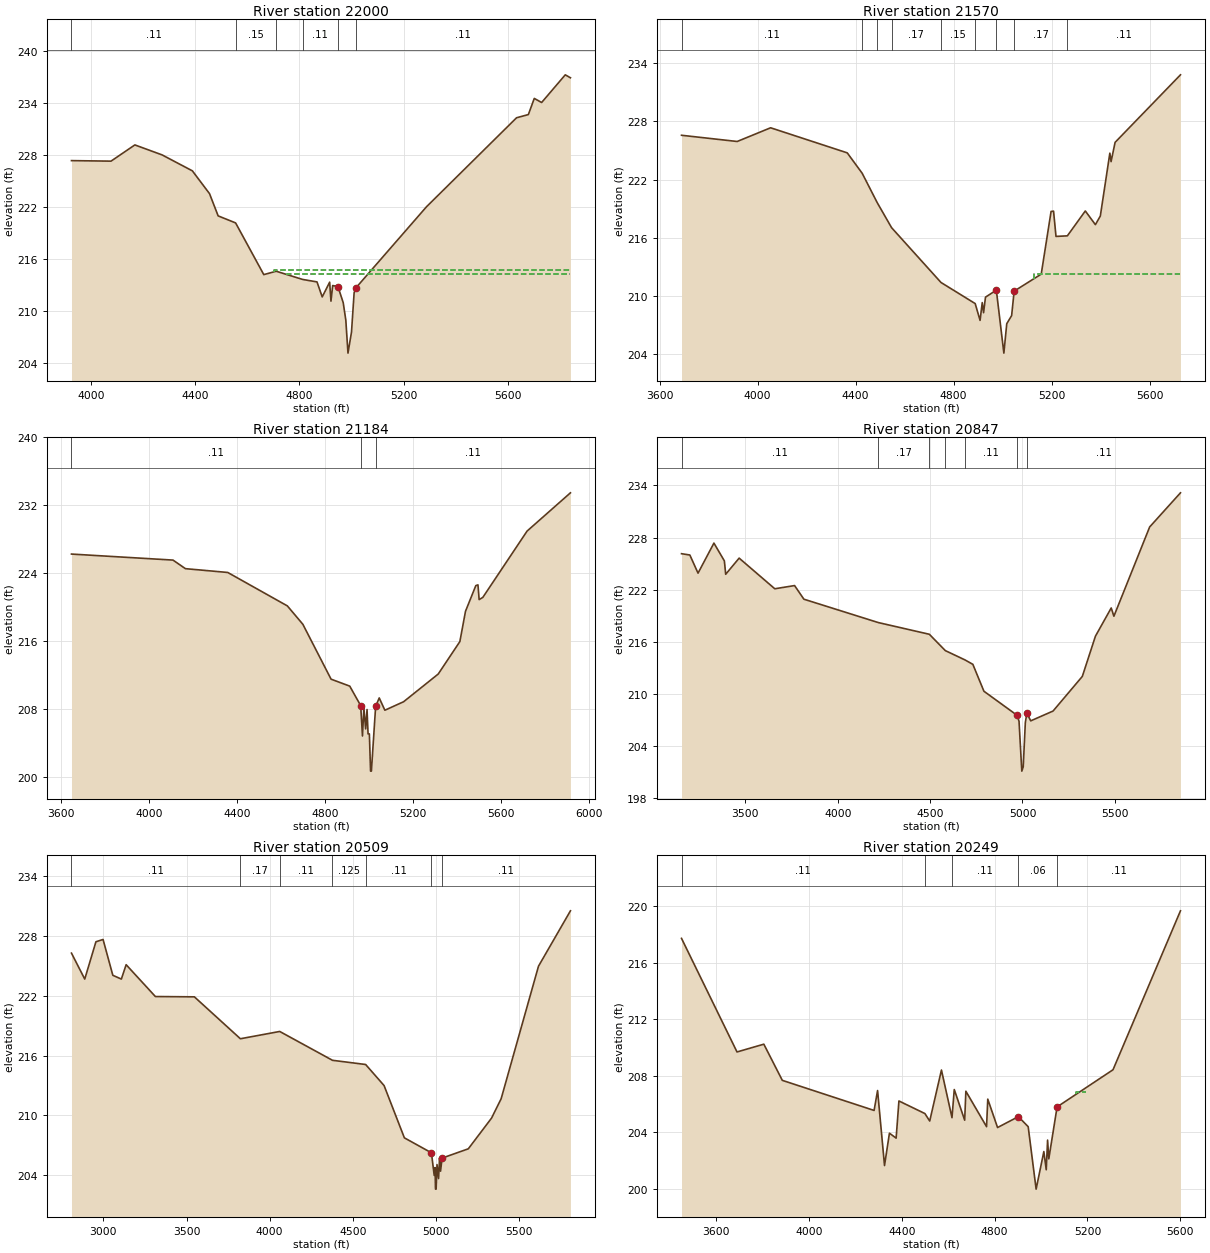
Type RM Length L Ch R = 1 ,22000   ,430,430,430
BEGIN DESCRIPTION:
BELL CREEK 44.0
END DESCRIPTION:
XS GIS Cut Line= 4
      3807340.53     10145949.29      3806472.72      10145686.6
      3806306.21     10145704.82      3805943.51     10146462.37
#Sta/Elev= 30
  3925.8  227.32  4077.5  227.26  4168.9  229.13  4273.4  227.98  4389.6  226.14
  4455.4  223.51  4488.4  220.95  4555.4  220.14  4663.5  214.18  4711.1  214.57
    4813  213.62  4867.6  213.34  4887.7  211.61  4916.2  213.31  4921.2  211.12
  4927.9  212.92    4948   212.8  4968.2  210.95  4978.2  208.94  4986.5  205.13
    5000  207.56  5010.1   212.1    5018  212.69  5287.7     222  5633.2  232.26
  5678.5  232.63  5701.2  234.49  5729.4  234.02  5820.1  237.21  5839.9  236.87
#Mann= 6 ,-1 , 0
  3925.8     .11       0  4555.4     .15       0  4711.1     .17       0
    4813     .11       0    4948     .06       0    5018     .11       0
#XS Ineff= 2 ,-1
  4701.8  4649.5  214.67    4754  4701.8  214.29
Permanent Ineff=
       F       F
Bank Sta=4948,5018
XS Rating Curve= 0 ,0
Exp/Cntr=0.3,0.1

Type RM Length L Ch R = 1 ,21570   ,386,386,386
BEGIN DESCRIPTION:
BELL CREEK 43.0
END DESCRIPTION:
XS GIS Cut Line= 3
      3807359.11     10145902.93      3806174.77     10145341.89
      3805452.42     10145414.55
#Sta/Elev= 30
  3689.5  226.56  3916.7  225.92  4053.2  227.33  4365.9  224.75  4426.9  222.65
  4488.2  219.63  4546.9  217.05  4748.6  211.41  4888.1  209.24  4908.1  207.51
  4916.9  209.34  4922.4   208.3  4930.2   209.9  4974.5  210.62  5005.2  204.14
    5017  207.17  5036.9     208  5047.2  210.52  5157.7  212.27  5197.9  218.72
    5208  218.75    5218  216.15  5264.4  216.21  5337.6  218.77  5378.8  217.36
  5398.9  218.25  5437.8  224.72  5442.8  223.85  5459.2  225.83    5726  232.78
#Mann= 9 ,-1 , 0
  3689.5     .11       0  4426.9     .17       0  4488.2     .11       0
  4546.9     .17       0  4748.6     .15       0  4888.1     .17       0
  4974.5     .09       0  5047.2     .17       0  5264.4     .11       0
#XS Ineff= 2 , 0
       0  4706.6   212.1  5127.6       0   212.3
Permanent Ineff=
       F       F
Bank Sta=4974.5,5047.2
XS Rating Curve= 0 ,0
Exp/Cntr=0.3,0.1

Type RM Length L Ch R = 1 ,21184   ,337,337,337
BEGIN DESCRIPTION:
Mapping XS aeda876c
END DESCRIPTION:
XS GIS Cut Line= 3
      3807371.22     10145875.44      3806306.76     10145040.41
      3805441.74     10145343.83
#Sta/Elev= 30
  3647.1  226.23  4108.9  225.52  4165.3  224.51  4357.9  224.06    4629  220.12
  4699.6  217.95  4827.9  211.48  4912.9  210.66  4962.6  208.36  4970.7  204.78
  4977.1  208.09  4985.2  205.62  4991.5   207.9  4996.1  205.03  5002.1  205.03
  5007.5  200.64  5011.3  200.64  5030.6  208.26  5046.9  209.27  5072.6  207.82
  5157.8  208.82  5315.4  212.09  5413.7  215.91  5439.4  219.49  5486.3  222.51
  5496.1   222.6  5501.4  220.86  5518.1  221.12  5719.5  228.94  5916.7  233.45
#Mann= 3 , 0 , 0
  3647.1     .11       0  4962.6     .09       0  5030.6     .11       0
#XS Ineff= 2 , 0
       0  4912.9  210.66               0
Permanent Ineff=
       F       F
Bank Sta=4962.6,5030.6
XS Rating Curve= 0 ,0
Exp/Cntr=0.3,0.1

Type RM Length L Ch R = 1 ,20847   ,338,338,338
BEGIN DESCRIPTION:
BELL CREEK 42.0
END DESCRIPTION:
XS GIS Cut Line= 4
       3807386.9     10145865.81      3806601.93     10144764.27
      3806109.18     10144769.85      3805424.29     10145281.65
#Sta/Elev= 30
  3154.6  226.14  3199.7  225.99    3244   223.9    3330  227.36  3386.6  225.31
  3393.7  223.77  3466.5  225.63  3659.5   222.1  3766.5  222.47  3816.9   220.9
  4219.4  218.21  4495.9  216.86  4582.3  214.98  4687.5  213.92  4731.3   213.4
  4791.3   210.3  4971.3  207.52  4981.3  206.83  4996.3   201.1    5004   201.6
  5015.4  206.69  5023.7  207.77  5044.6  206.89  5165.5  208.02  5323.9  212.01
  5394.8  216.64  5480.2  219.89  5494.8  218.94  5688.3  229.22    5855  233.15
#Mann= 7 ,-1 , 0
  3154.6     .11       0  4219.4     .17       0  4495.9     .11       0
  4582.3    .125       0  4687.5     .11       0  4971.3     .06       0
  5023.7     .11       0
Bank Sta=4971.3,5023.7
XS Rating Curve= 0 ,0
Exp/Cntr=0.3,0.1

Type RM Length L Ch R = 1 ,20509   ,260,260,260
BEGIN DESCRIPTION:
Mapping XS 3d0ebc16
END DESCRIPTION:
XS GIS Cut Line= 4
        3807399.     10145859.81      3806681.57      10144636.3
      3805921.13     10144494.41      3805237.75     10144927.02
#Sta/Elev= 30
  2808.1  226.27  2887.8  223.67  2955.1  227.41    2998  227.64  3056.7  224.05
    3108  223.67  3136.8  225.11  3312.7  221.92  3547.2  221.89  3823.9  217.69
  4060.5  218.42  4377.8  215.53  4577.1  215.11    4688     213  4810.1  207.76
  4972.8  206.26  4989.5     204  4994.6  204.78  4997.2  202.62    5001  202.62
  5006.4  205.08  5015.7  203.68  5021.7  205.74  5027.6  204.42    5037  205.73
  5194.6  206.66  5334.5  209.74  5392.1  211.68  5616.7  224.96  5808.8  230.51
#Mann= 7 ,-1 , 0
  2808.1     .11       0  3823.9     .17       0  4060.5     .11       0
  4377.8    .125       0  4577.1     .11       0  4972.8     .06       0
    5037     .11       0
Bank Sta=4972.8,5037
XS Rating Curve= 0 ,0
Exp/Cntr=0.3,0.1

Type RM Length L Ch R = 1 ,20249   ,98,98,98
BEGIN DESCRIPTION:
BELL CREEK 41.0
END DESCRIPTION:
XS GIS Cut Line= 4
      3807295.17     10143956.98      3806014.82     10144223.33
      3805779.87     10144278.93      3805197.01     10144426.29
#Sta/Elev= 30
  3450.8  217.74    3690   209.7  3805.6  210.25  3885.2  207.69  4280.8  205.56
  4295.8  206.97  4325.7  201.66  4346.9  203.95  4375.8   203.6  4387.8  206.23
  4499.7  205.34  4520.5  204.81  4571.1  208.42  4616.5  205.05  4626.3  207.04
  4671.2  204.87  4676.3  206.92  4765.5  204.41  4770.7  206.36  4812.9  204.35
  4902.6  205.12  4944.9  204.41  4979.1  199.99  5012.4  202.65  5022.7  201.36
  5028.5  203.46  5033.7  202.13  5069.5  205.81  5310.5  208.44  5601.2  219.69
#Mann= 5 ,-1 , 0
  3450.8     .11       0  4499.7    .125       0  4616.5     .11       0
  4902.6     .06       0  5069.5     .11       0
#XS Ineff= 4 ,-1
  4571.1  3840.2  208.42  4770.7  4571.1  206.36  5115.7  5151.6  206.08
  5151.6  5192.6  206.85
Permanent Ineff=
       F       F       F       F
Bank Sta=4902.6,5069.5
XS Rating Curve= 0 ,0
Exp/Cntr=0.3,0.1