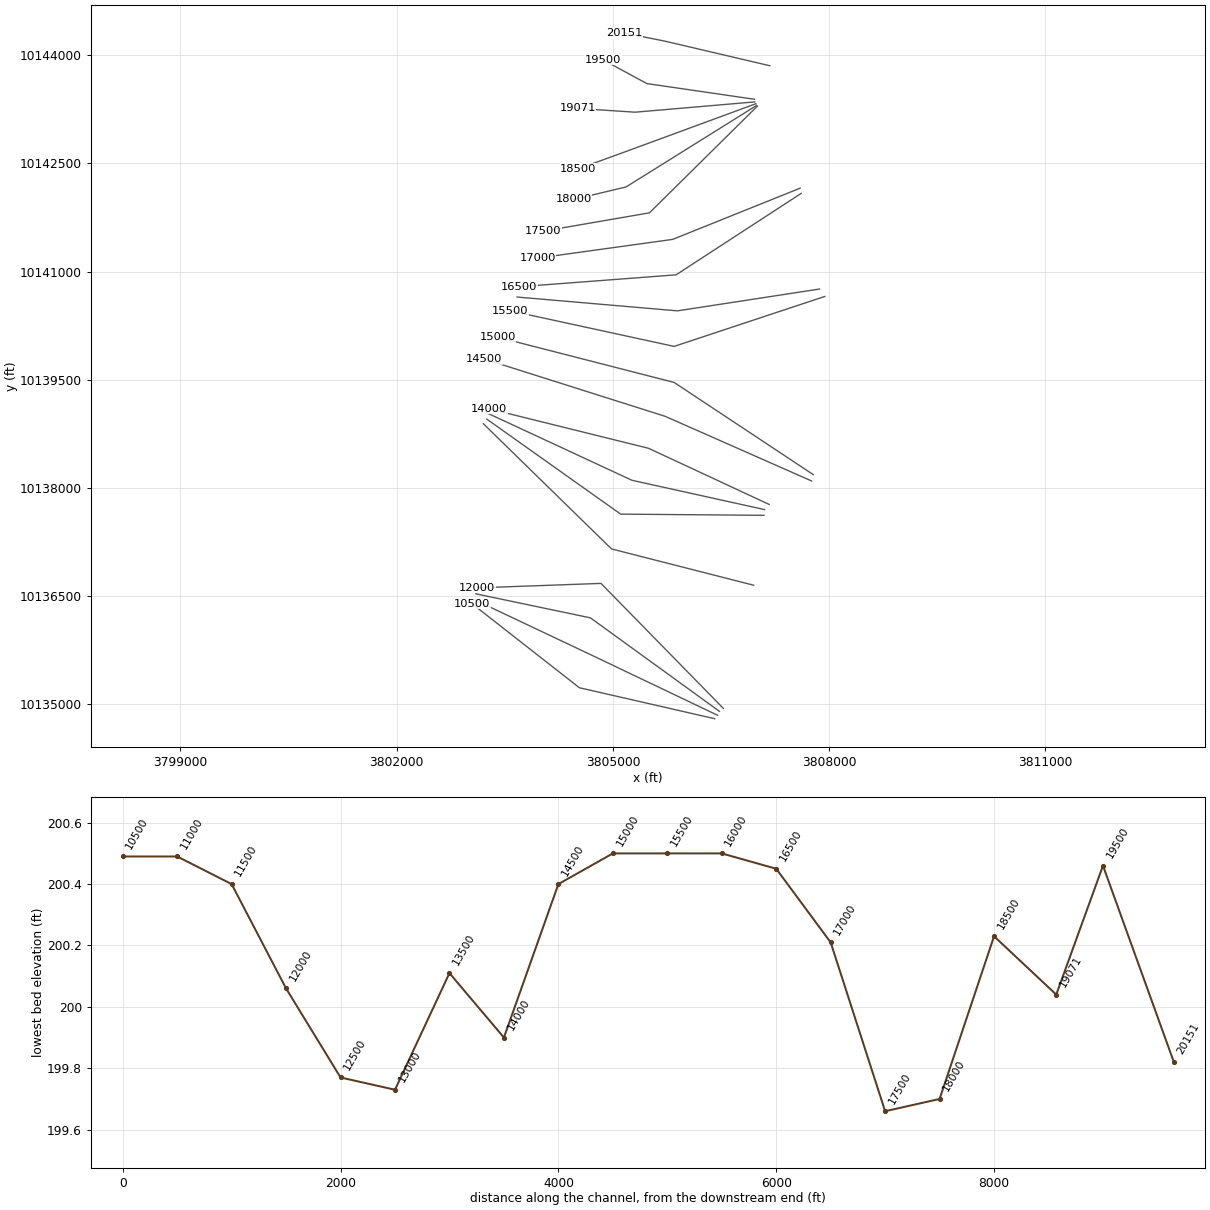
HEC-RAS study BELL CREEK.prj: BELL CREEK Base Level Engineering

--- BELL CREEK.g01 (geometry) --- (continued)

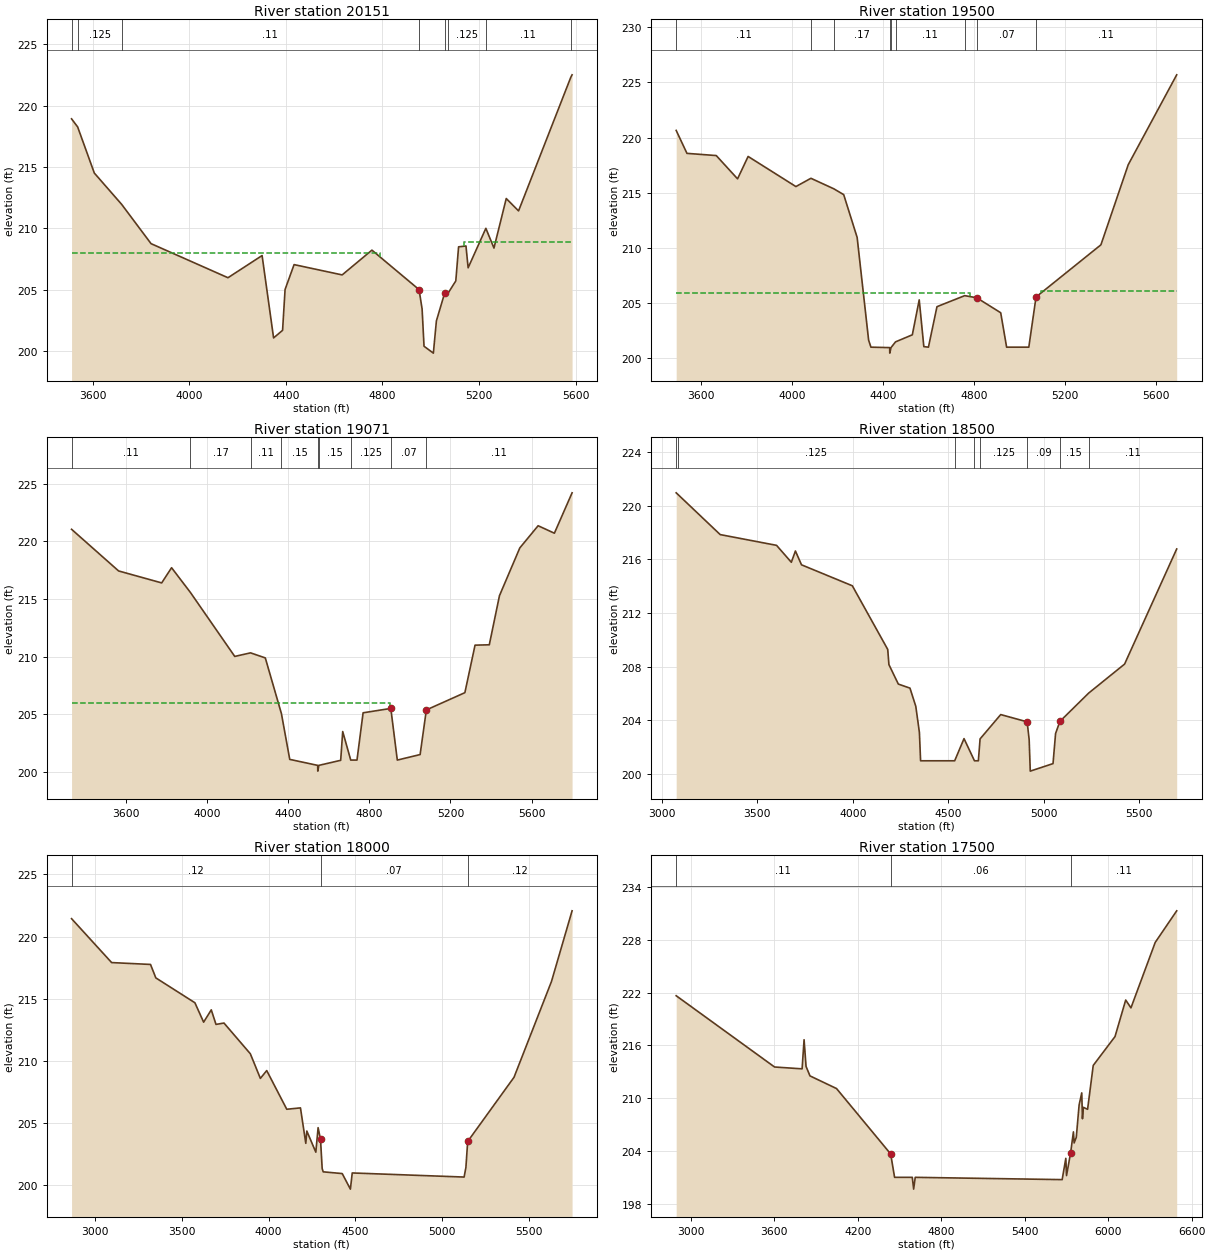
Type RM Length L Ch R = 1 ,20151   ,651,651,651
BEGIN DESCRIPTION:
BELL CREEK 40.0
END DESCRIPTION:
XS GIS Cut Line= 3
      3807178.03      10143855.4      3805730.63     10144194.95
      3805157.35     10144309.98
#Sta/Elev= 30
  3513.3  218.93  3538.5  218.27  3607.4  214.51  3720.8  211.95  3842.2  208.75
  4160.6  205.97  4301.8  207.78  4349.4  201.06  4386.6  201.68  4396.9  205.01
  4434.2  207.04  4633.1   206.2  4756.3  208.22  4951.5     205    4964  203.42
    4972  200.38  5010.6  199.82  5023.2  202.45  5057.7  204.74  5072.1  204.73
  5103.5  205.71    5115  208.49  5145.6  208.56  5154.5  206.78  5227.9     210
  5261.4  208.39  5312.3  212.43  5363.2  211.42  5579.2  222.31  5584.7  222.52
#Mann= 8 ,-1 , 0
  3513.3     .11       0  3538.5    .125       0  3720.8     .11       0
  4951.5     .07       0  5057.7     .11       0  5072.1    .125       0
  5227.9     .11       0  5579.2    .125       0
#XS Ineff= 2 , 0
       0  4789.1  207.97  5135.4       0   208.9
Permanent Ineff=
       T       F
Bank Sta=4951.5,5057.7
XS Rating Curve= 0 ,0
Exp/Cntr=0.3,0.1

Type RM Length L Ch R = 1 ,19500   ,429,429,429
BEGIN DESCRIPTION:
BELL CREEK 39.0
END DESCRIPTION:
XS GIS Cut Line= 3
       3806964.7     10143390.29      3805472.11     10143608.07
      3804864.09     10143936.59
#Sta/Elev= 30
  3491.6  220.65  3538.9  218.57  3667.7  218.37  3761.3  216.26  3807.7  218.29
  4017.7  215.56  4083.7  216.31    4184  215.36  4227.7  214.83  4286.8  210.95
  4337.3  201.63  4347.4     201  4429.8  200.96  4430.2  200.46  4435.6  200.96
  4455.5  201.48  4529.3  202.12  4559.6  205.29  4579.9  201.05  4600.1     201
  4637.6  204.67  4759.4  205.67  4812.3  205.48  4917.7  204.12  4943.7     201
  5041.2     201    5073  205.55  5358.1  210.28  5478.1  217.54  5691.1  225.69
#Mann= 9 ,-1 , 0
  3491.6     .11       0  4083.7     .15       0    4184     .17       0
  4429.8     .11       0  4435.6     .17       0  4455.5     .11       0
  4759.4    .125       0  4812.3     .07       0    5073     .11       0
#XS Ineff= 2 , 0
       0  4782.7  205.94  5095.5       0   206.1
Permanent Ineff=
       T       F
Bank Sta=4812.3,5073
XS Rating Curve= 0 ,0
Exp/Cntr=0.3,0.1

Type RM Length L Ch R = 1 ,19071   ,571,571,571
BEGIN DESCRIPTION:
BELL CREEK 38.0
END DESCRIPTION:
XS GIS Cut Line= 3
      3806968.75      10143353.8      3805308.37     10143211.03
      3804510.89     10143263.36
#Sta/Elev= 30
  3333.5  221.06  3565.2  217.44  3777.5   216.4  3826.2  217.72    3919  215.57
  4137.4  210.01  4215.2  210.32  4287.9  209.88  4367.3  205.04  4408.3  201.06
    4546  200.54  4546.4  200.04  4551.8  200.54  4659.3  200.98  4669.3  203.48
  4708.8     201  4739.6     201  4769.7  205.11  4906.2  205.49  4938.2     201
  5050.6  201.48  5081.3  205.36  5271.1  206.86  5321.2  210.99  5391.4  211.02
  5441.5  215.29  5541.7  219.44  5631.9  221.37  5712.1  220.72  5799.2  224.23
#Mann= 9 ,-1 , 0
  3333.5     .11       0    3919     .17       0  4215.2     .11       0
  4367.3     .15       0    4546     .12       0  4551.8     .15       0
  4708.8    .125       0  4906.2     .07       0  5081.3     .11       0
#XS Ineff= 2 , 0
       0  4900.2  205.97  5180.9       0  205.92
Permanent Ineff=
       T       F
Bank Sta=4906.2,5081.3
XS Rating Curve= 0 ,0
Exp/Cntr=0.3,0.1

Type RM Length L Ch R = 1 ,18500   ,500,500,500
BEGIN DESCRIPTION:
BELL CREEK 37.0
END DESCRIPTION:
XS GIS Cut Line= 3
      3806984.41     10143328.47       3805177.3     10142663.99
      3804521.18     10142425.27
#Sta/Elev= 30
  3074.6  220.95  3082.9  220.84  3305.3  217.84  3600.7  217.04  3678.2  215.78
  3699.6  216.62  3731.5  215.59  3997.9  214.03  4183.5  209.29  4189.7  208.16
  4239.1  206.71    4300  206.41  4330.5  205.06  4349.5  203.11  4355.7     201
  4534.4     201  4583.4  202.65  4638.1     201  4658.5     201  4667.6  202.63
  4775.7  204.44  4914.2   203.9  4924.8  202.58  4930.6  200.23  5049.9  200.79
  5063.3  203.03  5085.8  203.93  5236.8  206.04  5425.1   208.2  5698.2  216.77
#Mann= 8 ,-1 , 0
  3074.6    .125       0  3082.9    .125       0  4534.4     .15       0
  4638.1     .11       0  4667.6    .125       0  4914.2     .09       0
  5085.8     .15       0  5236.8     .11       0
#XS Ineff= 2 , 0
       0  4330.5  205.06               0
Permanent Ineff=
       F       F
Bank Sta=4914.2,5085.8
XS Rating Curve= 0 ,0
Exp/Cntr=0.3,0.1

Type RM Length L Ch R = 1 ,18000   ,500,500,500
BEGIN DESCRIPTION:
BELL CREEK 36.0
END DESCRIPTION:
XS GIS Cut Line= 3
       3806993.8     10143304.06      3805181.92     10142173.25
      3804452.23     10141999.89
#Sta/Elev= 30
  2864.2  221.44  3095.2  217.91  3319.4  217.76    3350  216.68  3575.4  214.68
  3625.6  213.12  3669.7  214.11  3696.9  212.94  3742.9  213.05    3895  210.58
  3952.8   208.6  3989.4  209.23    4105  206.12    4184  206.23  4214.7  203.38
  4220.6  204.37  4272.5  202.67  4285.7  204.64  4299.6  203.69  4309.1  201.36
    4315  201.09  4424.7  200.95  4471.8   199.7  4482.5     201  5127.5  200.67
  5137.8  201.44  5148.1  203.53  5415.3  208.69  5631.2  216.39    5750  222.07
#Mann= 3 , 0 , 0
  2864.2     .12       0  4299.6     .07       0  5148.1     .12       0
Bank Sta=4299.6,5148.1
XS Rating Curve= 0 ,0
Exp/Cntr=0.3,0.1

Type RM Length L Ch R = 1 ,17500   ,500,500,500
BEGIN DESCRIPTION:
BELL CREEK 35.0
END DESCRIPTION:
XS GIS Cut Line= 3
       3807004.5      10143294.3       3805507.5     10141814.71
      3804036.72     10141560.45
#Sta/Elev= 30
  2895.2  221.64  3602.2  213.54  3800.2  213.33  3814.4  216.64  3828.5  213.61
  3856.8  212.53  4047.7  211.09  4436.7  203.66    4465     201  4592.2     201
  4601.9  199.66  4613.4     201  5669.4  200.74  5695.6  203.16  5700.7   201.2
  5730.3   203.8  5750.3  206.17  5755.4  204.91  5770.9  205.55  5791.2  209.23
  5810.1   210.6  5815.2  207.66  5821.7  208.96  5852.1  208.73  5892.7  213.72
  6049.3     217  6126.1  221.15  6163.8  220.26  6338.2   227.7  6492.6  231.29
#Mann= 3 , 0 , 0
  2895.2     .11       0  4436.7     .06       0  5730.3     .11       0
#XS Ineff= 2 , 0
       0                  5750.3       0  206.17
Permanent Ineff=
       F       F
Bank Sta=4436.7,5730.3
XS Rating Curve= 0 ,0
Exp/Cntr=0.3,0.1

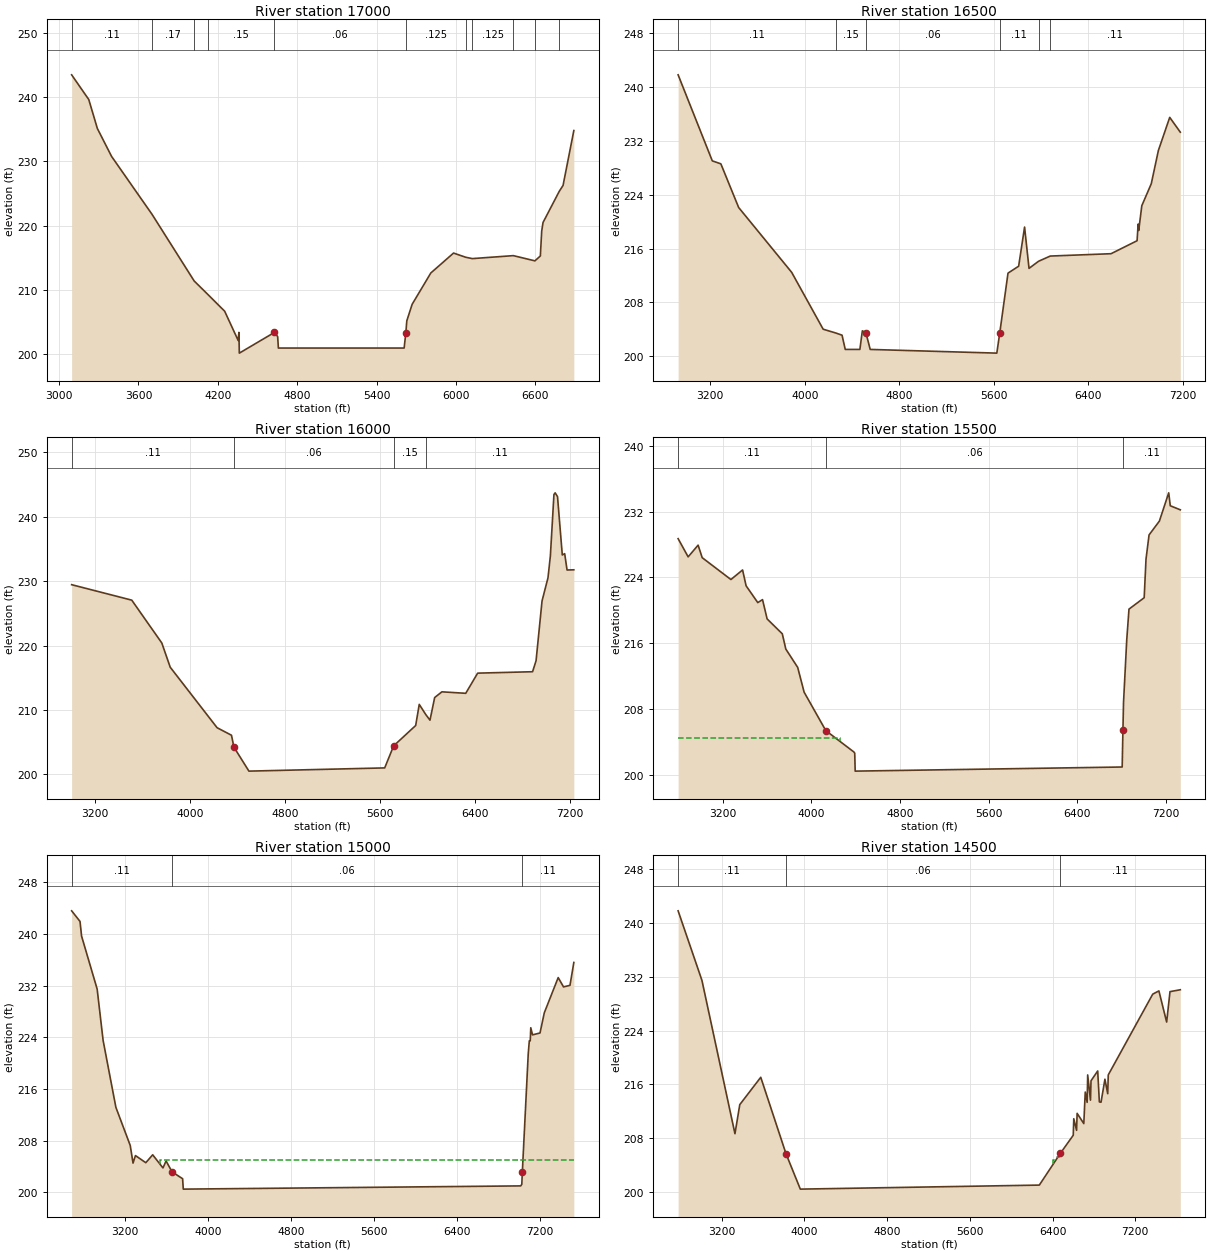
Type RM Length L Ch R = 1 ,17000   ,500,500,500
BEGIN DESCRIPTION:
BELL CREEK 34.0
END DESCRIPTION:
XS GIS Cut Line= 3
      3807597.99     10142156.64      3805830.36     10141446.37
      3803957.15     10141186.82
#Sta/Elev= 30
    3095  243.46  3224.5  239.62  3289.4  235.12  3396.9  230.78    3703  221.77
  4021.3  211.42    4126   209.3  4251.8  206.72  4353.9  202.17  4359.3  203.43
  4362.5  200.21  4628.1  203.43  4652.3  202.78  4657.8     201  5608.3     201
 5621.21  203.38  5628.5  205.23  5668.8   207.8  5810.2  212.67  5981.8  215.76
  6073.7  215.11  6123.6   214.9  6433.8  215.36  6596.9  214.55    6638  215.31
  6648.1  219.16  6658.2  220.51    6781  225.36  6809.6  226.27  6891.1   234.8
#Mann= 11 ,-1 , 0
    3095     .11       0    3703     .17       0  4021.3     .11       0
    4126     .15       0  4628.1     .06       0 5621.21    .125       0
  6073.7     .11       0  6123.6    .125       0  6433.8     .11       0
  6596.9    .125       0    6781     .11       0
Bank Sta=4628.1,5621.21
XS Rating Curve= 0 ,0
Exp/Cntr=0.3,0.1

Type RM Length L Ch R = 1 ,16500   ,500,500,500
BEGIN DESCRIPTION:
BELL CREEK 33.0
END DESCRIPTION:
XS GIS Cut Line= 3
      3807613.84     10142085.07      3805876.54     10140954.28
      3803702.79     10140789.36
#Sta/Elev= 30
  2927.1  241.85  3216.6  229.05  3289.1  228.61  3439.9  222.11  3888.8  212.47
  4155.4  204.01  4262.8  203.44  4315.4  203.12  4342.5     201  4466.3     201
  4487.4  203.77  4517.6  203.47  4553.9     201  5626.1  200.45  5650.6   203.4
  5720.8  212.35    5811  213.38  5861.2   219.2  5898.9  213.06  5980.1  214.12
  6078.8  214.89  6593.3  215.24  6813.9  217.17  6822.9  219.65  6827.9   218.7
    6854  222.38  6934.2  225.65  6994.4   230.6  7090.4  235.52    7180  233.32
#Mann= 6 ,-1 , 0
  2927.1     .11       0  4262.8     .15       0  4517.6     .06       0
  5650.6     .11       0  5980.1     .15       0  6078.8     .11       0
Bank Sta=4517.6,5650.6
XS Rating Curve= 0 ,0
Exp/Cntr=0.3,0.1

Type RM Length L Ch R = 1 ,16000   ,500,500,500
BEGIN DESCRIPTION:
BELL CREEK 32.0
END DESCRIPTION:
XS GIS Cut Line= 3
      3807868.23     10140757.56      3805895.65     10140454.64
      3803670.99     10140646.27
#Sta/Elev= 30
  3004.3  229.44  3510.5  227.04  3763.5  220.39  3834.3  216.63  4228.9  207.24
  4350.3  206.07  4370.5  204.23  4497.1   200.5  5640.2     201  5715.6  204.42
  5901.1  207.58  5931.2  210.86    5987  209.26  6021.6  208.41    6061  211.92
  6121.9  212.81  6322.7  212.58  6423.1  215.71  6885.4  215.93  6914.9  217.64
  6965.1  226.91  7015.2  230.51  7035.3   233.9  7065.4  243.43  7075.5   243.7
  7095.5  243.11  7135.7  234.05  7155.8  234.26  7175.8  231.72  7232.9  231.75
#Mann= 4 ,-1 , 0
  3004.3     .11       0  4370.5     .06       0  5715.6     .15       0
    5987     .11       0
Bank Sta=4370.5,5715.6
XS Rating Curve= 0 ,0
Exp/Cntr=0.3,0.1

Type RM Length L Ch R = 1 ,15500   ,500,500,500
BEGIN DESCRIPTION:
BELL CREEK 31.0
END DESCRIPTION:
XS GIS Cut Line= 3
       3807939.8     10140654.22      3805849.91     10139961.51
      3803575.64     10140455.48
#Sta/Elev= 30
  2798.3  228.71  2888.8   226.5  2978.6  227.92  3015.6   226.4  3274.4  223.75
  3379.8  224.91  3411.4  222.99  3516.7  220.95  3559.7  221.31    3601  218.97
    3738  217.16  3769.6  215.31  3876.6  213.09  3934.8  210.08  4130.2  205.42
  4383.7  202.82  4391.1  202.68  4395.2   200.5  6803.1     201    6810  205.54
  6815.2  208.82  6844.1  216.39  6864.5  220.16  7001.5  221.54    7018  226.22
  7045.5  229.16  7138.7  230.84  7222.7  234.27  7236.9   232.7  7327.3  232.21
#Mann= 3 , 0 , 0
  2798.3     .11       0  4130.2     .06       0    6810     .11       0
#XS Ineff= 2 , 0
       0    4257  204.52               0
Permanent Ineff=
       F       F
Bank Sta=4130.2,6810
XS Rating Curve= 0 ,0
Exp/Cntr=0.3,0.1

Type RM Length L Ch R = 1 ,15000   ,500,500,500
BEGIN DESCRIPTION:
BELL CREEK 30.0
END DESCRIPTION:
XS GIS Cut Line= 3
      3807780.84     10138181.96      3805850.16     10139461.51
      3803401.82     10140089.54
#Sta/Elev= 30
  2683.8  243.56  2764.5  241.92  2779.6  239.65  2929.9  231.45  2987.3  223.51
  3110.4  213.16  3248.8  207.26  3275.9  204.53  3299.2  205.69  3399.2  204.59
  3465.4  205.81  3564.6  203.78  3594.7  204.86  3651.9  203.18  3754.2  202.11
  3760.5   200.5  7015.5     201  7025.7  201.25  7030.8  203.14  7087.8  221.44
  7098.1  223.44  7107.2  223.46  7112.4  225.47  7129.1  224.37  7201.3  224.66
  7242.6  227.78  7376.8  233.23  7428.2  231.79  7490.4  232.03  7527.6  235.57
#Mann= 3 , 0 , 0
  2683.8     .11       0  3651.9     .06       0  7030.8     .11       0
#XS Ineff= 2 ,-1
  3537.6  3263.2  205.08  3594.7  3537.6  204.86
Permanent Ineff=
       F       F
Bank Sta=3651.9,7030.8
XS Rating Curve= 0 ,0
Exp/Cntr=0.3,0.1

Type RM Length L Ch R = 1 ,14500   ,500,500,500
BEGIN DESCRIPTION:
BELL CREEK 29.0
END DESCRIPTION:
XS GIS Cut Line= 3
      3807757.02     10138094.52      3805724.65     10138991.73
      3803211.36      10139787.3
#Sta/Elev= 30
  2778.4  241.83  3008.8  231.48  3328.3  208.65  3374.9  212.98  3577.8  217.05
  3821.8  205.68  3960.6   200.4  6272.3     201  6476.6  205.74  6600.6  208.42
  6605.8  210.88  6632.9  209.15  6638.1  211.68  6702.7  210.16  6716.8  214.85
    6735  213.32  6740.3   217.4  6767.3  213.65  6772.6  216.53  6837.2  217.99
  6853.2  213.38  6869.5  213.34    6907  216.76  6934.1  214.61  6939.3   217.4
  7369.7  229.43  7429.1  229.91  7504.2  225.27  7536.5   229.8  7636.2  230.08
#Mann= 3 , 0 , 0
  2778.4     .11       0  3821.8     .06       0  6476.6     .11       0
#XS Ineff= 2 ,-1
  6406.8  6444.3  204.77  6444.3  6476.6  205.16
Permanent Ineff=
       F       F
Bank Sta=3821.8,6476.6
XS Rating Curve= 0 ,0
Exp/Cntr=0.3,0.1

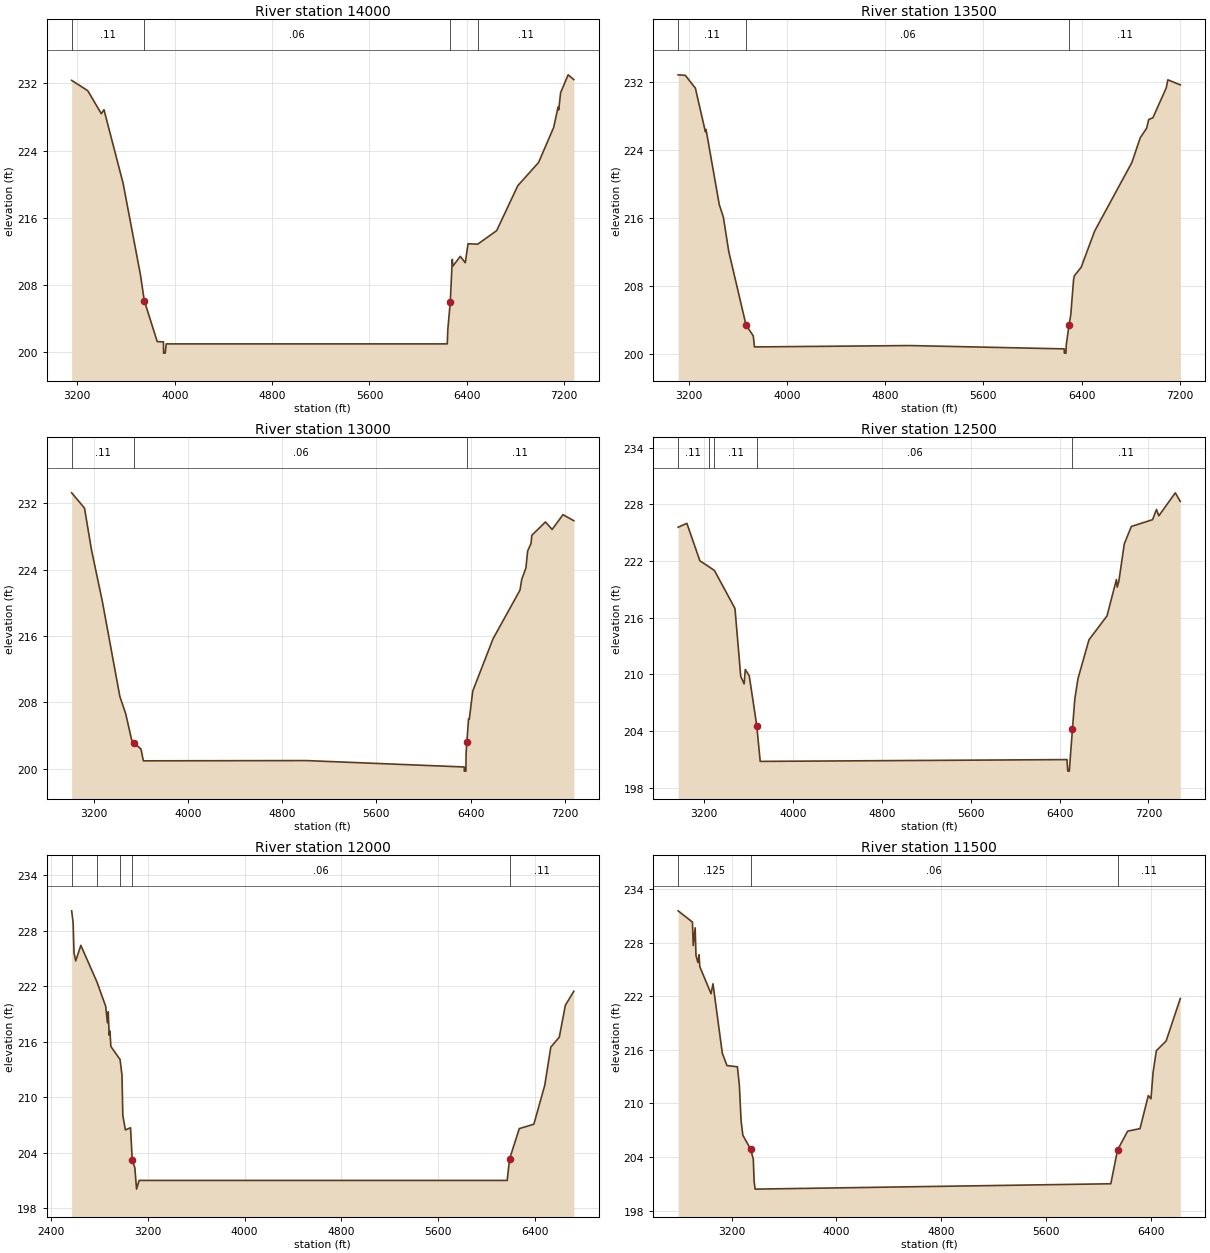
Type RM Length L Ch R = 1 ,14000   ,500,500,500
BEGIN DESCRIPTION:
BELL CREEK 28.0
END DESCRIPTION:
XS GIS Cut Line= 3
      3807168.69     10137768.63      3805494.54     10138547.82
      3803282.33     10139095.95
#Sta/Elev= 30
  3153.4  232.37  3285.4  231.15    3397   228.4    3419  228.88  3576.4   220.1
  3719.2  209.18  3749.9  206.16  3856.5  201.27  3907.8  201.24  3908.8   199.9
  3921.9   199.9  3930.7     201  6239.1     201  6244.2  202.78  6263.8  205.95
  6280.5  211.06  6285.6  210.26  6346.2  211.42  6387.4  210.66  6409.8  212.92
  6489.5  212.87    6645  214.48  6818.6  219.83  6989.3  222.59  7113.5  226.77
  7149.8   229.2  7154.9  228.86  7170.4   230.9  7232.2  233.03  7279.1  232.46
#Mann= 4 ,-1 , 0
  3153.4     .11       0  3749.9     .06       0  6263.8    .125       0
  6489.5     .11       0
Bank Sta=3749.9,6263.8
XS Rating Curve= 0 ,0
Exp/Cntr=0.3,0.1

Type RM Length L Ch R = 1 ,13500   ,500,500,500
BEGIN DESCRIPTION:
BELL CREEK 27.0
END DESCRIPTION:
XS GIS Cut Line= 3
       3807105.1     10137697.08      3805264.43     10138103.92
      3803265.61     10139032.55
#Sta/Elev= 30
  3114.9  232.85  3173.5  232.79  3255.5  231.28  3337.1  226.15  3342.2  226.43
    3450  217.59  3483.4   216.1  3527.1  212.08  3668.2   203.4  3726.6  202.15
  3736.8  200.84  5003.4     201  6259.1  200.61  6259.6  200.11  6273.1  200.11
  6275.3  201.07  6297.4  203.38  6312.2  204.62  6335.1  208.78  6341.5  209.21
  6396.6  210.21  6506.9  214.48  6809.5  222.53  6878.2  225.46  6929.5  226.56
  6946.8  227.59    6981   227.8  7089.7  231.32  7102.3  232.26    7204  231.67
#Mann= 3 , 0 , 0
  3114.9     .11       0  3668.2     .06       0  6297.4     .11       0
Bank Sta=3668.2,6297.4
XS Rating Curve= 0 ,0
Exp/Cntr=0.3,0.1

Type RM Length L Ch R = 1 ,13000   ,500,500,500
BEGIN DESCRIPTION:
BELL CREEK 26.0
END DESCRIPTION:
XS GIS Cut Line= 3
      3807097.16     10137617.58      3805108.23     10137634.23
      3803251.27     10138951.96
#Sta/Elev= 30
    3011  233.25  3120.3  231.41  3180.3  226.32  3270.3  220.28  3420.3  208.74
  3470.3  206.64  3520.3  203.52  3540.3  203.15  3600.3  202.38  3620.3  200.97
  5004.9     201    6346  200.23  6346.5  199.73    6360  199.73  6361.5  201.85
    6368  203.21  6382.7  206.03  6388.9  205.98  6418.4  209.38  6590.7  215.67
  6819.5  221.53  6834.2  222.82  6869.9   224.2  6884.7  226.25  6913.3  227.15
  6920.3  228.14  7035.9  229.74  7092.6  228.84  7184.8  230.62    7277  229.89
#Mann= 3 , 0 , 0
    3011     .11       0  3540.3     .06       0    6368     .11       0
Bank Sta=3540.3,6368
XS Rating Curve= 0 ,0
Exp/Cntr=0.3,0.1

Type RM Length L Ch R = 1 ,12500   ,500,500,500
BEGIN DESCRIPTION:
BELL CREEK 25.0
END DESCRIPTION:
XS GIS Cut Line= 3
      3806954.05     10136647.77      3804981.39     10137151.27
      3803202.42     10138889.07
#Sta/Elev= 30
  2964.1  225.58    3043  225.99  3160.4  222.02  3237.9  221.43  3291.4     221
  3476.2  216.98  3528.1   209.8  3558.7     209  3569.1  210.53  3604.7  209.86
  3672.3  204.59  3703.3   200.8  6466.2  200.99  6473.6  199.77  6487.1  199.77
  6515.6  204.24  6536.9  207.41  6565.2  209.55  6664.2  213.66  6826.8   216.2
  6911.7  220.05  6918.8  219.24    6933  219.83  6982.4  223.82    7046  225.66
    7237  226.38  7272.3  227.45  7293.6  226.79    7442  229.22  7486.9  228.31
#Mann= 5 ,-1 , 0
  2964.1     .11       0  3237.9     .17       0  3291.4     .11       0
  3672.3     .06       0  6515.6     .11       0
Bank Sta=3672.3,6515.6
XS Rating Curve= 0 ,0
Exp/Cntr=0.3,0.1

Type RM Length L Ch R = 1 ,12000   ,500,500,500
BEGIN DESCRIPTION:
BELL CREEK 24.0
END DESCRIPTION:
XS GIS Cut Line= 3
       3806532.8     10134938.63      3804835.08     10136673.15
       3803117.9     10136611.07
#Sta/Elev= 30
  2572.9  230.13  2585.2  228.85  2592.2  225.61  2606.4  224.72  2648.8   226.4
  2781.8  222.44    2854  219.81  2868.1  218.03  2875.1  219.22  2882.3  216.69
  2889.2  217.13  2896.4  215.48  2972.5  214.07  2988.3  212.39  2995.4  208.03
  3016.5  206.46    3059  206.69  3073.1   203.2  3094.3  202.38  3108.7  200.06
  3129.7     201    6168     201    6188  203.33  6268.1   206.6  6388.1  207.07
  6478.2  211.28  6528.2   215.4  6598.3  216.48  6648.3  219.93  6718.3  221.44
#Mann= 5 ,-1 , 0
  2572.9     .15       0  2781.8    .125       0  2972.5     .11       0
  3073.1     .06       0    6188     .11       0
Bank Sta=3073.1,6188
XS Rating Curve= 0 ,0
Exp/Cntr=0.3,0.1

Type RM Length L Ch R = 1 ,11500   ,500,500,500
BEGIN DESCRIPTION:
BELL CREEK 23.0
END DESCRIPTION:
XS GIS Cut Line= 3
      3806477.12     10134898.92      3804688.72     10136195.05
      3803098.71     10136528.51
#Sta/Elev= 30
  2791.3  231.57  2900.6  230.31  2906.7  227.68  2921.4  229.67  2927.6  226.55
  2942.3  225.79  2950.8  226.65    2957  225.31  3042.8  222.29  3057.5   223.4
  3128.6  215.63  3164.2  214.24  3243.9   214.1  3258.6  212.08  3272.1  208.04
  3285.6  206.42  3344.4   204.9  3365.3  203.75  3371.4  201.26  3379.3   200.4
  6094.2     201  6145.2  204.77  6222.4  206.89  6317.1  207.18  6380.3  210.88
  6400.7  210.52  6416.9  213.49  6441.6   215.9  6516.7     217  6624.6  221.75
#Mann= 3 , 0 , 0
  2791.3    .125       0  3344.4     .06       0  6145.2     .11       0
Bank Sta=3344.4,6145.2
XS Rating Curve= 0 ,0
Exp/Cntr=0.3,0.1

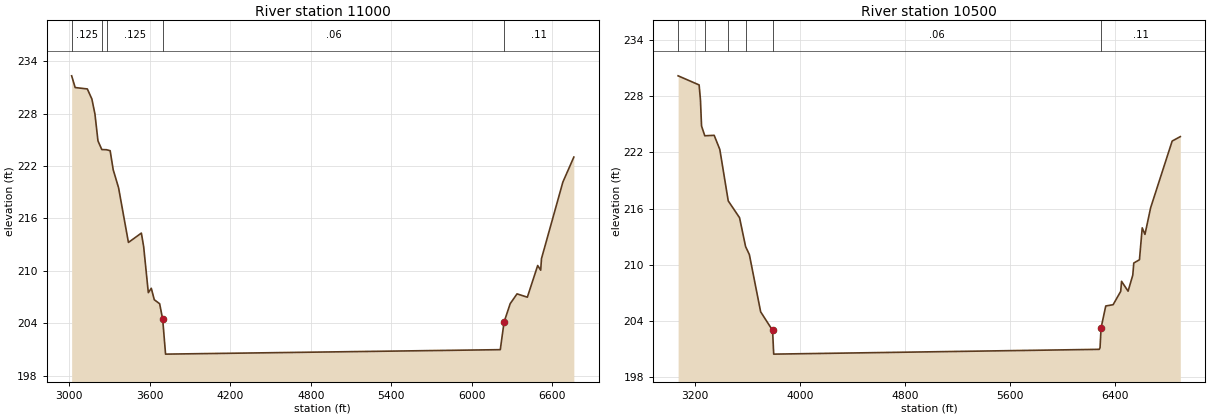
Type RM Length L Ch R = 1 ,11000   ,500,500,500
BEGIN DESCRIPTION:
BELL CREEK 22.0
END DESCRIPTION:
XS GIS Cut Line= 3
      3806453.28     10134843.27      3804665.18     10135696.64
      3803074.78     10136449.05
#Sta/Elev= 30
  3018.7  232.31  3044.9  230.97  3135.5  230.81  3169.4  229.66  3192.1  227.95
  3214.8  224.87  3243.3  223.88  3278.3  223.86  3305.5  223.75  3328.2  221.57
  3368.1  219.52  3441.7  213.26    3538  214.33  3555.1  212.78  3589.8  207.52
    3612  208.02  3634.3  206.71  3674.1  206.25  3696.8  204.49  3718.2  200.49
  6211.5     201  6239.8  204.16  6285.3  206.26  6336.3  207.38  6413.1     207
  6490.1  210.62  6512.6  210.09  6518.4  211.41  6677.7  220.16  6759.4  223.02
#Mann= 5 ,-1 , 0
  3018.7    .125       0  3243.3     .11       0  3278.3    .125       0
  3696.8     .06       0  6239.8     .11       0
Bank Sta=3696.8,6239.8
XS Rating Curve= 0 ,0
Exp/Cntr=0.3,0.1

Type RM Length L Ch R = 1 ,10500   ,500,500,500
BEGIN DESCRIPTION:
BELL CREEK 21.0
END DESCRIPTION:
XS GIS Cut Line= 3
      3806413.58     10134795.56      3804535.18     10135225.62
      3803043.01     10136393.39
#Sta/Elev= 30
    3073  230.15  3232.8  229.18    3243   227.6  3251.3   224.8    3276  223.76
  3347.4  223.81  3390.4   222.3  3454.5  216.82  3540.5  215.03  3586.6  211.95
  3615.2   211.1  3701.1     205    3792  203.02  3800.4  200.49  6277.7     201
    6284  201.17  6291.8  203.28  6327.4  205.62  6383.5  205.76  6441.3  207.18
  6447.7  208.25  6497.4   207.2  6533.1  208.91  6540.8   210.2  6583.9  210.55
    6605  213.95  6625.8  213.25  6669.2   216.1  6832.9   223.2  6894.8  223.67
#Mann= 6 ,-1 , 0
    3073    .125       0    3276     .11       0  3454.5    .125       0
  3586.6     .11       0    3792     .06       0  6291.8     .11       0
Bank Sta=3792,6291.8
XS Rating Curve= 0 ,0
Exp/Cntr=0.3,0.1