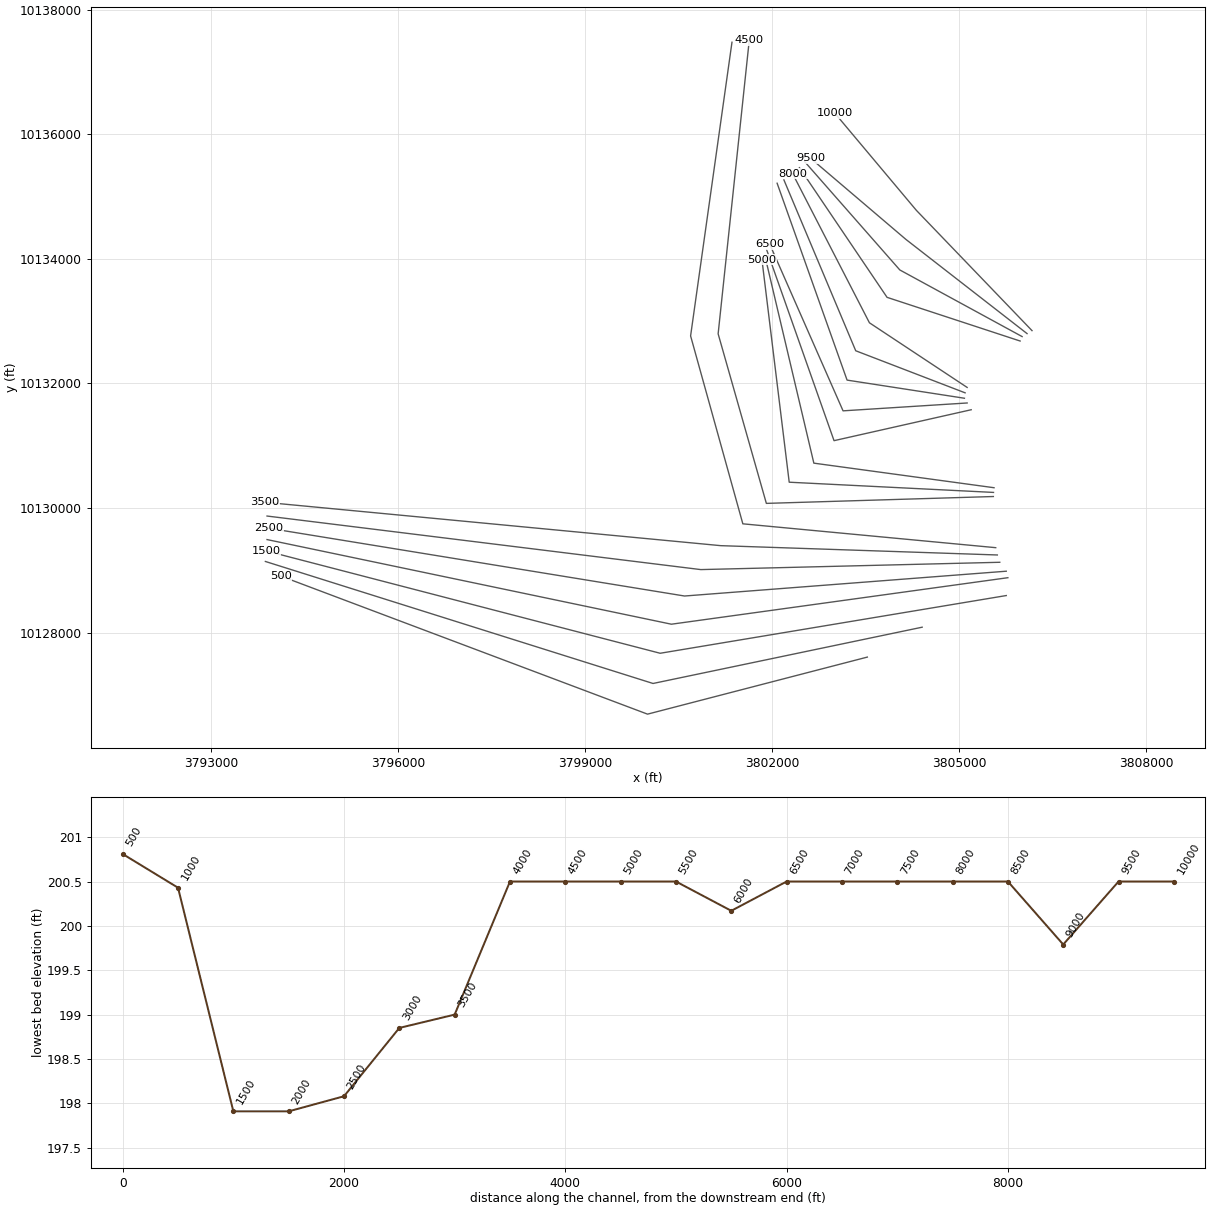
HEC-RAS study BELL CREEK.prj: BELL CREEK Base Level Engineering

--- BELL CREEK.g01 (geometry) --- (continued)

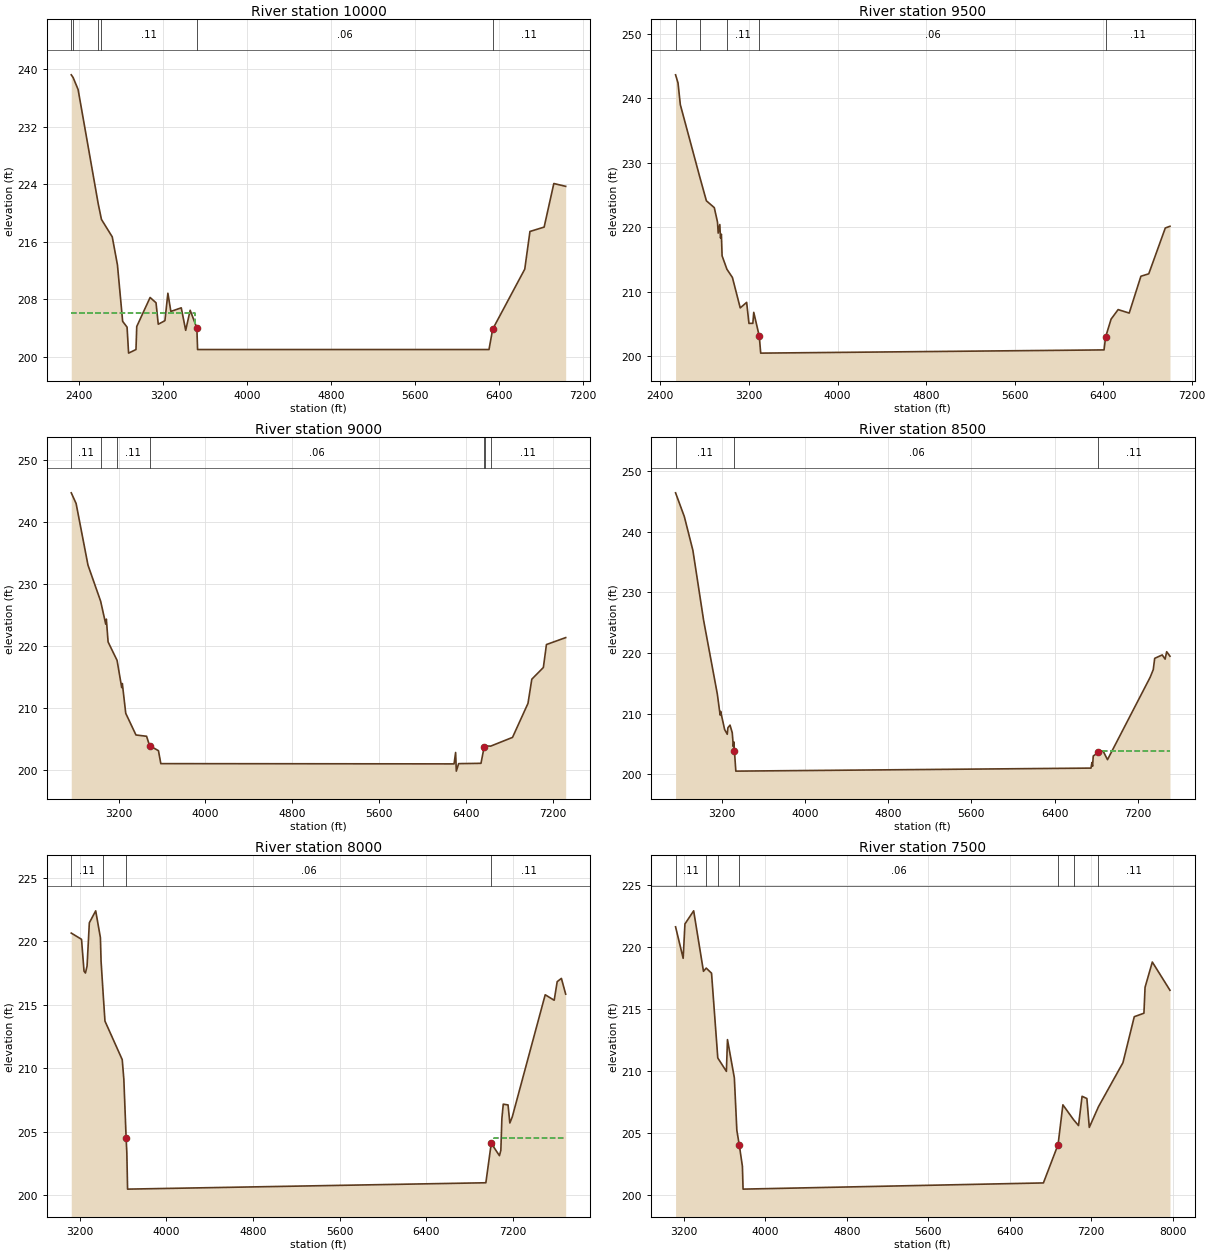
Type RM Length L Ch R = 1 ,10000   ,500,500,500
BEGIN DESCRIPTION:
BELL CREEK 20.0
END DESCRIPTION:
XS GIS Cut Line= 3
      3806167.09       10132848.      3804311.27     10134778.56
      3803003.96     10136336.92
#Sta/Elev= 30
  2322.1  239.21  2340.1  238.83  2387.4  237.16  2579.3  221.25  2609.8   219.1
  2712.8  216.67  2762.2  212.78  2811.9  204.92    2854  204.11  2868.5   200.5
  2938.9     201  2946.2   204.2  3073.5  208.24  3130.1   207.5  3151.2  204.52
  3214.7  205.01    3243  208.83  3271.3   206.3  3370.4   206.8  3412.8  203.67
  3455.3  206.46  3519.1     204  3526.1     201  6303.3     201  6338.4  203.83
  6644.1  212.18  6693.6  217.42  6828.8  218.03  6921.2  224.09  7034.1   223.7
#Mann= 6 ,-1 , 0
  2322.1     .17       0  2340.1     .11       0  2579.3    .125       0
  2609.8     .11       0  3519.1     .06       0  6338.4     .11       0
#XS Ineff= 2 , 0
       0    3505  206.15               0
Permanent Ineff=
       F       F
Bank Sta=3519.1,6338.4
XS Rating Curve= 0 ,0
Exp/Cntr=0.3,0.1

Type RM Length L Ch R = 1 ,9500    ,500,500,500
BEGIN DESCRIPTION:
BELL CREEK 19.0
END DESCRIPTION:
XS GIS Cut Line= 3
      3806087.61     10132800.29      3804143.36     10134312.16
      3802617.84     10135611.08
#Sta/Elev= 30
  2537.1  243.65  2559.3  242.39  2580.1  239.02  2755.7  227.82  2815.5  224.12
  2886.9  223.06  2915.8  220.83  2922.2  219.11  2936.7  220.44    2943  218.35
  2951.1  218.93  2957.5  215.58    3001  213.51  3050.7  212.23  3121.3  207.51
  3179.2  208.37    3200  205.11  3235.3  205.12  3243.4  206.82  3293.2  203.14
  3306.3   200.5  6407.9     201  6422.1     203  6471.5  205.77  6535.2  207.25
  6635.2  206.71  6740.9  212.42    6812   212.8  6961.3   219.9  7003.6  220.17
#Mann= 5 ,-1 , 0
  2537.1     .11       0  2755.7    .125       0    3001     .11       0
  3293.2     .06       0  6422.1     .11       0
Bank Sta=3293.2,6422.1
XS Rating Curve= 0 ,0
Exp/Cntr=0.3,0.1

Type RM Length L Ch R = 1 ,9000    ,500,500,500
BEGIN DESCRIPTION:
BELL CREEK 18.0
END DESCRIPTION:
XS GIS Cut Line= 3
      3806008.16     10132752.57      3804045.83     10133821.77
      3802517.88     10135561.04
#Sta/Elev= 30
  2765.3  244.75    2810  243.02  2919.2  233.07  3035.7  227.24  3082.5  223.54
  3088.2  224.35  3104.3  220.66  3186.9  217.68  3229.6  213.28  3235.3  213.94
  3266.7  209.13  3360.7  205.63  3458.5  205.42    3486  203.91  3567.7  203.09
  3589.5     201    6288  200.96  6302.2   202.8  6308.7  199.79  6330.2     201
  6535.7  201.05  6564.1  203.63  6570.5  203.86  6625.1  203.83    6826  205.24
  6968.3  210.74  7003.4  214.64  7109.7  216.53  7138.2  220.24  7315.1  221.36
#Mann= 7 ,-1 , 0
  2765.3     .11       0  3035.7    .125       0  3186.9     .11       0
    3486     .06       0  6564.1     .11       0  6570.5    .125       0
  6625.1     .11       0
Bank Sta=3486,6564.1
XS Rating Curve= 0 ,0
Exp/Cntr=0.3,0.1

Type RM Length L Ch R = 1 ,8500    ,500,500,500
BEGIN DESCRIPTION:
BELL CREEK 17.0
END DESCRIPTION:
XS GIS Cut Line= 3
      3805976.29     10132681.06      3803841.24     10133382.13
      3802435.29     10135462.97
#Sta/Elev= 30
  2752.8  246.39  2836.8  242.49  2919.6   236.9  3022.4   225.4  3154.9   213.2
  3181.5  209.75  3186.8  210.35  3224.8  207.37  3250.4  206.58  3256.4  207.65
  3276.9  208.09  3298.5  206.82  3308.8  204.54    3314  205.32  3319.5  203.81
  3332.8   200.5  6751.2     201  6760.1  201.92  6766.1   201.3  6772.8  202.99
  6823.1   203.6    6868   203.8    6910  202.39  7320.6  215.98  7350.5  217.24
  7364.2   219.1  7436.6  219.66  7464.4  218.97  7479.4  220.19  7511.3  219.45
#Mann= 3 , 0 , 0
  2752.8     .11       0  3319.5     .06       0  6823.1     .11       0
#XS Ineff= 2 , 0
       0                    6859       0  203.86
Permanent Ineff=
       F       F
Bank Sta=3319.5,6823.1
XS Rating Curve= 0 ,0
Exp/Cntr=0.3,0.1

Type RM Length L Ch R = 1 ,8000    ,500,500,500
BEGIN DESCRIPTION:
BELL CREEK 16.0
END DESCRIPTION:
XS GIS Cut Line= 3
      3805126.27     10131936.51      3803558.29     10132973.91
      3802326.77     10135365.33
#Sta/Elev= 30
  3119.9  220.63  3214.8  220.14  3237.9  217.64  3250.9  217.49    3266  218.04
    3287  221.44  3345.8  222.38  3389.4  220.27  3395.4  218.43    3417  215.56
  3431.5  213.71    3591  210.68    3606  209.13  3627.1  204.51  3633.6  203.35
  3640.4   200.5  6952.1     201  7002.1   204.1  7077.7  203.13  7090.7  203.55
  7100.2  206.04  7112.9  207.18  7157.2  207.12  7173.8   205.7    7196  206.17
  7500.7  215.78  7583.7  215.35  7611.5  216.81  7650.3  217.07  7689.9  215.83
#Mann= 4 ,-1 , 0
  3119.9     .11       0    3417    .125       0  3627.1     .06       0
  7002.1     .11       0
#XS Ineff= 2 , 0
       0                  7024.2       0  204.52
Permanent Ineff=
       F       F
Bank Sta=3627.1,7002.1
XS Rating Curve= 0 ,0
Exp/Cntr=0.3,0.1

Type RM Length L Ch R = 1 ,7500    ,500,500,500
BEGIN DESCRIPTION:
BELL CREEK 15.0
END DESCRIPTION:
XS GIS Cut Line= 3
      3805093.71     10131849.71      3803338.46     10132524.82
      3802186.04     10135266.89
#Sta/Elev= 30
  3119.4  221.66  3194.1  219.12  3211.4  221.89  3297.1  222.95  3393.5  218.07
  3420.5  218.33  3472.6  217.92  3534.1  211.08  3618.5     210  3629.2  212.56
  3696.6  209.48  3721.2  205.24  3745.8  204.02  3775.8  202.34  3782.2   200.5
  6731.5     201  6875.4  204.09  6922.9   207.3  7027.9   206.1  7076.2  205.63
  7111.2  207.99  7158.3  207.81  7182.1  205.48  7272.3  207.15  7512.5   210.7
  7623.8  214.41  7718.6  214.69  7729.7  216.78    7801  218.82  7974.4  216.54
#Mann= 7 ,-1 , 0
  3119.4     .11       0  3420.5    .125       0  3534.1     .11       0
  3745.8     .06       0  6875.4     .11       0  7027.9     .17       0
  7272.3     .11       0
Bank Sta=3745.8,6875.4
XS Rating Curve= 0 ,0
Exp/Cntr=0.3,0.1

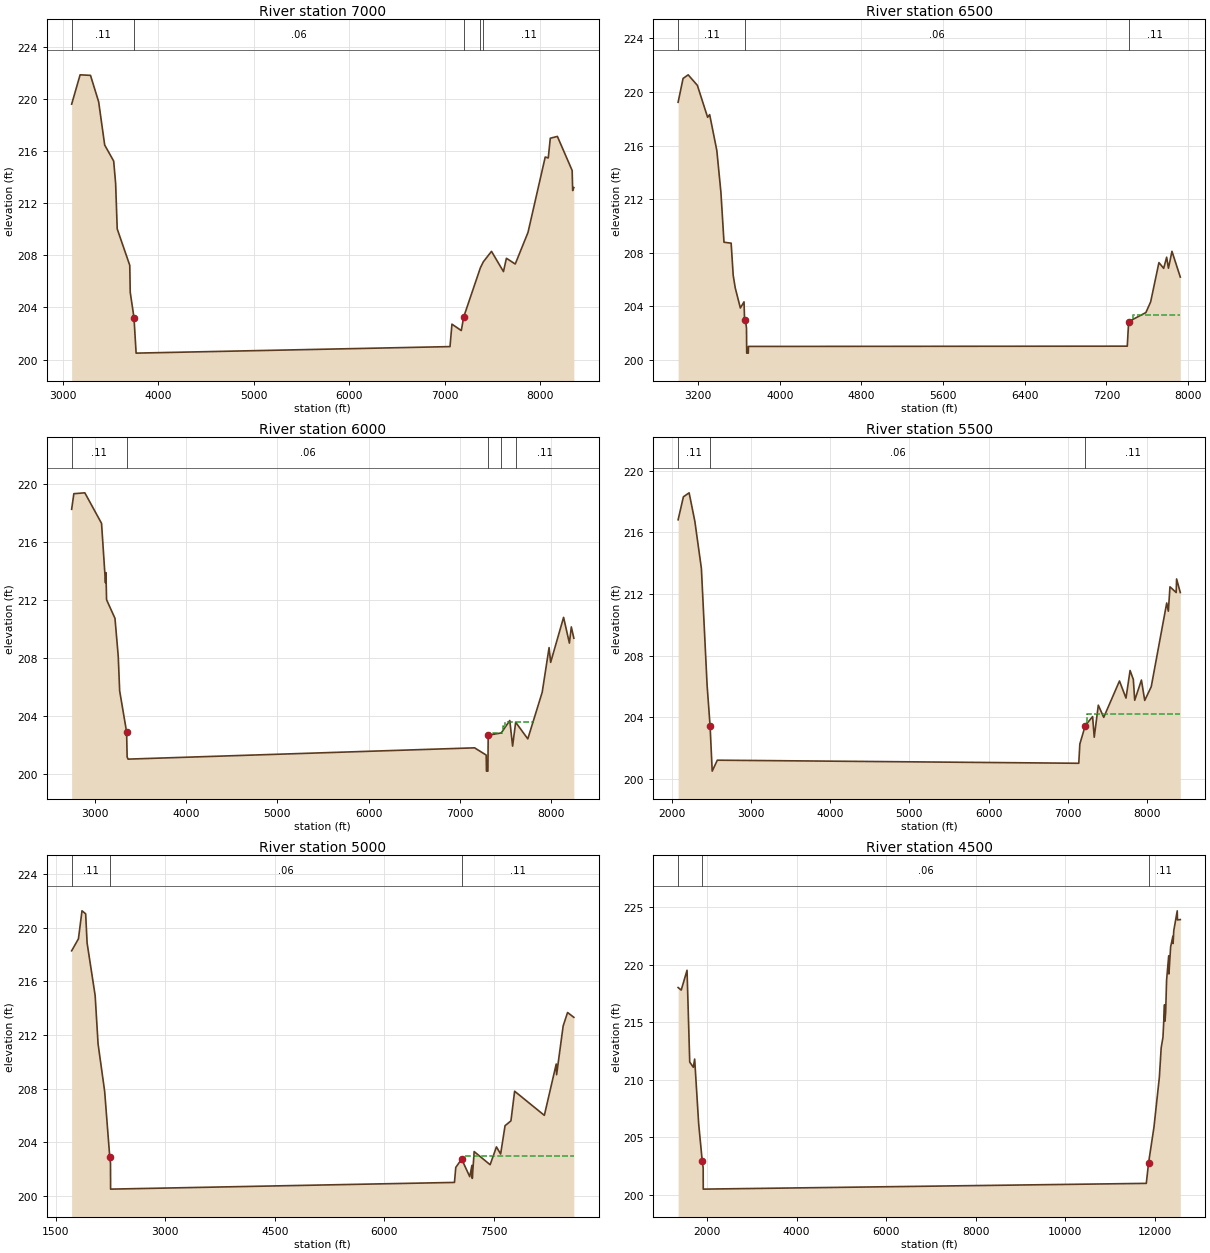
Type RM Length L Ch R = 1 ,7000    ,500,500,500
BEGIN DESCRIPTION:
BELL CREEK 14.0
END DESCRIPTION:
XS GIS Cut Line= 3
      3805082.81     10131762.92      3803199.66     10132053.95
      3802077.21     10135213.39
#Sta/Elev= 30
  3094.5  219.58  3183.1  221.83  3291.8  221.79  3377.4  219.76  3440.5  216.45
  3534.6  215.22  3554.9  213.52  3571.7  210.02    3703  207.23    3708  205.16
  3747.1  203.23  3769.5   200.5  7056.3     201  7076.6  202.72  7174.4  202.23
    7200  203.28  7373.3  207.02  7404.2  207.49  7490.8   208.3    7616  206.75
  7646.9  207.77  7739.4  207.33  7872.9  209.75  8053.3  215.53  8085.1  215.46
  8106.4  216.97  8180.6  217.11  8335.3   214.5  8340.6  212.96  8352.9  213.19
#Mann= 5 ,-1 , 0
  3094.5     .11       0  3747.1     .06       0    7200     .11       0
  7373.3     .17       0  7404.2     .11       0
Bank Sta=3747.1,7200
XS Rating Curve= 0 ,0
Exp/Cntr=0.3,0.1

Type RM Length L Ch R = 1 ,6500    ,500,500,500
BEGIN DESCRIPTION:
BELL CREEK 13.0
END DESCRIPTION:
XS GIS Cut Line= 3
      3805126.24     10131686.96      3803135.13     10131560.78
        3801958.      10134236.5
#Sta/Elev= 30
  3004.9  219.23  3053.4  221.01  3103.5  221.28  3193.7  220.49  3293.9  218.11
  3313.9  218.31    3384  215.63  3424.1  212.51  3454.2  208.78  3524.3  208.71
  3544.4  206.31  3564.4  205.37  3614.5  203.87  3650.5  204.33  3655.5  203.06
  3664.6  202.98  3674.6  202.37  3676.6   200.5  3692.6   200.5  3693.1     201
  7403.8  201.02  7417.3  202.85  7586.2  203.53  7632.9  204.33  7713.8  207.26
  7760.5  206.83  7789.3  207.66  7807.2  206.84  7841.5   208.1  7923.2  206.18
#Mann= 3 , 0 , 0
  3004.9     .11       0  3664.6     .06       0  7417.3     .11       0
#XS Ineff= 2 , 0
       0                    7464       0  203.35
Permanent Ineff=
       F       F
Bank Sta=3664.6,7417.3
XS Rating Curve= 0 ,0
Exp/Cntr=0.3,0.1

Type RM Length L Ch R = 1 ,6000    ,500,500,500
BEGIN DESCRIPTION:
BELL CREEK 12.0
END DESCRIPTION:
XS GIS Cut Line= 3
      3805191.37     10131578.46      3802990.43     10131082.17
       3801908.7     10134147.08
#Sta/Elev= 30
  2743.8  218.27  2767.9  219.35  2888.4  219.41  3071.6   217.3  3114.8  213.19
    3120  213.89  3126.7  212.02    3219  210.73  3254.8   208.1  3270.2  205.72
  3346.4  202.88  3352.2  201.15  3362.5     201  7162.2  201.78  7289.4  201.28
    7292  200.17    7308  200.17  7311.1  202.65  7454.4  202.81  7547.9  203.67
  7578.9   201.9  7612.3  203.55  7745.4   202.4  7903.2  205.62  7978.7  208.71
    7996  207.69  8137.8   210.8  8201.4  209.02  8222.6  210.14  8250.2  209.36
#Mann= 5 ,-1 , 0
  2743.8     .11       0  3346.4     .06       0  7311.1     .11       0
  7454.4     .17       0  7612.3     .11       0
#XS Ineff= 3 ,-1
  7367.7  7469.7   202.8  7469.7  7491.4  203.28  7491.4  7815.7  203.55
Permanent Ineff=
       F       F       F
Bank Sta=3346.4,7311.1
XS Rating Curve= 0 ,0
Exp/Cntr=0.3,0.1

Type RM Length L Ch R = 1 ,5500    ,500,500,500
BEGIN DESCRIPTION:
BELL CREEK 11.0
END DESCRIPTION:
XS GIS Cut Line= 3
      3805557.81     10130326.94      3802666.48     10130721.35
      3801881.23     10134047.93
#Sta/Elev= 30
  2081.9  216.81  2148.4   218.3  2220.8  218.56  2293.1  216.71  2375.5  213.66
  2447.8  206.06  2485.6  203.41    2512   200.5  2576.4  201.21  7136.9  201.01
  7150.5  202.26  7219.1  203.46  7311.5  204.04  7332.1   202.7  7383.5  204.78
  7451.8  203.99  7650.6  206.35  7732.8  205.24  7784.2  207.03  7825.3  206.45
  7842.9   205.1  7927.5  206.41  7969.1  205.09  8051.3  205.98  8246.6  211.41
  8267.1  210.88  8287.7  212.46  8366.1  212.09  8371.2  212.97    8418  212.09
#Mann= 3 , 0 , 0
  2081.9     .11       0  2485.6     .06       0  7219.1     .11       0
#XS Ineff= 2 , 0
       0                  7240.2       0  204.22
Permanent Ineff=
       F       F
Bank Sta=2485.6,7219.1
XS Rating Curve= 0 ,0
Exp/Cntr=0.3,0.1

Type RM Length L Ch R = 1 ,5000    ,500,500,500
BEGIN DESCRIPTION:
BELL CREEK 10.0
END DESCRIPTION:
XS GIS Cut Line= 3
      3805549.37     10130251.63      3802271.16      10130415.5
      3801833.64      10133986.5
#Sta/Elev= 30
  1717.7  218.27  1810.5  219.16  1859.4  221.25  1909.5  221.03  1929.5  218.85
  2039.6  214.94  2079.7  211.33  2169.8   207.8  2239.9  202.89  2249.9  202.43
  2251.3   200.5  6962.4     201  6980.3  202.12  7060.9  202.74  7171.7  201.43
  7201.6  202.27  7206.6   201.3  7232.1   203.3  7450.8  202.32  7537.3  203.65
  7594.8  203.12  7655.3  205.23  7735.9  205.59  7786.6   207.8  8193.6     206
  8356.5  209.83  8361.5  209.03  8451.2  212.66  8511.6  213.67  8597.7  213.31
#Mann= 3 , 0 , 0
  1717.7     .11       0  2239.9     .06       0  7060.9     .11       0
#XS Ineff= 2 , 0
       0                    7081       0  202.96
Permanent Ineff=
       F       F
Bank Sta=2239.9,7060.9
XS Rating Curve= 0 ,0
Exp/Cntr=0.3,0.1

Type RM Length L Ch R = 1 ,4500    ,500,500,500
BEGIN DESCRIPTION:
BELL CREEK 9.0
END DESCRIPTION:
XS GIS Cut Line= 4
      3805546.98     10130185.88      3801904.45     10130075.62
      3801130.73     10132796.56      3801629.86     10137505.78
#Sta/Elev= 30
  1355.8     218    1425  217.78    1555   219.5    1615  211.53  1695.1  211.08
  1725.1  211.79  1815.1  206.15  1895.2   202.9  1915.2  202.34  1916.6   200.5
 11805.5     201 11855.7  202.77 11976.4  205.88 12097.1  210.22 12137.3  212.76
 12177.5  213.69   12213  216.51   12218  215.07 12227.8  215.35 12237.9  215.86
   12258  218.63 12305.7  220.76 12310.7  219.18 12348.5  221.53 12398.4  222.45
 12403.4  221.82 12418.9  222.95 12496.1  224.66 12501.1  223.87 12564.4   223.9
#Mann= 3 , 0 , 0
  1355.8     .11       0  1895.2     .06       0 11855.7     .11       0
Bank Sta=1895.2,11855.7
XS Rating Curve= 0 ,0
Exp/Cntr=0.3,0.1

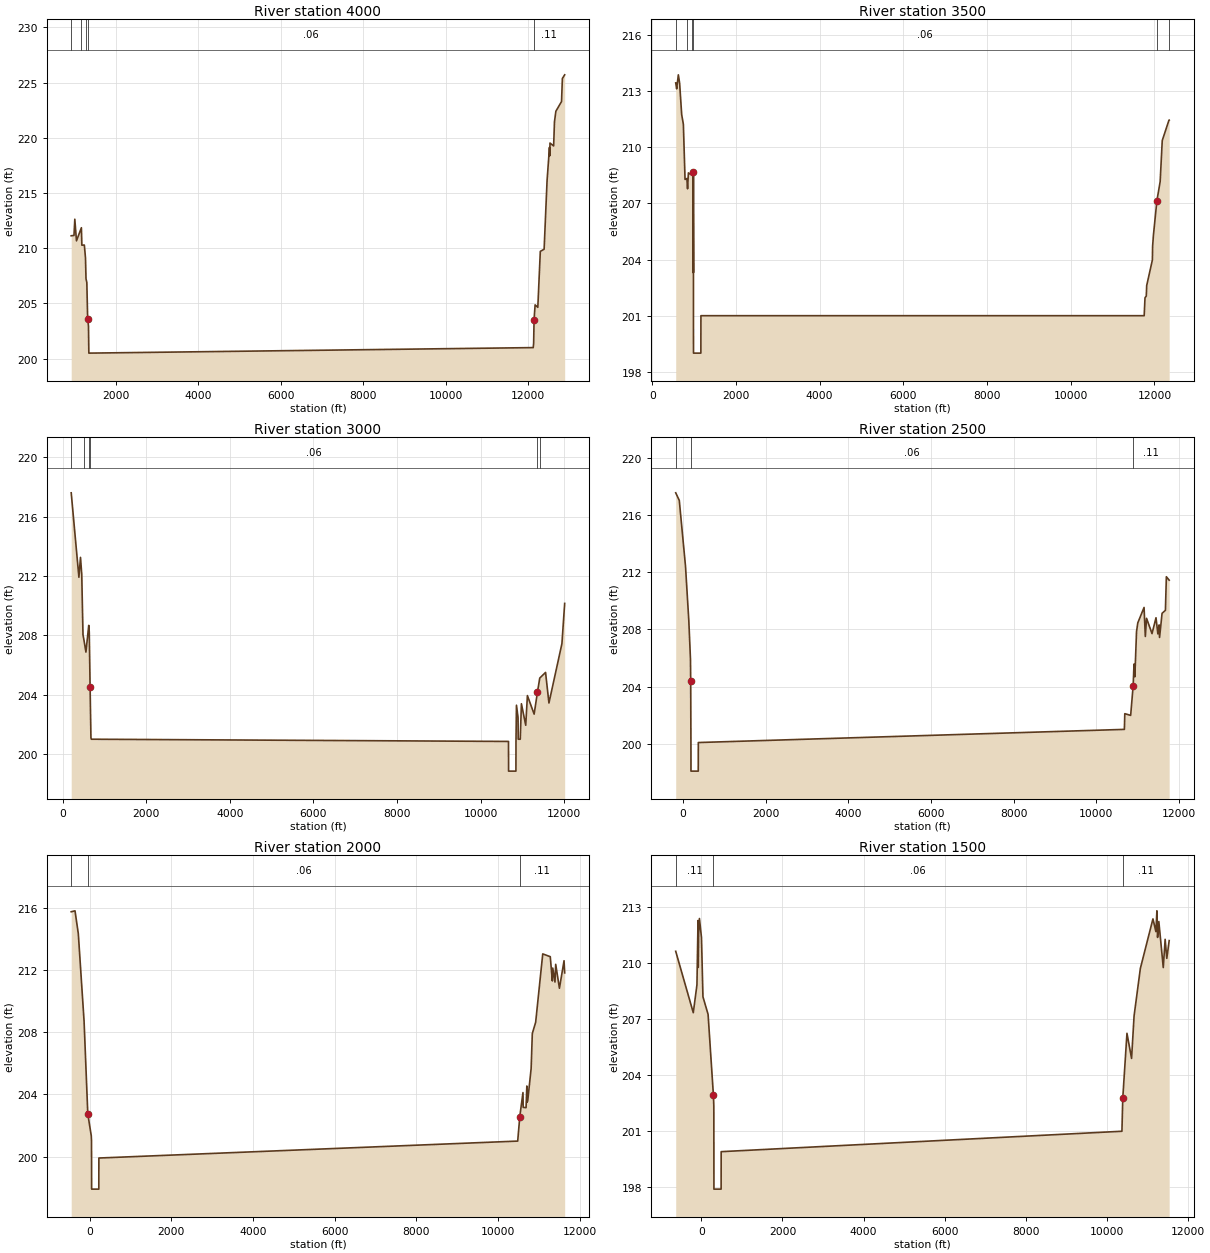
Type RM Length L Ch R = 1 ,4000    ,500,500,500
BEGIN DESCRIPTION:
BELL CREEK 8.0
END DESCRIPTION:
XS GIS Cut Line= 4
      3805584.75     10129364.88      3801527.07     10129747.68
      3800688.91     10132763.31      3801352.85     10137476.03
#Sta/Elev= 30
   924.3  211.13   991.5  211.16  1011.6  212.63  1051.8  210.67  1171.2  211.86
  1182.3  210.28  1242.6  210.29  1270.7  209.11  1282.8  207.24  1302.9   206.9
    1323  203.61  1343.1  202.94  1351.9   200.5 12126.8     201 12136.9   201.4
   12147  203.52 12172.3  204.87 12237.9  204.65 12298.5  209.72 12390.9  209.91
 12462.1  216.12 12520.6  219.14 12528.2  218.38 12533.3  219.53 12621.6  219.27
 12641.8  221.46 12675.7  222.41   12813  223.29 12833.7  225.38 12889.2  225.71
#Mann= 5 ,-1 , 0
   924.3     .11       0  1171.2    .125       0  1270.7     .11       0
    1323     .06       0   12147     .11       0
Bank Sta=1323,12147
XS Rating Curve= 0 ,0
Exp/Cntr=0.3,0.1

Type RM Length L Ch R = 1 ,3500    ,500,500,500
BEGIN DESCRIPTION:
BELL CREEK 7.0
END DESCRIPTION:
XS GIS Cut Line= 3
      3805610.77     10129247.69      3801172.78     10129397.24
      3793852.98     10130094.04
#Sta/Elev= 30
   559.5  213.44   582.4  213.12   622.4  213.87   652.5  213.43   702.5  211.74
   742.5  211.23   782.5  208.28   826.4  208.33   842.6  207.78   862.6  208.63
   955.7  208.49   972.6  208.68  982.39   203.3   982.7  208.74   983.3     201
   984.8     199  1160.6     199  1162.1     201 11755.3     201 11775.4  201.96
 11805.6  202.05 11815.6  202.61 11951.7  203.98 11956.7   204.7 11976.3   205.3
 12059.7  207.15 12137.1  208.16 12187.3  210.36 12346.7  211.44 12352.9  211.45
#Mann= 6 ,-1 , 0
   559.5     .11       0   826.4    .125       0   955.7     .11       0
   972.6     .06       0 12059.7     .11       0 12346.7    .125       0
Bank Sta=972.6,12059.7
XS Rating Curve= 0 ,0
Exp/Cntr=0.3,0.1

Type RM Length L Ch R = 1 ,3000    ,500,500,500
BEGIN DESCRIPTION:
BELL CREEK 6.0
END DESCRIPTION:
XS GIS Cut Line= 3
      3805649.86      10129130.5      3800852.69     10129013.13
      3793892.46     10129872.64
#Sta/Elev= 30
   201.4   217.6   385.5  211.91   423.5  213.25   453.5  212.11   483.5  208.03
   502.3  207.75   553.5  206.87   621.3  208.67   633.5  208.22   653.5  204.51
   673.5   201.1   683.5     201 10668.8  200.85 10670.3  198.85 10846.2  198.85
 10847.7  200.85   10859  203.29 10896.5  202.47 10901.6     201 10949.7     201
 10977.6  203.39 11080.7  201.94   11121  203.94 11282.2  202.69 11362.5  204.19
 11416.7  205.12 11555.4   205.5 11636.5  203.44 11947.2  207.44 12013.1  210.15
#Mann= 6 ,-1 , 0
   201.4     .11       0   502.3    .125       0   621.3     .11       0
   653.5     .06       0 11362.5    .125       0 11416.7     .11       0
#XS Ineff= 2 , 0
       0                   10859       0  203.29
Permanent Ineff=
       F       F
Bank Sta=653.5,11362.5
XS Rating Curve= 0 ,0
Exp/Cntr=0.3,0.1

Type RM Length L Ch R = 1 ,2500    ,500,500,500
BEGIN DESCRIPTION:
BELL CREEK 5.0
END DESCRIPTION:
XS GIS Cut Line= 3
      3805753.97     10128987.27       3800591.5     10128589.16
      3793918.04     10129677.38
#Sta/Elev= 30
  -177.8  217.55   -91.4  217.02      59  212.42   139.3   208.6   179.4   205.9
  184.42  204.39   190.2  200.08   191.7  198.08   367.6  198.08   369.1  200.08
 10677.7     201 10687.8   202.1 10829.6  201.98 10890.4  204.06 10910.7  205.57
   10931  204.68 10971.5  207.84 11001.9  208.45 11153.9  209.53 11184.3   207.5
 11214.7  208.77 11346.4   207.7 11442.7  208.81 11488.2  207.68 11518.6  208.31
 11528.8  207.43 11589.5  209.12 11670.6  209.33 11693.6  211.68 11761.6  211.44
#Mann= 3 , 0 , 0
  -177.8     .11       0  184.42     .06       0 10890.4     .11       0
#XS Ineff= 2 , 0
       0                 10687.8       0   202.1
Permanent Ineff=
       F       F
Bank Sta=184.42,10890.4
XS Rating Curve= 0 ,0
Exp/Cntr=0.3,0.1

Type RM Length L Ch R = 1 ,2000    ,500,500,500
BEGIN DESCRIPTION:
BELL CREEK 4.0
END DESCRIPTION:
XS GIS Cut Line= 3
        3805780.      10128883.1      3800380.95     10128136.74
      3793892.49     10129494.99
#Sta/Elev= 30
  -450.4  215.75  -357.4  215.81  -276.6  214.34  -135.3   208.7   -44.4  202.75
    40.2  201.35    46.4  201.02    49.3  197.91   225.2  197.91   226.7  199.91
 10479.3     201 10530.4  202.58 10608.2  204.12 10613.4  203.17 10683.7  203.15
   10703  204.54 10708.1   203.5 10724.5  203.59   10808  205.67 10836.9  207.92
 10918.7  208.64 11092.3  213.04 11276.2  212.86 11327.3   211.3   11337  212.13
   11392  211.23 11409.1  212.37   11501  210.83 11613.4   212.6 11629.1  211.82
#Mann= 3 , 0 , 0
  -450.4     .11       0   -44.4     .06       0 10530.4     .11       0
#XS Ineff= 2 , 0
       0                 10508.4       0  201.89
Permanent Ineff=
       F       F
Bank Sta=-44.4,10530.4
XS Rating Curve= 0 ,0
Exp/Cntr=0.3,0.1

Type RM Length L Ch R = 1 ,1500    ,500,500,500
BEGIN DESCRIPTION:
BELL CREEK 3.0
END DESCRIPTION:
XS GIS Cut Line= 3
      3805754.01     10128596.65      3800200.62     10127670.39
      3793880.93      10129312.3
#Sta/Elev= 30
  -630.1  210.61  -197.1  207.33  -106.8  208.82   -80.5  212.25   -75.4  209.75
   -66.3  211.47     -46  212.36     4.7  211.35    41.1  208.18   167.8  207.24
   298.7  202.92   308.9  202.34   311.5  197.91   488.6  197.91   490.1  199.91
 10365.2     201 10385.8  202.76 10489.2  206.23 10602.8  204.89 10664.6  207.16
 10819.8   209.7 11129.7  212.34 11202.1  211.66 11227.1  212.77 11243.4  211.35
 11274.4   212.2 11384.2  209.74 11429.9  211.25 11470.7  210.23 11529.5  211.18
#Mann= 3 , 0 , 0
  -630.1     .11       0   298.7     .06       0 10385.8     .11       0
Bank Sta=298.7,10385.8
XS Rating Curve= 0 ,0
Exp/Cntr=0.3,0.1

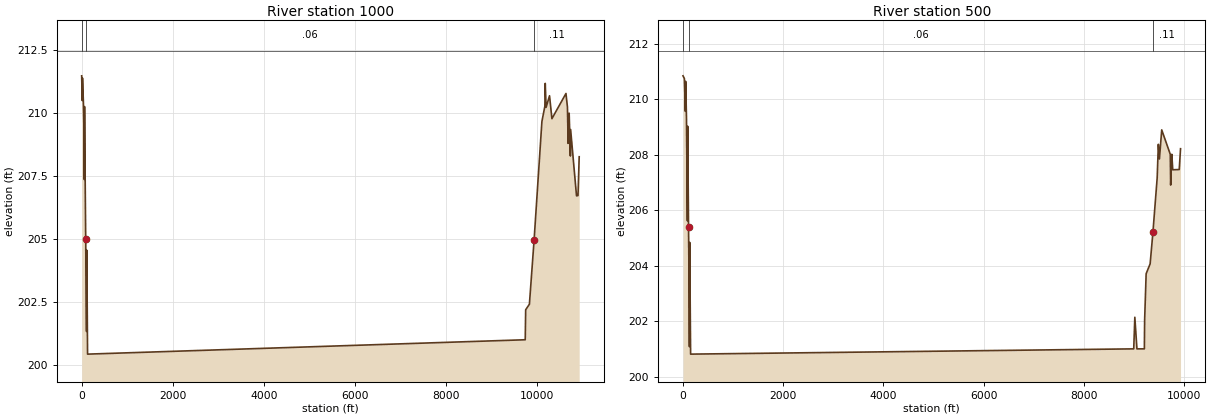
Type RM Length L Ch R = 1 ,1000    ,500,500,500
XS GIS Cut Line= 3
      3804404.61     10128088.81      3800086.11      10127185.6
      3793865.99     10129143.52
#Sta/Elev= 30
       0  211.47    12.7  210.49    17.8  211.38    37.6  210.45    47.8  209.57
    57.6  207.36    62.7  210.25    88.6     205   107.5  201.33   112.6  204.55
   129.5  200.43    9747     201  9756.8  202.19  9838.9  202.41  9941.3  204.94
 10113.6  209.66 10178.4  210.26 10186.6  211.17 10205.5  210.22   10281  210.68
 10333.4  209.77 10642.2  210.77 10674.6  210.23 10689.9  208.79 10712.2  209.99
 10739.3  208.29 10744.6  209.34 10874.1  206.71 10906.4  206.72 10932.9  208.26
#Mann= 3 , 0 , 0
       0     .11       0    88.6     .06       0  9941.3     .11       0
Bank Sta=88.6,9941.3
XS Rating Curve= 0 ,0
Exp/Cntr=0.3,0.1

Type RM Length L Ch R = 1 ,500     ,0,0,0
XS GIS Cut Line= 3
      3803524.67     10127609.01      3799997.84     10126693.45
      3794113.39     10128909.15
#Sta/Elev= 30
       0  210.85    27.7  210.75    47.3  209.57    52.5  210.65      69  209.36
    87.9  205.62    93.1  209.03   110.4  205.38   120.7  203.54   128.5  201.08
   133.6  204.84   151.7  200.81  8997.1     201  9019.2  202.14  9061.2     201
  9209.4     201  9214.7  202.03    9245  203.71  9324.9  204.07    9380   205.2
  9465.3  207.17  9488.6  208.38    9510  207.85    9556   208.9  9726.6  208.02
  9734.4  206.91  9756.8  208.02  9776.3  207.46  9905.4  207.47  9931.5  208.22
#Mann= 3 , 0 , 0
       0     .11       0   110.4     .06       0    9380     .11       0
Bank Sta=110.4,9380
XS Rating Curve= 0 ,0
Exp/Cntr=0.3,0.1

Chan Stop Cuts=-1
Use User Specified Reach Order=0
Composite Channel Slope=5