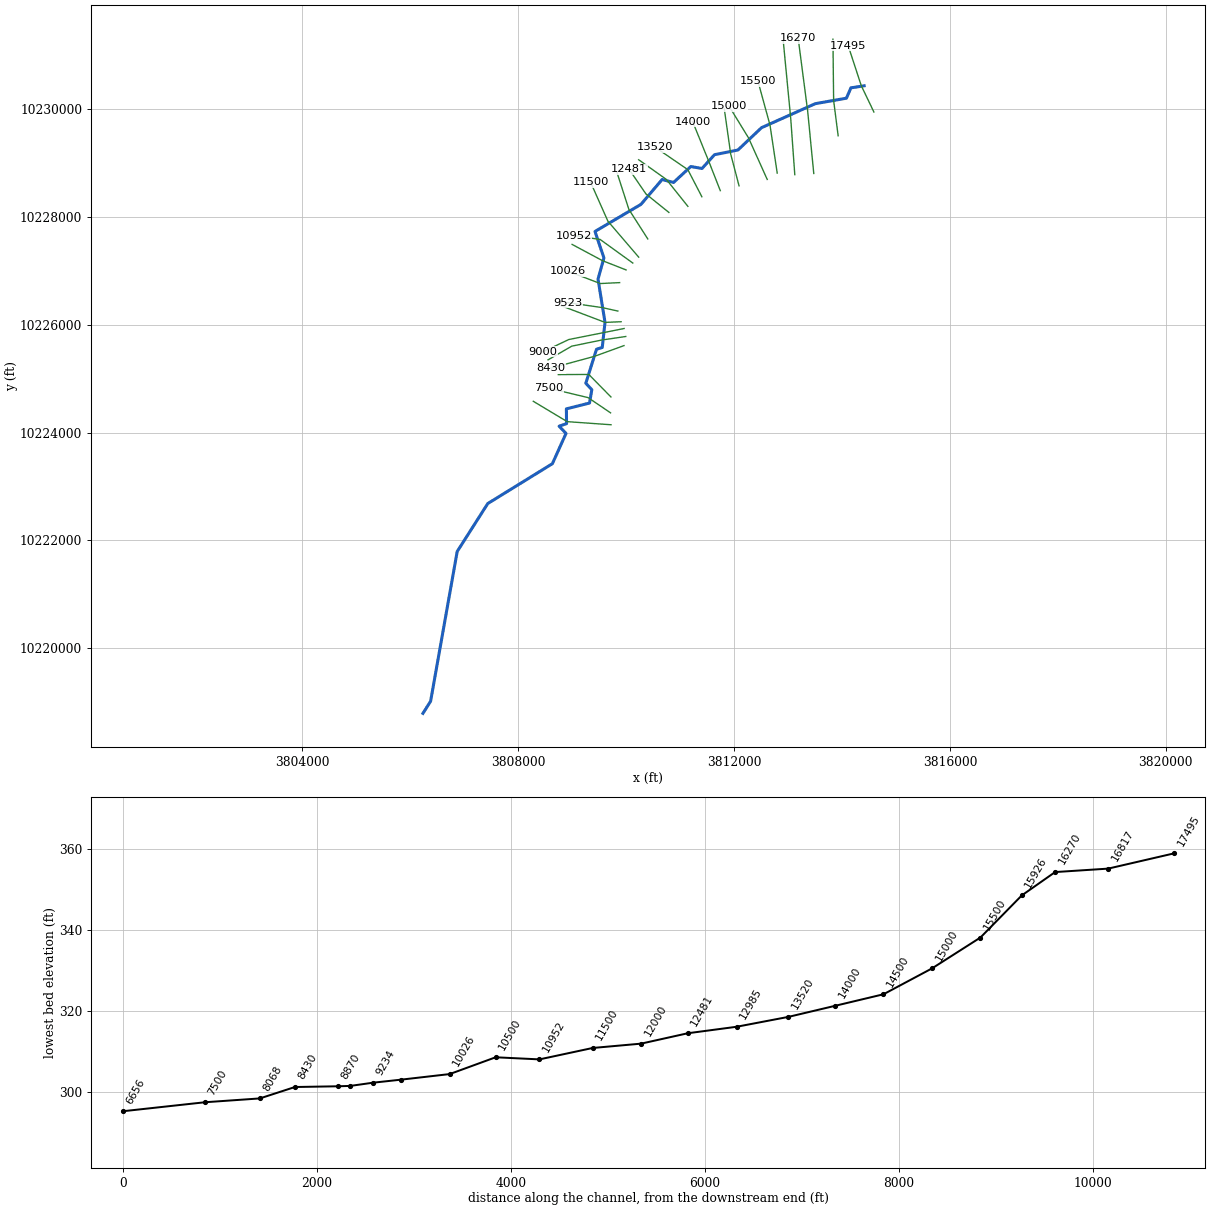
--- BIG CHINQUAPIN CREEK.prj (project) ---

Proj Title=BIG CHINQUAPIN CREEK Base Level Engineering
Current Plan=p01
Default Exp/Contr=0.3,0.1
English Units
Geom File=g01
Flow File=f01
Flow File=f02
Plan File=p01
Y Axis Title=Elevation
X Axis Title(PF)=Main Channel Distance
X Axis Title(XS)=Station
BEGIN DESCRIPTION:
BIG CHINQUAPIN CREEK
END DESCRIPTION:
DSS Export Rating Curves= 0
DSS Export Rating Curve Sorted= 0
DSS Export Volume Flow Curves= 0
DXF OffsetX= 0
DXF OffsetY= 0
DXF ScaleX= 1
DXF ScaleY= 10

--- BIG CHINQUAPIN CREEK.p01 (plan) ---

Plan Title=Multiple Run
Short Identifier=Multiple
Geom File=g01
Flow File=f01
Subcritical Flow
K Sum by GR= 0
Std Step Tol= 0.01
Critical Tol= 0.01
Num of Std Step Trials= 20
Max Error Tol= 0.3
Flow Tol Ratio= 0.001
Split Flow NTrial= 30
Split Flow Tol= 0.02
Split Flow Ratio= 0.02
Log Output Level= 0
Friction Slope Method= 1
Unsteady Friction Slope Method= 2
Unsteady Bridges Friction Slope Method= 1
Parabolic Critical Depth
Global Vel Dist=  1 , 1 , 1
Global Log Level= 0
CheckData=True
Encroach Param= -1, 0, 0, 0
BEGIN DESCRIPTION:
Multiple Run
END DESCRIPTION:

--- BIG CHINQUAPIN CREEK.f01 (steady flow) ---

Flow Title=Multiple
Program Version=4.10
Number of Profiles= 7
Profile Names=10-year,25-year,50-year,1pct_min,100-year,1pct_plu,500-year
River Rch & RM=BIG CHINQUAPIN C,Reach-1         ,17495
     410     542     720     316     954    2881    1730
River Rch & RM=BIG CHINQUAPIN C,Reach-1         ,16817
     916    1272    1750     793    2395    7233    4627
River Rch & RM=BIG CHINQUAPIN C,Reach-1         ,12000
    1212    1691    2332    1056    3190    9634    6170
River Rch & RM=BIG CHINQUAPIN C,Reach-1         ,5500
    1372    1919    2650    1201    3626   10950    7021
River Rch & RM=BIG CHINQUAPIN C,Reach-1         ,141
    2376    3412    4797    2208    6668   20137   13335
Boundary for River Rch & Prof#=BIG CHINQUAPIN C,Reach-1         , 1
Up Type= 0
Dn Type= 3
Dn Slope=0.005
Boundary for River Rch & Prof#=BIG CHINQUAPIN C,Reach-1         , 2
Up Type= 0
Dn Type= 3
Dn Slope=0.005
Boundary for River Rch & Prof#=BIG CHINQUAPIN C,Reach-1         , 3
Up Type= 0
Dn Type= 3
Dn Slope=0.005
Boundary for River Rch & Prof#=BIG CHINQUAPIN C,Reach-1         , 4
Up Type= 0
Dn Type= 3
Dn Slope=0.005
Boundary for River Rch & Prof#=BIG CHINQUAPIN C,Reach-1         , 5
Up Type= 0
Dn Type= 3
Dn Slope=0.005
Boundary for River Rch & Prof#=BIG CHINQUAPIN C,Reach-1         , 6
Up Type= 0
Dn Type= 3
Dn Slope=0.005
Boundary for River Rch & Prof#=BIG CHINQUAPIN C,Reach-1         , 7
Up Type= 0
Dn Type= 3
Dn Slope=0.005
DSS Import GetInterval= 0
DSS Import GetPeak= 0
DSS Import FillOption= 0

--- BIG CHINQUAPIN CREEK.f02 (steady flow) ---

Flow Title=Orig_BLE_Flow
Program Version=4.10
Number of Profiles= 7
Profile Names=10-year,25-year,50-year,1pct_min,100-year,1pct_plu,500-year
River Rch & RM=BIG CHINQUAPIN C,Reach-1         ,17495
     410     531     626     243     734    2218    1006
River Rch & RM=BIG CHINQUAPIN C,Reach-1         ,16817
     916    1247    1522     610    1842    5562    2690
River Rch & RM=BIG CHINQUAPIN C,Reach-1         ,12000
    1212    1658    2028     813    2454    7410    3587
River Rch & RM=BIG CHINQUAPIN C,Reach-1         ,5500
    1372    1881    2304     923    2789    8422    4082
River Rch & RM=BIG CHINQUAPIN C,Reach-1         ,141
    2376    3345    4171    1698    5129   15489    7753
Boundary for River Rch & Prof#=BIG CHINQUAPIN C,Reach-1         , 1
Up Type= 0
Dn Type= 3
Dn Slope=0.005
Boundary for River Rch & Prof#=BIG CHINQUAPIN C,Reach-1         , 2
Up Type= 0
Dn Type= 3
Dn Slope=0.005
Boundary for River Rch & Prof#=BIG CHINQUAPIN C,Reach-1         , 3
Up Type= 0
Dn Type= 3
Dn Slope=0.005
Boundary for River Rch & Prof#=BIG CHINQUAPIN C,Reach-1         , 4
Up Type= 0
Dn Type= 3
Dn Slope=0.005
Boundary for River Rch & Prof#=BIG CHINQUAPIN C,Reach-1         , 5
Up Type= 0
Dn Type= 3
Dn Slope=0.005
Boundary for River Rch & Prof#=BIG CHINQUAPIN C,Reach-1         , 6
Up Type= 0
Dn Type= 3
Dn Slope=0.005
Boundary for River Rch & Prof#=BIG CHINQUAPIN C,Reach-1         , 7
Up Type= 0
Dn Type= 3
Dn Slope=0.005
DSS Import GetInterval= 0
DSS Import GetPeak= 0
DSS Import FillOption= 0

--- BIG CHINQUAPIN CREEK.g01 (geometry) ---

Geom Title=Existing Conditions
Program Version=4.10

River Reach=BIG CHINQUAPIN C,Reach-1
Reach XY= 30
       3814409.9     10230431.58      3814164.32     10230393.31
      3814081.83     10230201.41      3813506.13     10230100.41
      3812508.96      10229655.1      3812070.86     10229240.52
      3811637.48     10229154.08      3811405.74     10228898.26
      3811197.44     10228934.25      3810878.19     10228638.95
      3810666.77     10228693.84      3810272.95     10228231.86
      3809422.61     10227730.88      3809587.75     10227239.65
      3809478.46     10226846.76      3809607.94     10226045.83
      3809556.94     10225579.39      3809450.25     10225546.37
       3809252.3      10224915.7       3809363.4     10224796.18
      3809321.32     10224548.73      3808892.07     10224440.99
      3808895.43     10224166.61       3808757.4     10224119.47
      3808885.33      10223984.8       3808632.6     10223423.66
      3807435.97     10222685.26      3806868.86     10221795.73
      3806376.09     10219019.32      3806234.06     10218793.89

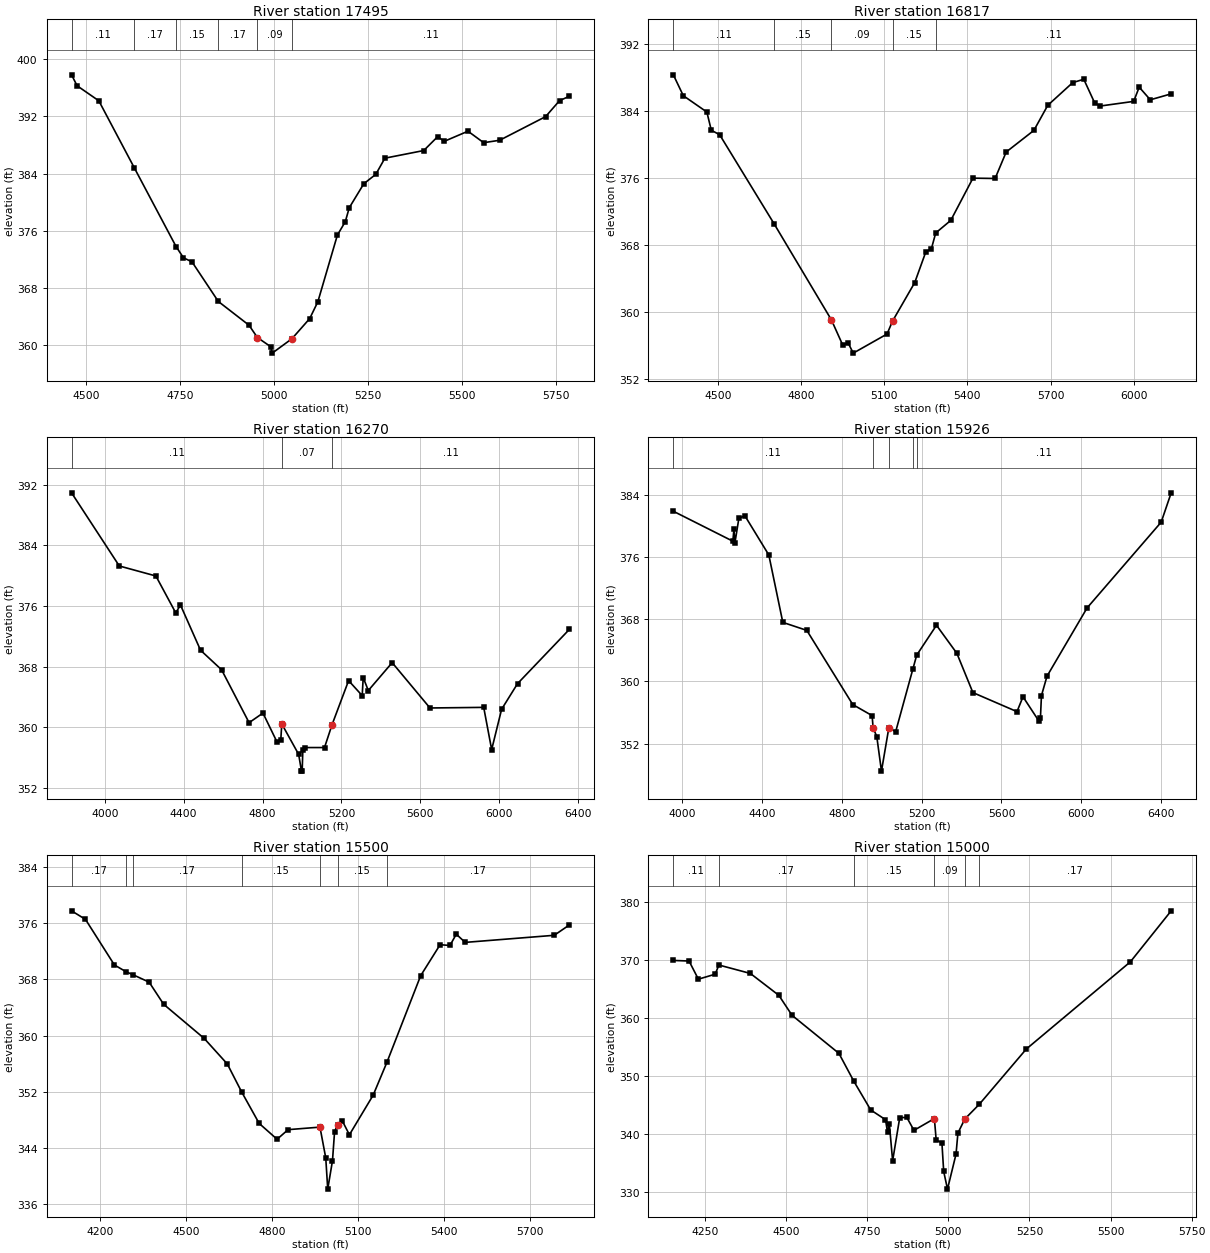
Type RM Length L Ch R = 1 ,17495   ,678,678,678
BEGIN DESCRIPTION:
BIG CHINQUAPIN CREEK 35.0
END DESCRIPTION:
XS GIS Cut Line= 3
      3814590.63     10229945.73       3814357.9     10230430.35
      3814113.48     10231177.27
#Sta/Elev= 30
  4462.4  397.83  4477.1   396.3  4534.9  394.19    4629  384.82  4740.2  373.77
  4759.9  372.19  4782.6  371.62  4852.6  366.07  4934.2  362.74  4956.4  361.02
  4991.9  359.73  4995.9  358.83  5048.3  360.85  5095.5  363.67  5117.2  366.03
  5169.1  375.37  5190.2  377.26  5200.7  379.21  5239.4  382.57  5271.3  383.89
  5295.4  386.15  5398.7  387.22  5435.8  389.17  5453.2  388.51  5516.3  389.93
    5558  388.32  5600.5  388.66  5722.6  391.97  5759.7  394.21  5785.9  394.83
#Mann= 6 ,-1 , 0
  4462.4     .11       0    4629     .17       0  4740.2     .15       0
  4852.6     .17       0  4956.4     .09       0  5048.3     .11       0
#XS Ineff= 2 , 0
       0    4924  363.07               0
Permanent Ineff=
       F       F
Bank Sta=4956.4,5048.3
XS Rating Curve= 0 ,0
Exp/Cntr=0.3,0.1

Type RM Length L Ch R = 1 ,16817   ,547,547,547
BEGIN DESCRIPTION:
BIG CHINQUAPIN CREEK 34.0
END DESCRIPTION:
XS GIS Cut Line= 3
      3813928.02     10229505.31      3813844.48     10230161.01
      3813831.79     10231296.44
#Sta/Elev= 30
    4339  388.29  4374.9   385.8  4459.9  383.85  4475.9  381.68  4506.1  381.14
  4702.8   370.5  4909.3  359.05  4949.7  356.08  4969.8  356.29  4988.2  355.08
  5110.1  357.36  5130.1  358.91  5210.1   363.5  5250.1  367.17  5270.1  367.53
  5285.8  369.42  5340.1  370.92  5420.1  375.96  5500.1  375.92  5540.1  379.08
  5640.1  381.66  5690.1  384.65  5780.1  387.36  5820.1  387.76  5860.1  384.89
  5880.1  384.57  6000.1  385.12  6020.1  386.82  6060.1  385.31  6135.5  386.02
#Mann= 5 ,-1 , 0
    4339     .11       0  4702.8     .15       0  4909.3     .09       0
  5130.1     .15       0  5285.8     .11       0
Bank Sta=4909.3,5130.1
XS Rating Curve= 0 ,0
Exp/Cntr=0.3,0.1

Type RM Length L Ch R = 1 ,16270   ,344,344,344
BEGIN DESCRIPTION:
BIG CHINQUAPIN CREEK 33.0
END DESCRIPTION:
XS GIS Cut Line= 3
      3813476.43     10228805.66      3813362.85     10229968.02
       3813187.7     10231311.65
#Sta/Elev= 30
  3832.1  390.94  4074.1  381.29  4259.5  379.97    4360  375.11  4384.1  376.14
  4485.7  370.18  4592.4   367.6  4731.8  360.62  4802.1  361.89  4872.4  358.12
  4892.4  358.33  4897.4  360.46    4983  356.44  4997.3  354.23  5000.8  354.23
  5004.1  356.97  5013.2  357.34    5114  357.34    5152  360.34  5236.1  366.17
    5305  364.19  5310.1  366.58  5335.9  364.86  5456.9  368.54  5648.5  362.56
  5920.8  362.64  5961.1  357.07  6011.5  362.39  6092.2  365.77    6355  372.93
#Mann= 3 , 0 , 0
  3832.1     .11       0  4897.4     .07       0    5152     .11       0
#XS Ineff= 2 , 0
       0  4897.4  360.46    5152       0  360.34
Permanent Ineff=
       F       F
Bank Sta=4897.4,5152
XS Rating Curve= 0 ,0
Exp/Cntr=0.3,0.1

Type RM Length L Ch R = 1 ,15926   ,426,426,426
BEGIN DESCRIPTION:
BIG CHINQUAPIN CREEK 32.0
END DESCRIPTION:
XS GIS Cut Line= 3
      3813124.78     10228783.47      3813049.46     10229826.45
      3812910.08     10231270.94
#Sta/Elev= 30
  3954.3  381.89  4252.7  378.04  4258.2  379.58  4263.2  377.85  4282.8  380.97
  4312.8  381.32  4433.1  376.27  4503.3   367.6  4623.6  366.57  4854.2  357.03
  4951.2  355.61  4956.2  354.04  4974.6  352.92  4998.1  348.47  5034.8     354
  5069.4  353.55  5155.5  361.59  5174.9  363.39    5274  367.23  5376.3  363.62
  5456.7  358.57  5677.8  356.12  5707.9  358.03  5788.3  354.89  5795.5  355.36
  5800.5  358.18  5828.4  360.68  6029.4  369.46  6401.1  380.49  6451.2  384.26
#Mann= 5 ,-1 , 0
  3954.3     .11       0  4956.2     .07       0  5034.8     .11       0
  5155.5    .125       0  5174.9     .11       0
#XS Ineff= 2 , 0
       0                    5274       0  367.23
Permanent Ineff=
       F       F
Bank Sta=4956.2,5034.8
XS Rating Curve= 0 ,0
Exp/Cntr=0.3,0.1

Type RM Length L Ch R = 1 ,15500   ,500,500,500
BEGIN DESCRIPTION:
BIG CHINQUAPIN CREEK 31.0
END DESCRIPTION:
XS GIS Cut Line= 3
      3812799.04     10228813.04       3812665.3     10229703.15
      3812443.67     10230512.14
#Sta/Elev= 30
  4099.9  377.78  4148.5  376.56  4249.6  370.06  4290.4  369.09  4314.4  368.67
  4370.9  367.61  4421.5  364.46  4563.1  359.59    4644  355.94  4693.7  351.98
  4755.2  347.47  4817.8  345.21  4856.3  346.58  4967.6  346.94  4987.8  342.55
  4994.7   338.1  5011.3  342.15  5018.6  346.29    5029  347.29  5045.8  347.82
  5070.4  345.85  5153.4   351.5  5201.3  356.17  5319.3  368.53  5387.2  372.95
  5421.7  372.84  5443.7  374.45  5474.8  373.28  5785.8  374.29  5838.8  375.77
#Mann= 7 ,-1 , 0
  4099.9     .17       0  4290.4     .11       0  4314.4     .17       0
  4693.7     .15       0  4967.6     .09       0    5029     .15       0
  5201.3     .17       0
#XS Ineff= 2 , 0
       0                  5045.8       0  347.82
Permanent Ineff=
       F       F
Bank Sta=4967.6,5029
XS Rating Curve= 0 ,0
Exp/Cntr=0.3,0.1

Type RM Length L Ch R = 1 ,15000   ,500,500,500
BEGIN DESCRIPTION:
BIG CHINQUAPIN CREEK 30.0
END DESCRIPTION:
XS GIS Cut Line= 3
      3812613.94     10228694.66      3812266.32     10229467.69
      3811906.97     10230053.09
#Sta/Elev= 30
  4152.4  369.89  4200.8  369.79  4229.5  366.66  4281.3  367.52  4292.8   369.1
  4389.7  367.65  4477.5  363.88  4518.3  360.43  4662.7  353.88  4708.7  349.07
  4760.8  344.12  4806.3  342.45  4812.6  340.27  4818.1  341.75  4828.3  335.36
  4850.2  342.81  4872.1  342.83  4894.1  340.61    4957  342.64  4962.5  338.95
  4980.2  338.45  4985.7  333.52  4997.4  330.48  5023.7  336.51  5029.5  340.14
  5050.9  342.57  5095.6  345.11  5240.3  354.62  5561.1  369.65  5686.9  378.44
#Mann= 6 ,-1 , 0
  4152.4     .11       0  4292.8     .17       0  4708.7     .15       0
    4957     .09       0  5050.9     .15       0  5095.6     .17       0
#XS Ineff= 2 , 0
       0    4957  342.64               0
Permanent Ineff=
       F       F
Bank Sta=4957,5050.9
XS Rating Curve= 0 ,0
Exp/Cntr=0.3,0.1

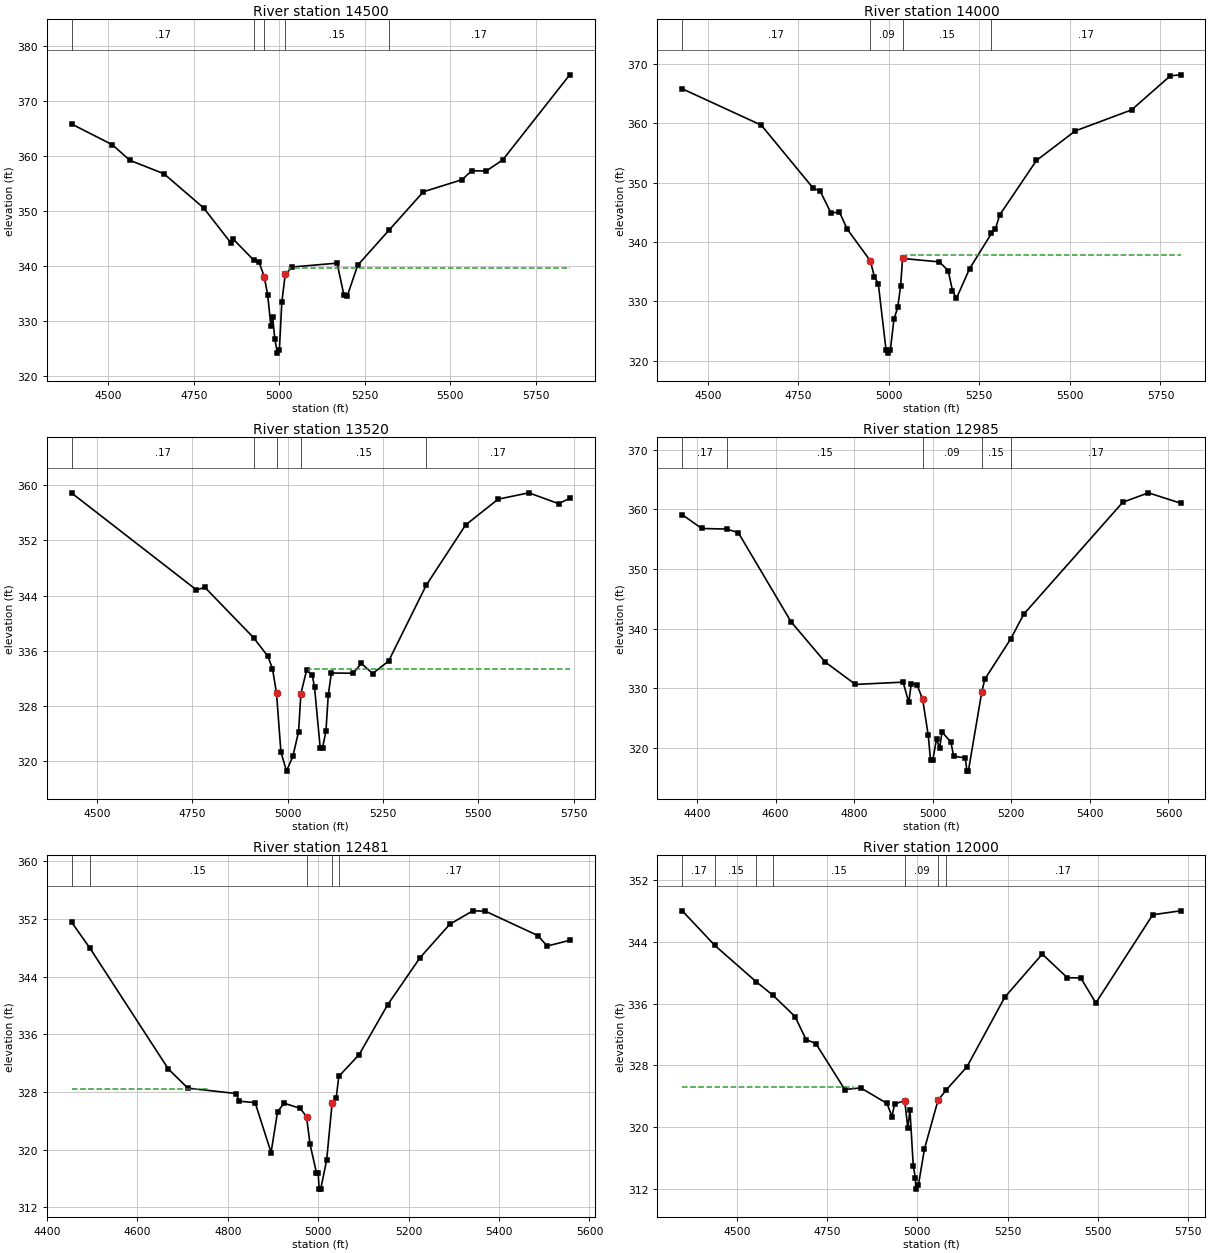
Type RM Length L Ch R = 1 ,14500   ,500,500,500
BEGIN DESCRIPTION:
BIG CHINQUAPIN CREEK 29.0
END DESCRIPTION:
XS GIS Cut Line= 3
      3812092.03     10228576.18      3811937.55     10229164.02
      3811818.11     10230004.98
#Sta/Elev= 30
  4392.2  365.82  4511.6  362.04  4562.7  359.21  4662.7  356.75  4778.5  350.54
  4859.2   344.1  4864.4   344.9  4924.6  341.07  4939.9  340.78  4955.6  338.05
  4965.9  334.69  4975.1   329.1  4980.3  330.71  4986.6  326.76  4994.1  324.11
    5000  324.61  5007.1  333.34  5017.2  338.44    5038  339.79  5168.7  340.49
  5188.9  334.68    5199  334.59  5229.3  340.12  5320.7  346.49  5421.2  353.48
  5534.3  355.68  5562.6  357.31  5605.2  357.26  5653.5  359.29  5849.4  374.77
#Mann= 5 ,-1 , 0
  4392.2     .17       0  4924.6     .15       0  4955.6     .09       0
  5017.2     .15       0  5320.7     .17       0
#XS Ineff= 2 , 0
       0                  5027.3       0  339.64
Permanent Ineff=
       F       F
Bank Sta=4955.6,5017.2
XS Rating Curve= 0 ,0
Exp/Cntr=0.3,0.1

Type RM Length L Ch R = 1 ,14000   ,480,480,480
BEGIN DESCRIPTION:
BIG CHINQUAPIN CREEK 28.0
END DESCRIPTION:
XS GIS Cut Line= 3
      3811744.08     10228487.34      3811536.06     10229018.14
      3811233.24     10229764.44
#Sta/Elev= 30
  4429.9  365.79  4647.9  359.67  4791.6  349.02  4809.8  348.63  4840.5  344.86
  4863.5  345.05    4885  342.16    4949  336.81  4960.2  334.12  4970.9  332.97
  4992.4  321.77  4997.1  321.26  5004.3  321.76    5014  326.93  5024.7     329
  5032.6   332.6    5038  337.21  5139.8  336.63  5163.9  335.15  5175.8  331.79
  5186.6  330.47  5222.9  335.48  5283.4  341.42  5294.5   342.2  5305.9  344.52
  5407.7  353.72  5514.8   358.7  5670.2  362.24  5777.3  367.98  5805.4  368.15
#Mann= 4 ,-1 , 0
  4429.9     .17       0    4949     .09       0    5038     .15       0
  5283.4     .17       0
#XS Ineff= 2 , 0
       0                  5046.3       0  337.77
Permanent Ineff=
       F       F
Bank Sta=4949,5038
XS Rating Curve= 0 ,0
Exp/Cntr=0.3,0.1

Type RM Length L Ch R = 1 ,13520   ,535,535,535
BEGIN DESCRIPTION:
BIG CHINQUAPIN CREEK 27.0
END DESCRIPTION:
XS GIS Cut Line= 3
      3811402.75      10228374.2      3811142.23     10228877.01
      3810532.79     10229295.52
#Sta/Elev= 30
  4433.7  358.89    4761  344.83  4783.1  345.19    4911  337.88  4948.3  335.19
  4960.2  333.41  4970.8  329.88  4982.3  321.34    4997  318.54  5013.7   320.7
  5028.6  324.25  5034.7  329.79  5049.5  333.14  5064.4  332.51  5070.5  330.69
  5085.4  321.85  5091.5  321.95  5100.3   324.3  5106.4  329.54  5114.5  332.77
    5172  332.74    5193  334.17  5222.8   332.7  5264.7  334.51  5363.2  345.51
  5466.3  354.24  5551.6  357.99  5632.2  358.91    5710  357.34  5739.3  358.11
#Mann= 5 ,-1 , 0
  4433.7     .17       0    4911     .15       0  4970.8     .09       0
  5034.7     .15       0  5363.2     .17       0
#XS Ineff= 2 , 0
       0                  5055.6       0  333.33
Permanent Ineff=
       F       F
Bank Sta=4970.8,5034.7
XS Rating Curve= 0 ,0
Exp/Cntr=0.3,0.1

Type RM Length L Ch R = 1 ,12985   ,504,504,504
BEGIN DESCRIPTION:
BIG CHINQUAPIN CREEK 26.0
END DESCRIPTION:
XS GIS Cut Line= 3
        3811143.     10228196.67      3810745.74     10228694.74
      3810231.94     10229060.35
#Sta/Elev= 30
  4362.9  359.09  4412.3  356.79  4475.8  356.69  4505.2   356.1  4639.7  341.13
  4726.1  334.41  4803.4  330.64  4924.7  331.02  4939.1  327.62  4945.5  330.78
  4959.9  330.58  4974.3  328.18  4988.7  322.09  4994.5   317.9    5000   317.9
  5009.7  321.47  5017.7  320.01  5023.8  322.67  5046.5  320.94  5053.3  318.59
  5082.9  318.32  5087.2   316.1  5090.7   316.1  5124.7   329.3  5132.4   331.5
  5198.8   338.3  5231.6  342.41  5483.7  361.19  5548.9  362.77  5630.6  361.04
#Mann= 5 ,-1 , 0
  4362.9     .17       0  4475.8     .15       0  4974.3     .09       0
  5124.7     .15       0  5198.8     .17       0
#XS Ineff= 2 , 0
       0  4945.5  330.78               0
Permanent Ineff=
       F       F
Bank Sta=4974.3,5124.7
XS Rating Curve= 0 ,0
Exp/Cntr=0.3,0.1

Type RM Length L Ch R = 1 ,12481   ,481,481,481
BEGIN DESCRIPTION:
BIG CHINQUAPIN CREEK 25.0
END DESCRIPTION:
XS GIS Cut Line= 3
      3810791.33      10228083.3       3810366.8     10228425.54
       3810053.5     10228885.23
#Sta/Elev= 30
  4454.7  351.57  4495.6  347.93  4668.7  331.18  4711.8  328.52  4818.8  327.77
  4825.4  326.71  4860.6  326.51  4895.9  319.58  4910.2  325.25  4924.6  326.43
  4960.1  325.72  4974.2  324.57  4982.1  320.71  4996.1   316.8    5000   316.8
  5002.1   314.5  5005.6   314.5  5018.8  318.55  5030.9  326.49  5039.7  327.12
  5045.7  330.16  5090.6  333.18  5153.5  340.08  5225.3  346.64  5291.1  351.28
  5341.9  353.14  5369.7  353.09  5485.6  349.71  5506.5  348.25  5556.3  349.05
#Mann= 5 ,-1 , 0
  4454.7     .17       0  4495.6     .15       0  4974.2     .09       0
  5030.9     .15       0  5045.7     .17       0
#XS Ineff= 2 , 0
       0  4754.6  328.43               0
Permanent Ineff=
       F       F
Bank Sta=4974.2,5030.9
XS Rating Curve= 0 ,0
Exp/Cntr=0.3,0.1

Type RM Length L Ch R = 1 ,12000   ,500,500,500
BEGIN DESCRIPTION:
BIG CHINQUAPIN CREEK 24.0
END DESCRIPTION:
XS GIS Cut Line= 3
      3810400.25     10227591.95      3810050.04     10228140.25
      3809826.73     10228834.31
#Sta/Elev= 30
  4349.4  348.03  4439.4  343.55  4553.2  338.87    4601  337.06  4661.6  334.32
    4692  331.34  4719.1  330.82  4799.3  324.86  4843.5  325.07  4916.2  323.06
  4929.8  321.36  4937.4  322.99  4965.4  323.41  4973.8  319.87  4979.7  322.23
    4989  314.92  4994.9  313.42  4995.8  311.94  5003.1  312.44    5020  317.16
  5057.4  323.44  5079.3  324.76  5137.4  327.79  5242.5  336.84  5346.1  342.43
  5415.5  339.37  5452.9  339.33  5494.6  336.09  5652.2  347.53  5729.1  348.04
#Mann= 7 ,-1 , 0
  4349.4     .17       0  4439.4     .15       0  4553.2     .17       0
    4601     .15       0  4965.4     .09       0  5057.4     .15       0
  5079.3     .17       0
#XS Ineff= 2 , 0
       0  4822.3  325.17               0
Permanent Ineff=
       F       F
Bank Sta=4965.4,5057.4
XS Rating Curve= 0 ,0
Exp/Cntr=0.3,0.1

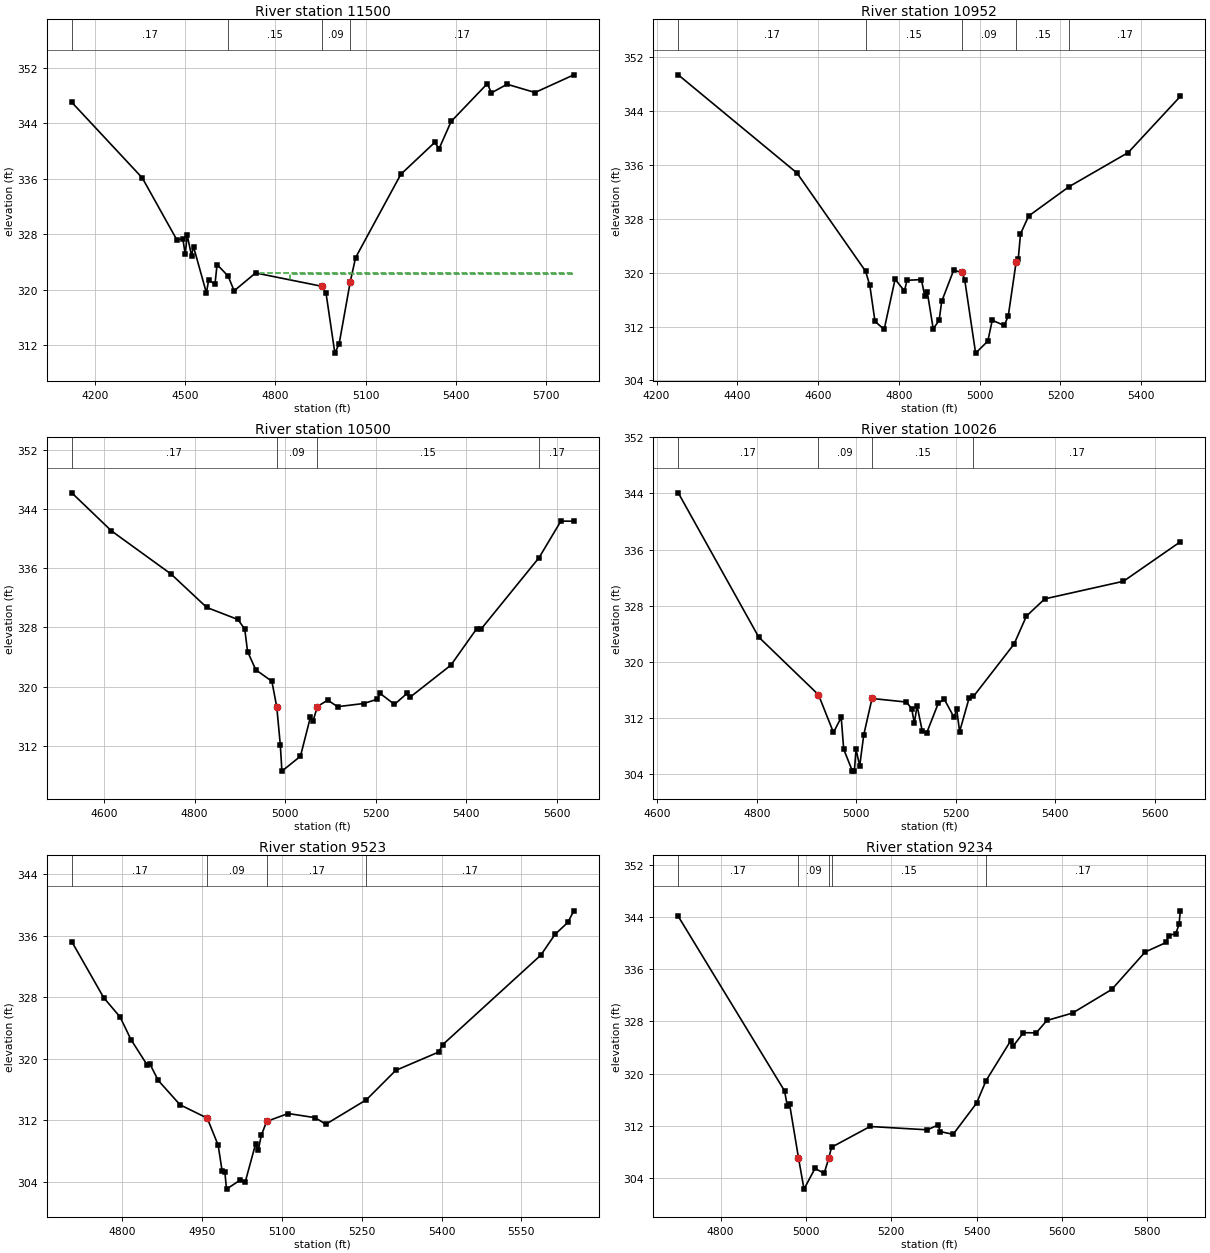
Type RM Length L Ch R = 1 ,11500   ,548,548,548
BEGIN DESCRIPTION:
BIG CHINQUAPIN CREEK 23.0
END DESCRIPTION:
XS GIS Cut Line= 3
      3810231.98     10227254.26      3809661.86     10227920.39
      3809340.34     10228643.65
#Sta/Elev= 30
  4123.2  347.03  4357.5  336.13  4471.7  327.25  4492.5  327.29  4500.2   325.1
  4506.8  327.87  4521.1  324.94  4527.7  326.22  4570.5  319.56  4578.2  321.42
    4599  320.79    4606  323.64  4642.8  321.97  4662.7  319.85    4734  322.43
  4953.6  320.51  4967.9  319.56  4997.4  310.87  5011.7  312.23  5048.4  321.12
  5066.2  324.63  5216.6  336.65  5329.1  341.24  5343.8  340.35  5383.8  344.27
  5504.1  349.72  5517.5  348.39  5569.8  349.63  5662.5  348.44  5791.5  350.99
#Mann= 4 ,-1 , 0
  4123.2     .17       0  4642.8     .15       0  4953.6     .09       0
  5048.4     .17       0
#XS Ineff= 2 ,-1
  4748.3  4541.9  322.46  4847.1  4783.4  322.31
Permanent Ineff=
       F       F
Bank Sta=4953.6,5048.4
XS Rating Curve= 0 ,0
Exp/Cntr=0.3,0.1

Type RM Length L Ch R = 1 ,10952   ,452,452,452
BEGIN DESCRIPTION:
BIG CHINQUAPIN CREEK 22.0
END DESCRIPTION:
XS GIS Cut Line= 3
      3810122.54     10227144.99      3809517.77      10227582.1
       3809026.6     10227655.29
#Sta/Elev= 30
  4253.8  349.34  4547.7  334.78  4717.5  320.21    4728  318.11  4740.8  312.78
  4763.5  311.57  4790.6  319.02  4813.8  317.28    4820  318.86  4855.6  318.97
  4864.1  316.52  4870.3   317.1    4885  311.65  4899.7  312.95  4905.9  315.72
  4935.3  320.32  4956.1  320.07  4962.9  318.95  4989.9  308.06  5020.1  309.84
  5031.1  312.94  5060.6  312.16  5070.7  313.56  5090.3   321.6  5095.4  321.97
    5101  325.75  5121.2   328.4  5221.2  332.75  5367.6  337.81  5496.6  346.14
#Mann= 5 ,-1 , 0
  4253.8     .17       0  4717.5     .15       0  4956.1     .09       0
  5090.3     .15       0  5221.2     .17       0
#XS Ineff= 2 , 0
       0  4935.3  320.32               0
Permanent Ineff=
       F       F
Bank Sta=4956.1,5090.3
XS Rating Curve= 0 ,0
Exp/Cntr=0.3,0.1

Type RM Length L Ch R = 1 ,10500   ,474,474,474
BEGIN DESCRIPTION:
BIG CHINQUAPIN CREEK 21.0
END DESCRIPTION:
XS GIS Cut Line= 3
      3809999.31     10227016.82       3809560.7     10227189.02
      3808998.55     10227490.08
#Sta/Elev= 30
  4528.8   346.2  4616.3  341.06  4748.1  335.22  4826.8  330.71  4895.6  329.08
  4910.8  327.79  4917.1  324.74  4935.2  322.28  4970.8  320.72  4981.6  317.22
  4989.4  312.12  4992.9  308.58  5033.9  310.59  5055.8  315.87  5061.5  315.32
  5071.3  317.31    5094  318.18  5115.9  317.29  5173.4  317.72  5203.7   318.3
  5209.3  319.11  5241.5   317.6  5269.5   319.1  5275.5  318.55  5366.2  322.91
    5423  327.82  5433.6  327.84  5560.9  337.44  5609.1  342.38  5637.7  342.36
#Mann= 4 ,-1 , 0
  4528.8     .17       0  4981.6     .09       0  5071.3     .15       0
  5560.9     .17       0
#XS Ineff= 2 ,-1
    5094  5209.3  318.18  5209.3  5291.4  319.11
Permanent Ineff=
       F       F
Bank Sta=4981.6,5071.3
XS Rating Curve= 0 ,0
Exp/Cntr=0.3,0.1

Type RM Length L Ch R = 1 ,10026   ,503,503,503
BEGIN DESCRIPTION:
BIG CHINQUAPIN CREEK 20.0
END DESCRIPTION:
XS GIS Cut Line= 3
      3809879.35     10226781.84      3809522.07     10226764.65
      3808913.14     10226995.45
#Sta/Elev= 30
  4642.3  344.09    4804  323.54  4924.1  315.32  4954.2  309.95  4969.8  312.09
  4974.8  307.56  4992.3  304.44  4996.2  304.44  4999.6  307.55  5006.9  305.17
  5015.2  309.65  5031.7  314.79  5100.8  314.28  5111.4  313.33  5116.8  311.28
  5122.2  313.76  5132.8  310.11  5141.6  309.89  5164.9  314.12  5177.1  314.66
  5196.6  312.09  5201.9  313.28  5207.7  310.06  5226.7  314.83  5235.5  315.08
  5317.2  322.55    5342  326.53  5378.8  328.98    5537  331.49  5651.2  337.11
#Mann= 4 ,-1 , 0
  4642.3     .17       0  4924.1     .09       0  5031.7     .15       0
  5235.5     .17       0
Bank Sta=4924.1,5031.7
XS Rating Curve= 0 ,0
Exp/Cntr=0.3,0.1

Type RM Length L Ch R = 1 ,9523    ,289,289,289
BEGIN DESCRIPTION:
BIG CHINQUAPIN CREEK 19.0
END DESCRIPTION:
XS GIS Cut Line= 3
      3809846.47     10226254.36      3809558.36     10226318.23
      3808916.53     10226410.97
#Sta/Elev= 30
  4704.9  335.21  4764.9  327.93  4795.7  325.42  4816.2  322.48  4846.6  319.19
  4851.7  319.32  4867.4  317.18  4908.3  314.02  4959.5  312.28    4980  308.77
  4987.6  305.35  4992.7  305.23  4995.7  303.06  5020.7   304.2  5030.8  303.96
  5050.4  308.94  5055.5  308.15  5061.1  310.05  5071.2  311.86  5111.7  312.88
  5162.2  312.34  5182.4  311.49  5258.6  314.67  5313.7  318.48  5394.6  320.87
    5402  321.82  5586.5  333.46    5613  336.14  5637.1   337.7  5648.5  339.21
#Mann= 4 ,-1 , 0
  4704.9     .17       0  4959.5     .09       0  5071.2     .17       0
  5258.6     .17       0
Bank Sta=4959.5,5071.2
XS Rating Curve= 0 ,0
Exp/Cntr=0.3,0.1

Type RM Length L Ch R = 1 ,9234    ,234,234,234
BEGIN DESCRIPTION:
Mapping XS e0778099
END DESCRIPTION:
XS GIS Cut Line= 3
      3809906.73      10226056.4      3809607.87      10226044.4
      3808787.84      10226356.2
#Sta/Elev= 30
  4700.9  344.08    4950  317.35  4956.7  314.99  4961.7  315.36 4982.64   307.1
  4995.6  302.31  5021.4  305.49  5042.8  304.72  5053.5  307.04  5060.1  308.72
  5150.3   311.9  5284.8  311.39  5309.6  312.13  5314.9  311.12    5345   310.7
  5399.9  315.47  5422.2  318.93  5479.6     325  5484.9  324.15  5509.7  326.26
  5539.8  326.24  5564.6  328.13  5624.8  329.27  5716.8  332.89  5794.8  338.61
  5844.3  340.08  5849.7  341.12  5866.6  341.43  5874.4  342.84  5877.3  344.92
#Mann= 5 ,-1 , 0
  4700.9     .17       0 4982.64     .09       0  5053.5     .17       0
  5060.1     .15       0  5422.2     .17       0
#XS Ineff= 2 , 0
       0                  5150.3       0   311.9
Permanent Ineff=
       F       F
Bank Sta=4982.64,5053.5
XS Rating Curve= 0 ,0
Exp/Cntr=0.3,0.1

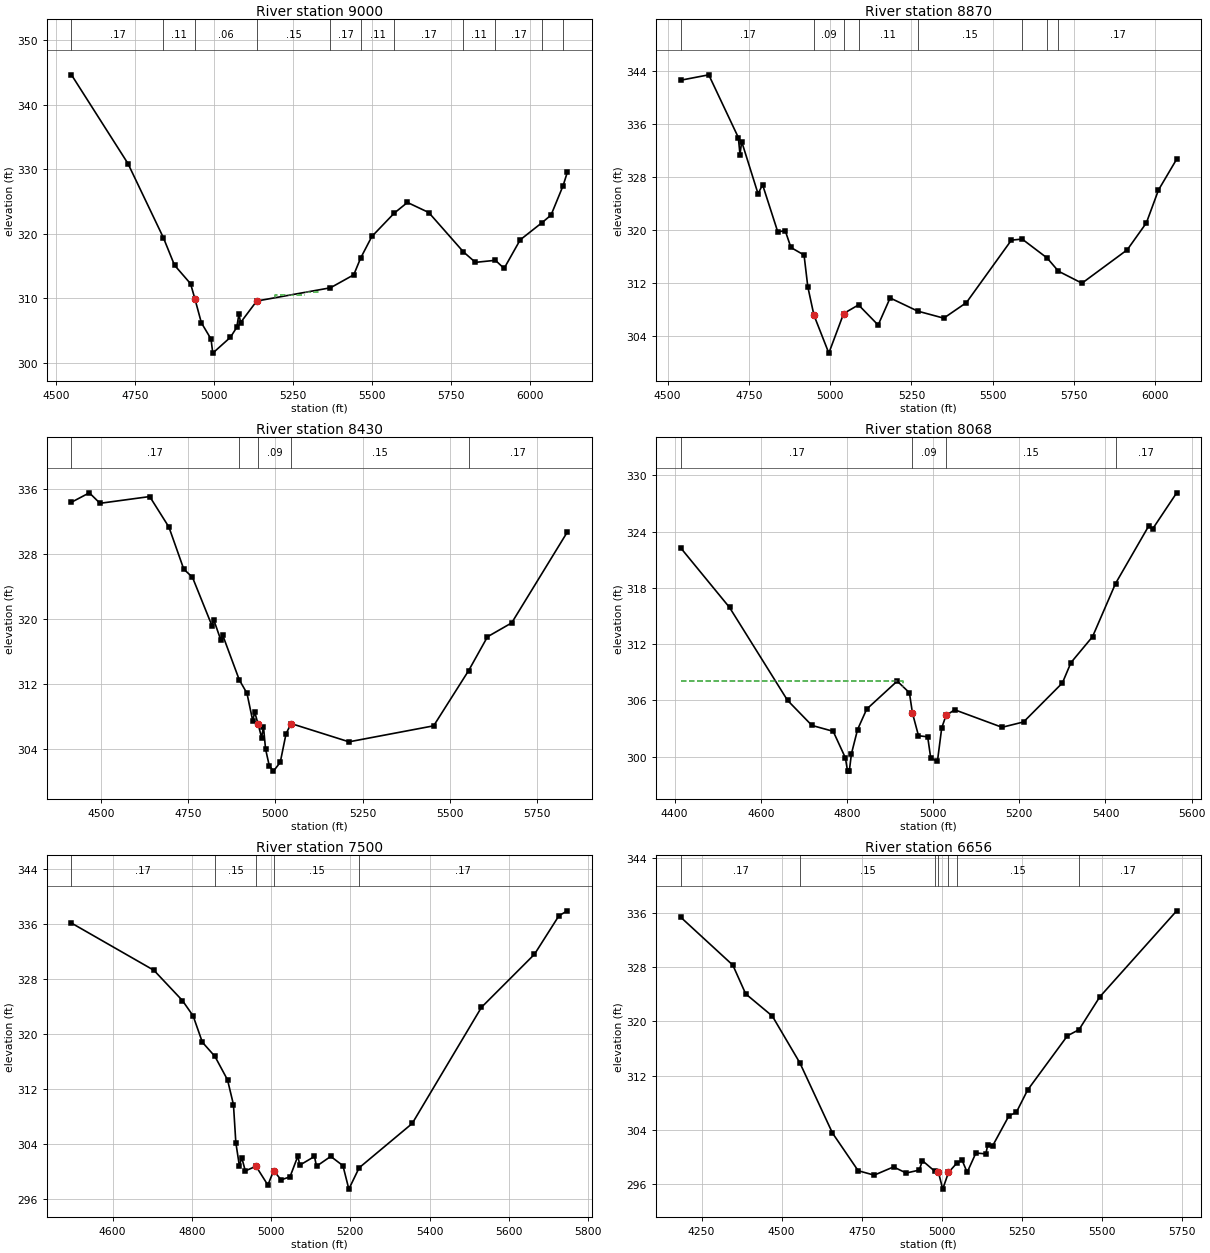
Type RM Length L Ch R = 1 ,9000    ,130,130,130
BEGIN DESCRIPTION:
BIG CHINQUAPIN CREEK 18.0
END DESCRIPTION:
XS GIS Cut Line= 4
       3809961.5     10225930.64      3809518.14     10225841.68
      3808937.74     10225726.87      3808461.36     10225500.44
#Sta/Elev= 30
  4547.8  344.63  4726.8  330.89  4839.2  319.39  4874.4  315.14  4925.3  312.27
  4939.1  309.91  4959.5  306.22  4990.1   303.7  4995.6  301.52  5051.3  303.96
  5071.7  305.51  5078.6  307.61  5083.7  306.25  5134.9  309.59  5368.5  311.64
  5442.4  313.65  5464.2  316.24  5499.8  319.59  5570.8  323.21  5612.5  324.86
  5680.1   323.3    5790   317.2    5828  315.58  5891.3   315.9  5918.9  314.64
  5969.9  319.07    6039  321.73  6067.6   322.9    6106  327.48  6119.1  329.52
#Mann= 11 ,-1 , 0
  4547.8     .17       0  4839.2     .11       0  4939.1     .06       0
  5134.9     .15       0  5368.5     .17       0  5464.2     .11       0
  5570.8     .17       0    5790     .11       0  5891.3     .17       0
    6039     .11       0    6106     .17       0
#XS Ineff= 2 ,-1
    5194  5288.7  310.48  5288.7  5339.9  311.01
Permanent Ineff=
       F       F
Bank Sta=4939.1,5134.9
XS Rating Curve= 0 ,0
Exp/Cntr=0.3,0.1

Type RM Length L Ch R = 1 ,8870    ,440,440,440
BEGIN DESCRIPTION:
BIG CHINQUAPIN CREEK 17.0
END DESCRIPTION:
XS GIS Cut Line= 4
      3809992.71     10225782.74      3809538.37     10225715.44
      3808991.97     10225603.63      3808552.24     10225349.31
#Sta/Elev= 30
  4540.7  342.64  4626.5  343.45  4717.5  333.98  4722.6   331.4  4727.7  333.38
  4778.1  325.49  4792.1  326.85  4838.8  319.73  4861.6  319.93  4879.2  317.38
  4919.6  316.24  4931.1  311.46    4950  307.16  4995.8  301.43  5041.4  307.41
  5087.1  308.71  5147.5  305.67  5184.3  309.76  5269.3  307.77  5349.3  306.71
    5419  309.06  5557.3  318.49  5590.4  318.65  5667.3  315.79    5702   313.8
  5774.4  311.99  5913.6  317.03  5972.4  321.09  6009.7  326.06  6065.7  330.72
#Mann= 8 ,-1 , 0
  4540.7     .17       0    4950     .09       0  5041.4     .17       0
  5087.1     .11       0  5269.3     .15       0  5590.4     .11       0
  5667.3     .15       0    5702     .17       0
Bank Sta=4950,5041.4
XS Rating Curve= 0 ,0
Exp/Cntr=0.3,0.1

Type RM Length L Ch R = 1 ,8430    ,362,362,362
BEGIN DESCRIPTION:
Mapping XS 778c54ae
END DESCRIPTION:
XS GIS Cut Line= 3
      3809960.15     10225613.87      3809412.64     10225414.65
      3808604.49     10225195.73
#Sta/Elev= 30
  4416.2  334.37  4467.4  335.53    4498  334.24  4640.3  335.07  4695.3  331.31
  4737.9  326.12  4762.6  325.14  4818.5  319.17  4823.8  319.88  4843.7  317.42
    4849  318.04  4896.7   312.5  4918.8  310.84  4935.5  307.42  4940.8  308.55
  4950.7  307.04  4960.7  305.38  4966.1  306.72    4972  303.98  4982.6  301.93
  4994.6  301.25  5014.1  302.33  5030.7  305.85  5045.2  307.11    5211  304.86
  5453.4  306.83  5553.7  313.64  5607.6   317.8  5676.9  319.51  5836.1  330.69
#Mann= 5 ,-1 , 0
  4416.2     .17       0  4896.7     .15       0  4950.7     .09       0
  5045.2     .15       0  5553.7     .17       0
#XS Ineff= 2 , 0
       0  4940.8  308.55               0
Permanent Ineff=
       F       F
Bank Sta=4950.7,5045.2
XS Rating Curve= 0 ,0
Exp/Cntr=0.3,0.1

Type RM Length L Ch R = 1 ,8068    ,568,568,568
BEGIN DESCRIPTION:
BIG CHINQUAPIN CREEK 16.0
END DESCRIPTION:
XS GIS Cut Line= 3
      3809717.82      10224661.1      3809307.85     10225078.98
      3808742.56     10225076.15
#Sta/Elev= 30
  4414.6  322.25  4527.6  315.91  4662.1     306  4718.7  303.32  4768.1  302.69
  4796.4  299.86  4801.5  298.44  4805.5  298.44  4810.5   300.3  4824.7  302.88
  4845.9  305.06  4916.7  308.05    4945  306.81    4952  304.65  4966.1  302.22
  4987.4   302.1  4994.4  299.87    5010  299.47    5020  303.06    5030  304.38
    5050  304.99    5160  303.12    5210  303.69    5300  307.85    5320  310.03
    5370  312.79  5423.4  318.47    5500  324.58    5510  324.33  5565.3  328.15
#Mann= 4 ,-1 , 0
  4414.6     .17       0    4952     .09       0    5030     .15       0
  5423.4     .17       0
#XS Ineff= 2 , 0
       0  4930.8  308.06               0
Permanent Ineff=
       F       F
Bank Sta=4952,5030
XS Rating Curve= 0 ,0
Exp/Cntr=0.3,0.1

Type RM Length L Ch R = 1 ,7500    ,844,844,844
BEGIN DESCRIPTION:
BIG CHINQUAPIN CREEK 15.0
END DESCRIPTION:
XS GIS Cut Line= 3
      3809711.24     10224366.73      3809294.22      10224649.4
      3808567.33     10224823.29
#Sta/Elev= 30
  4496.2  336.19  4704.3  329.32  4776.2  324.92  4803.2  322.69  4826.5  318.86
  4858.3  316.79    4890  313.39    4905  309.78    4911  304.26  4919.9  300.89
    4926  302.05  4934.9  300.14  4961.9  300.82  4991.8  298.08  5006.5  300.17
  5025.3  298.84  5047.7  299.28  5067.4  302.27  5072.5  300.98  5109.4  302.24
  5114.6  300.82  5150.5  302.25  5181.3   300.9  5196.2  297.49  5222.1  300.59
  5356.1  307.04  5530.9  323.94  5664.6  331.65  5726.3  337.25  5747.4  337.97
#Mann= 5 ,-1 , 0
  4496.2     .17       0  4858.3     .15       0  4961.9     .09       0
  5006.5     .15       0  5222.1     .17       0
Bank Sta=4961.9,5006.5
XS Rating Curve= 0 ,0
Exp/Cntr=0.3,0.1

Type RM Length L Ch R = 1 ,6656    ,656,656,656
BEGIN DESCRIPTION:
BIG CHINQUAPIN CREEK 13.0
END DESCRIPTION:
XS GIS Cut Line= 3
      3809719.68     10224146.04      3808907.22     10224203.64
      3808279.22      10224580.7
#Sta/Elev= 30
  4185.5   335.3  4347.7  328.26  4387.8  324.03  4470.9  320.76    4557  313.85
  4658.5  303.54  4738.7  297.99  4788.8  297.34    4849  298.55  4888.5  297.65
  4929.2  298.08  4939.2  299.47    4978   297.9  4989.3  297.75  5002.5  295.28
  5020.5  297.73    5048  299.19  5063.2  299.51  5078.8  297.75    5106   300.6
  5137.1  300.47  5142.9   301.8  5158.4  301.67  5209.2  306.08  5232.3   306.6
  5267.5  309.88  5391.6  317.86  5427.7  318.76  5492.7   323.6  5732.5  336.26
#Mann= 7 ,-1 , 0
  4185.5     .17       0    4557     .15       0    4978     .17       0
  4989.3     .09       0  5020.5     .17       0    5048     .15       0
  5427.7     .17       0
Bank Sta=4989.3,5020.5
XS Rating Curve= 0 ,0
Exp/Cntr=0.3,0.1