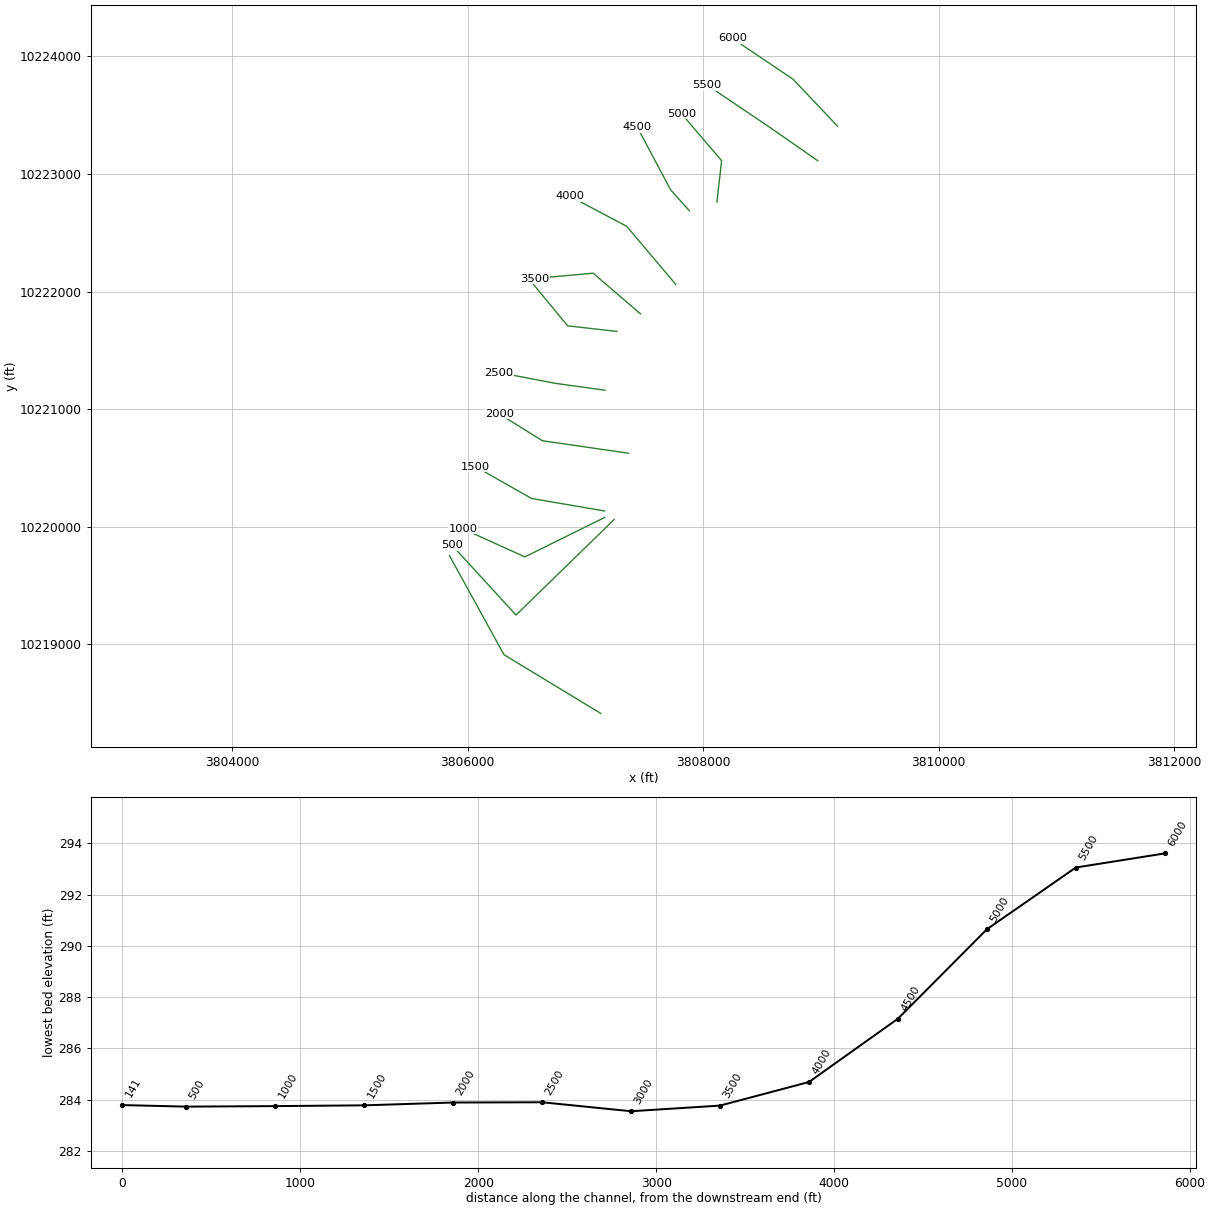
HEC-RAS study BIG CHINQUAPIN CREEK.prj: BIG CHINQUAPIN CREEK Base Level Engineering

--- BIG CHINQUAPIN CREEK.g01 (geometry) --- (continued)

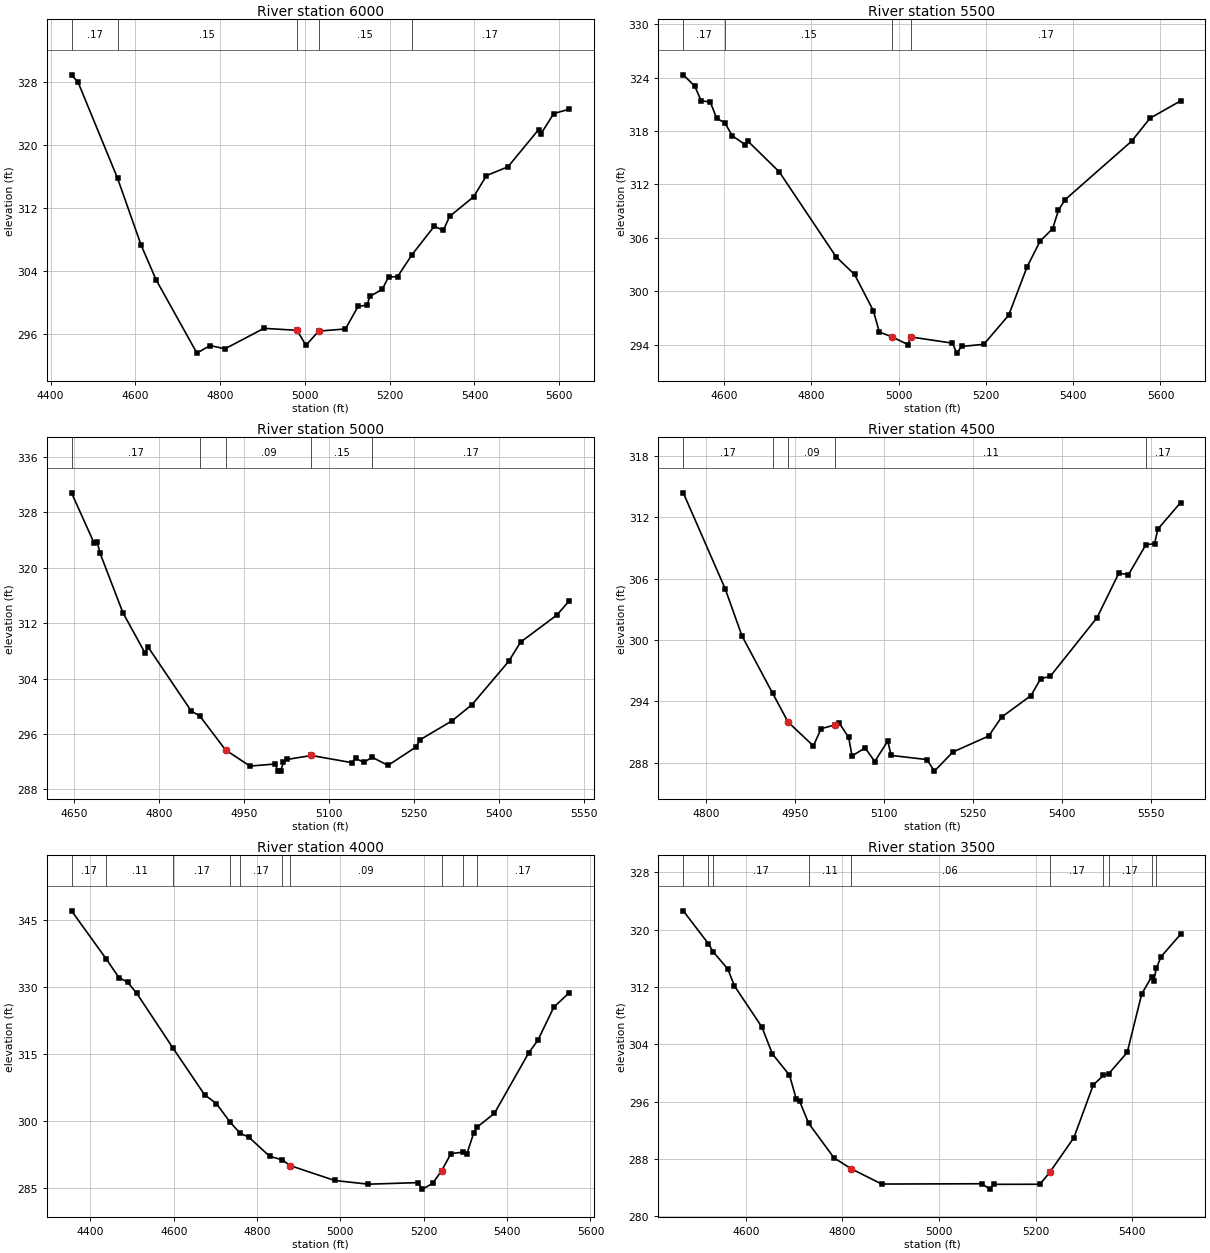
Type RM Length L Ch R = 1 ,6000    ,500,500,500
BEGIN DESCRIPTION:
BIG CHINQUAPIN CREEK 12.0
END DESCRIPTION:
XS GIS Cut Line= 3
      3809143.46     10223404.81      3808764.97     10223804.55
      3808248.88     10224152.81
#Sta/Elev= 30
  4449.5  328.87    4465  327.92  4558.1  315.76  4613.4  307.33    4649   302.9
  4745.3  293.61  4776.1  294.57  4811.6  294.16  4903.5  296.75  4981.4   296.5
  5002.6   294.6  5032.6   296.4  5095.6  296.67  5125.5  299.53  5146.5  299.69
  5153.3  300.79  5182.5   301.7  5197.5  303.27  5218.5  303.29  5252.5  306.07
  5305.4   309.7  5326.4  309.15  5341.4  310.93  5398.3  313.43  5428.3   316.1
  5479.1  317.22  5551.2  321.92  5557.2  321.42  5587.1  323.96  5622.6   324.5
#Mann= 5 ,-1 , 0
  4449.5     .17       0  4558.1     .15       0  4981.4     .09       0
  5032.6     .15       0  5252.5     .17       0
Bank Sta=4981.4,5032.6
XS Rating Curve= 0 ,0
Exp/Cntr=0.3,0.1

Type RM Length L Ch R = 1 ,5500    ,500,500,500
BEGIN DESCRIPTION:
BIG CHINQUAPIN CREEK 11.0
END DESCRIPTION:
XS GIS Cut Line= 3
      3808975.02     10223111.64      3808570.43     10223393.87
      3808034.94     10223755.21
#Sta/Elev= 30
  4506.7  324.31  4532.8  323.05  4547.7   321.4  4568.6  321.25  4583.4  319.41
  4601.6  318.94  4619.2  317.46  4648.9  316.46    4655  316.85  4726.5  313.42
  4856.8  303.88  4899.2  301.89  4942.2  297.82  4955.9  295.43  4985.6  294.87
  5021.5  294.02  5027.5  294.88  5123.4  294.18  5133.2  293.06  5144.4  293.81
  5195.3  294.05  5252.3  297.32  5294.3  302.74  5324.3  305.64    5353  307.04
  5366.3  309.11  5381.2  310.28  5533.9  316.86  5576.1  319.44    5646  321.38
#Mann= 4 ,-1 , 0
  4506.7     .17       0  4601.6     .15       0  4985.6     .09       0
  5027.5     .17       0
Bank Sta=4985.6,5027.5
XS Rating Curve= 0 ,0
Exp/Cntr=0.3,0.1

Type RM Length L Ch R = 1 ,5000    ,500,500,500
BEGIN DESCRIPTION:
BIG CHINQUAPIN CREEK 10.0
END DESCRIPTION:
XS GIS Cut Line= 3
      3808117.85     10222761.03      3808157.48     10223112.81
      3807817.86     10223511.06
#Sta/Elev= 30
    4646  330.84    4686  323.55    4691  323.81  4696.4  322.11  4736.6  313.54
  4775.9  307.68    4781  308.58  4857.4  299.31  4872.1  298.64  4917.7  293.71
  4960.8  291.38  5005.7  291.68  5009.7  290.65  5014.9  290.65    5020  291.97
  5026.6  292.34  5069.4  292.91  5140.8  291.87  5147.3  292.49  5161.6  291.92
  5176.5  292.65  5204.5  291.48  5253.9  294.14  5260.6  295.16  5317.5  297.92
  5352.7  300.26  5417.5  306.52  5438.3  309.28    5502  313.17  5523.4  315.16
#Mann= 5 ,-1 , 0
    4646     .17       0  4872.1     .15       0  4917.7     .09       0
  5069.4     .15       0  5176.5     .17       0
Bank Sta=4917.7,5069.4
XS Rating Curve= 0 ,0
Exp/Cntr=0.3,0.1

Type RM Length L Ch R = 1 ,4500    ,500,500,500
BEGIN DESCRIPTION:
BIG CHINQUAPIN CREEK 9.0
END DESCRIPTION:
XS GIS Cut Line= 3
      3807883.32     10222687.11      3807724.36     10222865.45
      3807442.48     10223395.34
#Sta/Elev= 30
  4761.1   314.4  4831.8  305.01  4860.2  300.39  4911.7   294.8    4938  291.96
  4980.6  289.63  4993.7  291.31  5017.7   291.7  5023.9  291.89  5040.2  290.46
  5045.9  288.64  5067.9  289.44  5084.2   288.1  5106.2  290.11  5111.8   288.7
  5172.1  288.29  5184.9  287.16    5216  289.03  5276.3  290.59  5298.3  292.45
  5347.9  294.56  5364.2  296.21  5380.2  296.43  5459.4  302.19    5496  306.53
  5512.3  306.39  5541.7  309.32  5556.3  309.42  5561.9  310.85  5600.2  313.44
#Mann= 5 ,-1 , 0
  4761.1     .17       0  4911.7     .15       0    4938     .09       0
  5017.7     .11       0  5541.7     .17       0
Bank Sta=4938,5017.7
XS Rating Curve= 0 ,0
Exp/Cntr=0.3,0.1

Type RM Length L Ch R = 1 ,4000    ,500,500,500
BEGIN DESCRIPTION:
BIG CHINQUAPIN CREEK 8.0
END DESCRIPTION:
XS GIS Cut Line= 3
      3807767.84     10222061.09      3807351.98     10222554.39
      3806867.82     10222811.09
#Sta/Elev= 30
  4354.8  347.15  4438.4  336.31  4468.5  332.16  4489.4  331.15  4511.4  328.62
  4598.8  316.26    4674  305.88  4702.6  303.87  4735.2  299.73  4759.3  297.23
  4780.6  296.33  4830.1  292.06  4859.7  291.28  4879.5  289.97  4986.1  286.63
  5067.3   285.8  5185.8  286.15  5196.6  284.69  5221.2  285.96  5243.2  288.87
  5265.2  292.66  5293.6  292.98  5303.5  292.61  5319.9  297.31  5328.6  298.65
  5369.5   301.7  5451.8  315.28  5473.8  318.11  5512.1  325.54    5548  328.68
#Mann= 10 ,-1 , 0
  4354.8     .17       0  4438.4     .11       0  4598.8     .17       0
  4735.2     .11       0  4759.3     .17       0  4859.7     .15       0
  4879.5     .09       0  5243.2     .17       0  5293.6     .11       0
  5328.6     .17       0
Bank Sta=4879.5,5243.2
XS Rating Curve= 0 ,0
Exp/Cntr=0.3,0.1

Type RM Length L Ch R = 1 ,3500    ,500,500,500
BEGIN DESCRIPTION:
BIG CHINQUAPIN CREEK 7.0
END DESCRIPTION:
XS GIS Cut Line= 3
      3807467.86     10221811.06      3807066.18     10222156.22
      3806567.82     10222111.07
#Sta/Elev= 30
  4470.4  322.64  4522.3  318.06    4532  316.95  4562.7   314.5  4576.3  312.16
  4633.4  306.39    4655  302.65  4690.4  299.69  4704.7  296.29  4711.3  296.06
  4730.1  292.96  4782.6  288.14  4817.7  286.63  4881.4  284.48  5088.7  284.52
  5105.1  283.77  5113.1  284.44  5209.2  284.45  5229.3   286.1  5279.5  290.96
  5319.6  298.32  5340.8  299.66  5351.3  299.86  5389.9  302.86    5420  311.04
  5440.8  313.45  5445.1   312.8    5450   314.6  5460.2  316.25  5500.4  319.36
#Mann= 10 ,-1 , 0
  4470.4     .17       0  4522.3     .11       0    4532     .17       0
  4730.1     .11       0  4817.7     .06       0  5229.3     .17       0
  5340.8     .11       0  5351.3     .17       0  5440.8     .11       0
    5450     .17       0
Bank Sta=4817.7,5229.3
XS Rating Curve= 0 ,0
Exp/Cntr=0.3,0.1

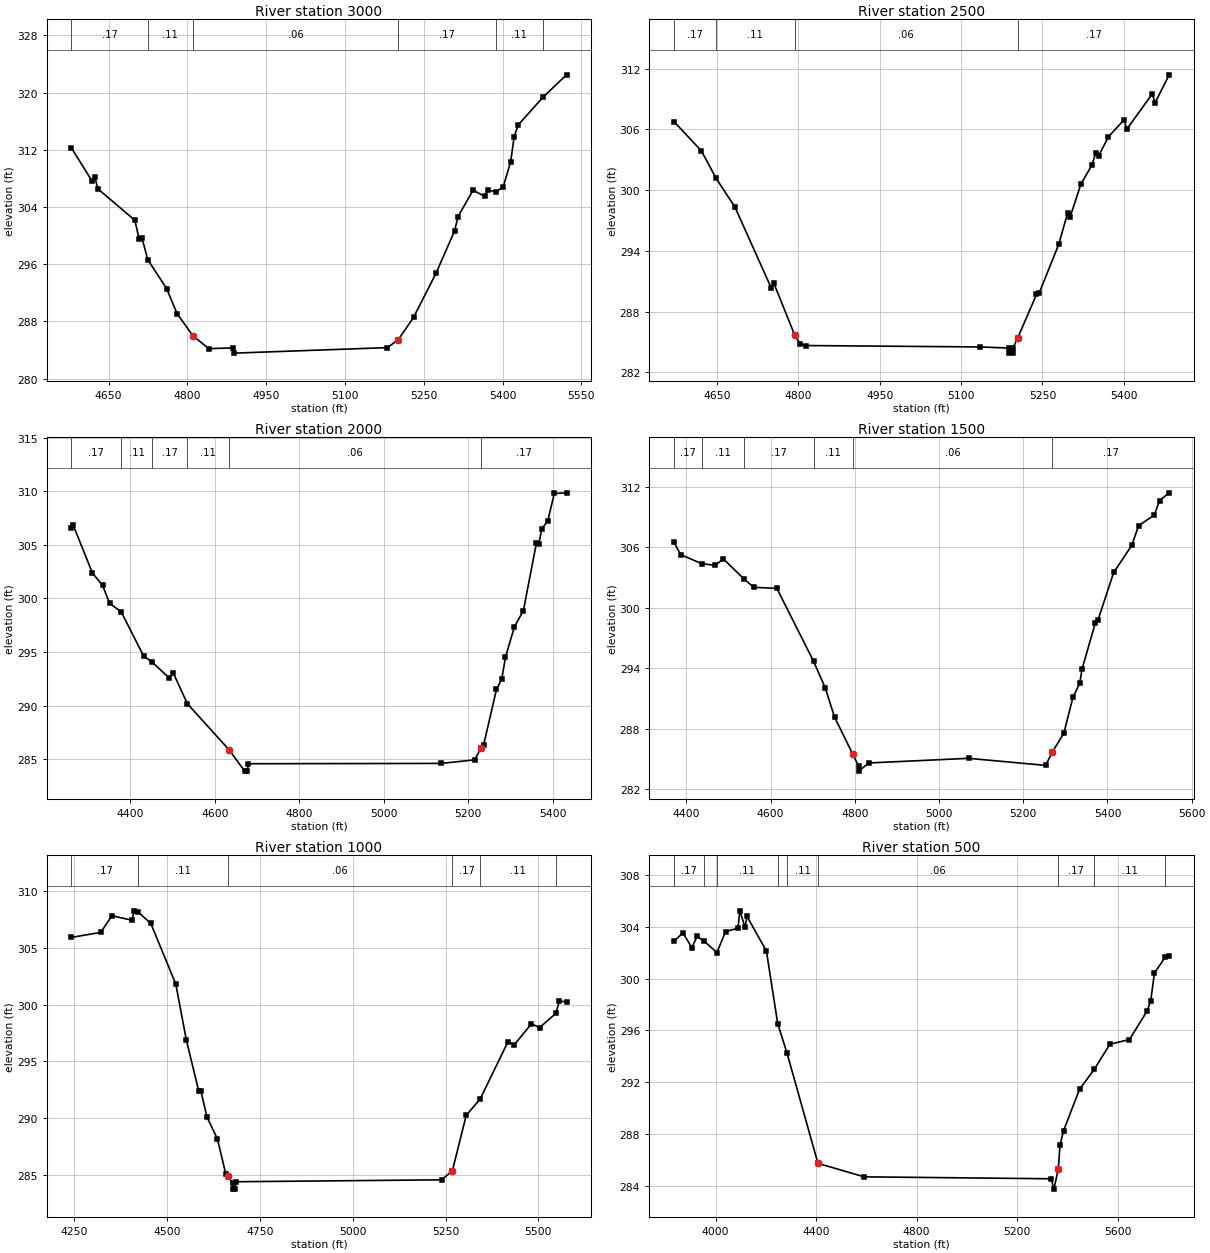
Type RM Length L Ch R = 1 ,3000    ,500,500,500
BEGIN DESCRIPTION:
BIG CHINQUAPIN CREEK 6.0
END DESCRIPTION:
XS GIS Cut Line= 3
      3807267.82     10221661.08      3806849.82     10221708.75
      3806517.85     10222111.07
#Sta/Elev= 30
  4579.3  312.25  4618.9  307.59    4624  308.16  4629.6  306.53    4700  302.14
  4708.4  299.47  4713.4  299.72  4724.5  296.64  4760.4  292.59  4780.6  289.06
  4810.8  285.95  4840.9  284.18  4887.2  284.28  4889.2  283.55  5180.9  284.32
  5201.7  285.45  5230.4  288.54  5273.4  294.74  5308.6  300.66  5315.1  302.64
  5343.7  306.34  5365.9  305.48  5372.4  306.35  5387.1  306.13  5401.1  306.78
  5415.4  310.34  5421.9   313.8  5429.8  315.48  5476.9  319.35  5521.6  322.48
#Mann= 6 ,-1 , 0
  4579.3     .17       0  4724.5     .11       0  4810.8     .06       0
  5201.7     .17       0  5387.1     .11       0  5476.9     .17       0
Bank Sta=4810.8,5201.7
XS Rating Curve= 0 ,0
Exp/Cntr=0.3,0.1

Type RM Length L Ch R = 1 ,2500    ,500,500,500
BEGIN DESCRIPTION:
BIG CHINQUAPIN CREEK 5.0
END DESCRIPTION:
XS GIS Cut Line= 3
      3807167.81     10221161.08      3806742.92     10221220.31
      3806267.82     10221311.08
#Sta/Elev= 30
    4571  306.75  4621.4  303.86  4648.4  301.16  4683.3   298.3  4749.8  290.36
  4754.9  290.79  4793.1   285.7  4803.2  284.83  4813.3  284.65  5134.9  284.51
  5188.5   284.4    5189   283.9  5195.1   283.9  5195.6   284.4 5204.55  285.42
    5239  289.69  5244.1  289.85    5280  294.63  5296.2   297.7  5301.3  297.39
  5320.8  300.57  5341.1  302.47  5348.3  303.65  5353.4  303.37  5371.7  305.26
  5400.4  306.94  5405.5  306.01  5452.5   309.5  5457.6  308.62  5483.7  311.38
#Mann= 4 ,-1 , 0
    4571     .17       0  4648.4     .11       0  4793.1     .06       0
 5204.55     .17       0
Bank Sta=4793.1,5204.55
XS Rating Curve= 0 ,0
Exp/Cntr=0.3,0.1

Type RM Length L Ch R = 1 ,2000    ,500,500,500
BEGIN DESCRIPTION:
BIG CHINQUAPIN CREEK 4.0
END DESCRIPTION:
XS GIS Cut Line= 3
      3807367.07     10220625.58      3806634.98      10220732.1
      3806267.83     10220961.08
#Sta/Elev= 30
  4260.2  306.59    4264  306.88  4309.9  302.37  4334.1  301.21  4350.4  299.55
  4378.2  298.74  4431.2  294.63  4451.3  294.06  4491.8  292.58  4501.9     293
  4534.9  290.17  4633.3  285.89  4670.6  283.89  4676.8  283.89  4679.5  284.58
    5136  284.61    5215  284.94  5230.3  286.04  5236.2  286.31  5266.9  291.51
  5279.5   292.5  5288.2  294.52  5309.4  297.37  5330.6  298.86  5361.3  305.14
  5367.2  305.06  5373.8  306.46  5388.4  307.24  5403.8  309.79  5432.7  309.85
#Mann= 6 ,-1 , 0
  4260.2     .17       0  4378.2     .11       0  4451.3     .17       0
  4534.9     .11       0  4633.3     .06       0  5230.3     .17       0
Bank Sta=4633.3,5230.3
XS Rating Curve= 0 ,0
Exp/Cntr=0.3,0.1

Type RM Length L Ch R = 1 ,1500    ,500,500,500
BEGIN DESCRIPTION:
BIG CHINQUAPIN CREEK 3.0
END DESCRIPTION:
XS GIS Cut Line= 3
      3807163.27     10220134.75      3806543.35     10220241.23
      3806067.87     10220511.06
#Sta/Elev= 30
    4371  306.48  4386.6  305.27  4436.6  304.38  4467.8  304.21  4488.1  304.84
  4537.4  302.84  4560.1  302.03    4615  301.92  4702.1  294.69  4729.9  292.04
  4751.9  289.15  4794.9  285.49  4809.1  284.28  4809.6  283.78  4833.1  284.59
  5070.1  285.05  5253.2  284.35  5269.1  285.67  5296.5  287.55  5318.1  291.11
    5334  292.48  5339.8  293.93  5371.5  298.53  5377.3  298.75  5414.8   303.5
    5458  306.21  5473.9  308.14  5511.4  309.21  5523.7  310.64  5546.7  311.41
#Mann= 6 ,-1 , 0
    4371     .17       0  4436.6     .11       0  4537.4     .17       0
  4702.1     .11       0  4794.9     .06       0  5269.1     .17       0
Bank Sta=4794.9,5269.1
XS Rating Curve= 0 ,0
Exp/Cntr=0.3,0.1

Type RM Length L Ch R = 1 ,1000    ,500,500,500
BEGIN DESCRIPTION:
BIG CHINQUAPIN CREEK 2.0
END DESCRIPTION:
XS GIS Cut Line= 3
       3807165.6     10220080.17      3806486.05      10219744.6
      3805961.79     10219982.48
#Sta/Elev= 30
  4242.1  305.93  4321.2  306.37  4351.1  307.84  4405.4  307.44    4411  308.27
  4420.7  308.19  4455.9  307.16  4523.2  301.82  4551.9  296.85  4584.9  292.41
  4590.5  292.43  4607.4  290.09  4635.4  288.17  4657.9  285.08  4663.4  284.92
  4676.7  284.25  4677.2  283.75  4683.5  283.75  4685.9   284.4  5239.6  284.57
  5268.4  285.38  5305.5  290.24  5343.6  291.72  5417.9  296.73  5435.5  296.48
  5481.2  298.32  5503.2  297.98  5546.9  299.23  5556.4  300.31  5575.7  300.25
#Mann= 6 ,-1 , 0
  4242.1     .17       0  4420.7     .11       0  4663.4     .06       0
  5268.4     .17       0  5343.6     .11       0  5546.9     .17       0
Bank Sta=4663.4,5268.4
XS Rating Curve= 0 ,0
Exp/Cntr=0.3,0.1

Type RM Length L Ch R = 1 ,500     ,359,359,359
BEGIN DESCRIPTION:
BIG CHINQUAPIN CREEK 1.0
END DESCRIPTION:
XS GIS Cut Line= 3
      3807245.49     10220062.84       3806411.1     10219250.24
        3805867.     10219844.06
#Sta/Elev= 30
  3835.3  302.88  3870.3  303.53  3905.6  302.39  3926.9  303.25  3954.3  302.89
  4005.6  302.01    4040  303.63  4089.5  303.89  4096.6  305.23  4117.7  303.95
  4124.9  304.81  4202.6  302.12  4247.5  296.51  4284.3  294.25  4407.6  285.72
  4591.5  284.68  5335.6  284.53  5346.6  283.73    5364  285.28  5370.8  287.12
    5385  288.25  5448.7  291.45  5507.6  292.99  5569.3  294.93    5647  295.28
    5718  297.51  5732.1   298.3  5746.3  300.41  5789.6  301.66  5805.4  301.73
#Mann= 9 ,-1 , 0
  3835.3     .17       0  3954.3     .15       0  4005.6     .11       0
  4247.5     .17       0  4284.3     .11       0  4407.6     .06       0
    5364     .17       0  5507.6     .11       0  5789.6     .17       0
Bank Sta=4407.6,5364
XS Rating Curve= 0 ,0
Exp/Cntr=0.3,0.1

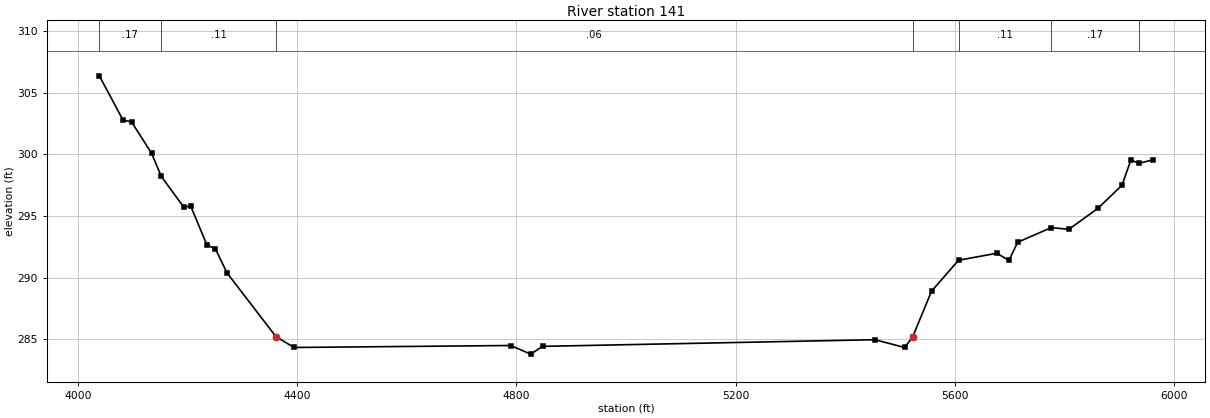
Type RM Length L Ch R = 1 ,141     ,0,0,0
BEGIN DESCRIPTION:
BIG CHINQUAPIN CREEK 36.0
END DESCRIPTION:
XS GIS Cut Line= 3
      3807130.57      10218414.1      3806309.03     10218912.88
      3805845.87     10219755.25
#Sta/Elev= 30
  4038.9  306.38  4082.1  302.79  4097.6  302.65  4134.4  300.08  4151.9  298.22
  4192.6  295.74  4205.9  295.78  4235.2  292.65  4250.7  292.33  4272.1  290.37
 4361.19  285.21  4394.2  284.33  4789.6  284.49  4826.1  283.79  4847.7  284.42
  5454.4  284.96  5508.4  284.33  5522.9  285.16  5557.6   288.9  5606.9  291.41
    5677  291.98  5698.8  291.39  5714.8  292.87    5776  294.06  5808.2  293.92
  5861.7  295.64  5905.2   297.5  5921.3  299.54  5936.4  299.28  5961.3  299.56
#Mann= 7 ,-1 , 0
  4038.9     .17       0  4151.9     .11       0 4361.19     .06       0
  5522.9     .17       0  5606.9     .11       0    5776     .17       0
  5936.4     .11       0
Bank Sta=4361.19,5522.9
XS Rating Curve= 0 ,0
Exp/Cntr=0.3,0.1

Chan Stop Cuts=-1
Use User Specified Reach Order=0
Composite Channel Slope=5