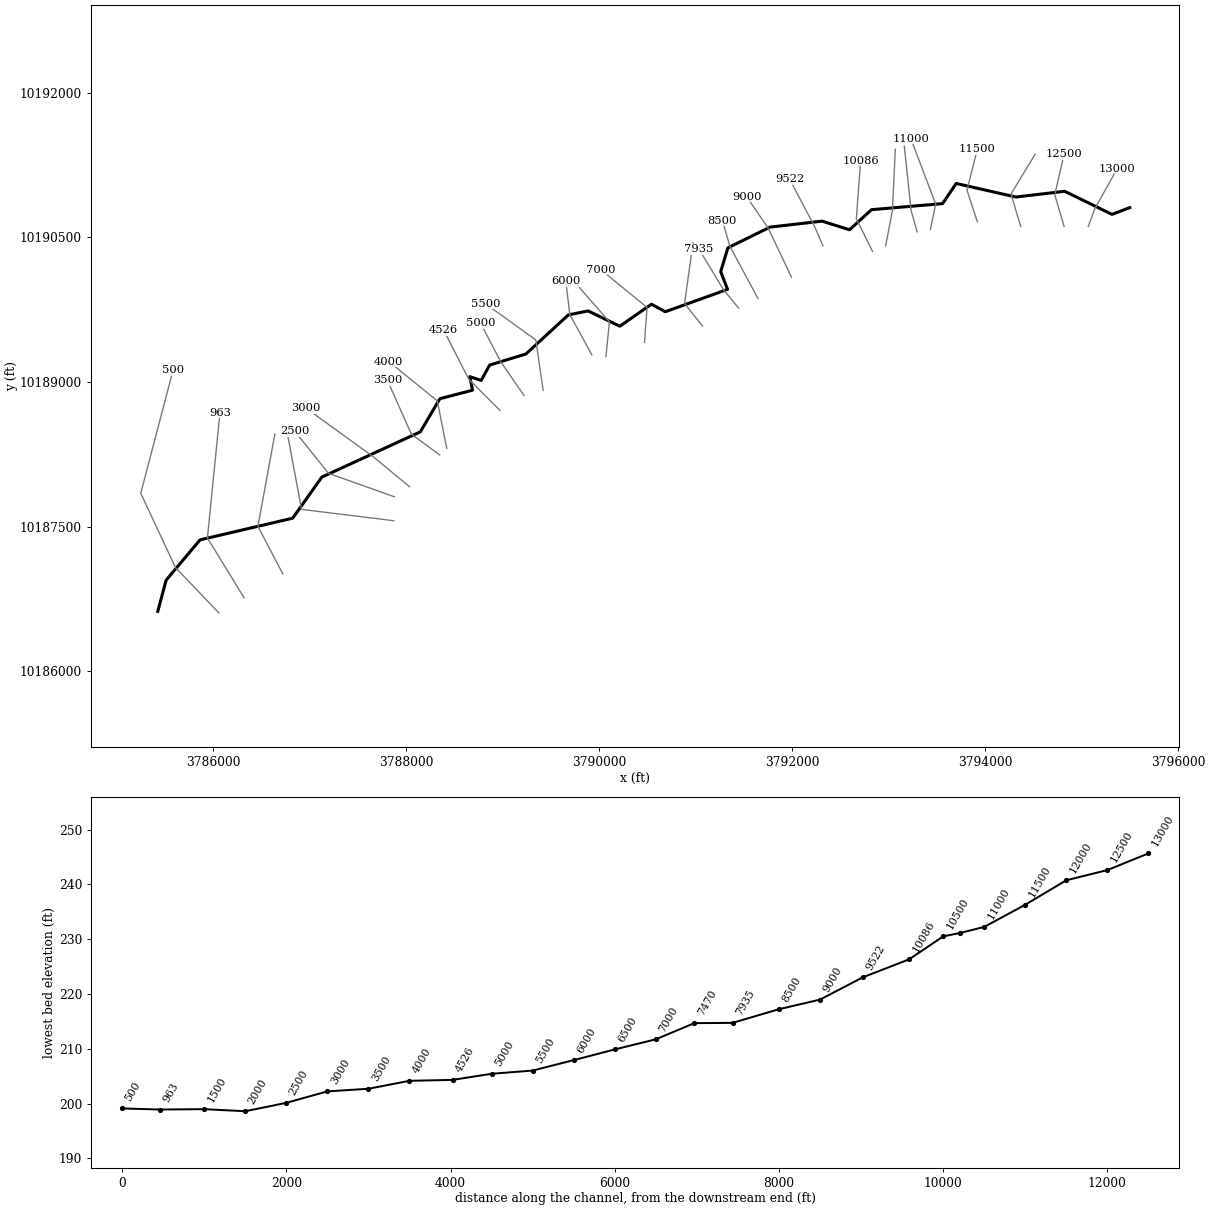
--- BROWN BRANCH.prj (project) ---

Proj Title=BROWN BRANCH Base Level Engineering
Current Plan=p01
Default Exp/Contr=0.3,0.1
English Units
Geom File=g01
Flow File=f01
Flow File=f02
Plan File=p01
Y Axis Title=Elevation
X Axis Title(PF)=Main Channel Distance
X Axis Title(XS)=Station
BEGIN DESCRIPTION:
BROWN BRANCH
END DESCRIPTION:
DSS Export Rating Curves= 0
DSS Export Rating Curve Sorted= 0
DSS Export Volume Flow Curves= 0
DXF OffsetX= 0
DXF OffsetY= 0
DXF ScaleX= 1
DXF ScaleY= 10

--- BROWN BRANCH.p01 (plan) ---

Plan Title=Multiple Run
Short Identifier=Multiple
Geom File=g01
Flow File=f01
Subcritical Flow
K Sum by GR= 0
Std Step Tol= 0.01
Critical Tol= 0.01
Num of Std Step Trials= 20
Max Error Tol= 0.3
Flow Tol Ratio= 0.001
Split Flow NTrial= 30
Split Flow Tol= 0.02
Split Flow Ratio= 0.02
Log Output Level= 0
Friction Slope Method= 1
Unsteady Friction Slope Method= 2
Unsteady Bridges Friction Slope Method= 1
Parabolic Critical Depth
Global Vel Dist=  1 , 1 , 1
Global Log Level= 0
CheckData=True
Encroach Param= -1, 0, 0, 0
BEGIN DESCRIPTION:
Multiple Run
END DESCRIPTION:

--- BROWN BRANCH.f01 (steady flow) ---

Flow Title=Multiple
Program Version=4.10
Number of Profiles= 7
Profile Names=10-year,25-year,50-year,1pct_min,100-year,1pct_plu,500-year
River Rch & RM=BROWN BRANCH,Reach-1         ,13000
     647     887    1211     545    1647    4974    3142
River Rch & RM=BROWN BRANCH,Reach-1         ,12500
     883    1221    1672     753    2275    6870    4353
River Rch & RM=BROWN BRANCH,Reach-1         ,7470
    1078    1496    2054     926    2796    8444    5365
River Rch & RM=BROWN BRANCH,Reach-1         ,2500
    1227    1711    2355    1064    3214    9706    6192
Boundary for River Rch & Prof#=BROWN BRANCH,Reach-1         , 1
Up Type= 0
Dn Type= 3
Dn Slope=0.005
Boundary for River Rch & Prof#=BROWN BRANCH,Reach-1         , 2
Up Type= 0
Dn Type= 3
Dn Slope=0.005
Boundary for River Rch & Prof#=BROWN BRANCH,Reach-1         , 3
Up Type= 0
Dn Type= 3
Dn Slope=0.005
Boundary for River Rch & Prof#=BROWN BRANCH,Reach-1         , 4
Up Type= 0
Dn Type= 3
Dn Slope=0.005
Boundary for River Rch & Prof#=BROWN BRANCH,Reach-1         , 5
Up Type= 0
Dn Type= 3
Dn Slope=0.005
Boundary for River Rch & Prof#=BROWN BRANCH,Reach-1         , 6
Up Type= 0
Dn Type= 3
Dn Slope=0.005
Boundary for River Rch & Prof#=BROWN BRANCH,Reach-1         , 7
Up Type= 0
Dn Type= 3
Dn Slope=0.005
DSS Import GetInterval= 0
DSS Import GetPeak= 0
DSS Import FillOption= 0

--- BROWN BRANCH.f02 (steady flow) ---

Flow Title=Orig_BLE_Flow
Program Version=4.10
Number of Profiles= 7
Profile Names=10-year,25-year,50-year,1pct_min,100-year,1pct_plu,500-year
River Rch & RM=BROWN BRANCH,Reach-1         ,13000
     647     870    1053     420    1267    3826    1827
River Rch & RM=BROWN BRANCH,Reach-1         ,12500
     883    1197    1454     579    1750    5284    2531
River Rch & RM=BROWN BRANCH,Reach-1         ,7470
    1078    1467    1786     712    2151    6497    3119
River Rch & RM=BROWN BRANCH,Reach-1         ,2500
    1227    1677    2048     819    2472    7466    3600
Boundary for River Rch & Prof#=BROWN BRANCH,Reach-1         , 1
Up Type= 0
Dn Type= 3
Dn Slope=0.005
Boundary for River Rch & Prof#=BROWN BRANCH,Reach-1         , 2
Up Type= 0
Dn Type= 3
Dn Slope=0.005
Boundary for River Rch & Prof#=BROWN BRANCH,Reach-1         , 3
Up Type= 0
Dn Type= 3
Dn Slope=0.005
Boundary for River Rch & Prof#=BROWN BRANCH,Reach-1         , 4
Up Type= 0
Dn Type= 3
Dn Slope=0.005
Boundary for River Rch & Prof#=BROWN BRANCH,Reach-1         , 5
Up Type= 0
Dn Type= 3
Dn Slope=0.005
Boundary for River Rch & Prof#=BROWN BRANCH,Reach-1         , 6
Up Type= 0
Dn Type= 3
Dn Slope=0.005
Boundary for River Rch & Prof#=BROWN BRANCH,Reach-1         , 7
Up Type= 0
Dn Type= 3
Dn Slope=0.005
DSS Import GetInterval= 0
DSS Import GetPeak= 0
DSS Import FillOption= 0

--- BROWN BRANCH.g01 (geometry) ---

Geom Title=Existing Conditions
Program Version=4.10

River Reach=BROWN BRANCH    ,Reach-1
Reach XY= 30
      3795498.23     10190806.84      3795314.12     10190737.06
      3794823.16      10190976.4      3794318.35     10190916.92
      3793699.07     10191057.28       3793557.7     10190848.61
      3792821.59     10190785.64      3792593.11      10190577.4
      3792309.17     10190666.81        3791769.     10190604.93
      3791332.13     10190390.18      3791257.96     10190143.45
      3791329.15     10189959.43       3790683.1     10189727.41
      3790540.09     10189805.54      3790212.07     10189577.14
      3789883.89     10189735.98      3789678.86     10189695.13
      3789238.87     10189289.53      3788862.88     10189174.87
      3788775.08      10189015.5      3788656.56     10189054.77
      3788685.18     10188914.24      3788346.85     10188825.75
      3788143.86     10188482.22      3787123.31     10188013.31
      3786821.07     10187587.34      3785860.54     10187362.48
      3785508.86     10186944.12      3785422.47     10186620.96

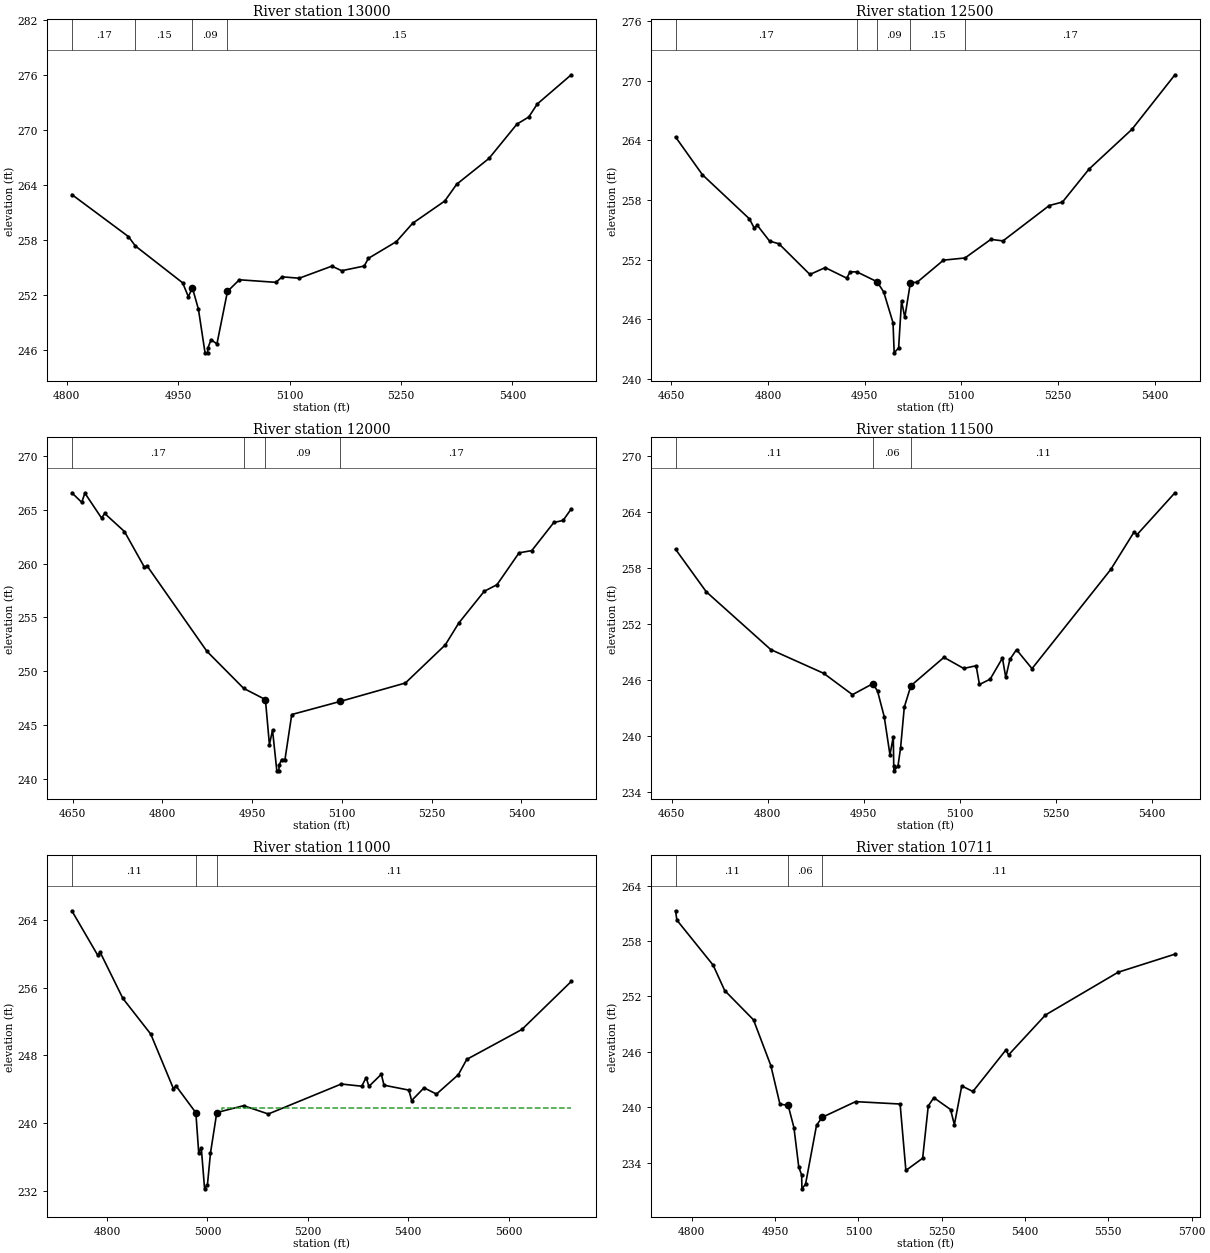
Type RM Length L Ch R = 1 ,13000   ,500,500,500
BEGIN DESCRIPTION:
BROWN BRANCH 26.0
END DESCRIPTION:
XS GIS Cut Line= 3
      3795067.84     10190611.04      3795134.52     10190792.48
      3795367.83     10191211.04
#Sta/Elev= 30
  4806.7  262.94  4882.9  258.35  4892.3  257.32  4955.9   253.3  4963.7  251.77
    4969  252.77  4977.2  250.41  4986.1  245.65  4989.6  245.65  4989.8  246.15
  4994.2  247.09  5002.1  246.62  5016.3  252.36  5032.3  253.63  5081.5  253.35
    5090  253.95  5112.9   253.8  5156.9  255.12  5170.1  254.62  5200.4  255.13
  5206.1  255.97  5243.8   257.8  5265.5  259.79  5308.9  262.23  5324.9  264.06
  5368.4  266.88  5406.1  270.63    5422  271.41  5433.5  272.83  5479.2  276.02
#Mann= 4 ,-1 , 0
  4806.7     .17       0  4892.3     .15       0    4969     .09       0
  5016.3     .15       0
Bank Sta=4969,5016.3
XS Rating Curve= 0 ,0
Exp/Cntr=0.3,0.1

Type RM Length L Ch R = 1 ,12500   ,500,500,500
BEGIN DESCRIPTION:
BROWN BRANCH 25.0
END DESCRIPTION:
XS GIS Cut Line= 3
      3794817.84      10190611.1      3794720.85     10190940.41
      3794817.85     10191361.07
#Sta/Elev= 30
  4656.7  264.34  4698.4  260.54  4771.3   256.1  4778.6   255.2  4783.8  255.43
  4802.6  253.86  4817.1  253.59  4865.2   250.5    4889  251.19  4922.3  250.13
  4927.7  250.76  4938.1  250.76  4969.4  249.77  4979.8  248.73  4994.2  245.64
    4996  242.61  5002.9  243.11  5007.4  247.85  5012.5  246.17  5021.2  249.68
  5031.5  249.71  5072.5  251.94  5105.9  252.16    5146  254.03  5164.9  253.88
  5236.7  257.44  5257.2  257.79  5298.3   261.1    5365  265.11  5431.7   270.6
#Mann= 5 ,-1 , 0
  4656.7     .17       0  4938.1     .15       0  4969.4     .09       0
  5021.2     .15       0  5105.9     .17       0
#XS Ineff= 2 , 0
       0  4817.1  253.59               0
Permanent Ineff=
       F       F
Bank Sta=4969.4,5021.2
XS Rating Curve= 0 ,0
Exp/Cntr=0.3,0.1

Type RM Length L Ch R = 1 ,12000   ,500,500,500
BEGIN DESCRIPTION:
BROWN BRANCH 24.0
END DESCRIPTION:
XS GIS Cut Line= 3
      3794367.85     10190611.07      3794267.19     10190947.85
      3794517.85     10191361.07
#Sta/Elev= 30
  4648.5  266.58  4665.1  265.69  4670.3  266.55  4698.2  264.23  4703.4  264.66
  4736.5  262.98  4769.6  259.69  4774.8  259.75  4874.2  251.86  4935.8  248.41
  4972.1  247.37  4978.8  243.19    4984  244.53  4991.2  240.75  4994.7  240.75
  4994.9  241.25  4999.1   241.8  5004.8   241.8  5016.1  245.98  5097.3   247.2
  5206.1  248.91  5272.8  252.45  5295.2  254.47  5337.9  257.43  5359.2  258.04
  5396.1     261  5417.4  261.21  5454.2  263.82  5469.7  264.01  5483.3  265.08
#Mann= 4 ,-1 , 0
  4648.5     .17       0  4935.8     .15       0  4972.1     .09       0
  5097.3     .17       0
Bank Sta=4972.1,5097.3
XS Rating Curve= 0 ,0
Exp/Cntr=0.3,0.1

Type RM Length L Ch R = 1 ,11500   ,500,500,500
BEGIN DESCRIPTION:
BROWN BRANCH 23.0
END DESCRIPTION:
XS GIS Cut Line= 3
      3793917.86     10190661.04      3793811.16     10190988.07
      3793917.84     10191411.03
#Sta/Elev= 30
    4656  260.03  4703.9  255.48  4804.8  249.28  4887.4  246.74  4932.4  244.45
  4964.3  245.63  4971.6  244.83  4982.1  242.07    4991     238  4996.2  239.96
  4996.9  236.79  4997.2  236.29  5003.5  236.79  5007.6  238.76  5013.4  243.12
  5023.7  245.41  5075.3  248.45  5106.2  247.26  5125.6  247.55  5130.8  245.54
  5147.5  246.11  5166.7  248.37  5171.9   246.3  5178.4  248.24  5188.7  249.27
  5212.9  247.24  5336.1  257.88  5372.1  261.85  5377.2  261.61  5436.2  266.08
#Mann= 3 , 0 , 0
    4656     .11       0  4964.3     .06       0  5023.7     .11       0
#XS Ineff= 2 , 0
       0                  5075.3       0  248.45
Permanent Ineff=
       F       F
Bank Sta=4964.3,5023.7
XS Rating Curve= 0 ,0
Exp/Cntr=0.3,0.1

Type RM Length L Ch R = 1 ,11000   ,289,289,289
BEGIN DESCRIPTION:
BROWN BRANCH 22.0
END DESCRIPTION:
XS GIS Cut Line= 3
      3793431.83     10190579.06      3793486.24     10190843.72
       3793229.3     10191521.34
#Sta/Elev= 30
  4729.8  265.08  4781.2  259.85  4786.3  260.17  4831.5  254.73    4887  250.52
  4932.2  244.07  4937.3   244.4  4976.9  241.23  4982.6  236.48  4987.7  237.09
  4994.3  232.24    5000  232.74    5006  236.45  5018.6  241.25    5072  242.06
  5121.3  241.08  5266.6  244.62  5307.3  244.36  5316.2  245.38  5321.6  244.34
  5346.4  245.77  5351.7  244.48  5401.3   243.9  5406.7  242.66  5431.5  244.17
  5456.3  243.43  5499.8  245.72  5516.6  247.53  5626.4  251.06  5724.7  256.73
#Mann= 3 , 0 , 0
  4729.8     .11       0  4976.9     .06       0  5018.6     .11       0
#XS Ineff= 2 , 0
       0                  5029.3       0  241.82
Permanent Ineff=
       F       F
Bank Sta=4976.9,5018.6
XS Rating Curve= 0 ,0
Exp/Cntr=0.3,0.1

Type RM Length L Ch R = 1 ,10711   ,211,211,211
BEGIN DESCRIPTION:
Mapping XS 2e5de542
END DESCRIPTION:
XS GIS Cut Line= 3
      3793294.14     10190555.91       3793231.8     10190776.68
      3793161.15     10191442.84
#Sta/Elev= 30
  4770.6  261.28    4773  260.27  4838.3  255.39  4859.1  252.64    4911  249.46
  4942.2  244.51  4958.6  240.33  4973.4  240.19  4983.8  237.79  4992.5  233.51
  4997.7  232.65  4998.2  231.15  5004.7  231.65  5024.5  238.04  5034.6   238.9
  5094.9   240.6    5175  240.34  5185.4  233.14  5215.6  234.47  5225.7  240.13
  5235.7  241.03  5265.9  239.74  5272.7   238.1    5286   242.3  5306.1   241.7
  5365.4  246.19  5370.4  245.67  5436.8  249.99  5567.6  254.62  5669.9  256.58
#Mann= 3 ,-1 , 0
  4770.6     .11       0  4973.4     .06       0  5034.6     .11       0
#XS Ineff= 2 , 0
       0                  5094.9       0   240.6
Permanent Ineff=
       F       F
Bank Sta=4973.4,5034.6
XS Rating Curve= 0 ,0
Exp/Cntr=0.3,0.1

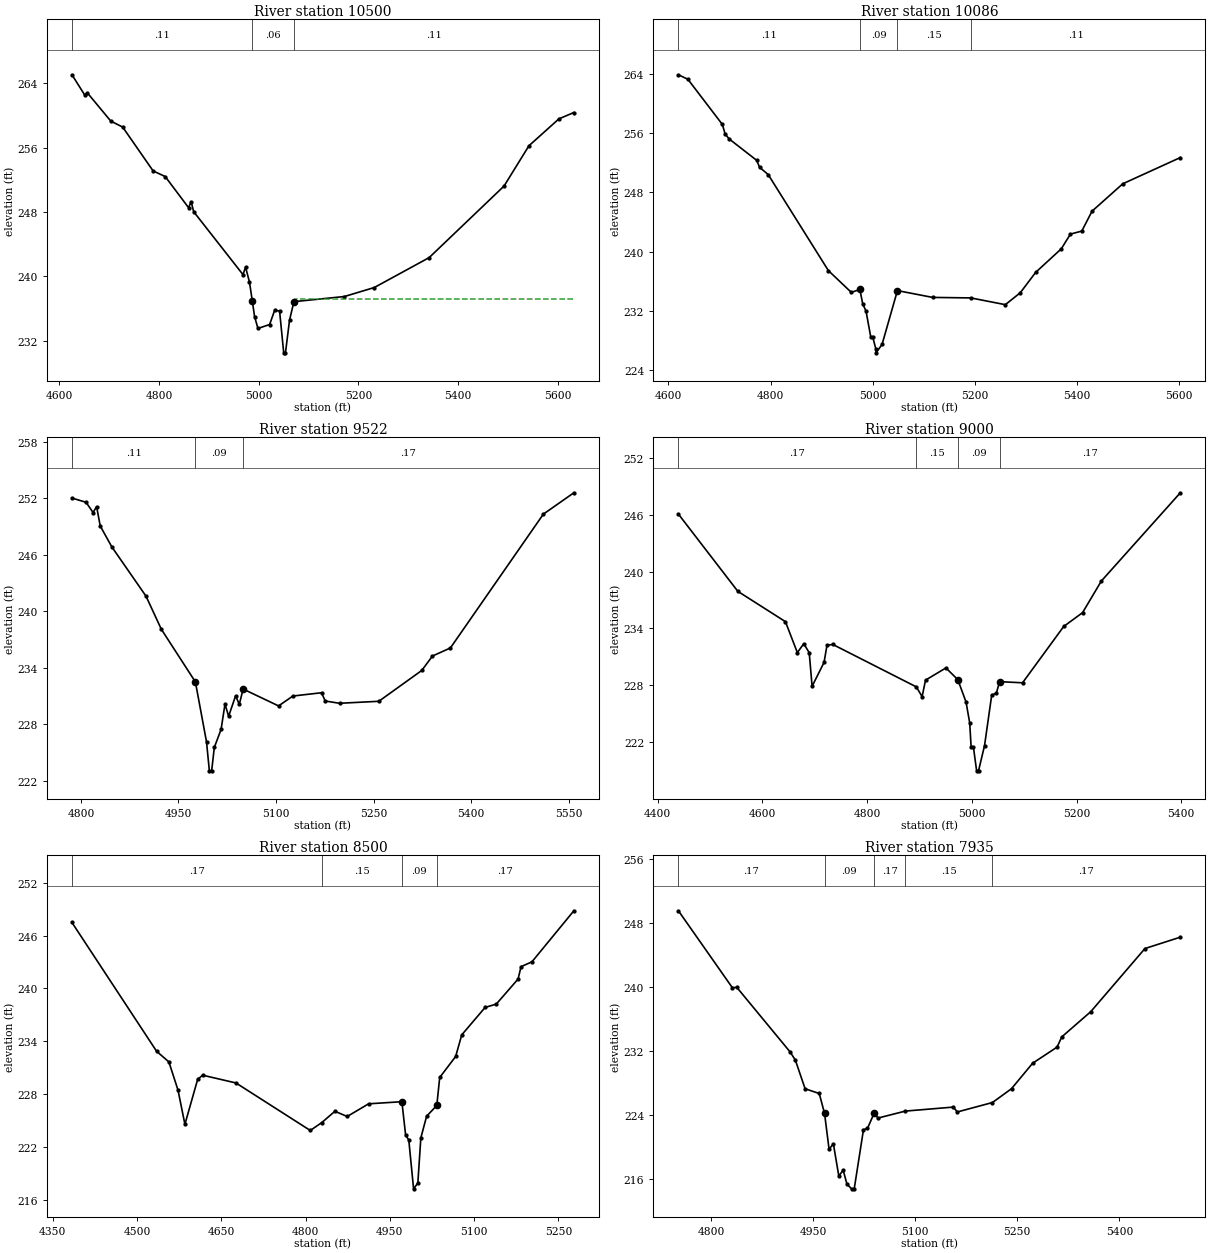
Type RM Length L Ch R = 1 ,10500   ,414,414,414
BEGIN DESCRIPTION:
BROWN BRANCH 21.0
END DESCRIPTION:
XS GIS Cut Line= 3
      3792967.86     10190411.11       3793038.4     10190779.41
      3793067.85     10191411.03
#Sta/Elev= 30
    4625  265.07    4651  262.52  4656.1  262.81    4703  259.31  4726.8  258.57
  4787.9  253.12  4812.2  252.42  4859.1  248.55  4864.2   249.3  4869.3  248.05
  4968.3  240.23  4973.4  241.17  4981.3   239.3 4987.11   236.9  4991.5  235.02
  4998.3  233.54  5021.7  234.03  5031.7  235.78  5041.7  235.72    5050  230.51
  5053.5  230.51  5061.7  234.58 5070.46  236.87  5171.8  237.51  5231.9  238.63
    5342  242.35  5492.2  251.24  5542.2  256.25  5602.3  259.59  5632.3  260.38
#Mann= 3 , 0 , 0
    4625     .11       0 4987.11     .06       0 5070.46     .11       0
#XS Ineff= 2 , 0
       0                  5071.7       0  237.22
Permanent Ineff=
       F       F
Bank Sta=4987.11,5070.46
XS Rating Curve= 0 ,0
Exp/Cntr=0.3,0.1

Type RM Length L Ch R = 1 ,10086   ,564,564,564
BEGIN DESCRIPTION:
BROWN BRANCH 20.0
END DESCRIPTION:
XS GIS Cut Line= 3
      3792832.26     10190351.73      3792663.86     10190692.82
      3792708.65     10191293.46
#Sta/Elev= 30
  4619.6  263.85  4638.2  263.24  4705.6  257.15  4711.1  255.85  4719.2  255.18
  4772.9   252.3  4778.5  251.37  4795.4  250.38  4913.2  237.43  4958.1  234.49
  4974.9  234.88  4980.5  232.92  4986.9  231.97  4996.2  228.47    5000  228.47
  5006.3  226.83  5006.5  226.33  5018.3  227.46  5048.4  234.73  5117.2  233.81
  5192.1  233.74  5259.7  232.83    5289  234.44  5319.1  237.19  5369.3  240.37
  5387.1  242.35  5409.4  242.76  5429.4  245.44  5489.6  249.14  5602.3  252.68
#Mann= 4 ,-1 , 0
  4619.6     .11       0  4974.9     .09       0  5048.4     .15       0
  5192.1     .11       0
Bank Sta=4974.9,5048.4
XS Rating Curve= 0 ,0
Exp/Cntr=0.3,0.1

Type RM Length L Ch R = 1 ,9522    ,522,522,522
BEGIN DESCRIPTION:
BROWN BRANCH 19.0
END DESCRIPTION:
XS GIS Cut Line= 3
      3792317.84     10190411.11      3792233.03     10190607.37
      3791972.61     10191100.76
#Sta/Elev= 30
  4786.2  252.04  4807.9  251.59  4818.7   250.5  4824.1  251.13  4829.7  249.07
  4847.6  246.84  4900.1  241.61  4923.6   238.1    4976   232.5  4993.1  226.13
  4997.5  223.05    5001  223.05  5005.1  225.54  5015.5  227.45  5021.5  230.14
  5027.1  228.85  5037.8  231.02  5043.5  230.12  5049.4  231.74  5103.9  229.95
  5125.9     231    5170  231.35  5175.6  230.47  5197.6  230.23    5258  230.44
  5324.1  233.72  5340.5  235.25  5368.1  236.11    5511  250.33  5557.9   252.6
#Mann= 3 ,-1 , 0
  4786.2     .11       0    4976     .09       0  5049.4     .17       0
Bank Sta=4976,5049.4
XS Rating Curve= 0 ,0
Exp/Cntr=0.3,0.1

Type RM Length L Ch R = 1 ,9000    ,500,500,500
BEGIN DESCRIPTION:
BROWN BRANCH 18.0
END DESCRIPTION:
XS GIS Cut Line= 3
      3791992.11     10190084.83      3791751.76     10190590.96
      3791527.55     10190920.04
#Sta/Elev= 30
  4439.7  246.07  4553.2  237.92  4644.1  234.72  4666.8  231.46  4679.1  232.39
  4689.5  231.45    4695   227.9  4717.8  230.42  4723.4  232.22  4734.4  232.32
    4894  227.84  4905.1  226.81  4911.6  228.55  4950.6  229.84  4973.3   228.6
    4989  226.24    4996  224.03  4998.7  221.48  5003.1  221.48  5009.2  218.98
  5012.8  218.98  5024.3  221.64    5038  226.97  5046.9  227.17    5053  228.39
  5096.9  228.27  5175.6  234.22  5211.5  235.67  5247.4  239.01  5398.2  248.32
#Mann= 4 ,-1 , 0
  4439.7     .17       0    4894     .15       0  4973.3     .09       0
    5053     .17       0
#XS Ineff= 2 , 0
       0  4734.4  232.32               0
Permanent Ineff=
       F       F
Bank Sta=4973.3,5053
XS Rating Curve= 0 ,0
Exp/Cntr=0.3,0.1

Type RM Length L Ch R = 1 ,8500    ,565,565,565
BEGIN DESCRIPTION:
BROWN BRANCH 17.0
END DESCRIPTION:
XS GIS Cut Line= 3
      3791644.52     10189864.05      3791352.91      10190406.2
      3791275.64     10190672.73
#Sta/Elev= 30
  4384.4  247.49    4535  232.86  4556.9  231.65  4573.1  228.45  4585.4  224.56
  4608.1  229.67    4617  230.14  4676.2  229.26  4808.5  223.86    4829  224.76
  4852.3  226.04  4874.2  225.45  4912.3  226.89  4971.5  227.13  4978.1  223.36
  4983.8  222.77  4992.3  217.23  4999.9  217.89  5005.2  223.01  5015.5  225.48
  5033.6   226.7  5038.8  229.88  5067.2  232.27    5078  234.72  5119.6  237.84
  5139.5  238.22  5178.3  241.07  5183.5  242.47  5202.9  243.02  5277.5  248.82
#Mann= 4 ,-1 , 0
  4384.4     .17       0    4829     .15       0  4971.5     .09       0
  5033.6     .17       0
#XS Ineff= 2 , 0
       0    4617  230.14               0
Permanent Ineff=
       F       F
Bank Sta=4971.5,5033.6
XS Rating Curve= 0 ,0
Exp/Cntr=0.3,0.1

Type RM Length L Ch R = 1 ,7935    ,465,465,465
BEGIN DESCRIPTION:
BROWN BRANCH 16.0
END DESCRIPTION:
XS GIS Cut Line= 3
      3791443.56     10189765.19       3791285.9     10189956.76
      3791033.43     10190376.24
#Sta/Elev= 30
  4751.9   249.5  4831.2  239.88  4837.7  239.93  4915.9  231.87  4923.8  230.83
  4938.1  227.25  4958.9  226.66  4966.7  224.16  4973.3  219.71  4979.7  220.35
  4987.6  216.36  4994.1  217.06  4999.6  215.33  5006.5  214.74  5010.3  214.74
  5023.9  222.14  5029.8  222.29  5039.5  224.19  5045.3  223.59  5085.5  224.46
    5156  224.96  5161.8  224.35  5213.5  225.53  5241.5  227.26  5272.5  230.44
  5308.5  232.46  5315.3  233.73    5358  236.89  5437.6  244.78  5489.6   246.2
#Mann= 5 ,-1 , 0
  4751.9     .17       0  4966.7     .09       0  5039.5     .17       0
  5085.5     .15       0  5213.5     .17       0
Bank Sta=4966.7,5039.5
XS Rating Curve= 0 ,0
Exp/Cntr=0.3,0.1

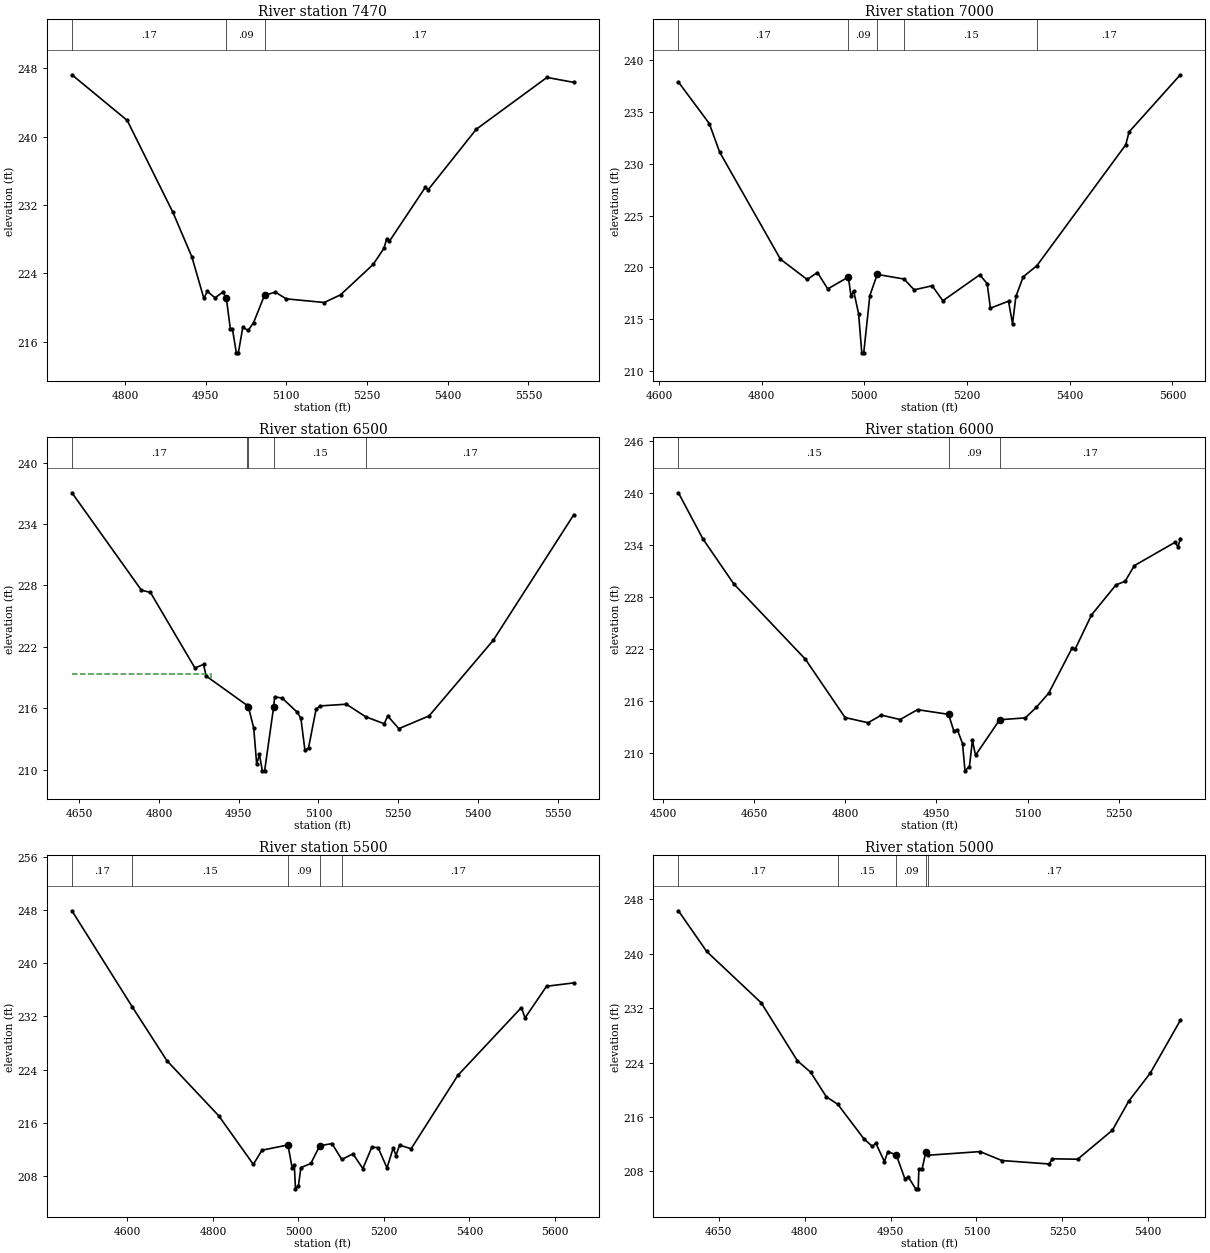
Type RM Length L Ch R = 1 ,7470    ,470,470,470
BEGIN DESCRIPTION:
BROWN BRANCH 15.0
END DESCRIPTION:
XS GIS Cut Line= 3
      3791069.58     10189579.06      3790883.31     10189812.18
      3790970.73     10190440.63
#Sta/Elev= 30
  4701.6  247.23  4804.3  241.89  4889.2  231.14  4924.4  225.94  4946.8  221.06
  4953.2  221.88  4967.6  221.13  4982.1   221.8  4988.5  221.14  4996.1  217.44
    5000  217.44  5007.1  214.69  5010.9  214.69  5019.1  217.66  5029.2  217.32
  5039.3  218.24  5059.5  221.43  5079.7  221.79  5099.8  221.01  5170.5  220.58
  5200.8  221.48  5261.4  225.03  5281.6  226.93  5286.8  228.07  5291.8  227.76
  5358.4  234.06  5363.5  233.76  5453.2  240.86  5584.5  246.92  5634.5  246.34
#Mann= 3 , 0 , 0
  4701.6     .17       0  4988.5     .09       0  5059.5     .17       0
Bank Sta=4988.5,5059.5
XS Rating Curve= 0 ,0
Exp/Cntr=0.3,0.1

Type RM Length L Ch R = 1 ,7000    ,500,500,500
BEGIN DESCRIPTION:
BROWN BRANCH 14.0
END DESCRIPTION:
XS GIS Cut Line= 3
      3790467.85     10189411.11      3790494.75     10189772.21
      3790017.88     10190161.04
#Sta/Elev= 30
  4637.9  237.91    4698   233.9  4718.1  231.15  4836.6  220.79  4888.6  218.83
  4908.6   219.5  4928.7  217.92  4968.8  219.06  4974.1  217.21  4979.1  217.73
  4988.8  215.52    4995  211.74  4998.8  211.74  5010.7  217.28  5025.1  219.32
  5077.4  218.87  5096.9  217.83  5132.1  218.22  5152.9  216.77  5224.7  219.28
  5239.1  218.43  5245.5  216.06  5280.7  216.73  5288.6  214.55  5295.1  217.19
  5309.4  219.09  5336.1  220.17  5509.1  231.85  5515.5  233.09  5615.3  238.61
#Mann= 5 ,-1 , 0
  4637.9     .17       0  4968.8     .09       0  5025.1     .17       0
  5077.4     .15       0  5336.1     .17       0
Bank Sta=4968.8,5025.1
XS Rating Curve= 0 ,0
Exp/Cntr=0.3,0.1

Type RM Length L Ch R = 1 ,6500    ,500,500,500
BEGIN DESCRIPTION:
BROWN BRANCH 13.0
END DESCRIPTION:
XS GIS Cut Line= 3
      3790067.85     10189261.04      3790104.42     10189622.69
      3789722.29     10190059.28
#Sta/Elev= 30
  4636.5  237.05  4767.2  227.53    4784  227.32  4867.7  219.94  4883.9  220.28
  4888.9  219.15  4965.4   216.3  4968.2  216.17  4978.3  214.06  4983.9  210.52
  4988.9   211.5  4994.5  209.89  4998.8  209.89 5015.68  216.11  5017.7  217.12
  5031.9  216.99  5060.4   215.6    5067  215.01  5074.6  211.88  5081.3  212.13
  5095.5   215.9  5103.1  216.23  5152.4   216.4  5188.8  215.17  5223.6  214.49
  5230.3  215.24  5251.2  214.01  5308.1  215.26  5428.6  222.64  5580.2  234.92
#Mann= 5 ,-1 , 0
  4636.5     .17       0  4965.4     .15       0  4968.2     .09       0
 5015.68     .15       0  5188.8     .17       0
#XS Ineff= 2 , 0
       0  4897.9  219.36               0
Permanent Ineff=
       F       F
Bank Sta=4968.2,5015.68
XS Rating Curve= 0 ,0
Exp/Cntr=0.3,0.1

Type RM Length L Ch R = 1 ,6000    ,500,500,500
BEGIN DESCRIPTION:
BROWN BRANCH 12.0
END DESCRIPTION:
XS GIS Cut Line= 3
      3789922.34     10189281.17      3789694.02     10189697.24
      3789651.98     10190046.22
#Sta/Elev= 30
  4525.4  240.03  4565.6  234.72  4616.5  229.52  4734.3  220.83  4799.7  214.09
  4837.6  213.49  4859.4  214.37  4890.3  213.86    4919     215  4970.1  214.46
  4978.7  212.53  4984.4   212.7    4993  211.09  4997.1  207.94  5004.4  208.44
  5009.3  211.45  5014.4  209.74  5054.2  213.84  5096.5  214.05  5114.7  215.29
  5134.8   216.9  5173.5  222.13  5178.5     222  5205.3  225.93  5245.6   229.4
  5260.6  229.81  5275.8  231.62  5342.7  234.31  5347.8  233.79  5351.5  234.75
#Mann= 3 , 0 , 0
  4525.4     .15       0  4970.1     .09       0  5054.2     .17       0
Bank Sta=4970.1,5054.2
XS Rating Curve= 0 ,0
Exp/Cntr=0.3,0.1

Type RM Length L Ch R = 1 ,5500    ,500,500,500
BEGIN DESCRIPTION:
BROWN BRANCH 11.0
END DESCRIPTION:
XS GIS Cut Line= 3
      3789417.85     10188911.09      3789341.45     10189435.45
      3788817.85     10189811.08
#Sta/Elev= 30
  4470.1  247.92  4610.7   233.5  4692.4  225.33  4813.7  217.03  4894.5  209.72
  4914.7  211.86  4975.4  212.65  4985.3  209.21  4990.4  209.63  4993.1  206.04
    5000  206.54  5005.8  209.24    5029  209.86    5050  212.54  5078.3  212.85
  5101.5  210.46  5127.5  211.31  5150.7  209.09  5171.6  212.29  5186.3  212.26
  5207.2  209.19  5221.9  212.22  5228.1  211.06  5236.7  212.62  5263.7  212.08
    5373  223.13  5521.6  233.34  5530.2  231.79  5580.5  236.55  5644.4  237.06
#Mann= 5 ,-1 , 0
  4470.1     .17       0  4610.7     .15       0  4975.4     .09       0
    5050     .15       0  5101.5     .17       0
Bank Sta=4975.4,5050
XS Rating Curve= 0 ,0
Exp/Cntr=0.3,0.1

Type RM Length L Ch R = 1 ,5000    ,474,474,474
BEGIN DESCRIPTION:
BROWN BRANCH 10.0
END DESCRIPTION:
XS GIS Cut Line= 3
      3789217.83     10188861.11        3788979.     10189206.96
      3788767.87     10189611.03
#Sta/Elev= 30
  4579.7  246.29    4629  240.32  4724.3  232.77  4787.2  224.28  4810.6  222.57
  4837.9  218.97    4858  217.86  4903.5   212.8  4918.3  211.68  4924.4  212.14
  4939.3  209.45  4945.4  210.93  4960.2   210.4  4975.1  206.92  4981.2  207.17
  4993.9  205.45  4998.3  205.45  4999.5  208.36  5005.1  208.36  5011.8  210.92
  5014.7  210.38  5106.2  210.92  5144.3  209.61  5226.9   209.1  5232.6  209.86
  5276.7   209.8  5337.3  214.06  5365.7  218.31  5403.6  222.47  5455.9   230.2
#Mann= 5 ,-1 , 0
  4579.7     .17       0    4858     .15       0  4960.2     .09       0
  5011.8     .15       0  5014.7     .17       0
Bank Sta=4960.2,5011.8
XS Rating Curve= 0 ,0
Exp/Cntr=0.3,0.1

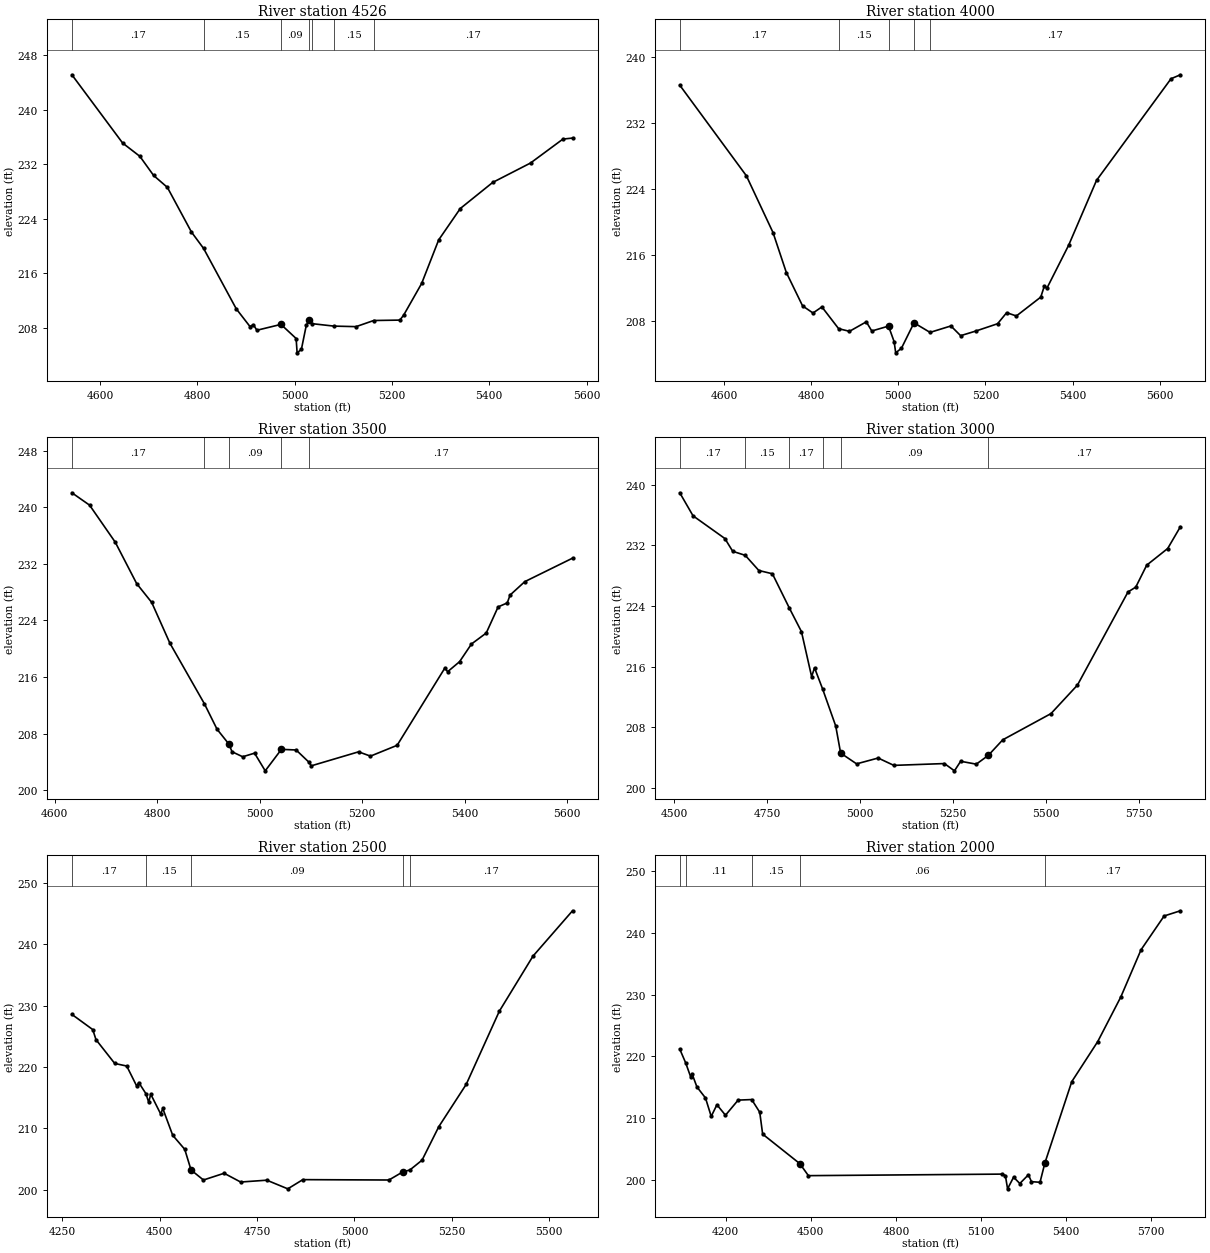
Type RM Length L Ch R = 1 ,4526    ,526,526,526
BEGIN DESCRIPTION:
BROWN BRANCH 9.0
END DESCRIPTION:
XS GIS Cut Line= 3
      3788969.35     10188705.06       3788645.8     10189028.64
      3788385.63     10189537.04
#Sta/Elev= 30
  4542.4  245.11  4646.7   235.1  4682.1  233.15  4710.3  230.35  4738.6   228.6
  4788.1  222.05  4813.1  219.64  4880.1   210.8  4908.3   208.2  4915.4  208.47
  4922.5  207.65    4972  208.51  5003.2  206.44  5005.2  204.34    5014  204.85
    5024  208.36  5029.6   209.1  5035.7  208.62  5080.7  208.26  5126.3  208.18
  5162.6  209.08  5216.2  209.14  5223.9  209.84  5261.1  214.51  5296.1   220.9
  5340.5   225.5  5407.2  229.33  5484.8  232.17  5551.4  235.68  5571.1  235.83
#Mann= 7 ,-1 , 0
  4542.4     .17       0  4813.1     .15       0    4972     .09       0
  5029.6     .15       0  5035.7     .17       0  5080.7     .15       0
  5162.6     .17       0
Bank Sta=4972,5029.6
XS Rating Curve= 0 ,0
Exp/Cntr=0.3,0.1

Type RM Length L Ch R = 1 ,4000    ,500,500,500
BEGIN DESCRIPTION:
BROWN BRANCH 8.0
END DESCRIPTION:
XS GIS Cut Line= 3
      3788417.84     10188311.11      3788320.52     10188803.18
      3787817.88     10189211.05
#Sta/Elev= 30
  4498.4  236.63  4651.3  225.64  4712.4  218.76    4743  213.91  4780.3  209.86
  4804.2     209  4824.6  209.74    4863   207.1  4887.9  206.78  4926.5  207.93
  4939.1  206.82  4977.5  207.41  4990.4  205.52    4994  204.17  5007.2  204.73
    5036  207.81  5072.8  206.65  5120.7  207.43    5143  206.25  5178.2  206.82
  5227.8   207.7  5248.6  209.04  5270.9  208.64  5326.9  210.93  5334.8  212.22
  5341.3  212.04  5390.8  217.21  5454.8  225.08  5625.8  237.41  5647.3  237.89
#Mann= 5 ,-1 , 0
  4498.4     .17       0    4863     .15       0  4977.5     .09       0
    5036     .15       0  5072.8     .17       0
Bank Sta=4977.5,5036
XS Rating Curve= 0 ,0
Exp/Cntr=0.3,0.1

Type RM Length L Ch R = 1 ,3500    ,500,500,500
BEGIN DESCRIPTION:
BROWN BRANCH 7.0
END DESCRIPTION:
XS GIS Cut Line= 3
      3788346.06     10188242.25      3788050.86     10188458.95
       3787803.1      10189016.7
#Sta/Elev= 30
  4633.8  242.05  4668.3   240.3  4718.4  235.06  4760.2   229.2  4789.5  226.54
    4825  220.77  4892.4  212.19  4916.9  208.61    4940  206.51  4946.2  205.42
    4967  204.71  4990.1  205.22  5010.9  202.72  5042.5  205.76  5071.2  205.67
  5095.5  203.99  5100.8  203.43    5193  205.41  5216.2   204.8  5268.2  206.33
  5361.3  217.26  5366.7  216.74    5390  218.16  5413.2  220.66    5442  222.21
  5465.2  225.91    5483  226.47  5488.5  227.58  5517.2  229.48  5610.3   232.8
#Mann= 5 ,-1 , 0
  4633.8     .17       0  4892.4     .15       0    4940     .09       0
  5042.5     .15       0  5095.5     .17       0
Bank Sta=4940,5042.5
XS Rating Curve= 0 ,0
Exp/Cntr=0.3,0.1

Type RM Length L Ch R = 1 ,3000    ,500,500,500
BEGIN DESCRIPTION:
BROWN BRANCH 6.0
END DESCRIPTION:
XS GIS Cut Line= 3
      3788031.44     10187914.11      3787657.67     10188223.17
      3786958.52     10188728.58
#Sta/Elev= 30
    4515  238.91  4550.8  235.87  4636.4  232.88  4657.6  231.19  4691.3  230.66
  4727.9  228.66  4764.4  228.23  4810.4  223.67  4842.6   220.6    4870  214.66
  4877.8  215.83  4899.4  213.06  4934.9  208.15  4948.1  204.58  4991.1  203.16
  5049.1  203.93  5091.3  202.96  5227.5   203.2  5254.5  202.24  5271.2   203.5
  5313.3  203.12 5345.67  204.28  5384.5  206.33  5514.4  209.79  5585.6  213.55
  5721.7  225.83  5742.6  226.47    5772  229.36  5828.5  231.56  5862.7  234.43
#Mann= 6 ,-1 , 0
    4515     .17       0  4691.3     .15       0  4810.4     .17       0
  4899.4     .15       0  4948.1     .09       0 5345.67     .17       0
Bank Sta=4948.1,5345.67
XS Rating Curve= 0 ,0
Exp/Cntr=0.3,0.1

Type RM Length L Ch R = 1 ,2500    ,500,500,500
BEGIN DESCRIPTION:
BROWN BRANCH 5.0
END DESCRIPTION:
XS GIS Cut Line= 3
      3787876.15     10187809.14      3787192.42     10188052.06
      3786842.12     10188488.85
#Sta/Elev= 30
  4274.4  228.59    4328  226.11  4336.3  224.47  4384.4  220.59  4415.2  220.17
  4440.8  216.91  4446.1  217.48  4464.6  215.65  4471.6  214.27  4476.9  215.58
  4502.5  212.34  4507.8  213.25  4533.3  208.88  4564.2  206.59  4580.4  203.22
  4612.2  201.59  4665.3  202.69  4707.7  201.26  4774.9  201.56  4828.8  200.15
  4867.4  201.65  5088.5  201.59  5123.8   202.9  5142.2  203.22  5173.5  204.82
  5216.6  210.29  5287.1   217.2  5371.9   229.1  5458.3  238.08  5559.9  245.48
#Mann= 5 ,-1 , 0
  4274.4     .17       0  4464.6     .15       0  4580.4     .09       0
  5123.8     .15       0  5142.2     .17       0
Bank Sta=4580.4,5123.8
XS Rating Curve= 0 ,0
Exp/Cntr=0.3,0.1

Type RM Length L Ch R = 1 ,2000    ,500,500,500
BEGIN DESCRIPTION:
BROWN BRANCH 4.0
END DESCRIPTION:
XS GIS Cut Line= 3
      3787867.89     10187561.07      3786912.97     10187678.42
      3786765.33     10188467.42
#Sta/Elev= 30
  4037.9  221.19  4058.9  218.95  4076.1  216.74  4081.1  217.22  4098.4  215.08
  4128.6   213.3  4148.8  210.32  4168.9   212.2  4199.1  210.51  4243.7  212.95
  4291.5  213.04  4319.9  210.99  4330.1  207.46  4461.1  202.69  4491.4  200.75
  5175.6     201  5185.8  200.76  5193.5  198.62  5214.7   200.5  5236.7  199.48
  5267.2   200.9  5277.5  199.78  5307.9  199.68    5325  202.79  5419.8  215.93
  5511.4  222.41  5592.8  229.62    5664  237.23  5745.4  242.69  5802.7  243.53
#Mann= 5 ,-1 , 0
  4037.9     .17       0  4058.9     .11       0  4291.5     .15       0
  4461.1     .06       0    5325     .17       0
Bank Sta=4461.1,5325
XS Rating Curve= 0 ,0
Exp/Cntr=0.3,0.1

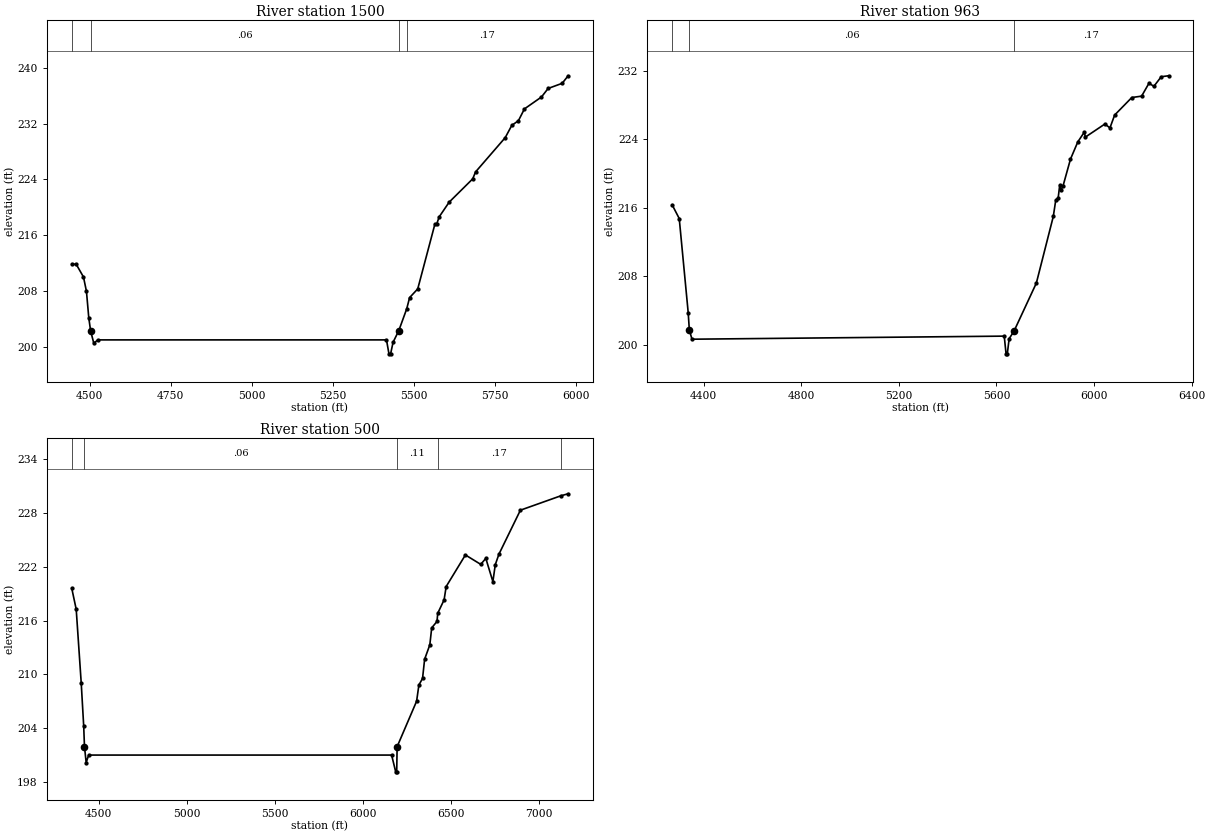
Type RM Length L Ch R = 1 ,1500    ,537,537,537
BEGIN DESCRIPTION:
BROWN BRANCH 3.0
END DESCRIPTION:
XS GIS Cut Line= 3
      3786717.86     10187011.05       3786460.6     10187502.48
      3786636.58     10188461.87
#Sta/Elev= 30
  4445.3  211.89  4459.2  211.82  4481.3  210.02  4490.5  207.96  4497.7  204.14
  4503.3   202.3  4513.1  200.52  4525.4     201  5415.4     201    5423     199
  5428.1     199  5435.7  200.66  5453.4  202.34  5477.8  205.46  5486.6  207.06
  5511.7  208.31  5564.8  217.63  5569.9  217.59  5578.1  218.66  5608.6  220.75
  5681.2  224.09  5689.9  225.08  5781.4     230  5801.7  231.76  5822.1  232.43
  5840.6  234.12  5893.2  235.83  5913.6  237.05    5957  237.79  5975.4  238.87
#Mann= 4 ,-1 , 0
  4445.3     .11       0  4503.3     .06       0  5453.4     .15       0
  5477.8     .17       0
Bank Sta=4503.3,5453.4
XS Rating Curve= 0 ,0
Exp/Cntr=0.3,0.1

Type RM Length L Ch R = 1 ,963     ,463,463,463
BEGIN DESCRIPTION:
BROWN BRANCH 2.0
END DESCRIPTION:
XS GIS Cut Line= 3
      3786317.85     10186761.08      3785937.27     10187382.27
      3786067.15     10188680.69
#Sta/Elev= 30
  4271.5  216.34  4300.5  214.74  4337.2  203.75 4341.81  201.73  4352.7  200.64
  5631.9     201  5639.4  198.93  5644.5  198.93    5652   200.7  5672.1  201.59
  5763.5   207.2  5832.9  214.98    5843   216.9    5853  217.17    5859   218.6
    5864  218.05  5873.1  218.58  5903.3  221.68  5933.4   223.7  5959.4  224.81
  5964.5  224.26    6044  225.78    6065  225.33  6084.2  226.83  6154.5  228.88
  6194.7  229.04  6224.9  230.55    6245  230.19  6275.1  231.31  6304.9  231.42
#Mann= 3 , 0 , 0
  4271.5     .11       0 4341.81     .06       0  5672.1     .17       0
Bank Sta=4341.81,5672.1
XS Rating Curve= 0 ,0
Exp/Cntr=0.3,0.1

Type RM Length L Ch R = 1 ,500     ,0,0,0
BEGIN DESCRIPTION:
BROWN BRANCH 1.0
END DESCRIPTION:
XS GIS Cut Line= 4
      3786056.71     10186604.28      3785605.22     10187076.88
      3785245.96     10187845.59      3785581.03     10189121.61
#Sta/Elev= 30
  4346.4  219.57  4371.5  217.25  4399.8  209.09    4414  204.25 4418.53  201.93
  4428.1  200.17  4442.3     201  6164.4     201  6187.5  199.13  6193.3  199.13
  6195.6  201.93  6306.3     207  6319.4  208.81  6340.1  209.54  6351.9  211.68
  6381.5  213.29  6392.2  215.18  6422.3   215.9  6426.5  216.81  6462.6   218.3
  6474.5  219.79  6583.7  223.31    6671  222.26  6699.7  222.93    6740  220.34
  6753.7  222.23  6774.4   223.4  6896.3   228.3    7127  229.91  7167.8  230.13
#Mann= 5 ,-1 , 0
  4346.4     .11       0 4418.53     .06       0  6195.6     .11       0
  6426.5     .17       0    7127     .11       0
Bank Sta=4418.53,6195.6
XS Rating Curve= 0 ,0
Exp/Cntr=0.3,0.1

Chan Stop Cuts=-1
Use User Specified Reach Order=0
Composite Channel Slope=5