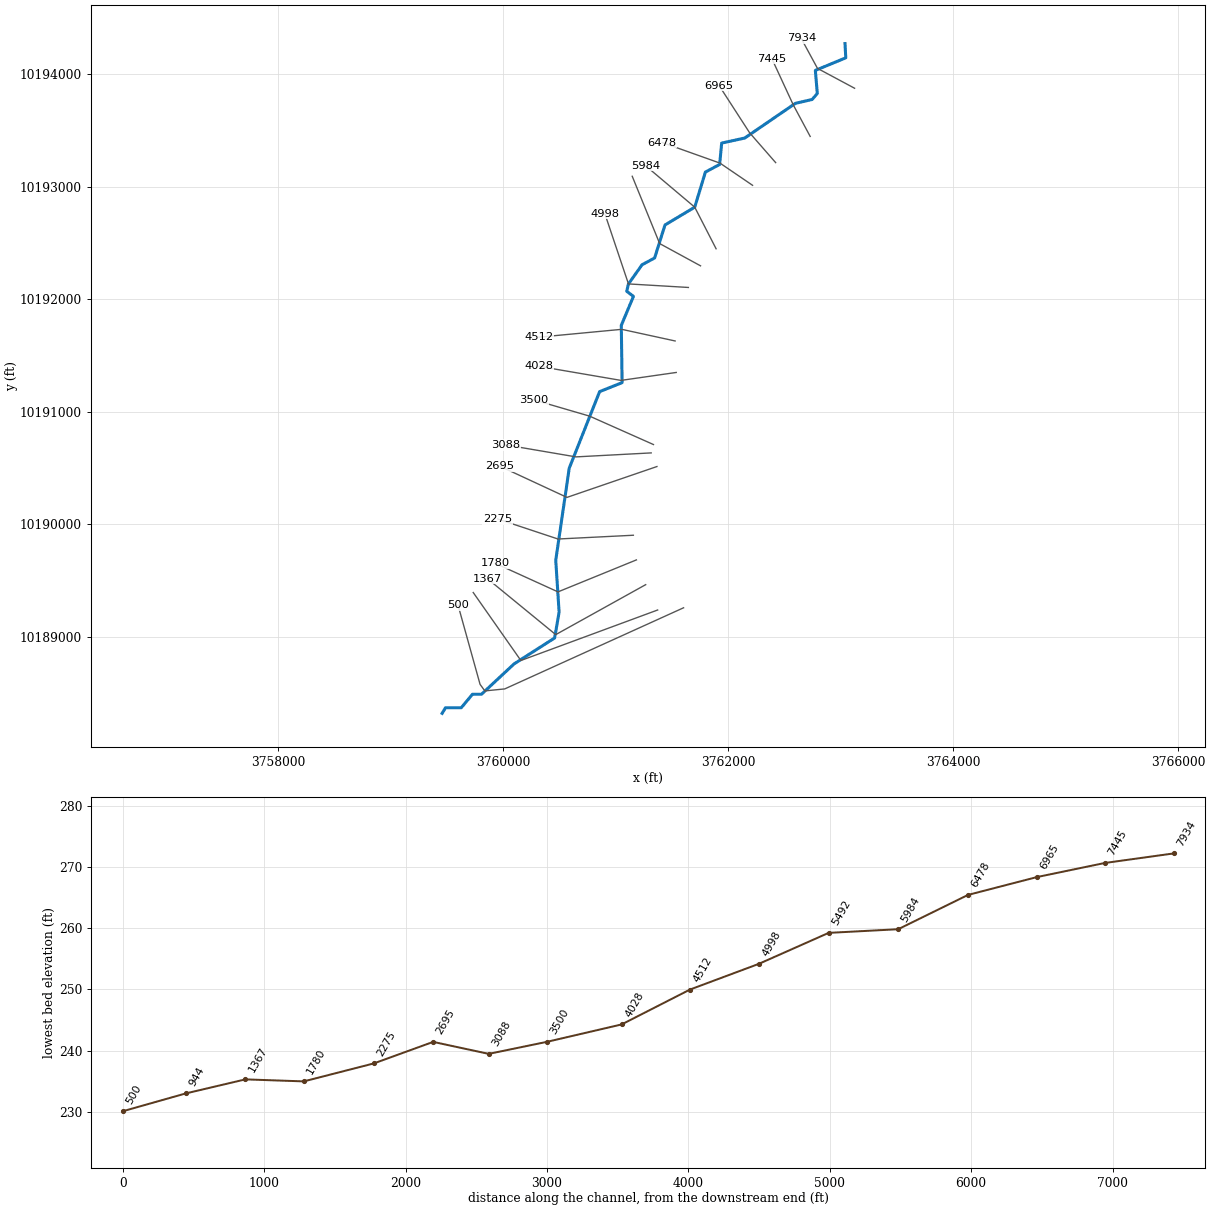
--- CANEY CREEK NORTH TRIB NO 1.prj (project) ---

Proj Title=CANEY CREEK NORTH TRIB NO 1 Base Level Engineering
Current Plan=p01
Default Exp/Contr=0.3,0.1
English Units
Geom File=g01
Flow File=f01
Flow File=f02
Plan File=p01
Y Axis Title=Elevation
X Axis Title(PF)=Main Channel Distance
X Axis Title(XS)=Station
BEGIN DESCRIPTION:
CANEY CREEK NORTH TRIB NO 1
END DESCRIPTION:
DSS Export Rating Curves= 0
DSS Export Rating Curve Sorted= 0
DSS Export Volume Flow Curves= 0
DXF OffsetX= 0
DXF OffsetY= 0
DXF ScaleX= 1
DXF ScaleY= 10

--- CANEY CREEK NORTH TRIB NO 1.p01 (plan) ---

Plan Title=Multiple Run
Short Identifier=Multiple
Geom File=g01
Flow File=f01
Subcritical Flow
K Sum by GR= 0
Std Step Tol= 0.01
Critical Tol= 0.01
Num of Std Step Trials= 20
Max Error Tol= 0.3
Flow Tol Ratio= 0.001
Split Flow NTrial= 30
Split Flow Tol= 0.02
Split Flow Ratio= 0.02
Log Output Level= 0
Friction Slope Method= 1
Unsteady Friction Slope Method= 2
Unsteady Bridges Friction Slope Method= 1
Parabolic Critical Depth
Global Vel Dist=  1 , 1 , 1
Global Log Level= 0
CheckData=True
Encroach Param= -1, 0, 0, 0
BEGIN DESCRIPTION:
Multiple Run
END DESCRIPTION:

--- CANEY CREEK NORTH TRIB NO 1.f01 (steady flow) ---

Flow Title=Multiple
Program Version=4.10
Number of Profiles= 7
Profile Names=10-year,25-year,50-year,1pct_min,100-year,1pct_plu,500-year
River Rch & RM=CANEY CREEK NORT,Reach-1         ,7934
     364     477     633     276     835    2522    1500
River Rch & RM=CANEY CREEK NORT,Reach-1         ,6965
     834    1157    1588     718    2168    6547    4178
River Rch & RM=CANEY CREEK NORT,Reach-1         ,3088
     788    1082    1478     663    2002    6046    3805
Boundary for River Rch & Prof#=CANEY CREEK NORT,Reach-1         , 1
Up Type= 0
Dn Type= 3
Dn Slope=0.0075
Boundary for River Rch & Prof#=CANEY CREEK NORT,Reach-1         , 2
Up Type= 0
Dn Type= 3
Dn Slope=0.0075
Boundary for River Rch & Prof#=CANEY CREEK NORT,Reach-1         , 3
Up Type= 0
Dn Type= 3
Dn Slope=0.0075
Boundary for River Rch & Prof#=CANEY CREEK NORT,Reach-1         , 4
Up Type= 0
Dn Type= 3
Dn Slope=0.0075
Boundary for River Rch & Prof#=CANEY CREEK NORT,Reach-1         , 5
Up Type= 0
Dn Type= 3
Dn Slope=0.0075
Boundary for River Rch & Prof#=CANEY CREEK NORT,Reach-1         , 6
Up Type= 0
Dn Type= 3
Dn Slope=0.0075
Boundary for River Rch & Prof#=CANEY CREEK NORT,Reach-1         , 7
Up Type= 0
Dn Type= 3
Dn Slope=0.0075
DSS Import GetInterval= 0
DSS Import GetPeak= 0
DSS Import FillOption= 0

--- CANEY CREEK NORTH TRIB NO 1.f02 (steady flow) ---

Flow Title=Orig_BLE_Flow
Program Version=4.10
Number of Profiles= 7
Profile Names=10-year,25-year,50-year,1pct_min,100-year,1pct_plu,500-year
River Rch & RM=CANEY CREEK NORT,Reach-1         ,7934
     364     468     550     213     642    1939     872
River Rch & RM=CANEY CREEK NORT,Reach-1         ,6965
     834    1134    1381     552    1668    5037    2429
River Rch & RM=CANEY CREEK NORT,Reach-1         ,3088
     788    1061    1285     510    1540    4652    2212
Boundary for River Rch & Prof#=CANEY CREEK NORT,Reach-1         , 1
Up Type= 0
Dn Type= 3
Dn Slope=0.0075
Boundary for River Rch & Prof#=CANEY CREEK NORT,Reach-1         , 2
Up Type= 0
Dn Type= 3
Dn Slope=0.0075
Boundary for River Rch & Prof#=CANEY CREEK NORT,Reach-1         , 3
Up Type= 0
Dn Type= 3
Dn Slope=0.0075
Boundary for River Rch & Prof#=CANEY CREEK NORT,Reach-1         , 4
Up Type= 0
Dn Type= 3
Dn Slope=0.0075
Boundary for River Rch & Prof#=CANEY CREEK NORT,Reach-1         , 5
Up Type= 0
Dn Type= 3
Dn Slope=0.0075
Boundary for River Rch & Prof#=CANEY CREEK NORT,Reach-1         , 6
Up Type= 0
Dn Type= 3
Dn Slope=0.0075
Boundary for River Rch & Prof#=CANEY CREEK NORT,Reach-1         , 7
Up Type= 0
Dn Type= 3
Dn Slope=0.0075
DSS Import GetInterval= 0
DSS Import GetPeak= 0
DSS Import FillOption= 0

--- CANEY CREEK NORTH TRIB NO 1.g01 (geometry) ---

Geom Title=Existing Conditions
Program Version=4.10

River Reach=CANEY CREEK NORT,Reach-1
Reach XY= 30
       3763039.6     10194270.99      3763046.45     10194144.29
       3762775.9     10194032.48      3762793.33     10193827.62
       3762747.5     10193773.97      3762598.54      10193739.6
      3762148.54     10193431.27      3761943.33     10193386.47
       3761925.1     10193196.37      3761798.54     10193128.66
      3761703.75     10192816.68      3761439.34     10192658.26
      3761347.15     10192365.03      3761235.78       10192305.
      3761114.68     10192134.43      3761099.06     10192069.33
      3761158.95     10192023.75      3761050.88     10191765.94
      3761058.23     10191256.84      3760858.23     10191176.84
      3760588.23     10190496.84      3760468.23     10189676.84
      3760498.23     10189216.84      3760458.23     10188986.84
      3760098.23     10188756.84      3759808.23     10188486.84
      3759728.23     10188486.84      3759628.23     10188366.84
      3759488.23     10188366.84      3759458.23     10188316.84

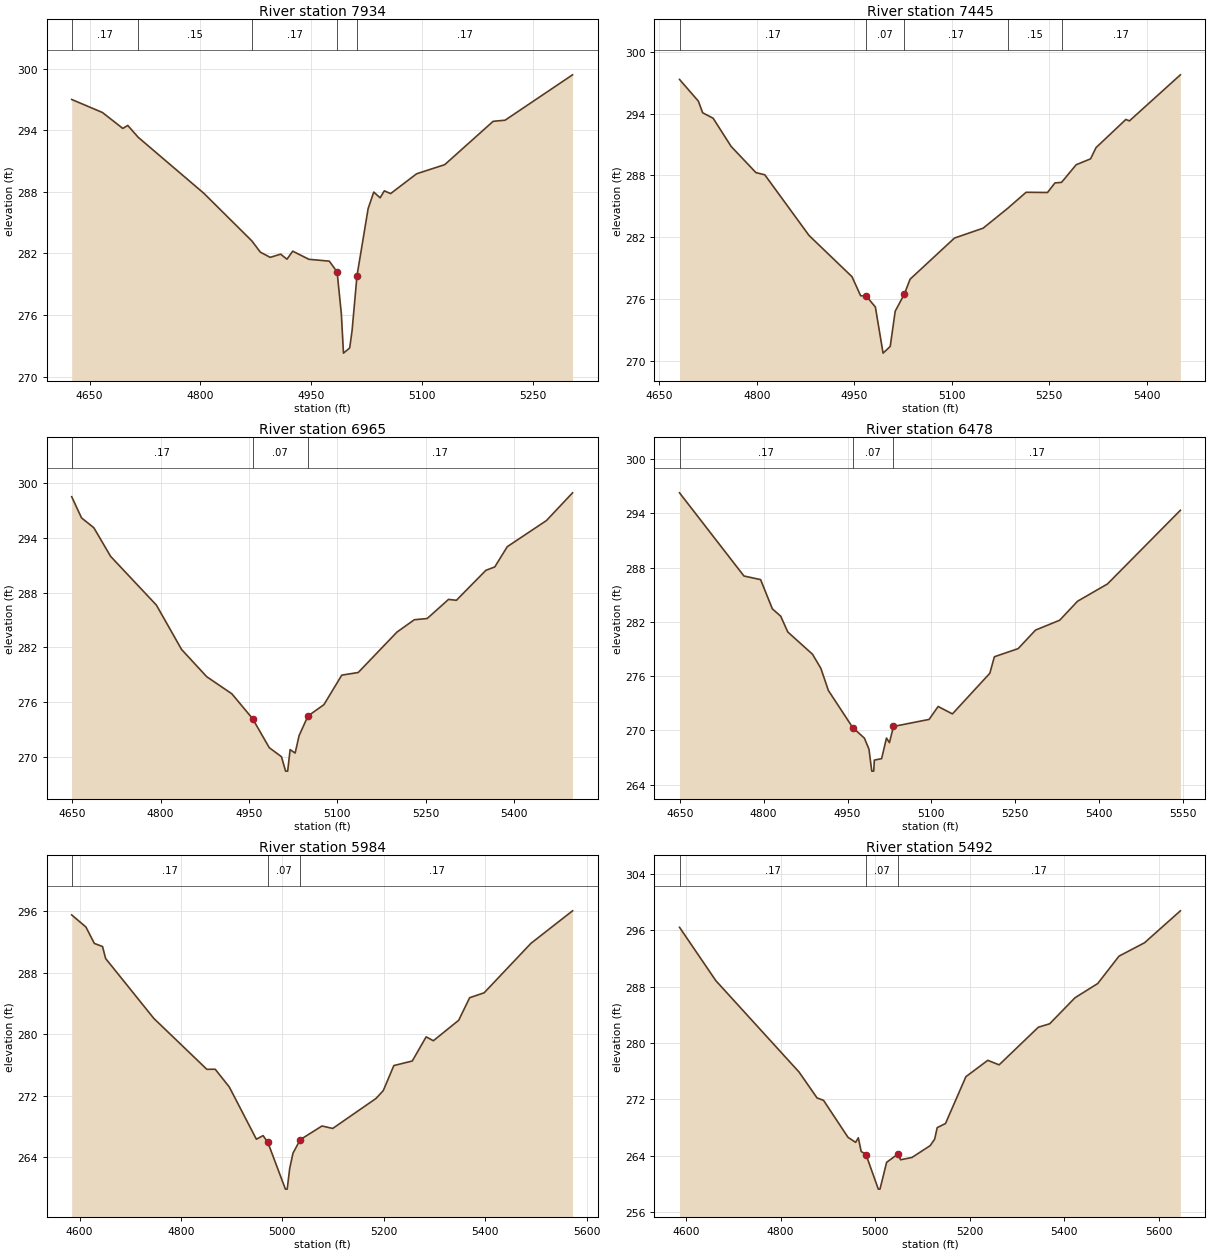
Type RM Length L Ch R = 1 ,7934    ,489,489,489
BEGIN DESCRIPTION:
CANEY CREEK NORTH TRIB NO 1 17.0
END DESCRIPTION:
XS GIS Cut Line= 3
      3763124.75     10193873.85      3762794.89     10194050.54
        3762650.     10194317.56
#Sta/Elev= 30
  4625.8     297  4667.4  295.73    4695  294.18  4701.7  294.47  4715.9  293.31
  4804.7  287.86  4869.7  283.22  4881.1  282.13  4894.5  281.62  4908.7  281.93
  4917.2  281.44    4925  282.22  4946.9  281.43  4974.5  281.25  4985.1   280.2
  4990.8  276.14  4993.7  272.29  5002.1  272.79  5005.3  274.45    5012  279.83
  5027.1  286.37  5034.7  287.98  5043.3  287.42    5049   288.1  5057.5  287.83
  5092.7  289.76  5130.8  290.65  5196.3  294.87  5212.5  294.98  5303.8   299.4
#Mann= 5 ,-1 , 0
  4625.8     .17       0  4715.9     .15       0  4869.7     .17       0
  4985.1     .07       0    5012     .17       0
#XS Ineff= 2 , 0
       0    4925  282.22               0
Permanent Ineff=
       F       F
Bank Sta=4985.1,5012
XS Rating Curve= 0 ,0
Exp/Cntr=0.3,0.1

Type RM Length L Ch R = 1 ,7445    ,480,480,480
BEGIN DESCRIPTION:
CANEY CREEK NORTH TRIB NO 1 16.0
END DESCRIPTION:
XS GIS Cut Line= 3
       3762730.1     10193445.49      3762579.27     10193726.58
      3762389.63     10194136.54
#Sta/Elev= 30
    4681  297.33    4710  295.22  4716.6  294.09  4732.7  293.56  4760.4  290.82
  4798.6  288.27  4812.2  288.06  4880.3  282.16  4946.4  278.15  4959.7   276.3
  4968.3  276.27  4982.4   275.2  4994.2  270.72  5005.2  271.37  5012.9   274.8
    5027  276.47  5035.8  277.91  5104.1  281.91  5148.2  282.87    5186   284.8
  5214.3  286.36  5247.3  286.34  5258.7  287.27  5268.8  287.32  5291.4  289.04
  5313.5  289.61  5321.9   290.7  5367.8  293.44  5373.3   293.3  5451.7  297.78
#Mann= 5 ,-1 , 0
    4681     .17       0  4968.3     .07       0    5027     .17       0
    5186     .15       0  5268.8     .17       0
Bank Sta=4968.3,5027
XS Rating Curve= 0 ,0
Exp/Cntr=0.3,0.1

Type RM Length L Ch R = 1 ,6965    ,487,487,487
BEGIN DESCRIPTION:
CANEY CREEK NORTH TRIB NO 1 15.0
END DESCRIPTION:
XS GIS Cut Line= 3
      3762423.17     10193212.72      3762192.29      10193477.1
      3761921.03     10193896.76
#Sta/Elev= 30
    4649  298.51  4665.7  296.19  4686.6  295.11  4715.1  291.97  4792.9  286.62
  4835.6  281.76  4878.3  278.77  4921.1  276.89  4956.2  274.17  4984.6  270.98
  5005.3  269.99  5012.3  268.41  5015.8  268.41    5020  270.77  5028.5  270.39
  5035.2   272.3  5050.3  274.46  5077.4   275.7  5107.7  278.94  5135.7  279.23
  5201.4  283.66    5231  285.02  5252.8  285.15  5289.1  287.25  5302.4  287.15
  5352.5  290.44  5367.6  290.81  5388.8  293.03  5455.4   295.9  5499.7  298.94
#Mann= 3 , 0 , 0
    4649     .17       0  4956.2     .07       0  5050.3     .17       0
Bank Sta=4956.2,5050.3
XS Rating Curve= 0 ,0
Exp/Cntr=0.3,0.1

Type RM Length L Ch R = 1 ,6478    ,494,494,494
BEGIN DESCRIPTION:
CANEY CREEK NORTH TRIB NO 1 14.0
END DESCRIPTION:
XS GIS Cut Line= 3
      3762217.83     10193011.09      3761928.23     10193208.35
       3761414.6      10193391.5
#Sta/Elev= 30
  4649.6  296.27  4764.8  287.07  4794.6  286.67  4815.6  283.44  4830.5  282.63
  4843.2  280.88  4887.4  278.42  4902.4  276.85  4915.8  274.41  4959.3  270.31
  4980.2  269.14  4988.4  267.91  4993.4  265.49  4996.9  265.49    4998  266.71
    5011  266.87  5019.7  269.15    5025  268.64  5032.2  270.43  5095.9  271.21
  5112.1  272.64  5137.6  271.82  5204.5  276.31  5212.7  278.14  5255.2  279.04
  5286.3  281.09  5329.5  282.18  5361.4  284.28  5414.9  286.19  5545.3  294.34
#Mann= 3 , 0 , 0
  4649.6     .17       0  4959.3     .07       0  5032.2     .17       0
Bank Sta=4959.3,5032.2
XS Rating Curve= 0 ,0
Exp/Cntr=0.3,0.1

Type RM Length L Ch R = 1 ,5984    ,492,492,492
BEGIN DESCRIPTION:
CANEY CREEK NORTH TRIB NO 1 13.0
END DESCRIPTION:
XS GIS Cut Line= 3
      3761893.62     10192446.99      3761703.75     10192816.68
      3761266.21     10193185.74
#Sta/Elev= 30
  4584.4  295.53  4612.5  293.95  4629.1  291.82  4645.2  291.42  4651.3  289.86
  4746.4  282.07    4851  275.45  4867.5  275.46  4895.3  273.15  4948.7  266.36
  4961.9  266.83  4971.2  265.97    5006  259.87  5009.5  259.87  5014.4  262.55
  5020.9  264.54  5035.2   266.3  5078.1  268.08  5099.3  267.76  5184.7  271.66
    5199  272.68  5219.9  275.94  5256.2  276.53  5283.6  279.67  5297.9  279.17
  5347.8  281.83  5369.4  284.76    5398   285.4  5490.3  291.83  5572.4  296.06
#Mann= 3 , 0 , 0
  4584.4     .17       0  4971.2     .07       0  5035.2     .17       0
Bank Sta=4971.2,5035.2
XS Rating Curve= 0 ,0
Exp/Cntr=0.3,0.1

Type RM Length L Ch R = 1 ,5492    ,494,494,494
BEGIN DESCRIPTION:
CANEY CREEK NORTH TRIB NO 1 12.0
END DESCRIPTION:
XS GIS Cut Line= 3
      3761755.33     10192295.23      3761391.94     10192493.15
      3761148.16     10193091.28
#Sta/Elev= 30
  4586.2  296.43    4663  288.86  4839.2  275.88  4877.2  272.21  4890.8  271.88
  4942.7  266.62  4958.8  265.91  4964.5  266.56  4970.5  264.62  4980.7  264.18
  5006.8  259.27  5010.3  259.27  5024.4  263.08  5048.5  264.25  5053.9  263.44
  5077.9  263.76  5116.5  265.44    5126  266.36  5131.4     268  5148.9  268.58
  5192.1  275.23  5238.4  277.55  5262.4  276.91  5345.4  282.25  5369.4  282.74
  5422.9  286.43    5471  288.45  5516.1  292.34  5570.1  294.24  5645.9  298.77
#Mann= 3 , 0 , 0
  4586.2     .17       0  4980.7     .07       0  5048.5     .17       0
Bank Sta=4980.7,5048.5
XS Rating Curve= 0 ,0
Exp/Cntr=0.3,0.1

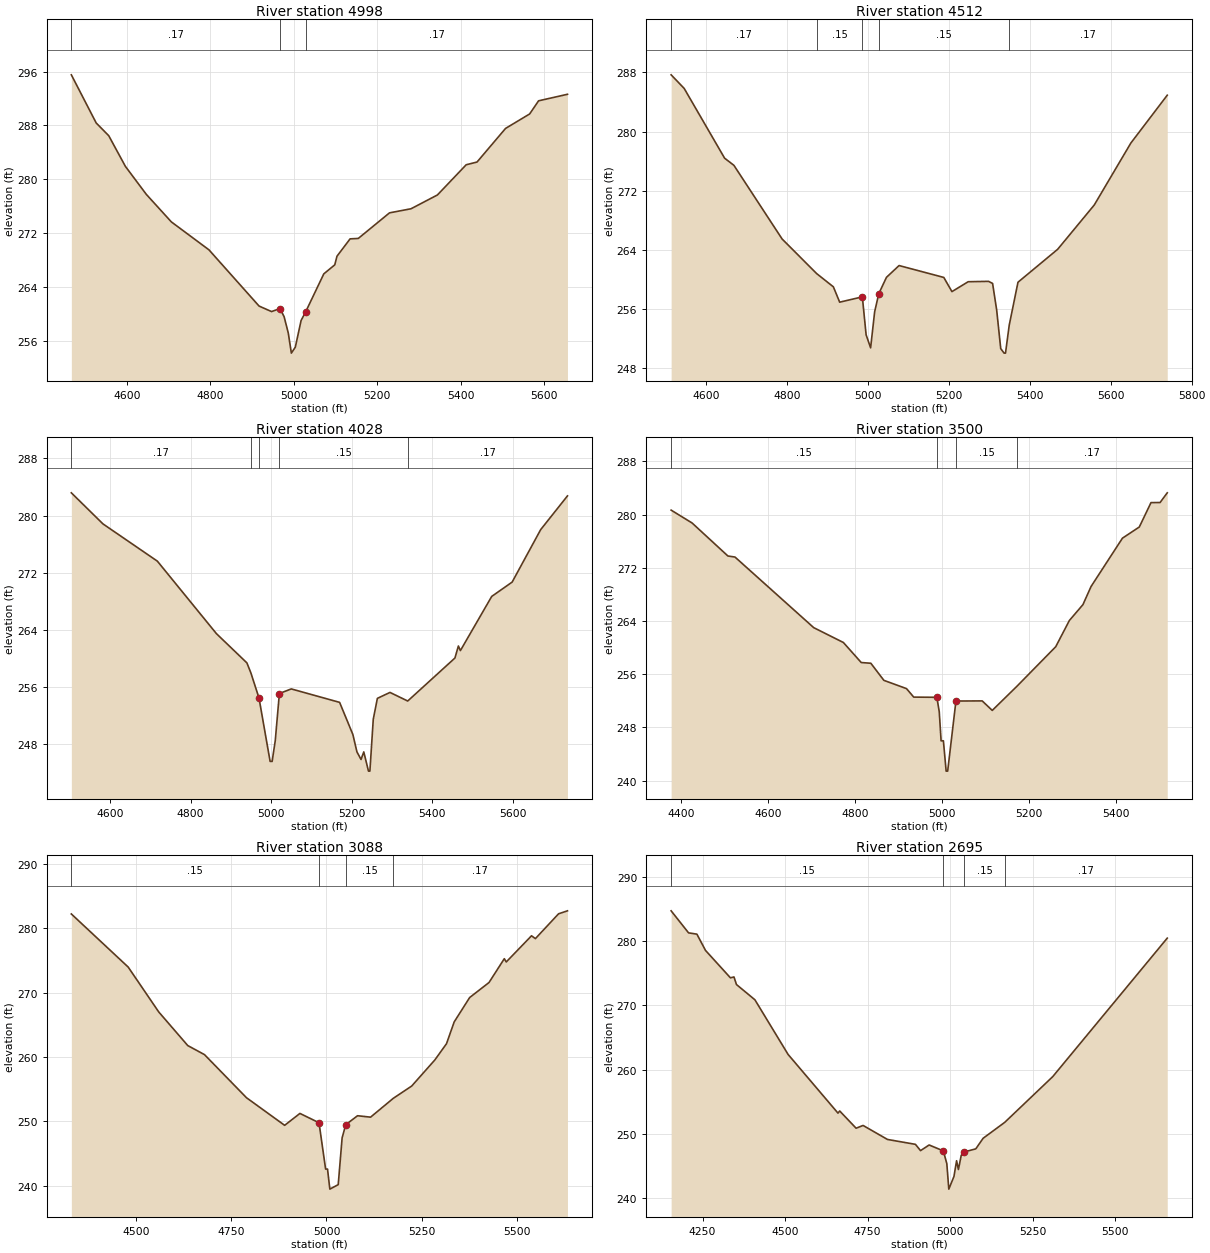
Type RM Length L Ch R = 1 ,4998    ,486,486,486
BEGIN DESCRIPTION:
CANEY CREEK NORTH TRIB NO 1 11.0
END DESCRIPTION:
XS GIS Cut Line= 3
      3761647.36     10192102.98      3761114.68     10192134.43
      3760905.51     10192756.71
#Sta/Elev= 30
  4466.4  295.52    4526  288.37  4556.1  286.48  4596.1  281.92  4646.2  277.77
  4706.3  273.68  4796.5  269.53  4916.7  261.18  4946.7  260.36  4966.8  260.81
  4976.8   259.6  4986.8  257.17  4994.2  254.19  5003.7  255.08  5017.6  259.05
  5028.1  260.27    5072  265.96  5098.3   267.3  5103.6  268.58  5135.1  271.16
  5154.7  271.22  5229.6  275.02  5281.3  275.63  5344.6  277.68  5413.5  282.16
  5439.6  282.57    5508  287.56  5565.8  289.71  5587.2  291.66  5656.5  292.63
#Mann= 3 , 0 , 0
  4466.4     .17       0  4966.8     .07       0  5028.1     .17       0
Bank Sta=4966.8,5028.1
XS Rating Curve= 0 ,0
Exp/Cntr=0.3,0.1

Type RM Length L Ch R = 1 ,4512    ,484,484,484
BEGIN DESCRIPTION:
CANEY CREEK NORTH TRIB NO 1 10.0
END DESCRIPTION:
XS GIS Cut Line= 3
      3761529.35     10191627.36      3761054.79     10191730.78
      3760318.38      10191661.1
#Sta/Elev= 30
  4514.3  287.68  4546.5  285.84  4646.4  276.39  4669.4  275.42  4788.5  265.44
    4874  260.75    4915  258.97  4930.6  256.89  4986.6  257.61  4995.9  252.47
    5007  250.71    5017  255.59  5027.1  258.02  5046.1  260.25  5077.3  261.85
  5187.8  260.24  5207.9  258.32    5248  259.66  5298.3  259.71  5308.3  259.43
  5318.4  255.82  5328.4   250.6  5336.7  249.99  5340.2  249.99  5349.4  253.78
    5371  259.59    5469  264.05  5559.4  270.05  5649.8  278.44  5739.7  284.92
#Mann= 5 ,-1 , 0
  4514.3     .17       0    4874     .15       0  4986.6     .07       0
  5027.1     .15       0  5349.4     .17       0
Bank Sta=4986.6,5027.1
XS Rating Curve= 0 ,0
Exp/Cntr=0.3,0.1

Type RM Length L Ch R = 1 ,4028    ,528,528,528
BEGIN DESCRIPTION:
CANEY CREEK NORTH TRIB NO 1 9.0
END DESCRIPTION:
XS GIS Cut Line= 3
      3761539.39      10191347.4      3761048.23     10191276.84
      3760322.32     10191401.28
#Sta/Elev= 30
  4503.8  283.17  4582.3  278.83  4717.5  273.62  4864.4  263.48    4940   259.4
  4949.9     258  4970.1  254.48  4997.7  245.63  5002.7  245.63  5010.5  248.55
  5020.7  255.12  5050.3  255.76  5170.4  253.88  5203.3  249.39  5213.4  246.96
  5223.6   245.9  5230.4  246.96  5242.1  244.27  5245.6  244.27    5254  251.53
  5264.2  254.44  5295.5  255.27  5339.6  254.07  5456.9  260.08  5465.5  261.76
  5470.5  261.12  5548.3  268.69    5599  270.69    5670  278.03  5736.5  282.74
#Mann= 5 ,-1 , 0
  4503.8     .17       0  4949.9     .15       0  4970.1     .07       0
  5020.7     .15       0  5339.6     .17       0
Bank Sta=4970.1,5020.7
XS Rating Curve= 0 ,0
Exp/Cntr=0.3,0.1

Type RM Length L Ch R = 1 ,3500    ,412,412,412
BEGIN DESCRIPTION:
CANEY CREEK NORTH TRIB NO 1 6.5
END DESCRIPTION:
XS GIS Cut Line= 3
      3761337.02     10190706.54      3760768.23     10190959.49
      3760272.03     10191104.29
#Sta/Elev= 30
  4377.5  280.67  4425.7  278.73  4507.9  273.77  4524.2  273.61  4704.9     263
  4773.1  260.76  4814.1  257.75  4836.2  257.64  4866.1  255.07    4918  253.83
  4934.7  252.55  4987.8  252.52  4993.3  250.34  4997.5  245.98  5002.8  245.98
  5009.1  241.42  5012.6  241.42  5031.6  251.96  5091.9  251.98    5115  250.55
  5171.5  254.17  5260.8  260.13  5292.1  264.07  5323.3  266.46  5341.9  269.18
    5414  276.45  5452.7  278.13  5479.6   281.8  5500.4  281.81  5516.9  283.27
#Mann= 4 ,-1 , 0
  4377.5     .15       0  4987.8     .07       0  5031.6     .15       0
  5171.5     .17       0
Bank Sta=4987.8,5031.6
XS Rating Curve= 0 ,0
Exp/Cntr=0.3,0.1

Type RM Length L Ch R = 1 ,3088    ,393,393,393
BEGIN DESCRIPTION:
CANEY CREEK NORTH TRIB NO 1 7.0
END DESCRIPTION:
XS GIS Cut Line= 3
      3761316.79     10190632.32      3760648.23     10190596.84
      3760024.93     10190703.15
#Sta/Elev= 30
  4330.5  282.23  4479.6  273.98  4559.8     267    4636  261.77  4679.9  260.36
  4790.1  253.66  4890.2  249.37  4930.3  251.22  4980.4  249.77  4997.7  242.57
  5002.7  242.57  5008.8  239.45  5030.8  240.15    5041  247.42  5050.5  249.47
  5081.5  250.86  5115.7  250.64  5175.1  253.56  5223.6  255.48  5284.4  259.54
  5314.9  262.06  5335.1  265.45  5375.7  269.24  5426.4  271.57  5466.6  275.28
  5471.7  274.77    5538  278.84  5548.2   278.4    5609  282.26  5632.3  282.72
#Mann= 4 ,-1 , 0
  4330.5     .15       0  4980.4     .07       0  5050.5     .15       0
  5175.1     .17       0
Bank Sta=4980.4,5050.5
XS Rating Curve= 0 ,0
Exp/Cntr=0.3,0.1

Type RM Length L Ch R = 1 ,2695    ,420,420,420
BEGIN DESCRIPTION:
CANEY CREEK NORTH TRIB NO 1 6.0
END DESCRIPTION:
XS GIS Cut Line= 3
      3761367.82     10190511.06      3760568.23     10190236.84
      3759971.91     10190513.81
#Sta/Elev= 30
  4154.7  284.72  4207.5  281.29  4232.8  281.09  4258.8  278.56  4334.4  274.29
    4345  274.43  4352.6  273.25  4408.4  270.88    4509  262.37  4660.1  253.24
  4665.3  253.57    4715  250.89  4736.1  251.32  4810.1  249.14  4894.7  248.38
  4910.2   247.4  4936.2  248.28  4979.3  247.36  4989.8  245.37  4995.8  241.41
  5011.4  243.38  5019.4  245.83  5024.9  244.46  5033.5  246.68  5042.3  247.19
  5077.6  247.68  5099.7  249.32  5165.2   251.8  5310.7  258.92  5657.5  280.47
#Mann= 4 ,-1 , 0
  4154.7     .15       0  4979.3     .07       0  5042.3     .15       0
  5165.2     .17       0
Bank Sta=4979.3,5042.3
XS Rating Curve= 0 ,0
Exp/Cntr=0.3,0.1

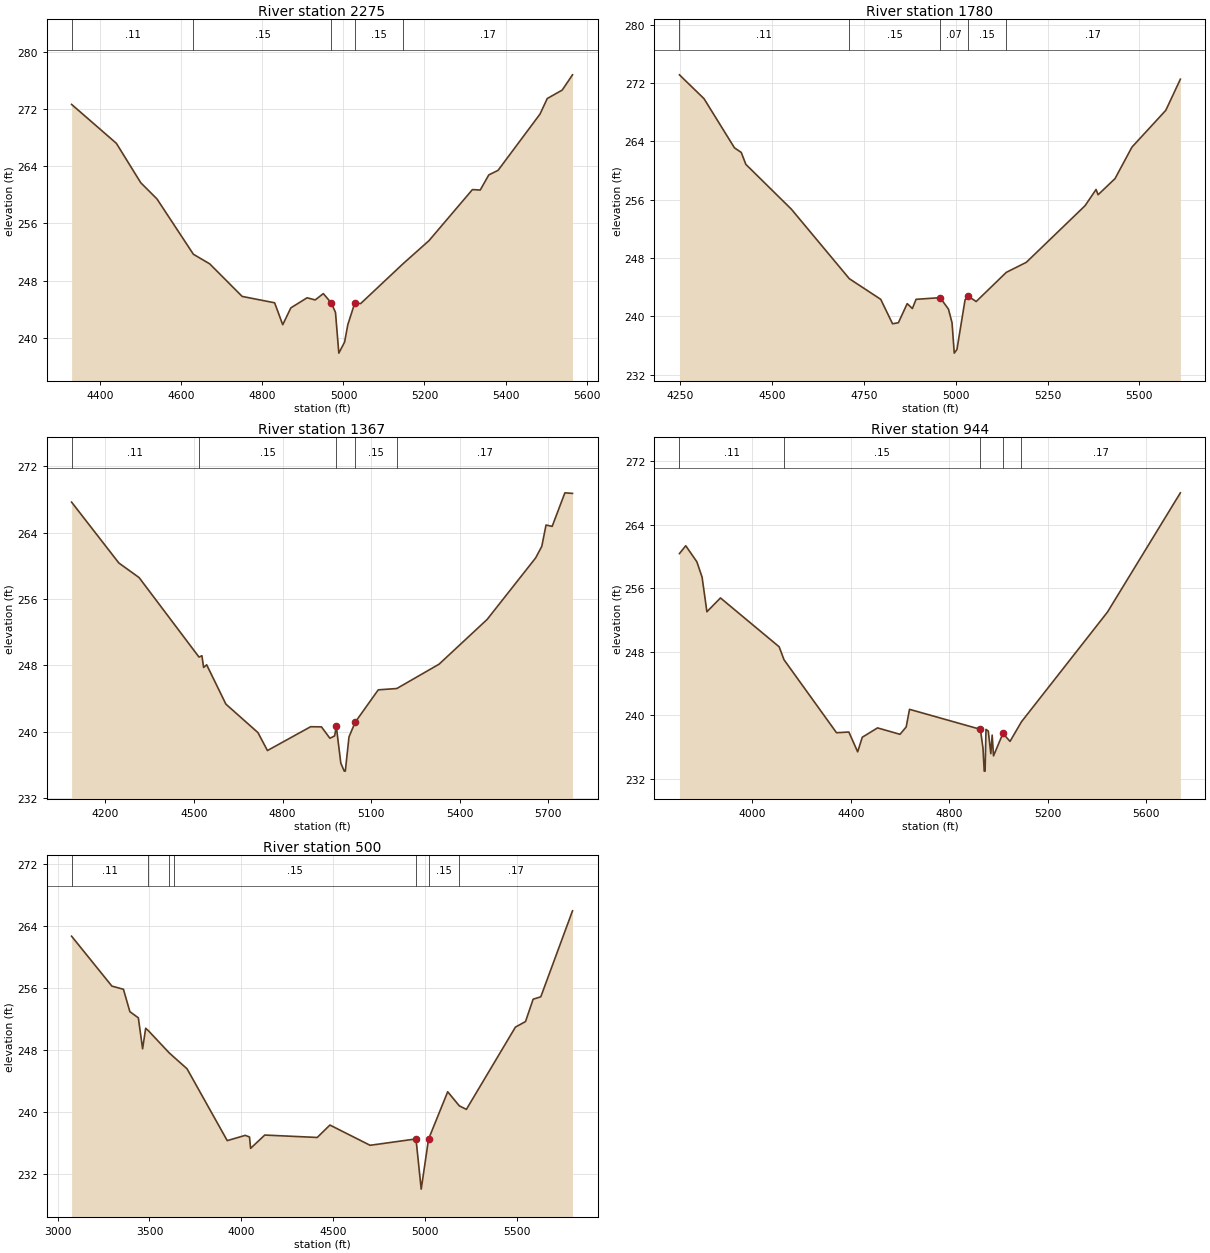
Type RM Length L Ch R = 1 ,2275    ,495,495,495
BEGIN DESCRIPTION:
CANEY CREEK NORTH TRIB NO 1 5.0
END DESCRIPTION:
XS GIS Cut Line= 3
      3761158.29     10189900.36      3760488.23     10189866.84
      3759951.76     10190045.06
#Sta/Elev= 30
  4329.1  272.62  4439.7  267.18  4499.8  261.68  4539.8  259.42  4629.7  251.69
    4670  250.35  4750.1   245.8  4830.2  244.91  4850.2  241.85  4870.2   244.2
  4910.3  245.61  4930.3  245.31  4950.3  246.19  4970.3  244.88  4980.4  243.56
  4988.6  237.88  5002.8  239.42  5010.9  241.87    5028  244.89  5042.5   244.8
  5147.8   250.4  5211.1  253.59  5318.3  260.72  5337.6  260.66  5358.7  262.77
  5381.6  263.41  5485.1  271.27    5503  273.44  5539.9  274.62  5565.3  276.75
#Mann= 5 ,-1 , 0
  4329.1     .11       0  4629.7     .15       0  4970.3     .07       0
    5028     .15       0  5147.8     .17       0
Bank Sta=4970.3,5028
XS Rating Curve= 0 ,0
Exp/Cntr=0.3,0.1

Type RM Length L Ch R = 1 ,1780    ,413,413,413
BEGIN DESCRIPTION:
CANEY CREEK NORTH TRIB NO 1 4.0
END DESCRIPTION:
XS GIS Cut Line= 3
      3761185.29     10189681.13      3760488.23     10189396.84
      3759931.69      10189650.2
#Sta/Elev= 30
  4247.2  273.12  4314.1  269.85    4397  263.11  4415.6  262.47    4428  260.84
    4552  254.69  4709.9  245.15  4795.4  242.32  4827.6  238.97  4843.5  239.11
  4867.5  241.73  4881.6  241.06  4891.6  242.32  4957.2  242.55  4979.9  240.98
  4989.6  239.11  4995.7  234.94    5003  235.44  5025.1  242.26  5033.4  242.76
  5055.4  242.02  5137.4  246.02    5192   247.4    5352  255.17  5381.9  257.39
  5387.4  256.67  5433.5  258.88  5479.6   263.2  5571.8  268.25  5611.5  272.52
#Mann= 5 ,-1 , 0
  4247.2     .11       0  4709.9     .15       0  4957.2     .07       0
  5033.4     .15       0  5137.4     .17       0
Bank Sta=4957.2,5033.4
XS Rating Curve= 0 ,0
Exp/Cntr=0.3,0.1

Type RM Length L Ch R = 1 ,1367    ,423,423,423
BEGIN DESCRIPTION:
CANEY CREEK NORTH TRIB NO 1 3.0
END DESCRIPTION:
XS GIS Cut Line= 3
      3761267.82     10189461.06      3760468.23     10189016.84
      3759862.98     10189512.49
#Sta/Elev= 30
  4085.3  267.67  4245.4  260.34  4314.1  258.58  4516.9  249.01  4526.8  249.17
  4532.6  247.76  4542.9  248.08  4608.1  243.34  4716.7  239.91  4748.8  237.75
  4895.2  240.62  4931.8   240.6  4960.4  239.23  4976.4  239.51  4982.1  240.66
  4997.4  236.23    5009  235.27  5012.6  235.27  5025.1  239.39  5045.9  241.15
  5124.2  245.06  5187.1  245.22  5330.2  248.15  5493.1  253.54  5657.4  260.95
  5678.3  262.35  5692.6  264.91  5713.4  264.75  5756.5  268.79  5782.3  268.72
#Mann= 5 ,-1 , 0
  4085.3     .11       0  4516.9     .15       0  4982.1     .07       0
  5045.9     .15       0  5187.1     .17       0
Bank Sta=4982.1,5045.9
XS Rating Curve= 0 ,0
Exp/Cntr=0.3,0.1

Type RM Length L Ch R = 1 ,944     ,444,444,444
BEGIN DESCRIPTION:
CANEY CREEK NORTH TRIB NO 1 2.0
END DESCRIPTION:
XS GIS Cut Line= 3
      3761374.17     10189235.87      3760158.23     10188786.84
      3759734.82     10189391.06
#Sta/Elev= 30
  3703.8  260.38  3729.3  261.37  3774.5  259.35  3795.8   257.4  3815.3  253.05
  3870.4  254.79  4108.8  248.63  4128.4     247  4341.6   237.8  4391.7  237.89
  4427.5  235.39  4446.1  237.23  4508.1  238.41  4599.4   237.6  4624.5  238.53
    4638  240.75  4925.8  238.23  4936.4  235.84  4941.3  232.96  4944.9  232.96
  4948.5  238.22  4957.8  238.01  4968.2  235.16  4973.6   237.5  4979.1  234.88
  5017.4  237.72  5046.1  236.71  5092.5  239.18  5441.8  253.01  5737.8  268.04
#Mann= 5 ,-1 , 0
  3703.8     .11       0  4128.4     .15       0  4925.8     .07       0
  5017.4     .15       0  5092.5     .17       0
Bank Sta=4925.8,5017.4
XS Rating Curve= 0 ,0
Exp/Cntr=0.3,0.1

Type RM Length L Ch R = 1 ,500     ,0,0,0
BEGIN DESCRIPTION:
CANEY CREEK NORTH TRIB NO 1 1.0
END DESCRIPTION:
XS GIS Cut Line= 5
      3761604.76     10189255.63       3760014.8     10188534.27
      3759837.94     10188516.55      3759795.55     10188574.75
      3759600.22     10189277.31
#Sta/Elev= 30
  3076.3  262.65  3295.5  256.22  3358.4  255.81  3393.4  252.92  3439.5  252.13
  3462.6  248.14  3479.2  250.78  3493.7  250.48  3606.6  247.63  3632.3  247.08
  3704.4  245.56  3923.1   236.3    4021  236.98  4044.1  236.77  4050.2  235.31
  4127.1  237.02  4412.6  236.71  4481.5  238.31  4700.2   235.7  4949.8  236.52
  4978.2  230.05    5018  236.49  5122.3   242.6  5185.6  240.78  5223.9  240.33
  5490.6  250.93  5545.6  251.65  5587.1  254.53  5628.7  254.84  5801.2  265.92
#Mann= 7 ,-1 , 0
  3076.3     .11       0  3493.7     .17       0  3606.6     .11       0
  3632.3     .15       0  4949.8     .06       0    5018     .15       0
  5185.6     .17       0
Bank Sta=4949.8,5018
XS Rating Curve= 0 ,0
Exp/Cntr=0.3,0.1

Chan Stop Cuts=-1
Use User Specified Reach Order=0
Composite Channel Slope=5