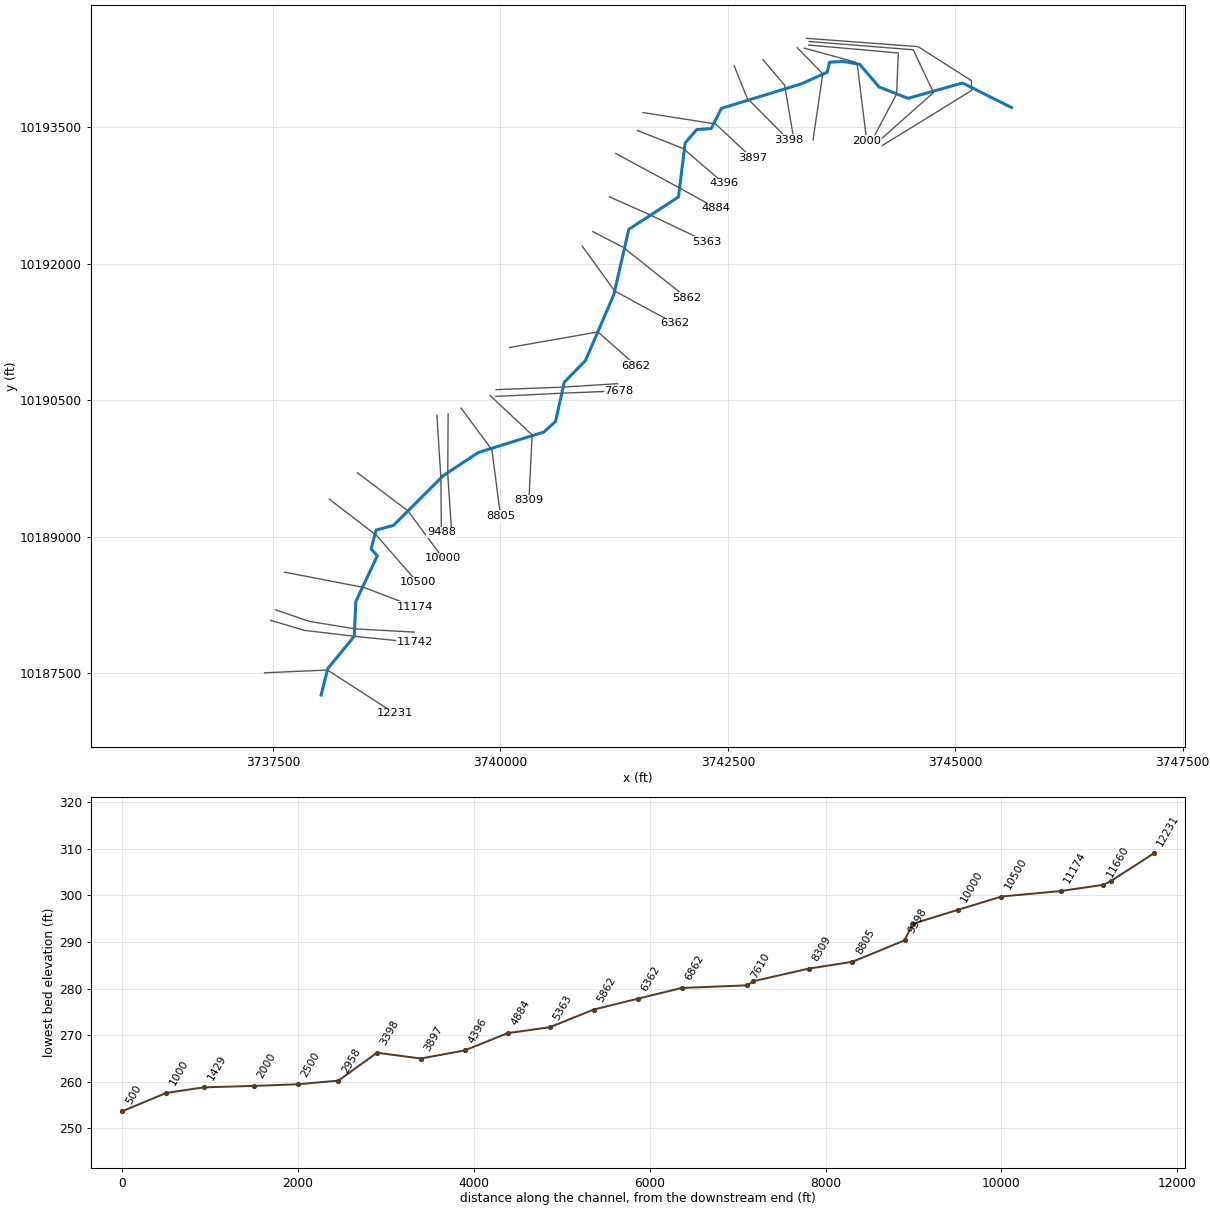
--- CANEY CREEK NORTH TRIB NO 2.prj (project) ---

Proj Title=CANEY CREEK NORTH TRIB NO 2 Base Level Engineering
Current Plan=p01
Default Exp/Contr=0.3,0.1
English Units
Geom File=g01
Flow File=f01
Flow File=f02
Plan File=p01
Y Axis Title=Elevation
X Axis Title(PF)=Main Channel Distance
X Axis Title(XS)=Station
BEGIN DESCRIPTION:
CANEY CREEK NORTH TRIB NO 2
END DESCRIPTION:
DSS Export Rating Curves= 0
DSS Export Rating Curve Sorted= 0
DSS Export Volume Flow Curves= 0
DXF OffsetX= 0
DXF OffsetY= 0
DXF ScaleX= 1
DXF ScaleY= 10

--- CANEY CREEK NORTH TRIB NO 2.p01 (plan) ---

Plan Title=Multiple Run
Short Identifier=Multiple
Geom File=g01
Flow File=f01
Subcritical Flow
K Sum by GR= 0
Std Step Tol= 0.01
Critical Tol= 0.01
Num of Std Step Trials= 20
Max Error Tol= 0.3
Flow Tol Ratio= 0.001
Split Flow NTrial= 30
Split Flow Tol= 0.02
Split Flow Ratio= 0.02
Log Output Level= 0
Friction Slope Method= 1
Unsteady Friction Slope Method= 2
Unsteady Bridges Friction Slope Method= 1
Parabolic Critical Depth
Global Vel Dist=  1 , 1 , 1
Global Log Level= 0
CheckData=True
Encroach Param= -1, 0, 0, 0
BEGIN DESCRIPTION:
Multiple Run
END DESCRIPTION:

--- CANEY CREEK NORTH TRIB NO 2.f01 (steady flow) ---

Flow Title=Multiple
Program Version=4.10
Number of Profiles= 7
Profile Names=10-year,25-year,50-year,1pct_min,100-year,1pct_plu,500-year
River Rch & RM=CANEY CREEK NORT,Reach-1         ,12231
     454     606     812     359    1083    3271    1988
River Rch & RM=CANEY CREEK NORT,Reach-1         ,11742
     867    1199    1642     739    2233    6744    4272
River Rch & RM=CANEY CREEK NORT,Reach-1         ,5862
     861    1181    1608     719    2172    6559    4099
Boundary for River Rch & Prof#=CANEY CREEK NORT,Reach-1         , 1
Up Type= 0
Dn Type= 3
Dn Slope=0.005
Boundary for River Rch & Prof#=CANEY CREEK NORT,Reach-1         , 2
Up Type= 0
Dn Type= 3
Dn Slope=0.005
Boundary for River Rch & Prof#=CANEY CREEK NORT,Reach-1         , 3
Up Type= 0
Dn Type= 3
Dn Slope=0.005
Boundary for River Rch & Prof#=CANEY CREEK NORT,Reach-1         , 4
Up Type= 0
Dn Type= 3
Dn Slope=0.005
Boundary for River Rch & Prof#=CANEY CREEK NORT,Reach-1         , 5
Up Type= 0
Dn Type= 3
Dn Slope=0.005
Boundary for River Rch & Prof#=CANEY CREEK NORT,Reach-1         , 6
Up Type= 0
Dn Type= 3
Dn Slope=0.005
Boundary for River Rch & Prof#=CANEY CREEK NORT,Reach-1         , 7
Up Type= 0
Dn Type= 3
Dn Slope=0.005
DSS Import GetInterval= 0
DSS Import GetPeak= 0
DSS Import FillOption= 0

--- CANEY CREEK NORTH TRIB NO 2.f02 (steady flow) ---

Flow Title=Orig_BLE_Flow
Program Version=4.10
Number of Profiles= 7
Profile Names=10-year,25-year,50-year,1pct_min,100-year,1pct_plu,500-year
River Rch & RM=CANEY CREEK NORT,Reach-1         ,12231
     454     594     706     276     833    2515    1156
River Rch & RM=CANEY CREEK NORT,Reach-1         ,11742
     867    1175    1428     569    1718    5188    2484
River Rch & RM=CANEY CREEK NORT,Reach-1         ,5862
     861    1158    1398     553    1671    5045    2383
Boundary for River Rch & Prof#=CANEY CREEK NORT,Reach-1         , 1
Up Type= 0
Dn Type= 3
Dn Slope=0.005
Boundary for River Rch & Prof#=CANEY CREEK NORT,Reach-1         , 2
Up Type= 0
Dn Type= 3
Dn Slope=0.005
Boundary for River Rch & Prof#=CANEY CREEK NORT,Reach-1         , 3
Up Type= 0
Dn Type= 3
Dn Slope=0.005
Boundary for River Rch & Prof#=CANEY CREEK NORT,Reach-1         , 4
Up Type= 0
Dn Type= 3
Dn Slope=0.005
Boundary for River Rch & Prof#=CANEY CREEK NORT,Reach-1         , 5
Up Type= 0
Dn Type= 3
Dn Slope=0.005
Boundary for River Rch & Prof#=CANEY CREEK NORT,Reach-1         , 6
Up Type= 0
Dn Type= 3
Dn Slope=0.005
Boundary for River Rch & Prof#=CANEY CREEK NORT,Reach-1         , 7
Up Type= 0
Dn Type= 3
Dn Slope=0.005
DSS Import GetInterval= 0
DSS Import GetPeak= 0
DSS Import FillOption= 0

--- CANEY CREEK NORTH TRIB NO 2.g01 (geometry) ---

Geom Title=Existing Conditions
Program Version=4.10

River Reach=CANEY CREEK NORT,Reach-1
Reach XY= 30
      3738028.23     10187256.84      3738100.99      10187547.5
      3738392.58     10187903.19      3738409.65      10188284.4
       3738646.6     10188789.39      3738577.99     10188861.67
      3738632.18     10189070.12      3738823.75     10189122.62
      3739370.99     10189669.43      3739756.64     10189923.69
      3740476.61     10190148.45      3740605.42     10190263.67
      3740700.95     10190695.94      3740934.42     10190934.64
       3741246.1     10191657.73      3741411.04     10192377.61
      3741957.54     10192733.06       3742030.7     10193326.78
      3742157.62      10193474.1      3742317.31     10193485.66
      3742429.32     10193707.54      3743307.15      10193976.6
      3743593.33     10194105.21      3743618.11     10194214.87
      3743767.72     10194223.32      3743950.52     10194191.26
      3744163.57     10193942.12      3744481.66     10193817.99
      3745080.97     10193986.66      3745618.23     10193716.84

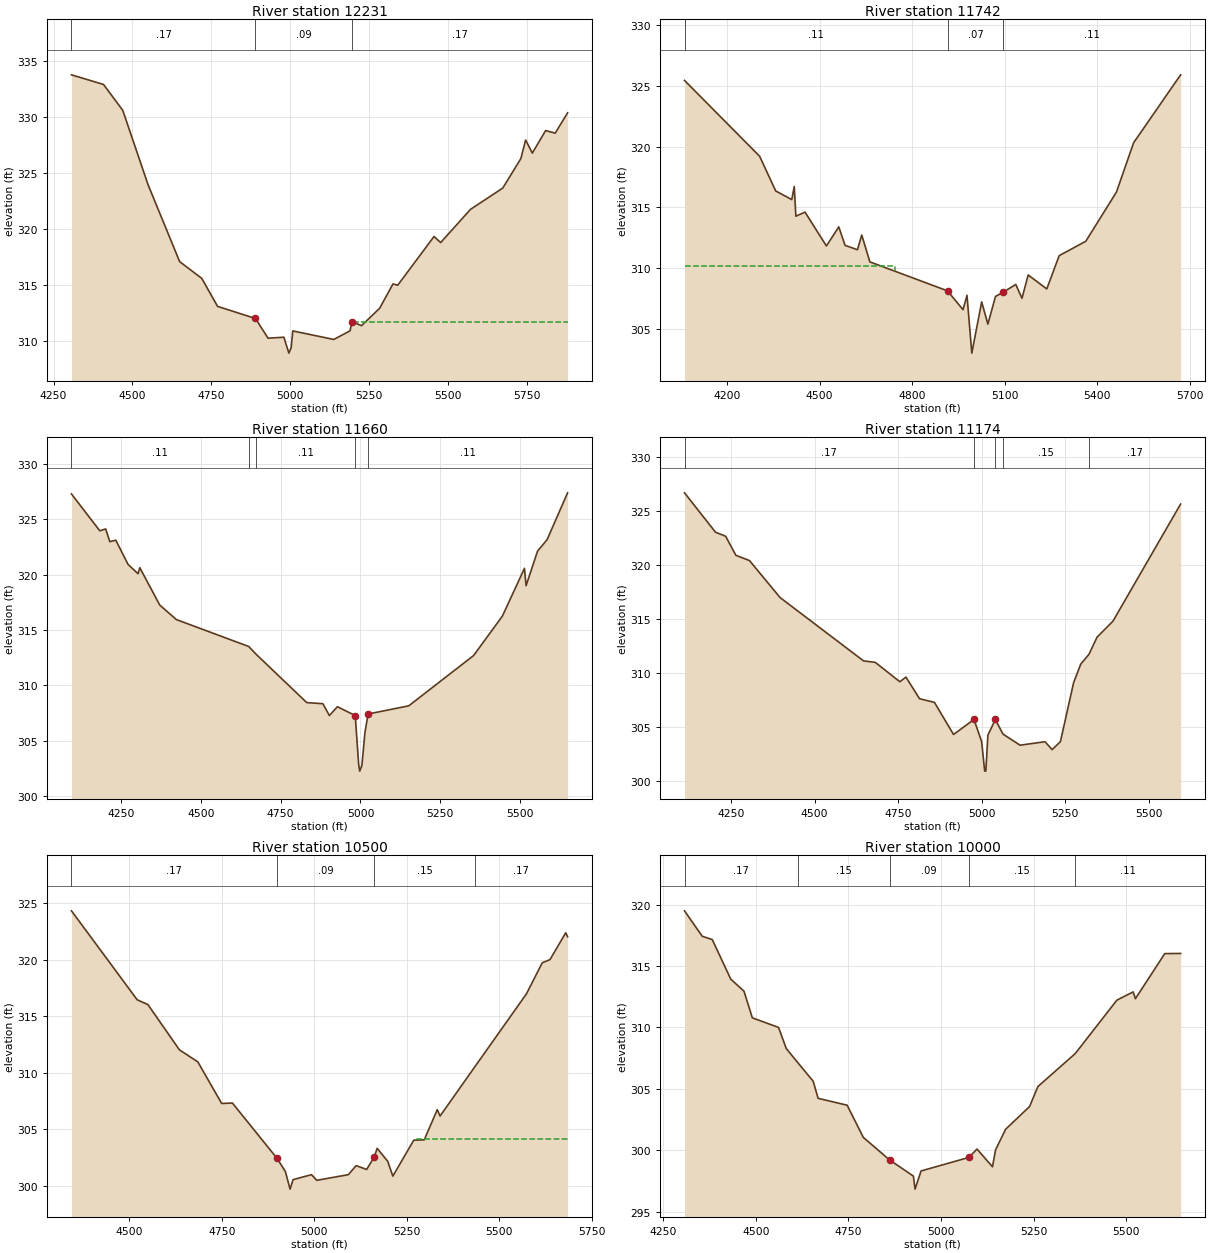
Type RM Length L Ch R = 1 ,12231   ,489,489,489
BEGIN DESCRIPTION:
CANEY CREEK NORTH TRIB NO 2 25.0
END DESCRIPTION:
XS GIS Cut Line= 3
      3737405.41     10187501.47      3738098.05     10187531.69
      3738836.37     10187055.25
#Sta/Elev= 30
  4306.7  333.78  4408.3  332.92  4469.3  330.61  4549.4  323.98  4649.5  317.12
  4719.5  315.63  4769.6  313.13  4889.7  312.05  4929.7  310.29  4979.8  310.38
  4995.6  308.96  5002.9  309.46    5008  310.94    5138  310.18  5189.5  310.95
  5195.5  311.76  5225.8  311.41  5283.2  312.96  5325.5  315.13  5340.6  315.02
  5455.5  319.36  5476.6  318.82    5571  321.78  5673.3  323.68  5730.7  326.31
  5745.8  327.97    5767   326.8  5809.2  328.81  5839.6  328.58  5878.7  330.39
#Mann= 3 , 0 , 0
  4306.7     .17       0  4889.7     .09       0  5195.5     .17       0
#XS Ineff= 2 , 0
       0                  5202.1       0  311.77
Permanent Ineff=
       F       F
Bank Sta=4889.7,5195.5
XS Rating Curve= 0 ,0
Exp/Cntr=0.3,0.1

Type RM Length L Ch R = 1 ,11742   ,82,82,82
BEGIN DESCRIPTION:
CANEY CREEK NORTH TRIB NO 2 24.0
END DESCRIPTION:
XS GIS Cut Line= 4
       3737474.3     10188078.11      3737845.05     10187968.04
      3738392.58     10187903.19      3739059.48     10187834.82
#Sta/Elev= 30
  4061.9  325.47  4305.5  319.22  4357.7  316.36  4409.8  315.65  4417.7  316.73
    4423  314.28  4452.6  314.62    4522  311.83  4562.2   313.4  4582.4  311.88
  4622.7  311.52  4636.6  312.73  4662.9  310.52  4914.7  308.13    4965  306.58
  4977.8  307.76  4993.4     303  5025.4  307.22  5045.5  305.39  5070.2  307.67
  5095.8  308.03    5136  308.66  5156.1  307.52  5176.2  309.44  5236.5  308.29
  5276.7  311.03  5363.1  312.22  5462.4  316.27    5518  320.33  5670.4  325.93
#Mann= 3 , 0 , 0
  4061.9     .11       0  4914.7     .07       0  5095.8     .11       0
#XS Ineff= 2 , 0
       0  4743.5  310.21               0
Permanent Ineff=
       F       F
Bank Sta=4914.7,5095.8
XS Rating Curve= 0 ,0
Exp/Cntr=0.3,0.1

Type RM Length L Ch R = 1 ,11660   ,486,486,486
BEGIN DESCRIPTION:
CANEY CREEK NORTH TRIB NO 2 23.0
END DESCRIPTION:
XS GIS Cut Line= 4
      3737526.43     10188193.96      3737899.11     10188066.51
      3738403.92      10187984.5      3739051.84      10187948.9
#Sta/Elev= 30
  4094.7  327.28  4183.5  323.95  4201.9  324.12  4214.8  322.97  4233.6   323.1
  4272.1  320.91  4303.4  320.07  4308.7  320.62  4371.3  317.24  4423.3  315.93
  4649.9   313.5  4673.8  312.78  4831.8  308.43  4882.4  308.33  4902.7  307.26
  4927.9  308.06  4983.7  307.26  4994.5  302.83  4997.7  302.24  5004.5  302.74
    5014  305.71    5024   307.4  5151.4  308.14  5354.5  312.68  5444.6  316.24
  5513.9  320.56  5518.9  318.99  5554.8  322.11  5584.8  323.15  5648.9  327.38
#Mann= 5 ,-1 , 0
  4094.7     .11       0  4649.9     .17       0  4673.8     .11       0
  4983.7     .07       0    5024     .11       0
Bank Sta=4983.7,5024
XS Rating Curve= 0 ,0
Exp/Cntr=0.3,0.1

Type RM Length L Ch R = 1 ,11174   ,674,674,674
BEGIN DESCRIPTION:
CANEY CREEK NORTH TRIB NO 2 22.0
END DESCRIPTION:
XS GIS Cut Line= 3
      3737626.83     10188607.81      3738500.47     10188439.03
      3739057.39      10188227.6
#Sta/Elev= 30
  4110.2  326.64  4202.9     323  4233.5  322.62    4264  320.86  4304.8  320.37
  4396.4  316.95  4646.3  311.09  4681.6  310.95    4755  309.16  4773.3  309.59
    4814  307.59  4858.6  307.25  4915.8  304.28    4977  305.67    5000  303.62
    5009  300.89  5012.5  300.89  5018.6  304.21  5040.9  305.67  5063.8  304.32
  5114.9  303.29  5189.7  303.61  5211.1  302.88  5235.8  303.62  5275.3  309.07
  5296.7  310.79  5321.3   311.7  5345.6  313.29    5393  314.76  5595.7   325.6
#Mann= 5 ,-1 , 0
  4110.2     .17       0    4977     .09       0  5040.9     .17       0
  5063.8     .15       0  5321.3     .17       0
Bank Sta=4977,5040.9
XS Rating Curve= 0 ,0
Exp/Cntr=0.3,0.1

Type RM Length L Ch R = 1 ,10500   ,500,500,500
BEGIN DESCRIPTION:
CANEY CREEK NORTH TRIB NO 2 21.0
END DESCRIPTION:
XS GIS Cut Line= 3
      3738117.82      10189411.1       3738638.5     10189011.08
      3739088.25     10188494.94
#Sta/Elev= 30
  4343.4  324.35    4521  316.48  4550.1  316.05  4635.2  312.05  4685.1  310.98
  4749.4   307.3  4778.5  307.34    4899  302.45  4921.7  301.28  4934.4  299.72
  4942.5  300.56  4992.3     301  5006.6   300.5  5092.1     301    5113   301.8
  5141.5  301.46  5162.3  302.59  5169.9  303.33  5198.4  302.18  5212.2  300.87
  5268.7  304.05  5297.1  304.08  5332.3  306.75  5339.9  306.19  5434.6  310.58
  5573.4     317  5616.1  319.75    5637  320.03  5679.7  322.41  5684.6  322.06
#Mann= 4 ,-1 , 0
  4343.4     .17       0    4899     .09       0  5162.3     .15       0
  5434.6     .17       0
#XS Ineff= 2 , 0
       0                  5276.3       0  304.17
Permanent Ineff=
       F       F
Bank Sta=4899,5162.3
XS Rating Curve= 0 ,0
Exp/Cntr=0.3,0.1

Type RM Length L Ch R = 1 ,10000   ,512,512,512
BEGIN DESCRIPTION:
CANEY CREEK NORTH TRIB NO 2 20.0
END DESCRIPTION:
XS GIS Cut Line= 3
      3738429.53     10189698.66      3738982.95     10189281.56
      3739367.83     10188761.11
#Sta/Elev= 30
    4307  319.49  4354.9  317.42    4382  317.15    4432  313.93  4467.7  312.95
  4490.3  310.78  4561.1     310  4581.9  308.28  4613.8  307.11  4654.7  305.62
    4668  304.23  4746.4  303.67  4790.1  301.05  4860.9  299.22  4925.4   297.9
  4929.9  296.84  4946.2  298.32  5075.2  299.42  5097.3   300.1    5139  298.66
  5147.4  300.04  5174.7  301.72  5239.2  303.56  5261.8  305.19  5362.6  307.87
  5475.1  312.22    5519  312.89  5525.2  312.34  5604.6  316.01  5647.3  316.02
#Mann= 5 ,-1 , 0
    4307     .17       0  4613.8     .15       0  4860.9     .09       0
  5075.2     .15       0  5362.6     .11       0
Bank Sta=4860.9,5075.2
XS Rating Curve= 0 ,0
Exp/Cntr=0.3,0.1

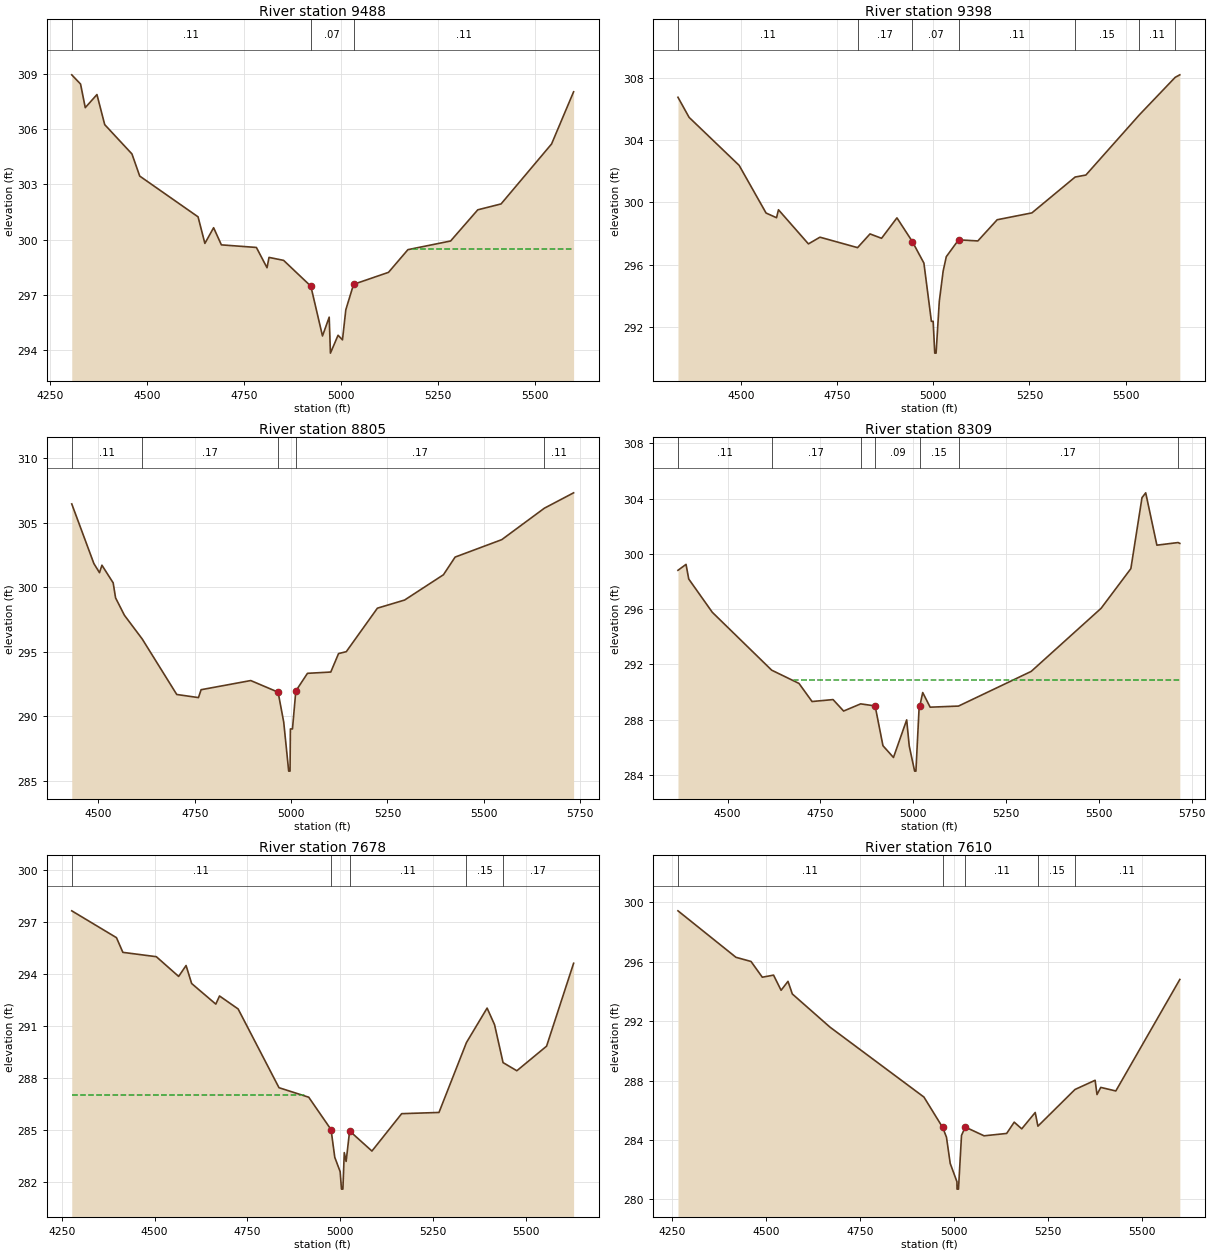
Type RM Length L Ch R = 1 ,9488    ,90,90,90
BEGIN DESCRIPTION:
CANEY CREEK NORTH TRIB NO 2 16.0
END DESCRIPTION:
XS GIS Cut Line= 3
      3739301.25     10190335.84      3739344.63      10189643.3
       3739350.5     10189044.23
#Sta/Elev= 30
  4306.1  308.94  4328.8  308.44  4340.9  307.16    4371  307.87    4391  306.24
  4461.2  304.65  4481.2  303.45  4631.5  301.24  4649.1   299.8  4671.6  300.65
  4691.6  299.72  4781.8  299.58  4809.2  298.48  4814.3  299.04  4851.9  298.88
  4922.1  297.48  4952.1  294.78  4969.4   295.8  4972.6  293.85  4992.2  294.82
  5003.6  294.57  5012.2   296.2  5032.2  297.58  5122.2  298.23  5172.2  299.46
  5282.2  299.93  5352.2  301.62  5412.2  301.94  5542.3  305.19  5599.1  308.02
#Mann= 3 , 0 , 0
  4306.1     .11       0  4922.1     .07       0  5032.2     .11       0
#XS Ineff= 2 , 0
       0  4814.3  299.04  5182.2       0  299.52
Permanent Ineff=
       F       F
Bank Sta=4922.1,5032.2
XS Rating Curve= 0 ,0
Exp/Cntr=0.3,0.1

Type RM Length L Ch R = 1 ,9398    ,593,593,593
BEGIN DESCRIPTION:
CANEY CREEK NORTH TRIB NO 2 15.0
END DESCRIPTION:
XS GIS Cut Line= 3
      3739424.44     10190349.94      3739420.37     10189686.95
      3739463.16     10189047.58
#Sta/Elev= 30
    4337  306.75  4365.9  305.46  4495.9  302.38  4565.9  299.32  4593.1  299.02
  4598.1  299.53  4675.9  297.34  4705.9  297.77  4803.6   297.1  4835.9  297.98
  4865.9   297.7  4905.9  299.01  4945.9  297.49  4975.9  296.11  4995.4  292.37
    5000  292.37  5004.1  290.33  5007.6  290.33  5015.9  293.65  5025.9  295.59
  5034.1  296.52    5066   297.6  5116.1  297.53  5166.3  298.89  5256.5  299.33
  5368.8  301.63  5396.8  301.76  5535.6  305.62  5628.8  308.03  5640.8  308.19
#Mann= 7 ,-1 , 0
    4337     .11       0  4803.6     .17       0  4945.9     .07       0
    5066     .11       0  5368.8     .15       0  5535.6     .11       0
  5628.8     .17       0
#XS Ineff= 2 , 0
       0  4905.9  299.01  5166.3       0  298.89
Permanent Ineff=
       T       F
Bank Sta=4945.9,5066
XS Rating Curve= 0 ,0
Exp/Cntr=0.3,0.1

Type RM Length L Ch R = 1 ,8805    ,496,496,496
BEGIN DESCRIPTION:
CANEY CREEK NORTH TRIB NO 2 14.0
END DESCRIPTION:
XS GIS Cut Line= 3
      3739567.86     10190411.06      3739906.01     10189953.32
      3740000.48     10189226.13
#Sta/Elev= 30
  4430.9  306.44  4488.3  301.82  4502.9  301.11  4509.2  301.69  4538.4  300.32
  4544.6  299.16  4567.6  297.81  4613.8  295.97  4703.4  291.67  4759.7  291.43
  4766.6  292.04  4895.4  292.75  4966.4  291.85    4981  289.53  4993.9  285.73
  4997.4  285.73  4998.3     289  5003.7     289  5012.4  291.94  5042.6  293.31
  5103.1  293.41  5123.3  294.84  5143.4  294.99  5224.1  298.36  5294.7  298.99
  5395.5  300.95  5425.8  302.32  5546.8  303.67  5657.5  306.11  5733.3   307.3
#Mann= 5 ,-1 , 0
  4430.9     .11       0  4613.8     .17       0  4966.4     .09       0
  5012.4     .17       0  5657.5     .11       0
Bank Sta=4966.4,5012.4
XS Rating Curve= 0 ,0
Exp/Cntr=0.3,0.1

Type RM Length L Ch R = 1 ,8309    ,631,631,631
BEGIN DESCRIPTION:
CANEY CREEK NORTH TRIB NO 2 13.0
END DESCRIPTION:
XS GIS Cut Line= 3
      3739886.19     10190550.11      3740348.45     10190116.65
      3740312.84     10189399.33
#Sta/Elev= 30
  4366.3  298.81    4388  299.24  4395.3  298.18  4458.8  295.77  4618.7  291.58
  4692.3  290.62  4727.5  289.31  4784.1  289.45  4812.5  288.62  4858.5  289.14
  4897.4  288.99  4918.5  286.11  4946.8  285.26  4982.4  287.98  4989.3  286.09
  5003.8  284.27  5007.3  284.27  5015.6  288.71 5018.04  289.02  5025.6  289.96
  5045.6   288.9    5122  288.98  5317.8  291.49  5506.2  296.06  5586.3  298.93
  5616.3  304.07  5626.3  304.42  5656.4  300.63  5713.5  300.82  5718.2  300.76
#Mann= 7 ,-1 , 0
  4366.3     .11       0  4618.7     .17       0  4858.5     .15       0
  4897.4     .09       0 5018.04     .15       0    5122     .17       0
  5713.5     .15       0
#XS Ineff= 2 ,-1
  4678.1  4649.8  290.89  4692.3  4678.1  290.62
Permanent Ineff=
       F       F
Bank Sta=4897.4,5018.04
XS Rating Curve= 0 ,0
Exp/Cntr=0.3,0.1

Type RM Length L Ch R = 1 ,7678    ,68,68,68
BEGIN DESCRIPTION:
CANEY CREEK NORTH TRIB NO 2 12.0
END DESCRIPTION:
XS GIS Cut Line= 3
      3739950.29     10190540.31      3740672.33     10190575.61
      3741300.63     10190600.75
#Sta/Elev= 30
  4277.1  297.65  4397.5   296.1  4414.8  295.25  4504.9     295    4565  293.86
    4585  294.49    4600  293.45  4665.1  292.26  4675.1  292.73  4725.2  291.98
  4835.3  287.43  4915.4  286.88  4975.5  285.01  4985.5  283.41    5000  282.58
  5003.6  281.57  5007.4  281.57  5011.1  283.68  5016.1  283.17  5025.5  284.93
  5085.6  283.77  5165.7  285.93  5266.2     286  5340.2  290.04  5395.8  292.03
  5415.9  291.07  5438.8  288.88  5475.9  288.41    5556  289.83  5628.8  294.62
#Mann= 5 ,-1 , 0
  4277.1     .11       0  4975.5     .07       0  5025.5     .11       0
  5340.2     .15       0  5438.8     .17       0
#XS Ineff= 2 , 0
       0  4905.4  287.01               0
Permanent Ineff=
       F       F
Bank Sta=4975.5,5025.5
XS Rating Curve= 0 ,0
Exp/Cntr=0.3,0.1

Type RM Length L Ch R = 1 ,7610    ,748,748,748
BEGIN DESCRIPTION:
CANEY CREEK NORTH TRIB NO 2 11.0
END DESCRIPTION:
XS GIS Cut Line= 3
      3739953.53     10190615.06      3740687.12     10190642.35
      3741287.92     10190680.27
#Sta/Elev= 30
  4265.9  299.43  4420.3   296.3  4460.4  296.02  4490.4  294.96  4520.4   295.1
  4540.4  294.08  4558.8  294.68  4570.4  293.83  4670.5   291.6  4920.7  286.89
  4970.7  284.84  4980.7  284.19  4990.7  282.42  5008.6  281.19  5008.9  280.69
  5012.7  280.69  5020.8  284.31  5030.8  284.87  5080.9  284.28    5141  284.44
  5161.1   285.2  5181.1  284.75    5217  285.85  5224.2  284.93  5322.9   287.4
  5376.5  288.02  5381.5  287.06  5391.5  287.54  5431.6   287.3    5602  294.81
#Mann= 5 ,-1 , 0
  4265.9     .11       0  4970.7     .06       0  5030.8     .11       0
  5224.2     .15       0  5322.9     .11       0
Bank Sta=4970.7,5030.8
XS Rating Curve= 0 ,0
Exp/Cntr=0.3,0.1

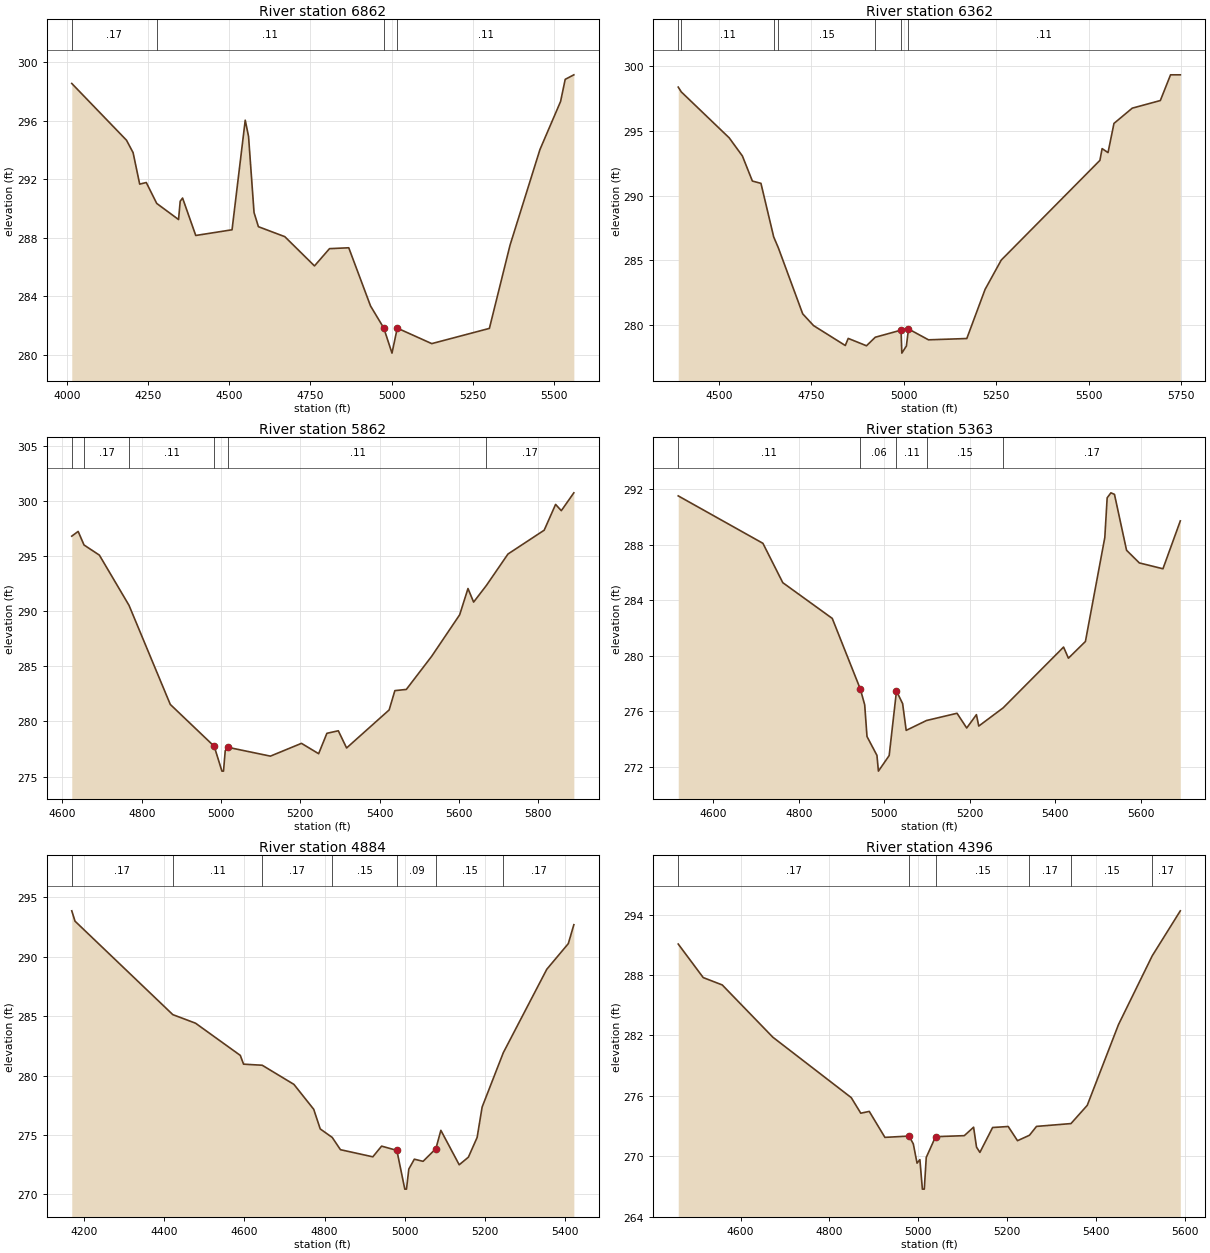
Type RM Length L Ch R = 1 ,6862    ,500,500,500
BEGIN DESCRIPTION:
CANEY CREEK NORTH TRIB NO 2 10.0
END DESCRIPTION:
XS GIS Cut Line= 3
      3740101.91     10191078.68      3741071.75      10191249.1
      3741492.49     10190878.18
#Sta/Elev= 30
  4015.3  298.55  4183.8  294.67  4204.1  293.82  4224.4  291.67  4244.7  291.78
  4276.9  290.35    4344  289.25  4349.1   290.5  4356.4  290.72    4397  288.16
  4508.7  288.55  4549.3  296.04  4559.5  294.93  4576.4  289.73  4589.9  288.76
  4671.1  288.08  4762.5  286.08  4808.7  287.26    4868  287.32  4935.1  283.34
  4975.7  281.84  5001.1  280.12  5017.3  281.83  5123.5  280.77  5300.9  281.81
  5364.5   287.5  5456.5  294.03  5520.1  297.32  5534.3  298.83  5560.9  299.14
#Mann= 4 ,-1 , 0
  4015.3     .17       0  4276.9     .11       0  4975.7     .06       0
  5017.3     .11       0
Bank Sta=4975.7,5017.3
XS Rating Curve= 0 ,0
Exp/Cntr=0.3,0.1

Type RM Length L Ch R = 1 ,6362    ,500,500,500
BEGIN DESCRIPTION:
CANEY CREEK NORTH TRIB NO 2 9.0
END DESCRIPTION:
XS GIS Cut Line= 3
      3740898.73      10192193.3      3741256.59     10191699.42
      3741913.62     10191342.11
#Sta/Elev= 30
  4390.1   298.4  4398.3  298.03    4528  294.47  4563.6  293.07  4590.6  291.13
  4613.8  290.95  4648.3   286.8  4660.7  285.97  4726.7  280.85  4756.1  279.94
  4841.9   278.4  4849.8  278.95  4899.2  278.38    4923  279.04  4992.7  279.59
  4994.8  277.81  5007.1  278.36  5012.8  279.68  5066.9  278.84  5170.5  278.94
  5219.9  282.74  5263.6  285.01  5530.5  292.73  5536.4  293.64  5552.4  293.33
  5568.5  295.59  5617.9  296.77  5693.9  297.36  5721.5  299.35  5747.9  299.35
#Mann= 7 ,-1 , 0
  4390.1     .17       0  4398.3     .11       0  4648.3     .17       0
  4660.7     .15       0    4923     .11       0  4992.7     .06       0
  5012.8     .11       0
Bank Sta=4992.7,5012.8
XS Rating Curve= 0 ,0
Exp/Cntr=0.3,0.1

Type RM Length L Ch R = 1 ,5862    ,499,499,499
BEGIN DESCRIPTION:
CANEY CREEK NORTH TRIB NO 2 8.0
END DESCRIPTION:
XS GIS Cut Line= 3
      3741015.98      10192352.1      3741350.39     10192179.34
      3742046.83     10191625.84
#Sta/Elev= 30
  4623.6   296.8  4639.7  297.23  4654.5     296  4693.2  295.08  4767.9  290.53
    4872  281.54  4982.8  277.74  5002.2  275.49  5006.2  275.49  5010.6  277.35
  5018.6  277.64  5124.5  276.85  5202.8  278.01  5246.1  277.07  5266.9  278.92
  5295.7  279.15  5316.6  277.59  5423.9  281.04  5438.3  282.79  5467.2   282.9
  5531.2  285.91  5601.7  289.67  5622.7  292.05  5636.9  290.82  5669.3  292.34
  5723.5  295.18  5814.8  297.34  5843.6  299.68    5858  299.11  5889.6  300.73
#Mann= 6 ,-1 , 0
  4623.6     .11       0  4654.5     .17       0  4767.9     .11       0
  4982.8     .06       0  5018.6     .11       0  5669.3     .17       0
#XS Ineff= 2 , 0
       0                  5295.7       0  279.15
Permanent Ineff=
       F       F
Bank Sta=4982.8,5018.6
XS Rating Curve= 0 ,0
Exp/Cntr=0.3,0.1

Type RM Length L Ch R = 1 ,5363    ,479,479,479
BEGIN DESCRIPTION:
CANEY CREEK NORTH TRIB NO 2 7.0
END DESCRIPTION:
XS GIS Cut Line= 3
      3741198.28     10192734.91      3741639.24     10192539.31
      3742264.36     10192240.89
#Sta/Elev= 30
  4517.6   291.5  4715.8  288.09  4762.3  285.26  4878.1  282.69  4943.8  277.61
    4954  276.48  4959.4   274.2  4982.7  272.84  4986.1  271.71  5011.3  272.83
  5028.4  277.47  5042.8  276.56  5051.1  274.64  5098.7  275.35  5170.1  275.87
  5192.8  274.81  5215.5  275.77    5221  274.95  5278.1  276.26  5419.5  280.63
  5430.8  279.83  5470.6  281.03    5516  288.51  5521.5  291.36  5530.3  291.72
  5538.6  291.61  5566.9  287.59  5596.8  286.68  5652.1  286.26  5692.7   289.7
#Mann= 5 ,-1 , 0
  4517.6     .11       0  4943.8     .06       0  5028.4     .11       0
  5098.7     .15       0  5278.1     .17       0
#XS Ineff= 2 , 0
       0                  5028.4       0  277.47
Permanent Ineff=
       F       T
Bank Sta=4943.8,5028.4
XS Rating Curve= 0 ,0
Exp/Cntr=0.3,0.1

Type RM Length L Ch R = 1 ,4884    ,488,488,488
BEGIN DESCRIPTION:
CANEY CREEK NORTH TRIB NO 2 6.0
END DESCRIPTION:
XS GIS Cut Line= 3
      3741267.82     10193211.09      3741999.06     10192816.09
      3742367.89     10192611.05
#Sta/Elev= 30
  4168.9  293.87    4177     293  4421.1  285.13  4477.8  284.41  4589.5   281.7
  4597.7  280.96  4644.2  280.87  4723.3  279.26  4772.8  277.16    4789  275.51
    4819  274.79  4839.5  273.76  4920.3  273.16  4942.2  274.06  4980.3   273.7
  5000.1  270.44  5004.3  270.44  5010.1  272.13  5023.9  272.96  5045.7  272.78
  5077.7  273.85  5090.1  275.39  5135.9  272.49  5158.8  273.13  5180.6  274.79
  5193.1  277.35    5246  281.93  5354.5  288.95  5408.2  291.11    5422   292.7
#Mann= 7 ,-1 , 0
  4168.9     .17       0  4421.1     .11       0  4644.2     .17       0
    4819     .15       0  4980.3     .09       0  5077.7     .15       0
    5246     .17       0
Bank Sta=4980.3,5077.7
XS Rating Curve= 0 ,0
Exp/Cntr=0.3,0.1

Type RM Length L Ch R = 1 ,4396    ,499,499,499
BEGIN DESCRIPTION:
CANEY CREEK NORTH TRIB NO 2 5.0
END DESCRIPTION:
XS GIS Cut Line= 3
       3741505.5     10193464.11      3742008.48     10193266.79
      3742456.01      10192883.4
#Sta/Elev= 30
  4459.7  291.08  4515.9  287.75  4558.7  287.02  4672.5  281.83  4848.9  275.83
  4870.4  274.28  4889.5  274.46  4924.7  271.88  4978.9  272.01  4988.6  271.23
    4997  269.32  5003.4  269.67    5009  266.74  5013.3  266.74  5017.7  269.89
  5038.7  271.95  5103.3  272.05  5124.2  272.89  5130.8  270.91  5138.4  270.39
    5167  272.86  5202.1  272.96    5223  271.55  5249.9  272.09  5265.8  272.97
  5343.3  273.25  5379.9  275.06  5450.2  283.08  5526.1  289.91  5589.3  294.38
#Mann= 6 ,-1 , 0
  4459.7     .17       0  4978.9     .09       0  5038.7     .15       0
  5249.9     .17       0  5343.3     .15       0  5526.1     .17       0
#XS Ineff= 2 , 0
       0  4889.5  274.46               0
Permanent Ineff=
       F       F
Bank Sta=4978.9,5038.7
XS Rating Curve= 0 ,0
Exp/Cntr=0.3,0.1

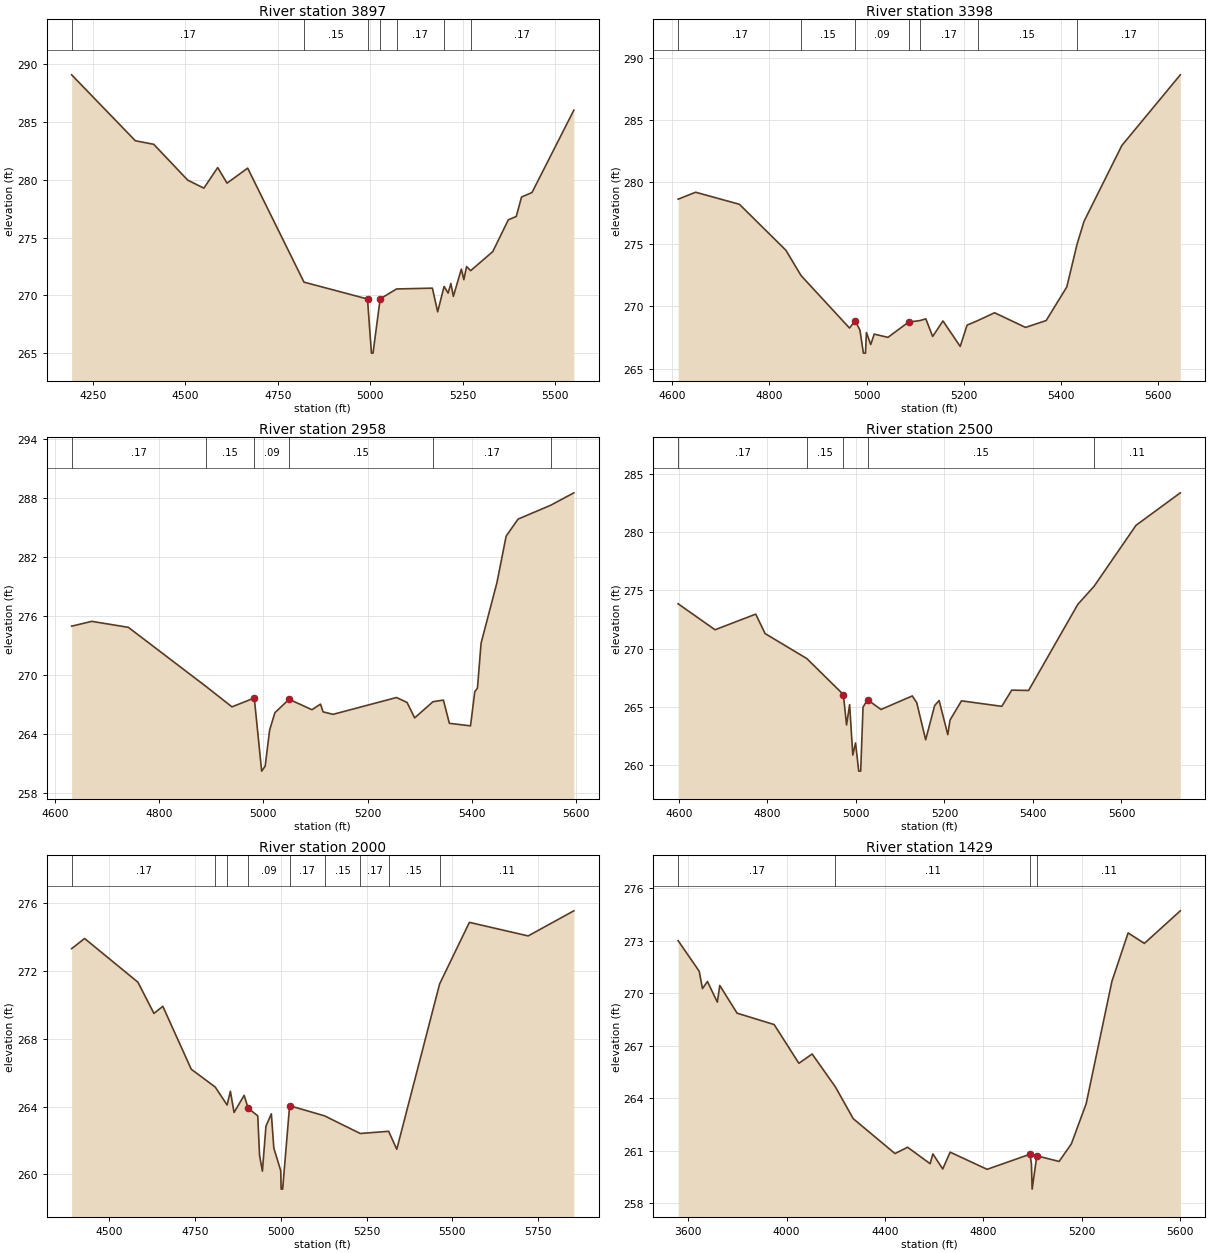
Type RM Length L Ch R = 1 ,3897    ,499,499,499
BEGIN DESCRIPTION:
CANEY CREEK NORTH TRIB NO 2 4.0
END DESCRIPTION:
XS GIS Cut Line= 3
       3741567.8     10193661.08      3742365.37      10193536.1
      3742767.83     10193161.09
#Sta/Elev= 30
  4192.7  289.07  4364.8  283.37  4414.6  283.06  4506.5  279.96  4550.1  279.27
  4587.5  281.05  4612.7   279.7  4668.5     281  4820.7  271.14  4992.4  269.68
    5003     265  5007.3     265  5026.6  269.69  5070.9  270.55  5167.8  270.62
    5182  268.57  5199.4  270.77  5210.3  270.19  5217.7  271.02  5224.5  269.91
    5246  272.27  5252.8  271.35  5260.2  272.49  5271.1  272.13    5331  273.78
    5373  276.53  5394.5  276.82  5408.7   278.5    5437  278.89  5550.1  286.01
#Mann= 7 ,-1 , 0
  4192.7     .17       0  4820.7     .15       0  4992.4     .09       0
  5026.6     .15       0  5070.9     .17       0  5199.4     .15       0
  5271.1     .17       0
Bank Sta=4992.4,5026.6
XS Rating Curve= 0 ,0
Exp/Cntr=0.3,0.1

Type RM Length L Ch R = 1 ,3398    ,440,440,440
BEGIN DESCRIPTION:
CANEY CREEK NORTH TRIB NO 2 3.0
END DESCRIPTION:
XS GIS Cut Line= 3
      3742568.91     10194178.04      3742713.02     10193818.55
      3743167.85     10193361.07
#Sta/Elev= 30
  4612.7  278.63  4648.7  279.19  4738.7  278.22  4834.3  274.52  4865.5  272.48
    4965  268.26  4976.9  268.84  4986.5  268.09  4993.6  266.24  4997.9  266.24
  4999.8   267.9  5008.7  266.93  5015.8  267.77  5044.1  267.51  5086.5  268.74
  5109.9  268.86  5121.9     269    5136  267.58  5157.2  268.83  5192.6  266.78
  5206.7  268.49  5228.2  268.85  5263.3  269.49  5326.9  268.31  5369.3  268.86
  5411.8  271.57  5432.8     275  5447.1  276.84  5524.9  282.95  5645.1  288.64
#Mann= 7 ,-1 , 0
  4612.7     .17       0  4865.5     .15       0  4976.9     .09       0
  5086.5     .15       0  5109.9     .17       0  5228.2     .15       0
  5432.8     .17       0
Bank Sta=4976.9,5086.5
XS Rating Curve= 0 ,0
Exp/Cntr=0.3,0.1

Type RM Length L Ch R = 1 ,2958    ,458,458,458
BEGIN DESCRIPTION:
CANEY CREEK NORTH TRIB NO 2 2.0
END DESCRIPTION:
XS GIS Cut Line= 3
      3742885.77     10194243.14      3743124.25     10193963.01
      3743224.21     10193375.55
#Sta/Elev= 30
  4632.1  274.99  4670.8  275.48    4741  274.87  4889.1   268.9  4939.8  266.79
  4982.6  267.69  4996.8  260.26  5003.5  260.76  5012.1  264.44  5022.2   266.2
  5049.4  267.56  5093.3   266.5  5109.7  267.07  5114.7  266.28  5133.8  266.03
  5255.6  267.74  5275.8  267.24  5290.4  265.67  5325.4  267.31  5345.6  267.48
    5357  265.12  5397.6  264.86  5405.8  268.33  5410.9  268.69  5417.9  273.27
  5448.3  279.41    5466  284.14  5488.9  285.87  5551.6  287.28  5595.9  288.54
#Mann= 6 ,-1 , 0
  4632.1     .17       0  4889.1     .15       0  4982.6     .09       0
  5049.4     .15       0  5325.4     .17       0  5551.6     .11       0
Bank Sta=4982.6,5049.4
XS Rating Curve= 0 ,0
Exp/Cntr=0.3,0.1

Type RM Length L Ch R = 1 ,2500    ,500,500,500
BEGIN DESCRIPTION:
CANEY CREEK NORTH TRIB NO 2 1.0
END DESCRIPTION:
XS GIS Cut Line= 3
      3743263.42     10194374.55      3743543.76     10194087.13
      3743436.95     10193362.06
#Sta/Elev= 30
  4598.5  273.84  4681.9  271.61  4773.8  272.95  4795.1  271.28  4889.2  269.14
  4971.8  266.05    4979  263.44  4985.9  265.19  4993.1  260.86  4999.3   261.9
  5006.5  259.48  5010.9  259.48  5016.2  264.96  5026.3  265.61  5056.7  264.77
  5127.4  265.93  5137.5  265.36  5157.7  262.17    5178  265.11  5188.1  265.54
  5207.7  262.61  5212.7  263.86  5238.6  265.51  5329.6  265.04  5352.1  266.43
  5390.2   266.4  5501.4  273.79  5538.3  275.35  5632.8  280.57  5732.9  283.36
#Mann= 5 ,-1 , 0
  4598.5     .17       0  4889.2     .15       0  4971.8     .09       0
  5026.3     .15       0  5538.3     .11       0
Bank Sta=4971.8,5026.3
XS Rating Curve= 0 ,0
Exp/Cntr=0.3,0.1

Type RM Length L Ch R = 1 ,2000    ,571,571,571
BEGIN DESCRIPTION:
CANEY CREEK NORTH TRIB NO 2 4.5
END DESCRIPTION:
XS GIS Cut Line= 4
      3743341.47     10194369.04      3743903.33     10194216.16
       3743922.1     10194196.74      3744027.24     10193349.03
#Sta/Elev= 30
  4390.7  273.31  4428.4  273.91  4583.9  271.33  4630.5  269.49  4656.4  269.91
  4739.3   266.2  4809.1  265.15  4843.7  264.09  4853.3   264.9    4864  263.65
  4893.4  264.66  4905.1   263.9  4933.1  263.45  4938.3  261.12  4946.6  260.19
  4956.9  262.84  4972.7  263.57  4979.9  261.55    5000  260.22  5001.2  259.13
  5005.6  259.13  5025.9  264.05  5127.8  263.45  5231.7  262.41  5314.5  262.54
  5338.2  261.48  5463.1  271.23  5549.8  274.86  5721.1  274.06  5854.2  275.54
#Mann= 9 ,-1 , 0
  4390.7     .17       0  4809.1     .15       0  4843.7     .17       0
  4905.1     .09       0  5025.9     .17       0  5127.8     .15       0
  5231.7     .17       0  5314.5     .15       0  5463.1     .11       0
#XS Ineff= 2 ,-1
  4853.3  4811.9   264.9  4893.4  4853.3  264.66
Permanent Ineff=
       F       F
Bank Sta=4905.1,5025.9
XS Rating Curve= 0 ,0
Exp/Cntr=0.3,0.1

Type RM Length L Ch R = 1 ,1429    ,429,429,429
BEGIN DESCRIPTION:
CANEY CREEK NORTH TRIB NO 2 3.5
END DESCRIPTION:
XS GIS Cut Line= 4
      3743389.19     10194403.77      3744374.45     10194316.96
      3744355.82     10193865.82      3744074.98     10193336.06
#Sta/Elev= 30
  3559.4     273  3645.2  271.25  3658.4  270.26  3678.5  270.67  3718.7  269.49
  3728.7  270.44    3799  268.86  3949.6  268.21    4050     266    4104  266.53
  4198.5  264.65  4270.8  262.84  4440.5  260.85  4491.7  261.21  4583.3  260.27
  4594.4  260.83  4634.4  259.97  4664.5  260.93  4814.6  259.95 4988.77  260.81
  4994.7  260.27  4997.7  258.82  5016.7  260.72  5107.2   260.4    5157   261.4
  5217.3   263.7  5321.6  270.67  5387.6  273.44  5453.6  272.84  5599.6   274.7
#Mann= 4 ,-1 , 0
  3559.4     .17       0  4198.5     .11       0 4988.77     .06       0
  5016.7     .11       0
Bank Sta=4988.77,5016.7
XS Rating Curve= 0 ,0
Exp/Cntr=0.3,0.1

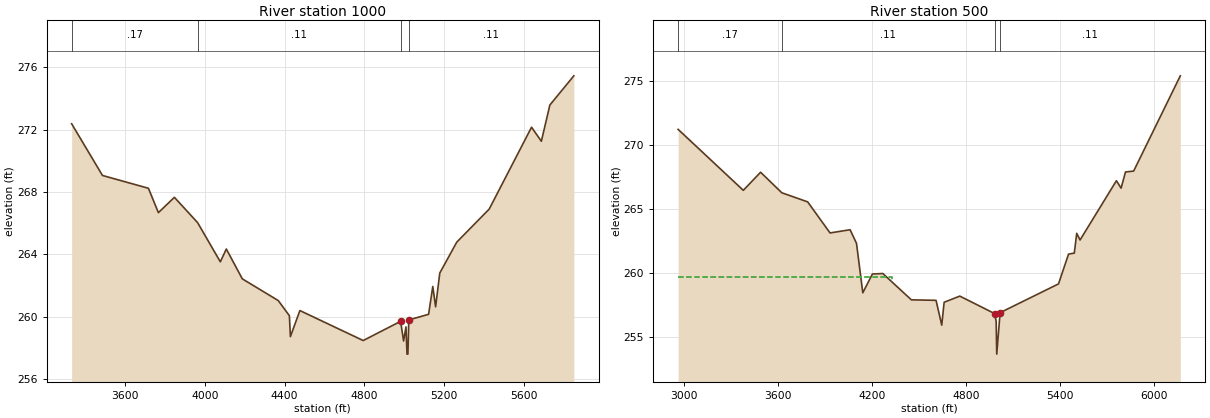
Type RM Length L Ch R = 1 ,1000    ,500,500,500
BEGIN DESCRIPTION:
CANEY CREEK NORTH TRIB NO 2 2.5
END DESCRIPTION:
XS GIS Cut Line= 4
      3743393.58     10194442.83      3744539.38     10194351.68
      3744760.88     10193880.91      3744123.74     10193315.26
#Sta/Elev= 30
  3330.3  272.37  3485.1  269.06  3715.8  268.24  3765.9  266.68  3846.2  267.66
  3962.8  266.04  4076.9  263.53    4107  264.35  4187.3  262.44  4367.8  261.05
  4423.7  260.08  4428.7  258.74  4476.4  260.41  4794.3  258.49  4982.2  259.72
  4997.1  258.46    5009  259.36  5014.3  257.62  5018.8  257.62  5023.2  259.81
  5122.7  260.17  5143.7  261.95  5157.9  260.65  5178.8  262.81  5264.1  264.79
  5427.2  266.91  5639.6  272.15  5688.9  271.25  5731.6  273.57    5852  275.44
#Mann= 4 ,-1 , 0
  3330.3     .17       0  3962.8     .11       0  4982.2     .06       0
  5023.2     .11       0
#XS Ineff= 2 , 0
       0                  5143.7       0  261.95
Permanent Ineff=
       F       F
Bank Sta=4982.2,5023.2
XS Rating Curve= 0 ,0
Exp/Cntr=0.3,0.1

Type RM Length L Ch R = 1 ,500     ,0,0,0
BEGIN DESCRIPTION:
CANEY CREEK NORTH TRIB NO 2 1.5
END DESCRIPTION:
XS GIS Cut Line= 5
      3743363.15     10194477.55      3744591.47      10194386.4
      3745177.41     10194013.14      3745180.74     10193904.32
      3744186.45     10193292.01
#Sta/Elev= 30
  2964.7  271.21  3380.5  266.46  3490.8  267.87  3626.1  266.27  3791.1  265.56
  3933.8  263.14  4061.6  263.39  4102.5  262.33  4142.6  258.48    4204  259.94
  4270.3  259.98  4452.3  257.93  4609.8  257.89  4646.2  255.96  4661.4  257.74
  4761.3  258.22  4983.2  256.86  4993.2  256.26  4996.9   253.7  5018.4  256.93
  5390.9  259.17  5454.9  261.49  5491.6  261.57    5507  263.11  5528.3  262.59
  5760.2  267.21  5790.2  266.63  5818.1  267.89  5870.2  267.96  6167.7  275.38
#Mann= 4 ,-1 , 0
  2964.7     .17       0  3626.1     .11       0  4983.2     .06       0
  5018.4     .11       0
#XS Ineff= 2 , 0
       0  4327.9  259.68               0
Permanent Ineff=
       F       F
Bank Sta=4983.2,5018.4
XS Rating Curve= 0 ,0
Exp/Cntr=0.3,0.1

Chan Stop Cuts=-1
Use User Specified Reach Order=0
Composite Channel Slope=5