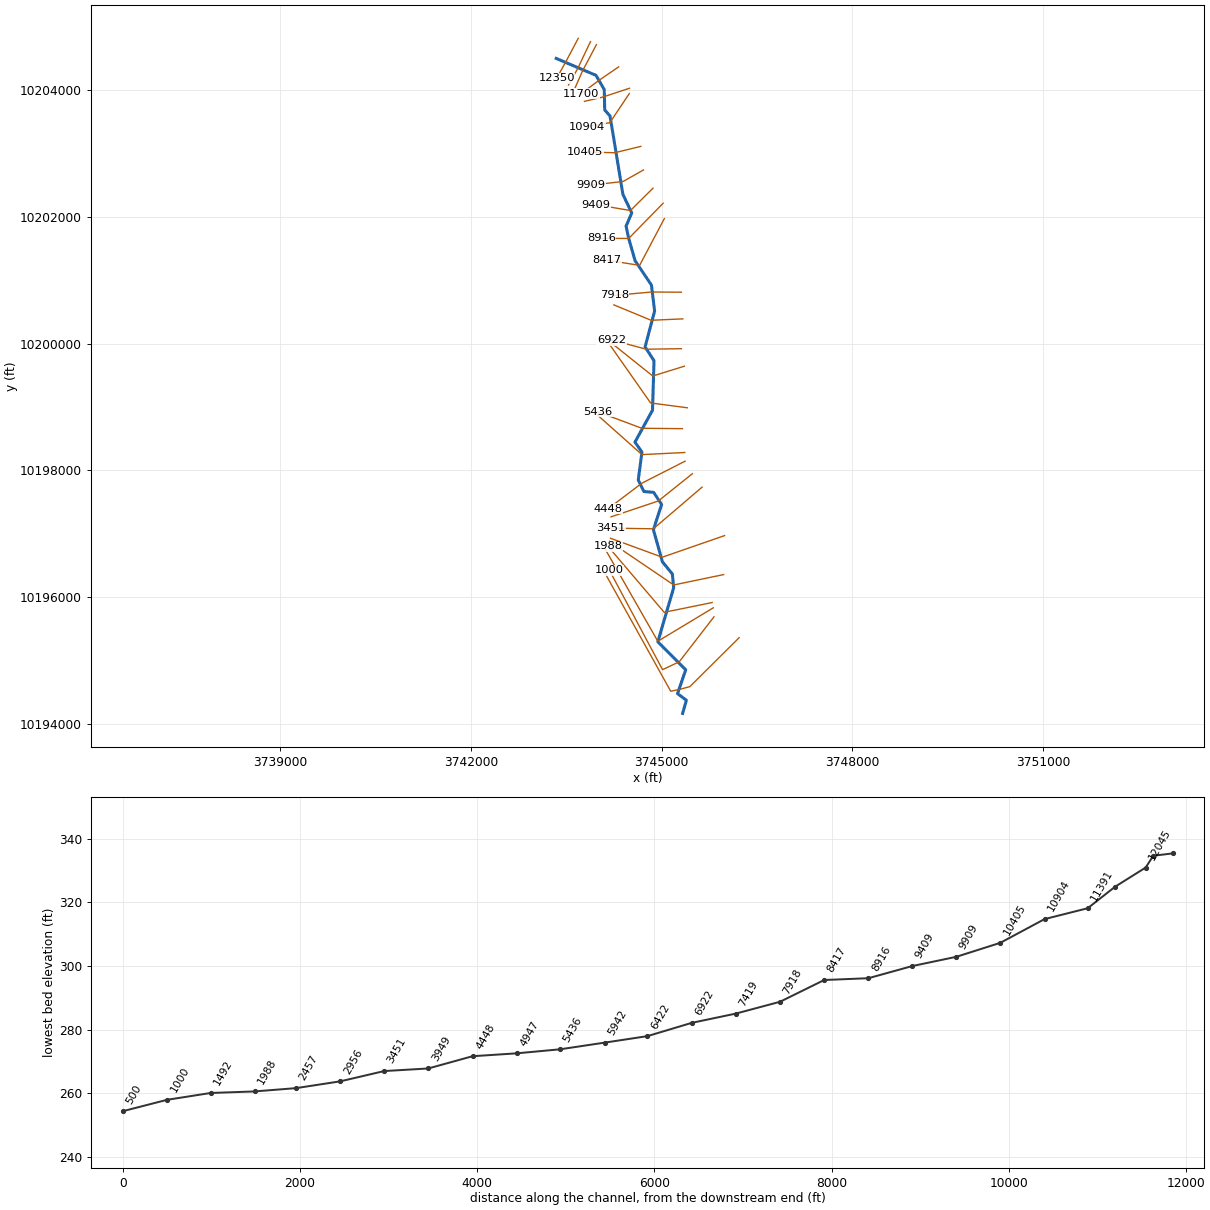
--- CANEY CREEK NORTH TRIB NO 3.prj (project) ---

Proj Title=CANEY CREEK NORTH TRIB NO 3 Base Level Engineering
Current Plan=p01
Default Exp/Contr=0.3,0.1
English Units
Geom File=g01
Flow File=f01
Flow File=f02
Plan File=p01
Y Axis Title=Elevation
X Axis Title(PF)=Main Channel Distance
X Axis Title(XS)=Station
BEGIN DESCRIPTION:
CANEY CREEK NORTH TRIB NO 3
END DESCRIPTION:
DSS Export Rating Curves= 0
DSS Export Rating Curve Sorted= 0
DSS Export Volume Flow Curves= 0
DXF OffsetX= 0
DXF OffsetY= 0
DXF ScaleX= 1
DXF ScaleY= 10

--- CANEY CREEK NORTH TRIB NO 3.p01 (plan) ---

Plan Title=Multiple Run
Short Identifier=Multiple
Geom File=g01
Flow File=f01
Subcritical Flow
K Sum by GR= 0
Std Step Tol= 0.01
Critical Tol= 0.01
Num of Std Step Trials= 20
Max Error Tol= 0.3
Flow Tol Ratio= 0.001
Split Flow NTrial= 30
Split Flow Tol= 0.02
Split Flow Ratio= 0.02
Log Output Level= 0
Friction Slope Method= 1
Unsteady Friction Slope Method= 2
Unsteady Bridges Friction Slope Method= 1
Parabolic Critical Depth
Global Vel Dist=  1 , 1 , 1
Global Log Level= 0
CheckData=True
Encroach Param= -1, 0, 0, 0
BEGIN DESCRIPTION:
Multiple Run
END DESCRIPTION:

--- CANEY CREEK NORTH TRIB NO 3.f01 (steady flow) ---

Flow Title=Multiple
Program Version=4.10
Number of Profiles= 7
Profile Names=10-year,25-year,50-year,1pct_min,100-year,1pct_plu,500-year
River Rch & RM=CANEY CREEK NORT,Reach-1         ,12350
     396     527     706     312     943    2848    1732
River Rch & RM=CANEY CREEK NORT,Reach-1         ,9909
     752    1031    1406     631    1905    5753    3610
River Rch & RM=CANEY CREEK NORT,Reach-1         ,3949
     779    1065    1449     648    1957    5910    3688
Boundary for River Rch & Prof#=CANEY CREEK NORT,Reach-1         , 1
Up Type= 0
Dn Type= 3
Dn Slope=0.008
Boundary for River Rch & Prof#=CANEY CREEK NORT,Reach-1         , 2
Up Type= 0
Dn Type= 3
Dn Slope=0.008
Boundary for River Rch & Prof#=CANEY CREEK NORT,Reach-1         , 3
Up Type= 0
Dn Type= 3
Dn Slope=0.008
Boundary for River Rch & Prof#=CANEY CREEK NORT,Reach-1         , 4
Up Type= 0
Dn Type= 3
Dn Slope=0.008
Boundary for River Rch & Prof#=CANEY CREEK NORT,Reach-1         , 5
Up Type= 0
Dn Type= 3
Dn Slope=0.008
Boundary for River Rch & Prof#=CANEY CREEK NORT,Reach-1         , 6
Up Type= 0
Dn Type= 3
Dn Slope=0.008
Boundary for River Rch & Prof#=CANEY CREEK NORT,Reach-1         , 7
Up Type= 0
Dn Type= 3
Dn Slope=0.008
DSS Import GetInterval= 0
DSS Import GetPeak= 0
DSS Import FillOption= 0

--- CANEY CREEK NORTH TRIB NO 3.f02 (steady flow) ---

Flow Title=Orig_BLE_Flow
Program Version=4.10
Number of Profiles= 7
Profile Names=10-year,25-year,50-year,1pct_min,100-year,1pct_plu,500-year
River Rch & RM=CANEY CREEK NORT,Reach-1         ,12350
     396     517     614     240     725    2190    1007
River Rch & RM=CANEY CREEK NORT,Reach-1         ,9909
     752    1011    1223     485    1465    4423    2099
River Rch & RM=CANEY CREEK NORT,Reach-1         ,3949
     779    1044    1260     498    1505    4544    2144
Boundary for River Rch & Prof#=CANEY CREEK NORT,Reach-1         , 1
Up Type= 0
Dn Type= 3
Dn Slope=0.009
Boundary for River Rch & Prof#=CANEY CREEK NORT,Reach-1         , 2
Up Type= 0
Dn Type= 3
Dn Slope=0.009
Boundary for River Rch & Prof#=CANEY CREEK NORT,Reach-1         , 3
Up Type= 0
Dn Type= 3
Dn Slope=0.009
Boundary for River Rch & Prof#=CANEY CREEK NORT,Reach-1         , 4
Up Type= 0
Dn Type= 3
Dn Slope=0.009
Boundary for River Rch & Prof#=CANEY CREEK NORT,Reach-1         , 5
Up Type= 0
Dn Type= 3
Dn Slope=0.009
Boundary for River Rch & Prof#=CANEY CREEK NORT,Reach-1         , 6
Up Type= 0
Dn Type= 3
Dn Slope=0.009
Boundary for River Rch & Prof#=CANEY CREEK NORT,Reach-1         , 7
Up Type= 0
Dn Type= 3
Dn Slope=0.009
DSS Import GetInterval= 0
DSS Import GetPeak= 0
DSS Import FillOption= 0

--- CANEY CREEK NORTH TRIB NO 3.g01 (geometry) ---

Geom Title=Existing Conditions
Program Version=4.10

River Reach=CANEY CREEK NORT,Reach-1
Reach XY= 30
      3743339.19     10204496.47      3743965.83     10204229.57
      3744095.39     10204004.83      3744102.59     10203683.48
      3744185.92     10203589.21      3744389.15     10202351.03
      3744527.87     10202059.89      3744438.48     10201850.66
      3744478.97     10201660.94      3744580.78     10201305.93
      3744837.54     10200921.86      3744887.53     10200513.03
      3744737.87     10199946.58      3744877.96     10199728.81
      3744854.69     10198949.08      3744578.44     10198445.48
      3744688.19     10198288.04      3744630.16     10197847.64
      3744718.43     10197666.17       3744872.2      10197652.5
      3744997.62      10197461.7      3744868.59     10197063.91
      3745010.16     10196557.65       3745166.2     10196366.03
      3745188.39     10196152.39      3744938.21     10195295.54
      3745376.78     10194854.43      3745248.32     10194478.98
      3745387.42     10194373.41      3745328.23     10194166.84

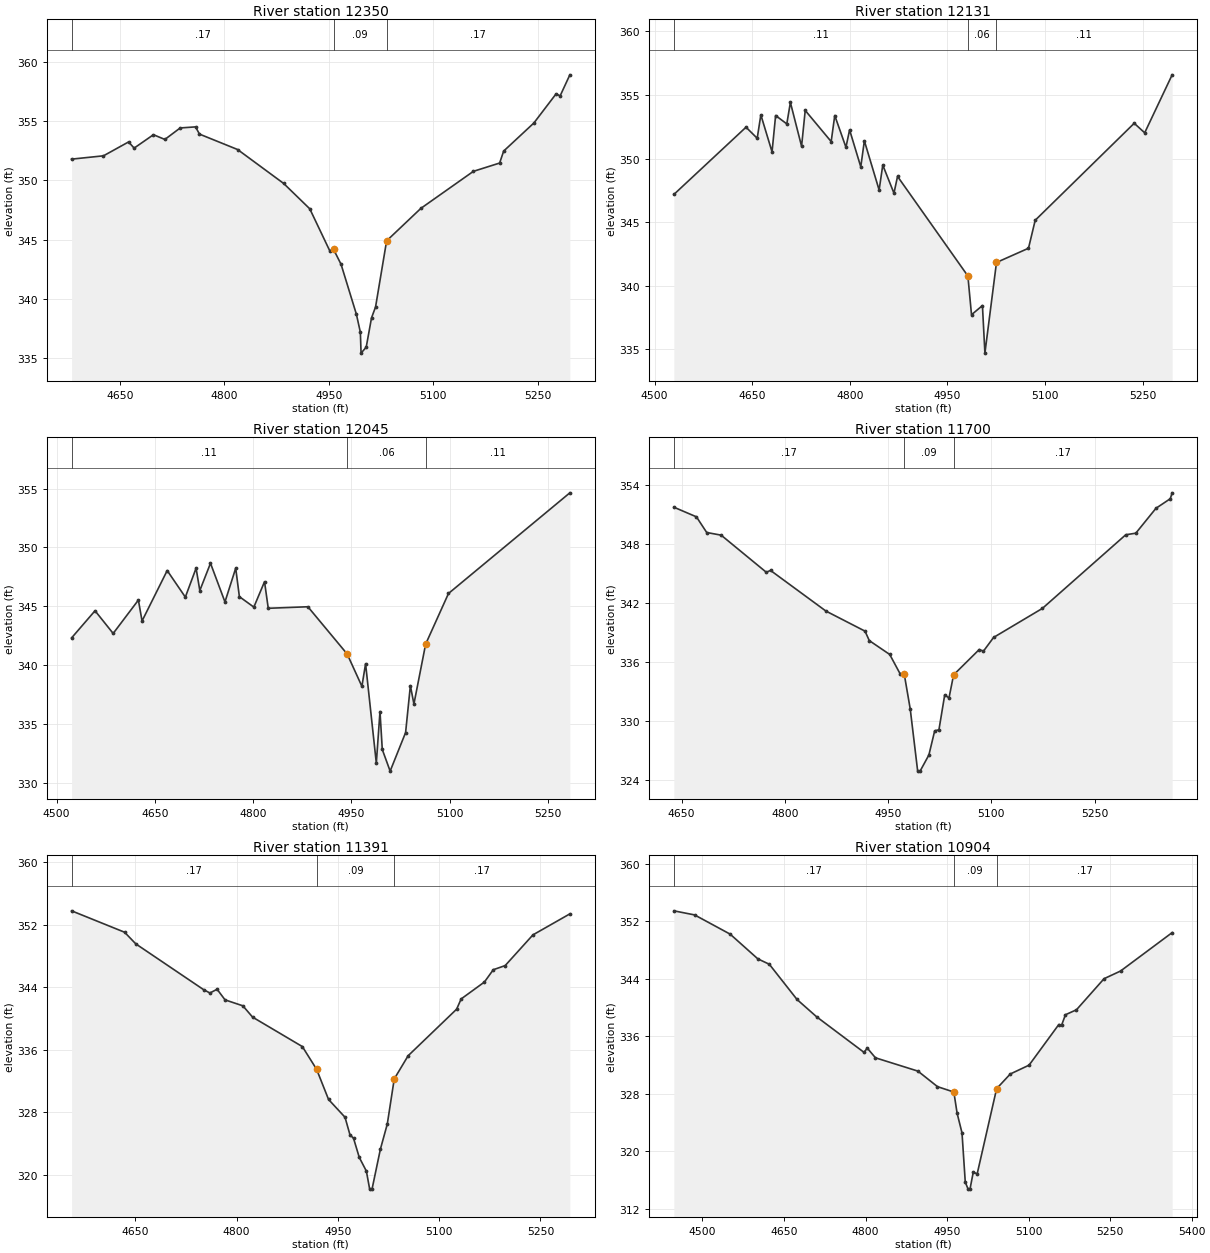
Type RM Length L Ch R = 1 ,12350   ,219,219,219
BEGIN DESCRIPTION:
CANEY CREEK NORTH TRIB NO 3 25.0
END DESCRIPTION:
XS GIS Cut Line= 3
       3743685.9      10204813.4      3743490.28     10204442.76
      3743345.81      10204184.3
#Sta/Elev= 30
  4580.9  351.79  4626.7  352.07  4662.7  353.24  4670.7  352.72  4698.4  353.85
  4714.8  353.45  4736.8  354.42  4758.8  354.51  4764.5   353.9  4819.2   352.6
  4885.3  349.74  4922.8   347.6  4951.3  344.08    4957  344.17  4967.7  342.92
  4989.7  338.71  4995.4  337.19  4996.4  335.43  5003.8  335.93  5011.4   338.4
  5017.2  339.32  5033.1   344.9  5082.3  347.64  5157.6  350.76  5195.3  351.46
  5201.1  352.47  5244.5  354.84  5276.4   357.3  5282.1  357.12  5296.1   358.9
#Mann= 3 , 0 , 0
  4580.9     .17       0    4957     .09       0  5033.1     .17       0
Bank Sta=4957,5033.1
XS Rating Curve= 0 ,0
Exp/Cntr=0.3,0.1

Type RM Length L Ch R = 1 ,12131   ,86,86,86
BEGIN DESCRIPTION:
CANEY CREEK NORTH TRIB NO 3 24.0
END DESCRIPTION:
XS GIS Cut Line= 3
      3743878.24     10204760.87      3743676.54      10204335.8
      3743533.32     10204077.44
#Sta/Elev= 30
  4529.5  347.18  4640.4  352.47  4657.6   351.6  4663.2  353.44  4680.4  350.53
  4685.9  353.39  4703.1  352.73  4708.6  354.42  4725.8  350.97  4731.4  353.79
  4771.3  351.34  4776.8  353.39    4794  350.89  4799.6  352.26  4816.8  349.35
  4822.3   351.4    4845  347.53  4850.6  349.49  4867.8  347.28  4873.3   348.6
  4981.4  340.77    4987  337.72  5003.8  338.44  5007.6   334.7  5025.4  341.83
  5074.6  342.95  5084.9  345.15  5237.1  352.78  5253.2  352.03  5295.4  356.59
#Mann= 3 , 0 , 0
  4529.5     .11       0  4981.4     .06       0  5025.4     .11       0
Bank Sta=4981.4,5025.4
XS Rating Curve= 0 ,0
Exp/Cntr=0.3,0.1

Type RM Length L Ch R = 1 ,12045   ,345,345,345
BEGIN DESCRIPTION:
CANEY CREEK NORTH TRIB NO 3 24.5
END DESCRIPTION:
XS GIS Cut Line= 3
      3743971.84     10204713.43      3743749.64     10204291.12
      3743635.91     10204031.32
#Sta/Elev= 30
  4522.8  342.31  4558.6  344.62  4586.3  342.69  4624.8  345.53  4630.4  343.75
  4668.8  348.04  4696.5  345.78  4712.9  348.24  4718.6  346.34  4734.9  348.66
    4757  345.37  4773.4  348.24    4779  345.82  4801.1  344.93  4817.4  347.09
  4823.1  344.83  4883.6  344.96  4943.6  340.94  4966.1  338.19  4971.7  340.12
  4988.1  331.66  4993.7  336.05  4997.2  332.82  5009.2  330.98  5032.8  334.26
  5040.1  338.25  5045.5  336.69  5063.4  341.78  5098.3  346.09  5283.6  354.65
#Mann= 3 , 0 , 0
  4522.8     .11       0  4943.6     .06       0  5063.4     .11       0
#XS Ineff= 2 , 0
       0  4993.7  336.05               0
Permanent Ineff=
       T       F
Bank Sta=4943.6,5063.4
XS Rating Curve= 0 ,0
Exp/Cntr=0.3,0.1

Type RM Length L Ch R = 1 ,11700   ,309,309,309
BEGIN DESCRIPTION:
CANEY CREEK NORTH TRIB NO 3 23.0
END DESCRIPTION:
XS GIS Cut Line= 3
      3744321.82     10204363.35      3744024.16     10204158.74
       3743732.5     10203943.14
#Sta/Elev= 30
  4638.8  351.76  4671.6  350.78  4686.5  349.19  4707.5  348.92  4773.1  345.15
  4779.2  345.34  4859.7  341.21  4916.5  339.17  4922.7  338.21  4952.4   336.8
  4967.3  334.86  4973.4  334.84  4982.2  331.26    4993  324.95  4996.5  324.95
  5009.3  326.59  5017.7  329.04  5023.9  329.15  5032.3   332.7  5038.5  332.38
  5045.2  334.73  5082.4   337.3  5088.6  337.14  5103.3  338.53  5174.2  341.48
  5295.3  348.96  5309.9  349.12  5339.2  351.65    5360  352.62  5362.7  353.22
#Mann= 3 , 0 , 0
  4638.8     .17       0  4973.4     .09       0  5045.2     .17       0
Bank Sta=4973.4,5045.2
XS Rating Curve= 0 ,0
Exp/Cntr=0.3,0.1

Type RM Length L Ch R = 1 ,11391   ,487,487,487
BEGIN DESCRIPTION:
CANEY CREEK NORTH TRIB NO 3 22.0
END DESCRIPTION:
XS GIS Cut Line= 3
      3744492.41     10204026.17      3744070.39      10203886.6
      3743784.61     10203819.73
#Sta/Elev= 30
  4555.5  353.81    4634  351.07  4650.6  349.58    4751  343.72  4760.4  343.29
    4771  343.77  4782.8  342.41  4809.2  341.65  4823.6   340.2  4897.3  336.43
  4918.4  333.52  4936.1  329.66  4960.5  327.38  4967.8  325.14  4973.1  324.69
  4981.6  322.24  4992.1  320.49    4997  318.18  5000.5  318.18  5012.9   323.3
  5023.1  326.51  5033.4  332.29    5054  335.26  5125.8  341.22  5132.5  342.53
  5166.9  344.69  5180.1  346.27  5197.7   346.8  5238.8  350.73  5293.5  353.42
#Mann= 3 , 0 , 0
  4555.5     .17       0  4918.4     .09       0  5033.4     .17       0
Bank Sta=4918.4,5033.4
XS Rating Curve= 0 ,0
Exp/Cntr=0.3,0.1

Type RM Length L Ch R = 1 ,10904   ,499,499,499
BEGIN DESCRIPTION:
CANEY CREEK NORTH TRIB NO 3 21.0
END DESCRIPTION:
XS GIS Cut Line= 3
      3744489.82     10203942.84      3744183.15     10203483.14
      3743824.39     10203420.99
#Sta/Elev= 30
  4447.4  353.46  4485.6  352.89  4550.9  350.22  4601.9  346.78    4623  346.03
    4674  341.13  4710.1  338.72  4797.2  333.78  4803.2  334.37  4818.3  333.02
  4896.4  331.17  4932.4  329.01  4962.5  328.26  4968.5  325.31  4977.5  322.58
  4983.5  315.74  4988.7  314.76  4992.2  314.76  4998.2  317.12  5005.4  316.88
  5041.2  328.73  5066.3  330.77  5100.9     332  5155.6  337.65  5160.6  337.53
  5167.8  339.01  5188.1   339.7  5238.8  344.02  5269.2  345.09  5364.1  350.43
#Mann= 3 , 0 , 0
  4447.4     .17       0  4962.5     .09       0  5041.2     .17       0
Bank Sta=4962.5,5041.2
XS Rating Curve= 0 ,0
Exp/Cntr=0.3,0.1

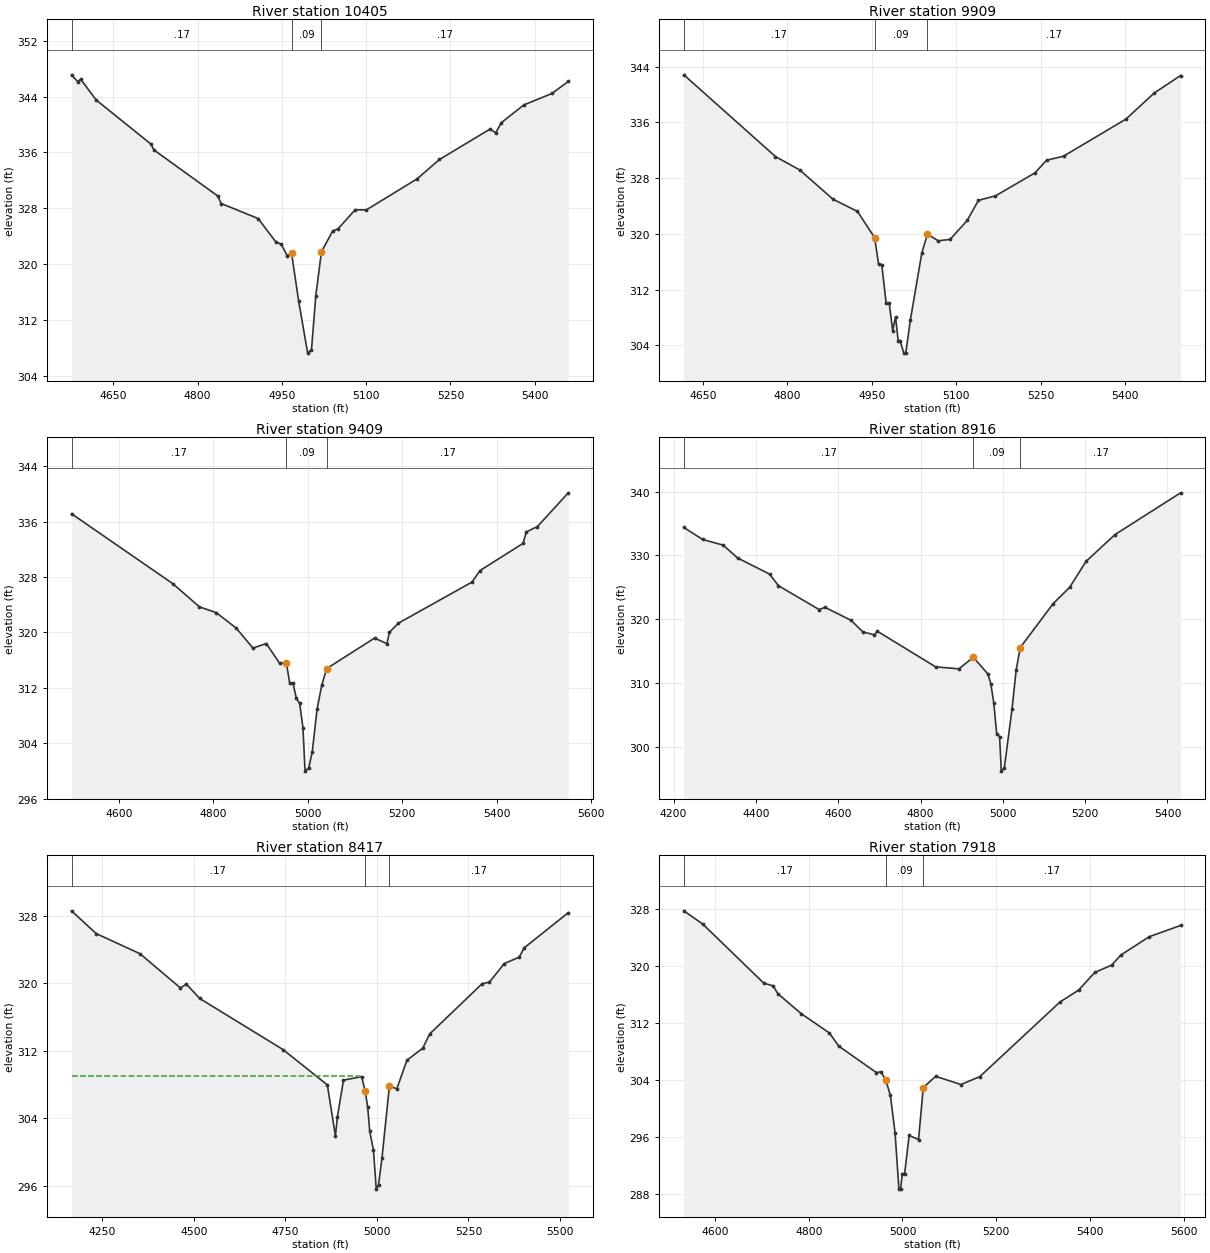
Type RM Length L Ch R = 1 ,10405   ,496,496,496
BEGIN DESCRIPTION:
CANEY CREEK NORTH TRIB NO 3 20.0
END DESCRIPTION:
XS GIS Cut Line= 3
      3744670.61     10203109.44      3744258.26     10203009.02
      3743798.72     10203020.96
#Sta/Elev= 30
  4575.6  347.11  4586.7  346.13  4591.8  346.49  4619.6   343.5    4717   337.2
  4722.5  336.35  4835.7  329.79  4842.1   328.7  4907.8  326.55  4938.7  323.26
    4949  322.86  4959.3  321.25  4967.3  321.57  4979.8  314.77  4995.9   307.3
  5002.7   307.8  5010.4  315.51  5020.4  321.79  5040.4  324.76  5050.4  325.12
  5080.4  327.81  5100.4  327.79  5190.5  332.22  5230.5     335  5320.5  339.35
  5330.5  338.81  5340.5  340.26  5380.5   342.8  5430.6  344.44  5459.7  346.16
#Mann= 3 , 0 , 0
  4575.6     .17       0  4967.3     .09       0  5020.4     .17       0
Bank Sta=4967.3,5020.4
XS Rating Curve= 0 ,0
Exp/Cntr=0.3,0.1

Type RM Length L Ch R = 1 ,9909    ,500,500,500
BEGIN DESCRIPTION:
CANEY CREEK NORTH TRIB NO 3 19.0
END DESCRIPTION:
XS GIS Cut Line= 4
      3744712.25     10202737.67      3744397.36     10202558.48
      3744376.17     10202554.29      3743881.48     10202496.97
#Sta/Elev= 30
  4616.1  342.81  4778.8  331.09    4822  329.16  4881.1  324.96  4924.3  323.23
  4954.8  319.47  4961.8  315.71  4967.6  315.53  4975.2  310.12  4980.7  310.12
  4986.9  306.12    4992  308.11  4996.6   304.7    5000   304.7  5006.6   302.9
  5010.1   302.9  5018.4  307.69  5038.6  317.25  5048.6  319.95  5067.6  319.01
  5088.9  319.21  5119.1  321.92  5139.2  324.81  5169.4  325.45  5239.9  328.77
    5260  330.56  5290.2  331.14    5401  336.46  5451.3  340.21    5498  342.71
#Mann= 3 , 0 , 0
  4616.1     .17       0  4954.8     .09       0  5048.6     .17       0
Bank Sta=4954.8,5048.6
XS Rating Curve= 0 ,0
Exp/Cntr=0.3,0.1

Type RM Length L Ch R = 1 ,9409    ,493,493,493
BEGIN DESCRIPTION:
CANEY CREEK NORTH TRIB NO 3 18.0
END DESCRIPTION:
XS GIS Cut Line= 3
      3744862.03     10202450.16      3744507.43     10202097.51
      3743963.57     10202190.82
#Sta/Elev= 30
  4499.9  337.15  4714.4  327.05  4770.9  323.69  4806.3  322.87  4848.7  320.63
  4884.1  317.74  4912.3   318.4  4940.6  315.54  4954.8  315.66  4961.8  312.72
  4968.9  312.68    4976  310.49  4983.1  309.74  4990.1  306.17  4994.4  299.97
  5002.3  300.47  5009.7  302.75  5019.9  308.92    5030  312.44  5040.2  314.78
  5141.6  319.19  5167.9  318.38    5173  320.02  5192.3  321.35    5348  327.28
  5364.8  328.94  5456.1  332.87  5462.9  334.53  5486.6   335.3  5551.8  340.17
#Mann= 3 , 0 , 0
  4499.9     .17       0  4954.8     .09       0  5040.2     .17       0
Bank Sta=4954.8,5040.2
XS Rating Curve= 0 ,0
Exp/Cntr=0.3,0.1

Type RM Length L Ch R = 1 ,8916    ,499,499,499
BEGIN DESCRIPTION:
CANEY CREEK NORTH TRIB NO 3 17.0
END DESCRIPTION:
XS GIS Cut Line= 3
       3745021.4     10202212.54      3744480.13     10201657.59
      3744048.23     10201656.96
#Sta/Elev= 30
  4224.8  334.38  4270.7  332.49  4320.3  331.61  4355.6  329.59  4433.5  327.05
  4454.6  325.25  4553.6   321.5  4567.8  321.85  4631.5   319.8  4659.8     318
  4687.9  317.54  4695.1   318.1  4836.5  312.52  4893.1   312.2  4928.4  314.01
  4963.8  311.39  4970.8  309.86    4978  306.84    4985  302.05  4992.1  301.57
  4996.3  296.16  5003.6  296.66  5022.3  305.87  5032.3  311.99  5042.3  315.54
  5122.3  322.43  5162.3  324.98  5202.3  329.06  5272.3  333.25  5431.9  339.81
#Mann= 3 , 0 , 0
  4224.8     .17       0  4928.4     .09       0  5042.3     .17       0
Bank Sta=4928.4,5042.3
XS Rating Curve= 0 ,0
Exp/Cntr=0.3,0.1

Type RM Length L Ch R = 1 ,8417    ,499,499,499
BEGIN DESCRIPTION:
CANEY CREEK NORTH TRIB NO 3 16.0
END DESCRIPTION:
XS GIS Cut Line= 3
      3745040.75      10201970.8      3744651.53     10201232.74
      3744135.27     10201315.19
#Sta/Elev= 30
  4165.6  328.59  4233.1  325.89  4352.9   323.5  4463.1  319.45  4479.4  319.89
  4515.8   318.2  4743.7  312.13  4864.6  307.95  4886.6  301.91  4892.2  304.19
  4908.6  308.51  4958.3  308.93    4968  307.19  4974.7  305.35  4980.3  302.48
  4990.6   300.2  4998.2  295.59  5004.4  296.09  5013.9  299.29  5034.1  307.81
  5054.4  307.48  5082.1  310.88  5125.2   312.3  5144.2  313.99  5287.3  319.94
  5307.5  320.14    5348  322.34  5388.5  323.09  5402.7  324.21  5522.8  328.37
#Mann= 3 , 0 , 0
  4165.6     .17       0    4968     .09       0  5034.1     .17       0
#XS Ineff= 2 , 0
       0  4952.7  308.99               0
Permanent Ineff=
       F       F
Bank Sta=4968,5034.1
XS Rating Curve= 0 ,0
Exp/Cntr=0.3,0.1

Type RM Length L Ch R = 1 ,7918    ,499,499,499
BEGIN DESCRIPTION:
CANEY CREEK NORTH TRIB NO 3 15.0
END DESCRIPTION:
XS GIS Cut Line= 3
      3745308.31     10200809.53      3744842.01     10200812.47
      3744251.37     10200759.69
#Sta/Elev= 30
  4533.7  327.69  4574.2  325.83  4704.2  317.57  4724.2  317.19  4734.2  316.09
  4784.2  313.29  4844.2  310.59  4864.2  308.75  4944.2  305.06  4954.2  305.16
  4964.2  304.03  4974.2  301.86  4984.2   296.6  4992.4  288.74  4995.9  288.74
  4999.6  290.92  5004.6  290.92  5014.2  296.25  5034.3  295.68  5044.3  302.95
  5070.7  304.53  5124.7  303.38  5164.8  304.48  5335.5  314.91  5375.7   316.6
  5409.9  319.06  5445.9  320.09    5466  321.52  5526.3  324.07    5593  325.64
#Mann= 3 , 0 , 0
  4533.7     .17       0  4964.2     .09       0  5044.3     .17       0
Bank Sta=4964.2,5044.3
XS Rating Curve= 0 ,0
Exp/Cntr=0.3,0.1

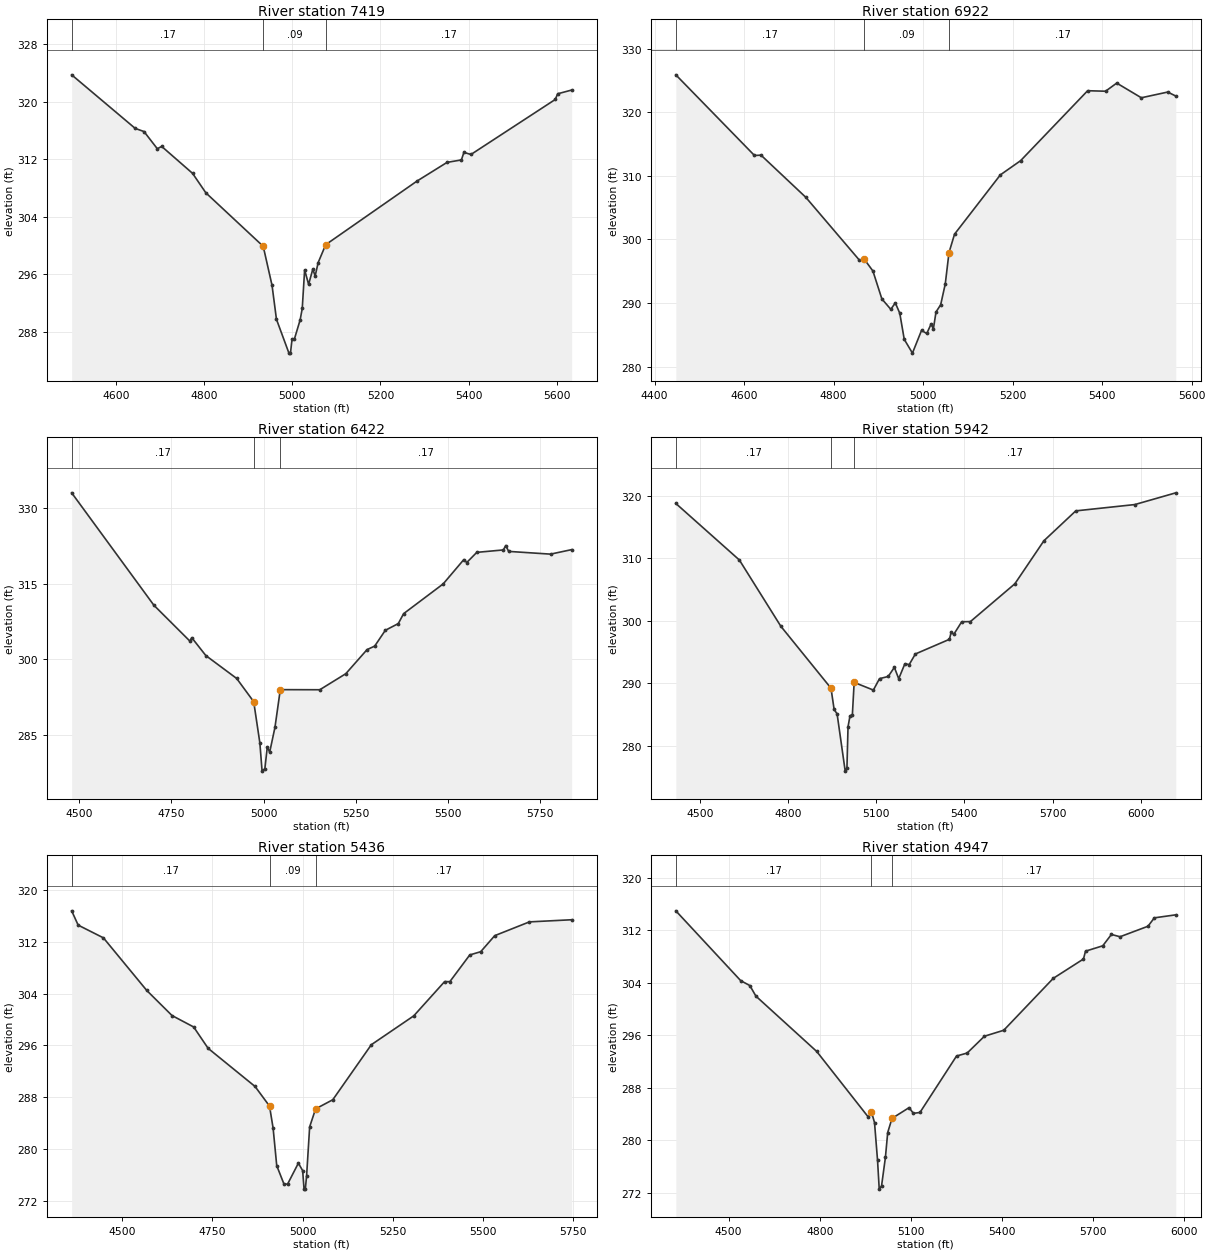
Type RM Length L Ch R = 1 ,7419    ,497,497,497
BEGIN DESCRIPTION:
CANEY CREEK NORTH TRIB NO 3 14.0
END DESCRIPTION:
XS GIS Cut Line= 3
      3745331.82     10200389.13      3744832.12     10200366.64
      3744246.97     10200609.63
#Sta/Elev= 30
  4499.8  323.77  4643.9  316.31  4663.9  315.87    4694  313.48    4704   313.8
    4774  310.05  4804.1  307.34  4934.2  299.89  4954.2  294.45  4964.2  289.73
  4992.5  285.02    4996  285.02  4999.6     287    5005     287  5017.9  289.64
  5022.7  291.24  5028.1  296.62  5037.1  294.59  5046.6   296.7    5052  295.77
  5058.8  297.63  5075.9  300.12    5283  308.98  5351.1  311.58  5383.6  311.92
  5389.3  312.97  5405.3  312.68  5596.5  320.34  5601.9  321.13  5633.6  321.65
#Mann= 3 , 0 , 0
  4499.8     .17       0  4934.2     .09       0  5075.9     .17       0
#XS Ineff= 2 , 0
       0                  5028.1       0  296.62
Permanent Ineff=
       F       F
Bank Sta=4934.2,5075.9
XS Rating Curve= 0 ,0
Exp/Cntr=0.3,0.1

Type RM Length L Ch R = 1 ,6922    ,500,500,500
BEGIN DESCRIPTION:
CANEY CREEK NORTH TRIB NO 3 13.0
END DESCRIPTION:
XS GIS Cut Line= 3
      3745308.23     10199918.75       3744755.7     10199910.33
      3744210.35      10200056.5
#Sta/Elev= 30
  4447.4   325.9  4623.1  313.21  4637.8  313.26  4737.8  306.63  4857.8  296.72
  4867.8  296.95  4887.8  295.03  4907.8  290.64  4927.8     289  4937.8  290.02
  4947.8  288.39  4957.8  284.28  4976.1  282.11  4996.4  285.68  5008.1   285.2
  5017.7  286.67  5022.9  285.93  5028.8  288.59  5039.2  289.72  5049.5  293.01
  5057.8  297.93  5070.2  300.83  5172.6  310.16  5217.8  312.39  5367.6   323.4
  5407.6  323.32  5432.6   324.6  5487.6  322.29  5546.5  323.19  5564.6  322.56
#Mann= 3 , 0 , 0
  4447.4     .17       0  4867.8     .09       0  5057.8     .17       0
Bank Sta=4867.8,5057.8
XS Rating Curve= 0 ,0
Exp/Cntr=0.3,0.1

Type RM Length L Ch R = 1 ,6422    ,480,480,480
BEGIN DESCRIPTION:
CANEY CREEK NORTH TRIB NO 3 12.0
END DESCRIPTION:
XS GIS Cut Line= 3
      3745355.31     10199642.41      3744858.09      10199487.8
      3744205.81      10200009.9
#Sta/Elev= 30
  4479.3  332.95  4702.3  310.73  4799.9  303.64  4805.1  304.31  4843.2  300.78
  4926.9  296.25  4973.1  291.66  4989.8   283.5  4995.8  277.93  5003.4  278.43
    5010  282.75  5016.4  281.66  5030.8  286.61  5045.2  294.04  5152.4  294.02
  5222.9  297.19  5280.5  301.95  5301.3  302.65  5330.1  305.77  5365.3   307.1
  5379.7  309.06    5487  314.94    5543  319.75    5551  319.17  5578.2  321.18
  5650.3  321.66  5656.7  322.53  5664.7  321.37  5778.3  320.83  5835.5  321.72
#Mann= 3 , 0 , 0
  4479.3     .17       0  4973.1     .09       0  5045.2     .17       0
Bank Sta=4973.1,5045.2
XS Rating Curve= 0 ,0
Exp/Cntr=0.3,0.1

Type RM Length L Ch R = 1 ,5942    ,506,506,506
BEGIN DESCRIPTION:
CANEY CREEK NORTH TRIB NO 3 11.0
END DESCRIPTION:
XS GIS Cut Line= 3
      3745402.37     10198986.81      3744824.61     10199062.56
      3744182.55     10199980.13
#Sta/Elev= 30
  4417.3  318.77  4633.7  309.71  4774.9   299.1  4945.7  289.18  4956.4  285.77
  4966.5  285.07  4994.1   275.9    5000   276.4  5003.7     283  5010.4  284.74
  5018.5  284.92  5024.6  290.11    5090  288.88  5110.9  290.71  5140.6  291.06
  5161.5  292.52  5176.3   290.7  5197.3  293.09  5212.1  292.97    5233  294.66
    5349  297.01  5355.1  298.18  5363.8   297.8  5390.8  299.82  5420.5  299.85
  5571.8   305.9  5670.7  312.79  5779.3  317.58  5980.3  318.59  6119.9  320.47
#Mann= 3 , 0 , 0
  4417.3     .17       0  4945.7     .09       0  5024.6     .17       0
Bank Sta=4945.7,5024.6
XS Rating Curve= 0 ,0
Exp/Cntr=0.3,0.1

Type RM Length L Ch R = 1 ,5436    ,489,489,489
BEGIN DESCRIPTION:
CANEY CREEK NORTH TRIB NO 3 10.0
END DESCRIPTION:
XS GIS Cut Line= 3
      3745325.88     10198657.55      3744686.01     10198663.31
      3743988.29     10198925.07
#Sta/Elev= 30
  4360.1  316.82  4378.1  314.61  4448.1  312.64  4568.1  304.51  4638.1  300.63
  4698.1  298.86  4738.1  295.56  4868.2  289.66  4908.2  286.63  4918.2  283.21
  4928.2  277.42  4948.2  274.58  4958.2  274.56  4988.2  277.81    5000  276.65
  5003.9  273.79  5007.4  273.79    5011  275.88  5019.4  283.42  5035.9   286.2
  5083.5  287.61  5190.3  296.12  5307.8  300.58  5393.2  305.87  5407.8  305.87
    5463     310  5493.3   310.5  5532.1  312.98  5628.2  315.11  5745.2  315.44
#Mann= 3 , 0 , 0
  4360.1     .17       0  4908.2     .09       0  5035.9     .17       0
Bank Sta=4908.2,5035.9
XS Rating Curve= 0 ,0
Exp/Cntr=0.3,0.1

Type RM Length L Ch R = 1 ,4947    ,499,499,499
BEGIN DESCRIPTION:
CANEY CREEK NORTH TRIB NO 3 9.0
END DESCRIPTION:
XS GIS Cut Line= 3
      3745361.23     10198281.25      3744688.34      10198248.1
      3743962.37     10198895.18
#Sta/Elev= 30
  4326.3  314.93  4539.9  304.29    4570  303.54    4590  301.93  4790.2   293.5
  4960.4  283.48  4970.5  284.28  4980.5  282.66  4990.5  276.89    4996  272.52
  5003.7  273.02  5016.4  277.36  5023.9  281.14  5038.1   283.3  5094.4  284.94
  5108.3  284.07  5130.1   284.2  5250.5   292.8  5285.6  293.26  5342.4  295.82
    5406  296.73    5569  304.64  5668.5  307.59  5675.2  308.78    5732   309.6
  5760.5  311.33  5788.9  310.98  5880.9  312.58  5901.8  313.86  5972.5  314.32
#Mann= 3 , 0 , 0
  4326.3     .17       0  4970.5     .09       0  5038.1     .17       0
Bank Sta=4970.5,5038.1
XS Rating Curve= 0 ,0
Exp/Cntr=0.3,0.1

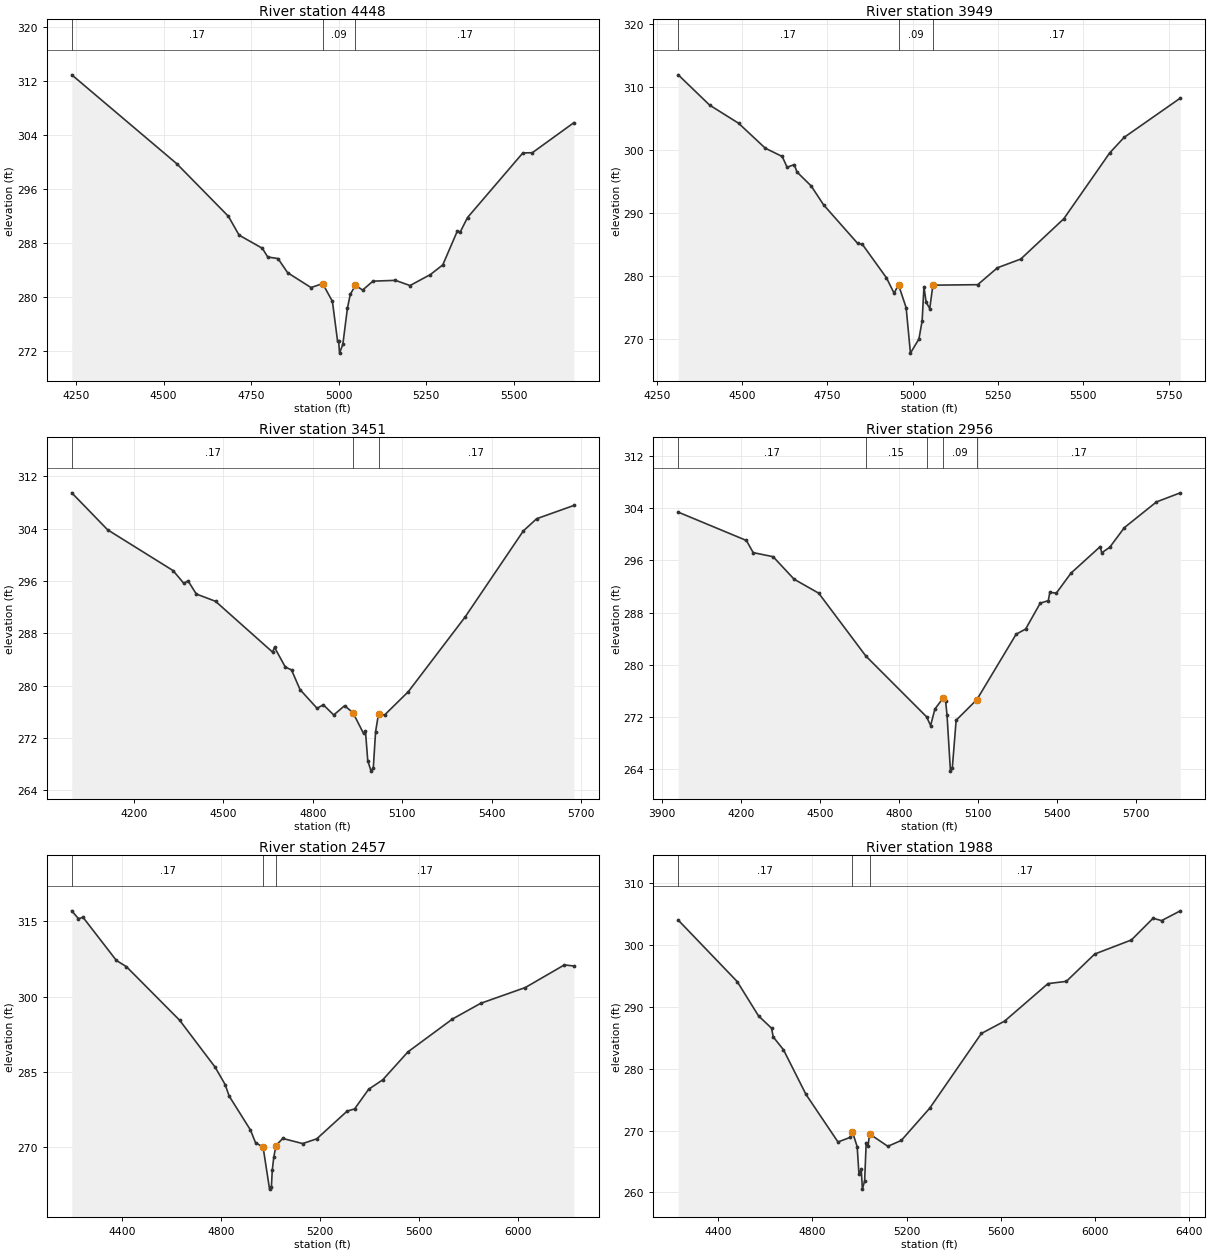
Type RM Length L Ch R = 1 ,4448    ,499,499,499
BEGIN DESCRIPTION:
CANEY CREEK NORTH TRIB NO 3 8.0
END DESCRIPTION:
XS GIS Cut Line= 3
      3745366.57     10198144.37      3744687.42     10197797.73
      3744152.09     10197391.52
#Sta/Elev= 30
  4237.5  312.95  4537.6  299.74  4685.1  291.93  4715.5  289.14  4782.1  287.18
  4797.4  285.89  4826.6  285.66  4854.4  283.55  4921.1  281.35  4954.3  281.94
  4982.2   279.3  4996.9  273.41    5000  273.41  5002.5  271.61    5012  272.92
  5025.1   278.3  5033.3  280.35  5047.9  281.67  5068.7  280.98  5097.8   282.3
  5162.3  282.42  5203.9  281.65  5262.1  283.28  5297.5  284.72  5339.1  289.74
  5347.4  289.61  5368.2  291.75  5526.3  301.35  5553.4  301.38    5672  305.84
#Mann= 3 , 0 , 0
  4237.5     .17       0  4954.3     .09       0  5047.9     .17       0
Bank Sta=4954.3,5047.9
XS Rating Curve= 0 ,0
Exp/Cntr=0.3,0.1

Type RM Length L Ch R = 1 ,3949    ,498,498,498
BEGIN DESCRIPTION:
CANEY CREEK NORTH TRIB NO 3 7.0
END DESCRIPTION:
XS GIS Cut Line= 3
      3745481.09     10197946.42      3744945.24     10197516.18
      3744201.64     10197266.48
#Sta/Elev= 30
  4312.8  311.87  4404.8  307.07  4489.6   304.2    4568  300.24  4617.6  298.93
    4632  297.21  4652.8  297.65  4660.8  296.47  4702.4  294.26  4739.2  291.24
  4838.4  285.17  4852.8  284.98  4923.2  279.69  4945.4  277.26  4958.4   278.6
  4980.8  274.96  4993.4  267.76  5018.3  270.01  5027.7  272.88    5033   278.3
  5039.4  275.83    5050  274.82  5059.2  278.53  5190.6  278.61  5248.4  281.29
  5316.7  282.67  5442.8  289.05  5577.4  299.49  5619.6  301.95  5784.4  308.18
#Mann= 3 , 0 , 0
  4312.8     .17       0  4958.4     .09       0  5059.2     .17       0
Bank Sta=4958.4,5059.2
XS Rating Curve= 0 ,0
Exp/Cntr=0.3,0.1

Type RM Length L Ch R = 1 ,3451    ,495,495,495
BEGIN DESCRIPTION:
CANEY CREEK NORTH TRIB NO 3 6.0
END DESCRIPTION:
XS GIS Cut Line= 3
      3745633.87     10197734.62      3744867.95     10197077.93
      3744192.94      10197088.8
#Sta/Elev= 30
  3991.1  309.46  4111.4  303.81  4330.9  297.58  4367.1  295.62    4381  296.02
  4408.8     294  4473.2  292.89  4664.5  285.13  4671.1  285.85  4707.4  282.84
  4728.2   282.4  4756.7   279.4  4813.8  276.54  4834.7  277.08  4869.8  275.52
    4906  276.93  4934.3  275.88  4969.7  272.69  4976.2  273.03  4983.9  268.53
    4995  266.94  5002.5  267.44  5010.1  272.96  5020.1  275.74  5040.1  275.51
  5120.1  279.09  5310.1  290.47  5505.5  303.63  5550.2   305.5  5675.1  307.53
#Mann= 3 , 0 , 0
  3991.1     .17       0  4934.3     .09       0  5020.1     .17       0
Bank Sta=4934.3,5020.1
XS Rating Curve= 0 ,0
Exp/Cntr=0.3,0.1

Type RM Length L Ch R = 1 ,2956    ,499,499,499
BEGIN DESCRIPTION:
CANEY CREEK NORTH TRIB NO 3 5.0
END DESCRIPTION:
XS GIS Cut Line= 3
      3745988.07     10196970.75      3745007.79     10196629.75
      3744192.93     10196929.07
#Sta/Elev= 30
  3962.1   303.4  4220.8  299.06  4246.6   297.2  4322.3  296.57  4402.1  293.12
  4495.4  290.98  4674.1  281.36  4904.8  272.04  4920.2  270.69  4936.4  273.22
  4968.2  274.94  4977.1  274.46  4982.4  272.37  4995.5  263.71  5002.6  264.21
  5017.1  271.51  5095.8  274.67    5245   284.7  5280.8  285.48  5336.4  289.46
  5366.9  289.83  5372.8  291.11  5397.4  290.99    5453  294.05  5564.3  298.13
  5569.6  297.17  5600.1  298.01  5655.8  301.03  5777.7  304.97  5868.1  306.36
#Mann= 5 ,-1 , 0
  3962.1     .17       0  4674.1     .15       0  4904.8     .17       0
  4968.2     .09       0  5095.8     .17       0
Bank Sta=4968.2,5095.8
XS Rating Curve= 0 ,0
Exp/Cntr=0.3,0.1

Type RM Length L Ch R = 1 ,2457    ,469,469,469
BEGIN DESCRIPTION:
CANEY CREEK NORTH TRIB NO 3 4.0
END DESCRIPTION:
XS GIS Cut Line= 3
      3745974.12     10196356.15      3745188.27     10196192.06
      3744175.59     10196880.44
#Sta/Elev= 30
  4197.2   317.1    4224  315.55  4242.9  315.79  4377.3   307.2  4418.1  305.95
  4632.7  295.27  4775.7  285.93  4816.5  282.44  4832.7  280.14  4918.7  273.37
  4939.1  270.85  4969.8  269.94  4995.8  261.57  5003.3  262.07  5006.8  265.35
  5012.9  267.95  5021.8  270.25  5048.9  271.68  5129.6  270.66  5186.5  271.61
  5309.2  277.14  5339.1  277.57    5396   281.5  5452.9  283.38  5554.6  288.96
  5734.3  295.51  5848.1  298.64  6028.3  301.79  6186.3  306.31  6224.5  306.09
#Mann= 3 , 0 , 0
  4197.2     .17       0  4969.8     .09       0  5021.8     .17       0
Bank Sta=4969.8,5021.8
XS Rating Curve= 0 ,0
Exp/Cntr=0.3,0.1

Type RM Length L Ch R = 1 ,1988    ,496,496,496
BEGIN DESCRIPTION:
CANEY CREEK NORTH TRIB NO 3 3.0
END DESCRIPTION:
XS GIS Cut Line= 3
      3745793.58     10195915.18      3745038.18     10195760.86
      3744154.72     10196800.61
#Sta/Elev= 30
    4229     304  4479.8  294.07  4570.4  288.53    4626  286.53  4632.9  285.13
  4676.5  283.06  4772.4  275.83  4908.5  268.15  4959.5  268.88  4969.3  269.84
  4990.1  267.39  4997.6  262.95  5007.5  263.74  5012.2  260.53  5021.8  261.85
  5028.4  268.03  5036.1  267.46  5042.7  269.45  5120.6  267.45  5177.8   268.4
  5298.6  273.61  5518.2  285.68  5617.1  287.68  5801.6  293.74  5879.6   294.1
  6000.4  298.52  6156.3  300.79  6248.6   304.3  6284.9  303.92  6364.4   305.5
#Mann= 3 , 0 , 0
    4229     .17       0  4969.3     .09       0  5042.7     .17       0
Bank Sta=4969.3,5042.7
XS Rating Curve= 0 ,0
Exp/Cntr=0.3,0.1

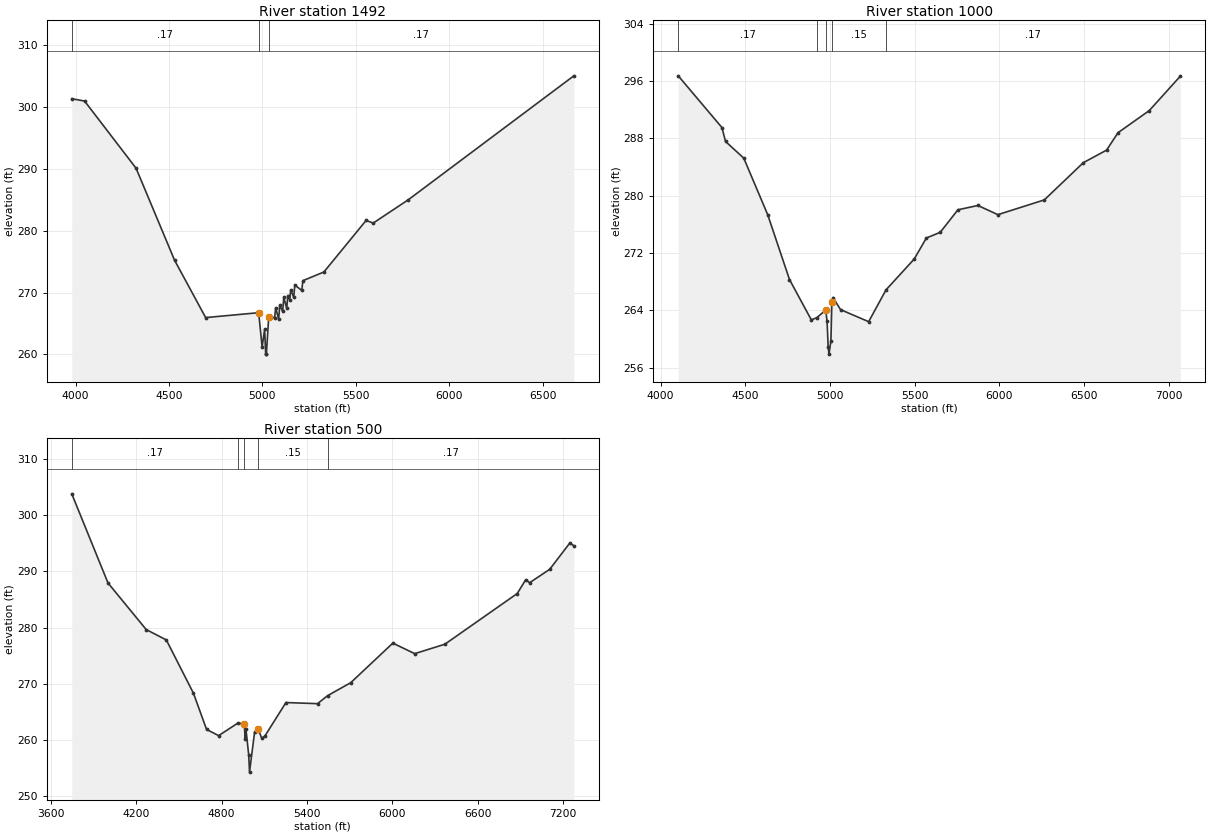
Type RM Length L Ch R = 1 ,1492    ,492,492,492
BEGIN DESCRIPTION:
CANEY CREEK NORTH TRIB NO 3 2.0
END DESCRIPTION:
XS GIS Cut Line= 3
      3745810.96     10195831.85      3744937.82     10195304.36
      3744113.05     10196751.99
#Sta/Elev= 30
  3979.9  301.35  4048.4  300.97    4324   290.1  4529.7  275.24  4696.2  265.95
  4979.9  266.74  4998.3  261.19  5011.8  264.06  5017.4  260.04  5021.1  260.04
  5033.4  265.99  5065.1  265.94  5070.8  267.53  5086.7  265.71  5092.4  267.94
  5108.3  266.95  5114.1  269.22  5129.9  267.46  5135.7  269.51  5145.8  268.84
  5151.5  270.44  5167.4  269.22  5173.1  271.21  5210.6  270.35  5216.3  271.92
  5328.7  273.32  5554.9  281.67  5592.4  281.23  5781.1  285.02  6666.1  305.05
#Mann= 3 , 0 , 0
  3979.9     .17       0  4979.9     .09       0  5033.4     .17       0
Bank Sta=4979.9,5033.4
XS Rating Curve= 0 ,0
Exp/Cntr=0.3,0.1

Type RM Length L Ch R = 1 ,1000    ,500,500,500
BEGIN DESCRIPTION:
CANEY CREEK NORTH TRIB NO 3 2.5
END DESCRIPTION:
XS GIS Cut Line= 4
       3745821.4     10195689.51      3745274.79     10194980.31
      3745012.36     10194856.16      3744175.56     10196425.59
#Sta/Elev= 30
  4104.6  296.74  4362.9  289.51  4383.7  287.58  4491.5  285.25  4632.9  277.35
  4761.5   268.3  4890.1  262.68  4921.6  262.96  4975.3  264.03  4983.4  262.46
  4989.8  258.92  4994.5  257.89    5006  259.74  5011.6  265.13  5018.7  265.79
    5063   264.1  5228.9  262.42  5331.3  266.86    5498  271.17  5569.6   274.1
  5651.7   274.9  5755.9  278.04  5873.9  278.64  5991.8  277.36  6265.9  279.42
  6496.1  284.61  6633.6  286.37  6701.1   288.8  6885.7  291.89  7068.9  296.69
#Mann= 5 ,-1 , 0
  4104.6     .17       0  4921.6     .15       0  4975.3     .09       0
  5011.6     .15       0  5331.3     .17       0
Bank Sta=4975.3,5011.6
XS Rating Curve= 0 ,0
Exp/Cntr=0.3,0.1

Type RM Length L Ch R = 1 ,500     ,0,0,0
BEGIN DESCRIPTION:
CANEY CREEK NORTH TRIB NO 3 1.0
END DESCRIPTION:
XS GIS Cut Line= 5
      3746217.84     10195361.06      3745442.02     10194589.01
      3745288.72     10194547.21      3745140.83     10194515.88
      3744109.56     10196373.55
#Sta/Elev= 30
  3746.6  303.77  4001.1  287.93  4269.8  279.64  4411.2   277.8  4602.2  268.31
  4694.1  261.89  4778.9  260.79  4914.6  263.02  4959.4  262.85  4965.5  260.23
  4970.7  262.01  4990.5  257.31    4996   254.3  5031.6  261.38  5055.4  262.01
  5082.7   260.3  5105.1  260.76  5252.2  266.67  5474.2  266.47  5544.8  267.89
  5707.6   270.2  6003.5  277.23  6157.2  275.36  6369.5  277.04  6878.1  286.05
  6937.6  288.51    6965  287.97  7105.8  290.34  7246.5  294.99  7275.9  294.56
#Mann= 5 ,-1 , 0
  3746.6     .17       0  4914.6     .15       0  4959.4     .07       0
  5055.4     .15       0  5544.8     .17       0
Bank Sta=4959.4,5055.4
XS Rating Curve= 0 ,0
Exp/Cntr=0.3,0.1

Chan Stop Cuts=-1
Use User Specified Reach Order=0
Composite Channel Slope=5