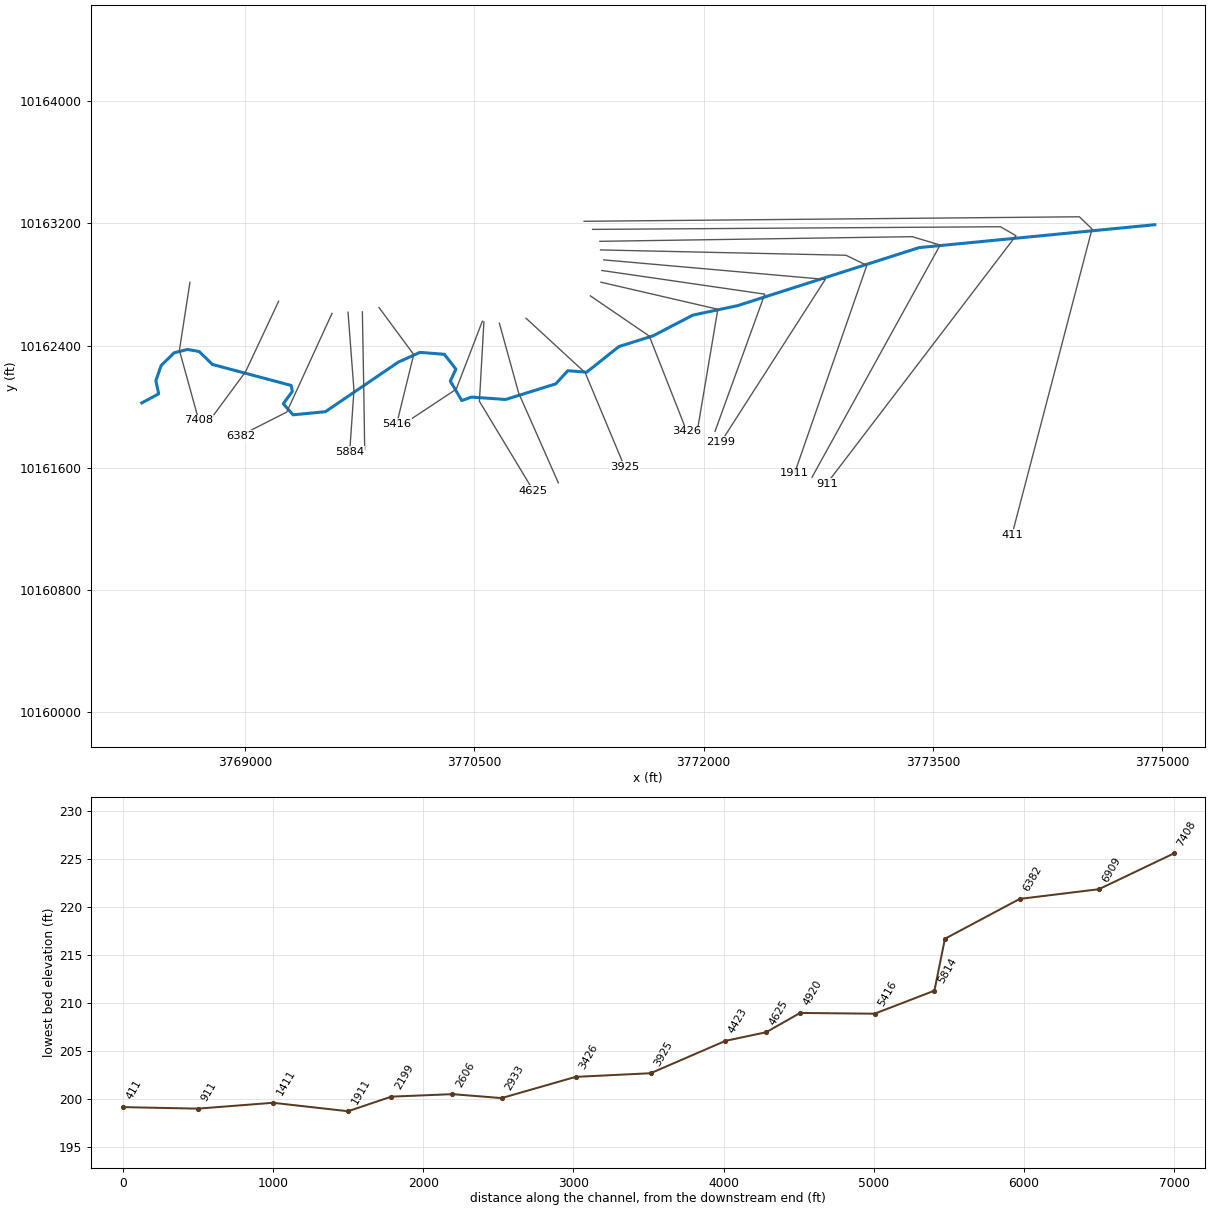
--- CANEY CREEK NORTH TRIB NO 4.prj (project) ---

Proj Title=CANEY CREEK NORTH TRIB NO 4 Base Level Engineering
Current Plan=p01
Default Exp/Contr=0.3,0.1
English Units
Geom File=g01
Flow File=f01
Flow File=f02
Plan File=p01
Y Axis Title=Elevation
X Axis Title(PF)=Main Channel Distance
X Axis Title(XS)=Station
BEGIN DESCRIPTION:
CANEY CREEK NORTH TRIB NO 4
END DESCRIPTION:
DSS Export Rating Curves= 0
DSS Export Rating Curve Sorted= 0
DSS Export Volume Flow Curves= 0
DXF OffsetX= 0
DXF OffsetY= 0
DXF ScaleX= 1
DXF ScaleY= 10

--- CANEY CREEK NORTH TRIB NO 4.p01 (plan) ---

Plan Title=Multiple Run
Short Identifier=Multiple
Geom File=g01
Flow File=f01
Subcritical Flow
K Sum by GR= 0
Std Step Tol= 0.01
Critical Tol= 0.01
Num of Std Step Trials= 20
Max Error Tol= 0.3
Flow Tol Ratio= 0.001
Split Flow NTrial= 30
Split Flow Tol= 0.02
Split Flow Ratio= 0.02
Log Output Level= 0
Friction Slope Method= 1
Unsteady Friction Slope Method= 2
Unsteady Bridges Friction Slope Method= 1
Parabolic Critical Depth
Global Vel Dist=  1 , 1 , 1
Global Log Level= 0
CheckData=True
Encroach Param= -1, 0, 0, 0
BEGIN DESCRIPTION:
Multiple Run
END DESCRIPTION:

--- CANEY CREEK NORTH TRIB NO 4.f01 (steady flow) ---

Flow Title=Multiple
Program Version=4.10
Number of Profiles= 7
Profile Names=10-year,25-year,50-year,1pct_min,100-year,1pct_plu,500-year
River Rch & RM=CANEY CREEK NORT,Reach-1         ,7408
     767    1057    1446     650    1964    5931    3751
River Rch & RM=CANEY CREEK NORT,Reach-1         ,4423
     375     491     647     281     850    2567    1515
Boundary for River Rch & Prof#=CANEY CREEK NORT,Reach-1         , 1
Up Type= 0
Dn Type= 3
Dn Slope=0.005
Boundary for River Rch & Prof#=CANEY CREEK NORT,Reach-1         , 2
Up Type= 0
Dn Type= 3
Dn Slope=0.005
Boundary for River Rch & Prof#=CANEY CREEK NORT,Reach-1         , 3
Up Type= 0
Dn Type= 3
Dn Slope=0.005
Boundary for River Rch & Prof#=CANEY CREEK NORT,Reach-1         , 4
Up Type= 0
Dn Type= 3
Dn Slope=0.005
Boundary for River Rch & Prof#=CANEY CREEK NORT,Reach-1         , 5
Up Type= 0
Dn Type= 3
Dn Slope=0.005
Boundary for River Rch & Prof#=CANEY CREEK NORT,Reach-1         , 6
Up Type= 0
Dn Type= 3
Dn Slope=0.005
Boundary for River Rch & Prof#=CANEY CREEK NORT,Reach-1         , 7
Up Type= 0
Dn Type= 3
Dn Slope=0.005
DSS Import GetInterval= 0
DSS Import GetPeak= 0
DSS Import FillOption= 0

--- CANEY CREEK NORTH TRIB NO 4.f02 (steady flow) ---

Flow Title=Orig_BLE_Flow
Program Version=4.10
Number of Profiles= 7
Profile Names=10-year,25-year,50-year,1pct_min,100-year,1pct_plu,500-year
River Rch & RM=CANEY CREEK NORT,Reach-1         ,7408
     767    1036    1257     500    1511    4564    2181
River Rch & RM=CANEY CREEK NORT,Reach-1         ,4423
     375     481     563     217     654    1975     881
Boundary for River Rch & Prof#=CANEY CREEK NORT,Reach-1         , 1
Up Type= 0
Dn Type= 3
Dn Slope=0.005
Boundary for River Rch & Prof#=CANEY CREEK NORT,Reach-1         , 2
Up Type= 0
Dn Type= 3
Dn Slope=0.005
Boundary for River Rch & Prof#=CANEY CREEK NORT,Reach-1         , 3
Up Type= 0
Dn Type= 3
Dn Slope=0.005
Boundary for River Rch & Prof#=CANEY CREEK NORT,Reach-1         , 4
Up Type= 0
Dn Type= 3
Dn Slope=0.005
Boundary for River Rch & Prof#=CANEY CREEK NORT,Reach-1         , 5
Up Type= 0
Dn Type= 3
Dn Slope=0.005
Boundary for River Rch & Prof#=CANEY CREEK NORT,Reach-1         , 6
Up Type= 0
Dn Type= 3
Dn Slope=0.005
Boundary for River Rch & Prof#=CANEY CREEK NORT,Reach-1         , 7
Up Type= 0
Dn Type= 3
Dn Slope=0.005
DSS Import GetInterval= 0
DSS Import GetPeak= 0
DSS Import FillOption= 0

--- CANEY CREEK NORTH TRIB NO 4.g01 (geometry) ---

Geom Title=Existing Conditions
Program Version=4.10

River Reach=CANEY CREEK NORT,Reach-1
Reach XY= 30
      3768323.01     10162025.06      3768433.49     10162084.44
      3768414.98     10162170.07      3768449.55     10162269.58
      3768533.65     10162352.63      3768622.26     10162374.97
      3768698.27     10162361.26      3768785.03     10162276.73
      3769300.24     10162139.49      3769308.05     10162100.83
      3769248.95     10162019.02      3769313.09     10161947.08
      3769524.79     10161967.58      3770001.14     10162291.69
       3770143.7     10162355.97      3770302.99     10162343.02
      3770378.54     10162246.25      3770342.08     10162167.89
      3770417.06     10162040.52      3770480.65     10162063.27
      3770704.56     10162047.49      3771032.86     10162149.98
      3771110.76     10162235.64      3771234.12     10162226.13
      3771445.96     10162393.89      3771669.15     10162464.19
      3771929.65     10162599.71      3772221.34     10162661.37
       3773410.2     10163041.39      3774952.45     10163191.27

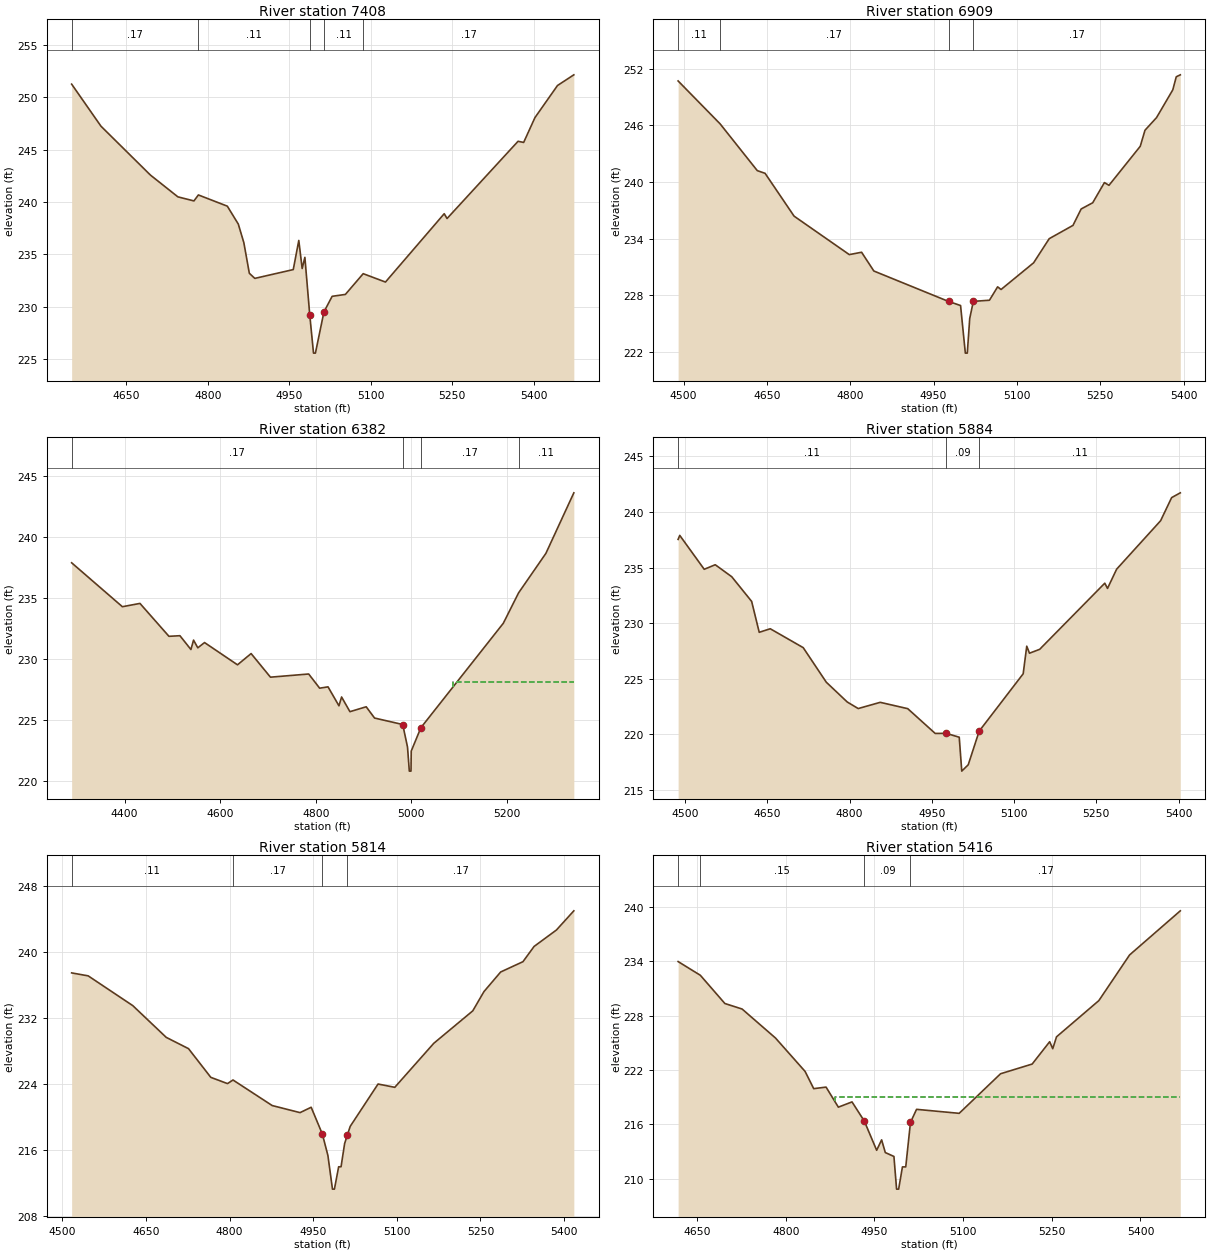
Type RM Length L Ch R = 1 ,7408    ,499,499,499
BEGIN DESCRIPTION:
CANEY CREEK NORTH TRIB NO 4 1.0
END DESCRIPTION:
XS GIS Cut Line= 3
      3768637.98      10162814.4      3768569.01     10162369.01
      3768695.39     10161912.06
#Sta/Elev= 30
  4549.3  251.24  4603.3  247.23  4694.3  242.57  4744.9  240.49  4774.5   240.1
  4782.7  240.67    4836   239.6  4856.2  237.89  4866.4  236.12  4876.5   233.2
  4886.6  232.71  4957.4  233.55  4967.6  236.33  4973.8  233.65  4978.8  234.72
  4987.8  229.21  4994.7  225.58  4998.2  225.58  5013.9  229.51    5029     231
  5053.4  231.18  5086.2  233.16  5127.2  232.36  5235.4  238.88  5240.6  238.42
  5371.4  245.79  5381.7  245.68  5402.5  248.05    5444  251.11  5474.1  252.13
#Mann= 5 ,-1 , 0
  4549.3     .17       0  4782.7     .11       0  4987.8     .09       0
  5013.9     .11       0  5086.2     .17       0
#XS Ineff= 2 ,-1
  4967.6  4856.2  236.33  4978.8  4967.6  234.72
Permanent Ineff=
       F       F
Bank Sta=4987.8,5013.9
XS Rating Curve= 0 ,0
Exp/Cntr=0.3,0.1

Type RM Length L Ch R = 1 ,6909    ,527,527,527
BEGIN DESCRIPTION:
CANEY CREEK NORTH TRIB NO 4 2.0
END DESCRIPTION:
XS GIS Cut Line= 3
       3769218.3     10162690.08      3769001.68     10162228.48
      3768767.87      10161911.1
#Sta/Elev= 30
  4490.1  250.72  4565.7  246.17  4632.6  241.21  4646.7  240.92  4698.9  236.38
  4798.3   232.3  4820.4  232.55  4842.5  230.56  4977.1  227.33  4998.6   226.9
  5007.2  221.85  5010.7  221.85  5015.1  225.53  5021.6  227.34  5050.6  227.46
  5065.3  228.88  5071.5   228.6  5130.1  231.43  5158.2  233.99    5201   235.4
  5215.7  237.14  5236.5   237.8  5257.6  239.94  5265.8  239.65  5322.1  243.79
  5330.6  245.49  5351.4  246.83  5380.7  249.78  5386.9  251.16  5394.2  251.37
#Mann= 4 ,-1 , 0
  4490.1     .11       0  4565.7     .17       0  4977.1     .09       0
  5021.6     .17       0
#XS Ineff= 2 , 0
       0  4820.4  232.55               0
Permanent Ineff=
       F       F
Bank Sta=4977.1,5021.6
XS Rating Curve= 0 ,0
Exp/Cntr=0.3,0.1

Type RM Length L Ch R = 1 ,6382    ,498,498,498
BEGIN DESCRIPTION:
CANEY CREEK NORTH TRIB NO 4 3.0
END DESCRIPTION:
XS GIS Cut Line= 3
      3769567.86     10162611.09      3769271.47     10161964.92
      3768967.83     10161811.06
#Sta/Elev= 30
  4289.1  237.87  4395.3  234.28  4432.1  234.55  4492.8  231.86  4515.8  231.91
  4538.8  230.78  4544.3  231.55  4553.2  230.92  4567.3  231.35  4636.3  229.53
  4664.8  230.45  4705.3  228.52  4785.3  228.78  4808.3  227.62  4825.8  227.73
  4848.7  226.18  4854.2   226.9  4871.7   225.7  4905.7   226.1  4923.2  225.18
  4982.2  224.65  4992.2  222.81    4996  220.84  4999.5  220.84    5000  222.48
  5020.2  224.39  5192.8  232.93  5224.7  235.41  5281.9  238.64  5340.4  243.59
#Mann= 4 ,-1 , 0
  4289.1     .17       0  4982.2     .09       0  5020.2     .17       0
  5224.7     .11       0
#XS Ineff= 2 , 0
       0                    5087       0  228.15
Permanent Ineff=
       F       F
Bank Sta=4982.2,5020.2
XS Rating Curve= 0 ,0
Exp/Cntr=0.3,0.1

Type RM Length L Ch R = 1 ,5884    ,70,70,70
BEGIN DESCRIPTION:
CANEY CREEK NORTH TRIB NO 4 4.0
END DESCRIPTION:
XS GIS Cut Line= 3
      3769672.58     10162618.55      3769711.49     10162107.43
      3769683.54      10161705.3
#Sta/Elev= 30
  4487.4  237.54  4490.4   237.9    4535  234.85  4555.1  235.26  4585.2  234.18
  4621.5  231.96  4635.3  229.18  4655.4   229.5  4715.5   227.8  4757.6  224.69
  4795.8  222.91  4815.8  222.32  4855.9  222.88  4906.1  222.31  4956.2  220.08
  4976.3  220.09    5000  219.74  5004.6  216.69  5016.4  217.26  5036.4  220.29
  5116.6  225.45  5123.1  227.93  5128.1   227.3  5146.7  227.65  5265.4   233.6
  5270.4  233.13    5287  234.86  5367.2  239.22  5387.3   241.3  5403.1  241.73
#Mann= 3 , 0 , 0
  4487.4     .11       0  4976.3     .09       0  5036.4     .11       0
#XS Ineff= 2 , 0
       0  4906.1  222.31               0
Permanent Ineff=
       F       F
Bank Sta=4976.3,5036.4
XS Rating Curve= 0 ,0
Exp/Cntr=0.3,0.1

Type RM Length L Ch R = 1 ,5814    ,398,398,398
BEGIN DESCRIPTION:
CANEY CREEK NORTH TRIB NO 4 5.5
END DESCRIPTION:
XS GIS Cut Line= 3
      3769766.39     10162620.77       3769775.3     10162137.45
      3769781.66      10161719.8
#Sta/Elev= 30
  4516.6  237.51  4546.3  237.15  4626.3  233.54  4686.3  229.69  4726.3  228.32
  4766.3  224.84  4796.3  224.08  4806.1  224.52  4876.4  221.42  4926.4  220.56
  4946.4  221.21  4966.4  217.97  4976.4  215.37  4984.6  211.28  4988.1  211.28
  4995.7  213.99    5000  213.99  5006.4   216.8 5011.22  217.81  5016.4  218.89
  5066.4  224.03  5096.4  223.63  5166.4  228.97  5236.4  232.91  5256.4  235.24
  5286.4  237.62  5326.4  238.87  5346.4  240.72  5386.4  242.71  5417.7  245.04
#Mann= 4 ,-1 , 0
  4516.6     .11       0  4806.1     .17       0  4966.4     .09       0
 5011.22     .17       0
Bank Sta=4966.4,5011.22
XS Rating Curve= 0 ,0
Exp/Cntr=0.3,0.1

Type RM Length L Ch R = 1 ,5416    ,496,496,496
BEGIN DESCRIPTION:
CANEY CREEK NORTH TRIB NO 4 5.0
END DESCRIPTION:
XS GIS Cut Line= 3
      3769875.47     10162649.14      3770102.49     10162341.66
      3769991.09     10161887.73
#Sta/Elev= 30
  4617.8  233.95  4655.4  232.44  4696.9  229.33  4726.1  228.72  4782.5  225.53
  4832.6  221.85  4847.2  219.95  4868.1  220.12  4888.9  217.91    4912  218.49
  4932.8  216.38  4953.7  213.16  4962.1  214.31  4968.3  212.91  4982.9  212.48
  4987.4  208.88  4990.9  208.88  4997.3  211.33  5002.9  211.33  5010.9  216.23
  5021.2  217.67  5093.3  217.23  5163.3  221.59  5216.8  222.66  5246.4  225.12
  5251.6  224.35    5258  225.66  5329.6  229.65  5381.6  234.68  5467.4  239.54
#Mann= 4 ,-1 , 0
  4617.8     .11       0  4655.4     .15       0  4932.8     .09       0
  5010.9     .17       0
#XS Ineff= 2 ,-1
  4868.1  4826.4  220.12  4882.7  4868.1  219.01
Permanent Ineff=
       F       F
Bank Sta=4932.8,5010.9
XS Rating Curve= 0 ,0
Exp/Cntr=0.3,0.1

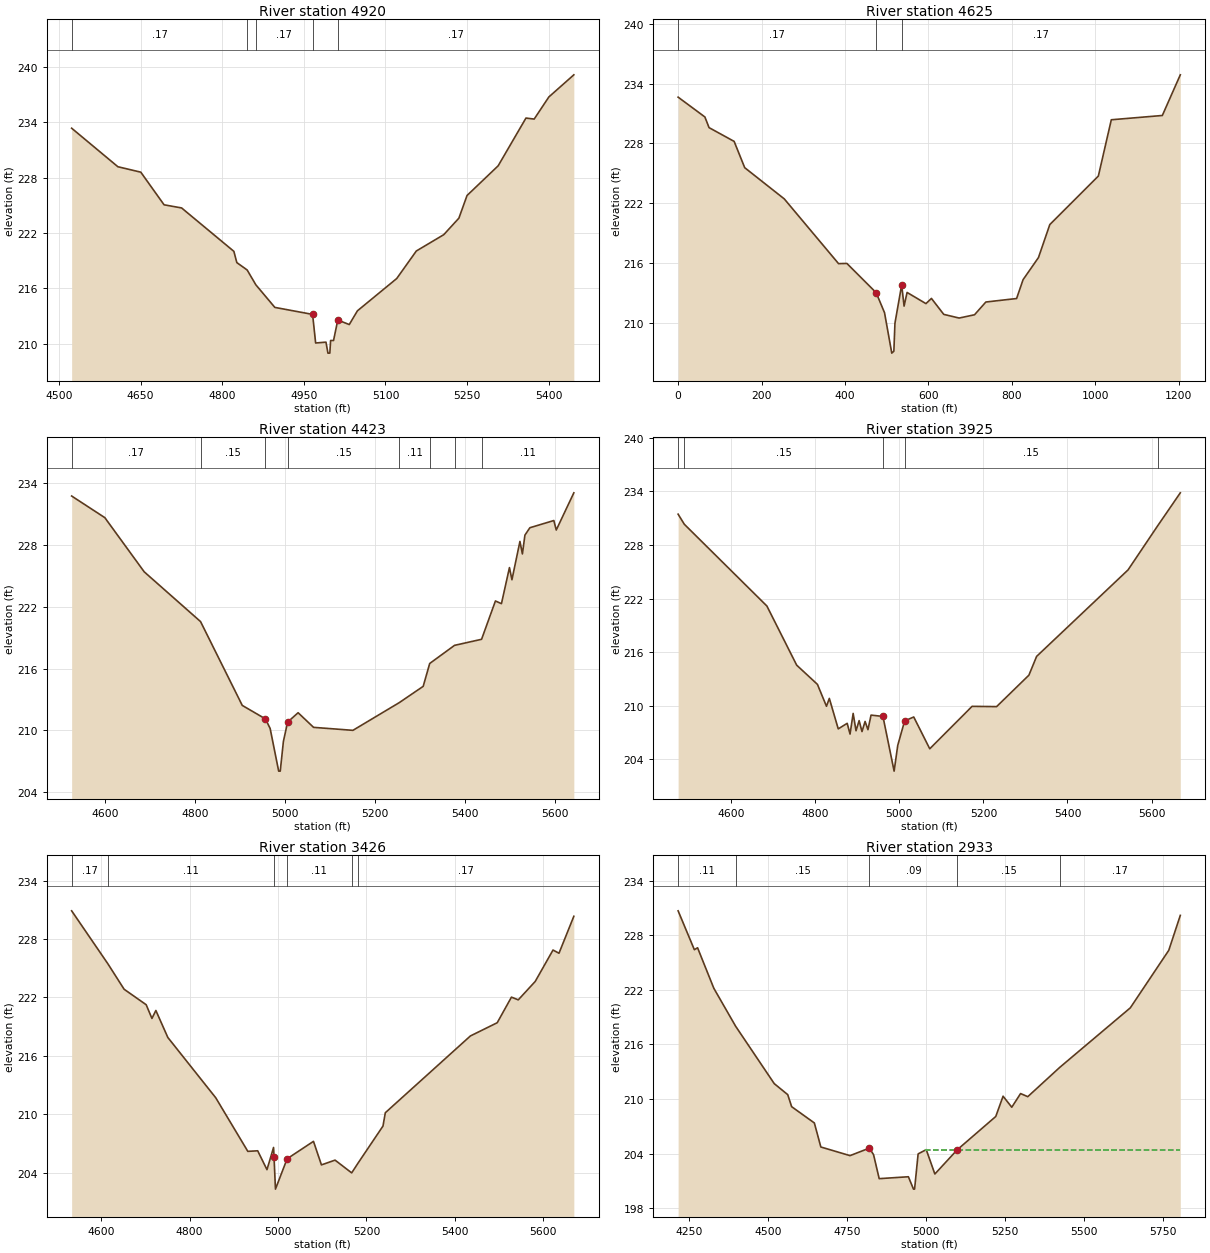
Type RM Length L Ch R = 1 ,4920    ,226,226,226
BEGIN DESCRIPTION:
CANEY CREEK NORTH TRIB NO 4 6.0
END DESCRIPTION:
XS GIS Cut Line= 3
      3770551.76     10162559.66      3770380.59     10162114.65
      3770008.55     10161868.12
#Sta/Elev= 30
  4523.2  233.36  4608.2  229.18  4650.3  228.59  4693.1  225.05  4725.3  224.71
  4821.4     220  4826.8  218.78  4845.8  217.98  4861.8  216.37  4896.7  213.92
  4966.1  213.16  4971.7  210.06  4990.7  210.15  4994.3  208.96  4997.8  208.96
  4999.2  210.33  5004.6  210.33  5012.4  212.55  5033.5  212.06  5048.5  213.55
  5120.7  217.05  5156.8  220.04  5207.2  221.81    5235   223.6    5250  226.06
  5307.2  229.28  5358.3  234.46  5373.4  234.35  5400.4  236.75  5446.3  239.15
#Mann= 5 ,-1 , 0
  4523.2     .17       0  4845.8     .15       0  4861.8     .17       0
  4966.1     .09       0  5012.4     .17       0
Bank Sta=4966.1,5012.4
XS Rating Curve= 0 ,0
Exp/Cntr=0.3,0.1

Type RM Length L Ch R = 1 ,4625    ,271,271,271
XS GIS Cut Line= 3
      3770561.88     10162555.14      3770532.52     10162035.43
      3770885.82     10161450.26
#Sta/Elev= 30
       0  232.64    64.2  230.65    74.2  229.58   134.3   228.2   159.7  225.56
   254.5  222.43   384.7  215.93   404.7  215.95   474.8  213.02   494.9  211.01
   512.3  206.95   517.3  207.14   519.9  209.95     536  213.79   541.8  211.67
     549  213.04   594.2  211.92   607.4  212.44   636.9  210.84   673.8  210.47
   710.7   210.8   737.9  212.08   811.6  212.43   827.1  214.32     864  216.54
   891.2  219.85  1007.6  224.72  1038.7  230.37    1161   230.8  1204.1  234.88
#Mann= 3 , 0 , 0
       0     .17       0   474.8     .09       0     536     .17       0
Bank Sta=474.8,536
XS Rating Curve= 0 ,0
Exp/Cntr=0.3,0.1

Type RM Length L Ch R = 1 ,4423    ,498,498,498
BEGIN DESCRIPTION:
CANEY CREEK NORTH TRIB NO 4 7.0
END DESCRIPTION:
XS GIS Cut Line= 3
      3770663.04     10162546.59       3770789.5     10162089.15
      3771049.19     10161501.58
#Sta/Elev= 30
  4525.4  232.76  4599.2  230.66  4686.8   225.4  4812.1  220.57  4904.9  212.43
  4956.5  211.12  4966.9  210.19  4985.9  206.05  4989.4  206.05  4996.4  208.94
  5005.8  210.81  5029.1  211.72  5063.5   210.3    5151  210.01  5254.1   212.7
  5307.3  214.28  5321.8   216.5    5377  218.26  5437.2  218.85    5468  222.57
  5481.4  222.31  5499.2  225.81  5504.7  224.63  5522.5  228.35    5528  227.14
  5533.6  228.96  5544.6  229.68  5597.9  230.38  5603.3  229.46  5642.4  233.07
#Mann= 8 ,-1 , 0
  4525.4     .17       0  4812.1     .15       0  4956.5     .09       0
  5005.8     .15       0  5254.1     .11       0  5321.8     .15       0
    5377     .17       0  5437.2     .11       0
#XS Ineff= 2 ,-1
  5029.1  5226.5  211.72  5226.5  5249.4  211.95
Permanent Ineff=
       F       F
Bank Sta=4956.5,5005.8
XS Rating Curve= 0 ,0
Exp/Cntr=0.3,0.1

Type RM Length L Ch R = 1 ,3925    ,499,499,499
BEGIN DESCRIPTION:
CANEY CREEK NORTH TRIB NO 4 8.0
END DESCRIPTION:
XS GIS Cut Line= 3
      3770837.53     10162579.36      3771224.92     10162222.51
      3771482.68      10161605.7
#Sta/Elev= 30
  4473.3  231.44  4488.1  230.31  4684.6  221.16  4755.5  214.54  4804.9  212.39
  4826.4  209.94  4833.2  210.82  4854.4  207.41  4875.7  208.03  4882.5  206.83
  4889.9  209.14  4896.7   207.2  4904.1  208.33  4910.9  207.11  4918.3  208.24
  4925.1  207.32  4932.5  208.95  4960.8   208.8  4987.4  202.68    4996  205.56
  5012.4   208.3  5034.1  208.74  5072.2  205.18  5172.9  209.93  5231.3   209.9
  5308.2  213.42  5326.5  215.52  5544.1   225.2  5614.5  230.13  5668.5  233.83
#Mann= 5 ,-1 , 0
  4473.3     .17       0  4488.1     .15       0  4960.8     .09       0
  5012.4     .15       0  5614.5     .17       0
#XS Ineff= 2 ,-1
  4889.9  4833.2  209.14  4960.8  4840.6   208.8
Permanent Ineff=
       F       F
Bank Sta=4960.8,5012.4
XS Rating Curve= 0 ,0
Exp/Cntr=0.3,0.1

Type RM Length L Ch R = 1 ,3426    ,493,493,493
BEGIN DESCRIPTION:
CANEY CREEK NORTH TRIB NO 4 9.0
END DESCRIPTION:
XS GIS Cut Line= 3
      3771258.61      10162725.5      3771644.16     10162462.53
       3771889.1     10161839.77
#Sta/Elev= 30
  4533.3   230.9  4615.5  225.44    4652  222.84  4701.9  221.25  4714.9  219.84
  4723.8  220.66  4750.8  217.89  4859.2  211.69  4931.8  206.18  4954.1  206.24
  4975.1   204.3    4990  206.58 4991.06   205.6  4994.3   202.3  5020.7  205.42
  5080.3  207.21  5098.3  204.79  5129.1  205.28  5166.7  203.97  5180.6  204.94
  5237.5  208.78  5242.8  210.15  5435.2  218.04  5495.9   219.4  5528.1  222.03
  5543.5  221.75  5581.8  223.64  5622.1  226.87  5635.6  226.54  5669.2  230.34
#Mann= 6 ,-1 , 0
  4533.3     .17       0  4615.5     .11       0 4991.06     .09       0
  5020.7     .11       0  5166.7     .11       0  5180.6     .17       0
#XS Ineff= 2 , 0
       0    4990  206.58  5080.3       0  207.21
Permanent Ineff=
       T       T
Bank Sta=4991.06,5020.7
XS Rating Curve= 0 ,0
Exp/Cntr=0.3,0.1

Type RM Length L Ch R = 1 ,2933    ,327,327,327
BEGIN DESCRIPTION:
CANEY CREEK NORTH TRIB NO 4 10.0
END DESCRIPTION:
XS GIS Cut Line= 3
      3771327.81       10162815.      3772092.98      10162637.9
      3771959.09     10161845.12
#Sta/Elev= 30
  4214.6  230.67    4266   226.4  4276.2  226.61  4327.6  222.16  4396.6  217.99
  4518.9  211.68  4561.6  210.47  4573.9  209.15  4645.8  207.36  4666.3  204.72
  4758.7  203.77  4820.2   204.6  4833.2  203.87    4851  201.24  4943.4  201.45
  4959.5  200.09    4963  200.09  4974.2  203.96  4999.9  204.43  5027.2  201.75
  5098.2  204.42  5219.9  208.07  5243.1   210.3  5270.6  209.09  5298.5  210.59
  5321.3  210.25  5422.5  213.47  5645.8  220.01  5767.5  226.33    5804  230.17
#Mann= 5 ,-1 , 0
  4214.6     .11       0  4396.6     .15       0  4820.2     .09       0
  5098.2     .15       0  5422.5     .17       0
#XS Ineff= 2 , 0
       0  4820.2   204.6  4994.7       0  204.44
Permanent Ineff=
       F       F
Bank Sta=4820.2,5098.2
XS Rating Curve= 0 ,0
Exp/Cntr=0.3,0.1

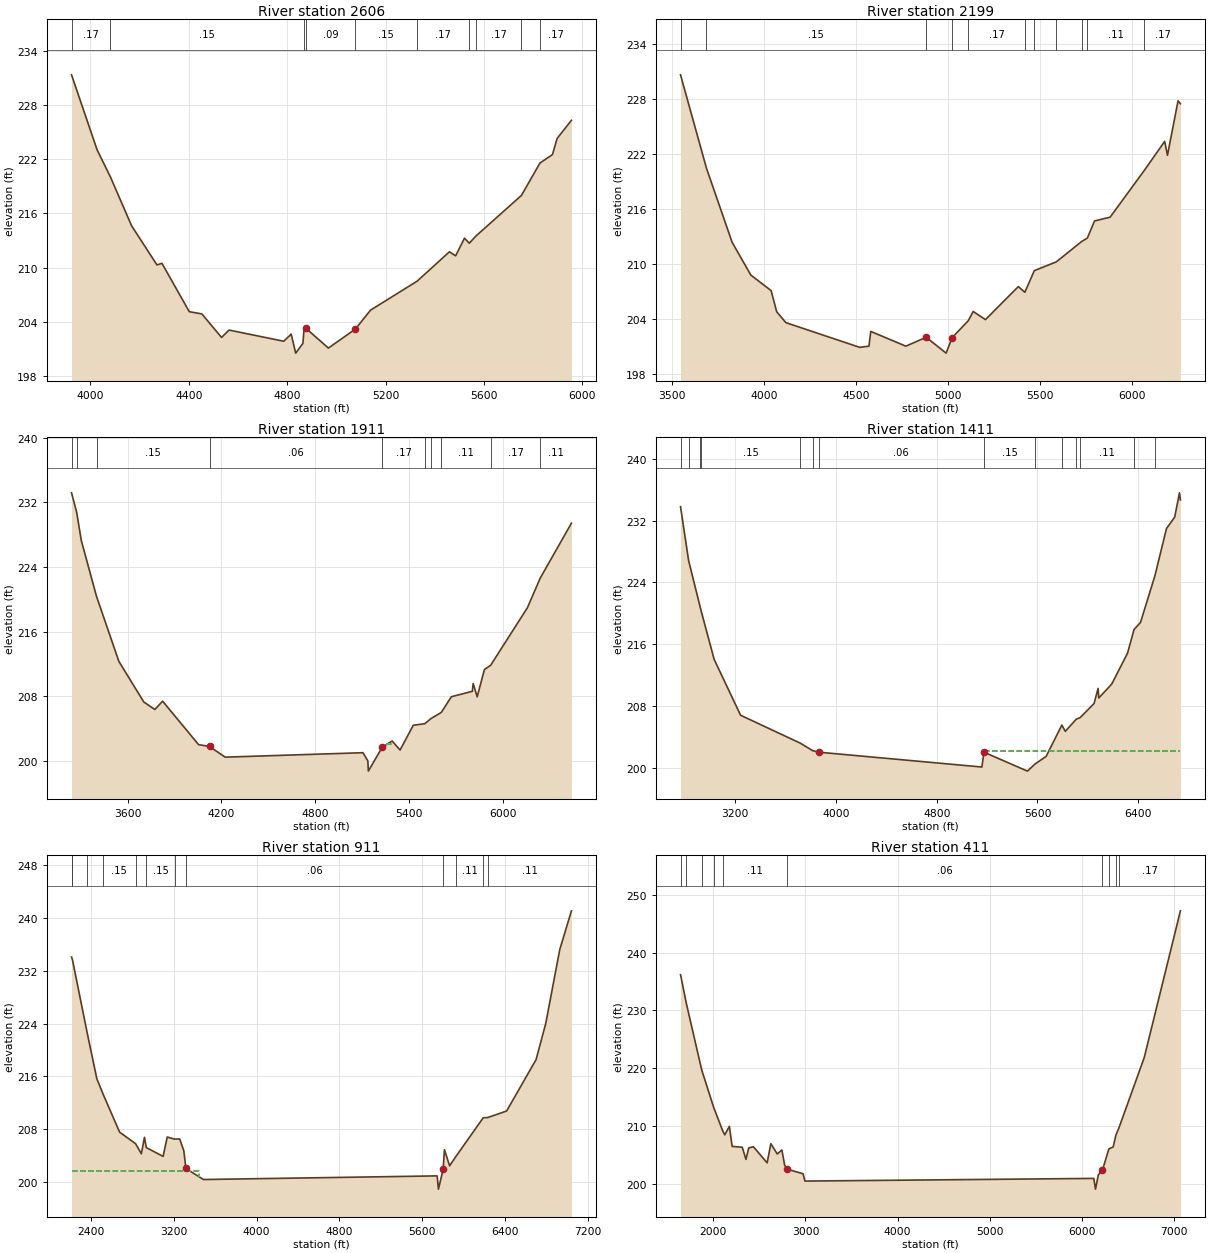
Type RM Length L Ch R = 1 ,2606    ,407,407,407
BEGIN DESCRIPTION:
CANEY CREEK NORTH TRIB NO 4 11.0
END DESCRIPTION:
XS GIS Cut Line= 3
      3771334.05     10162891.61      3772399.97      10162736.8
       3772074.3     10161838.41
#Sta/Elev= 30
  3922.9  231.39  4026.9  223.06  4081.3  220.04  4167.2  214.63  4270.3  210.29
  4290.5  210.47  4401.7   205.1  4452.9  204.85    4533  202.24  4563.3  203.06
  4785.7  201.82    4816  202.61  4834.4   200.5  4863.7  201.58  4868.7  203.26
  4876.6  203.24  4967.5  201.06  5077.4  203.18  5138.7  205.27  5328.4  208.49
  5459.6  211.75  5484.7   211.3  5520.8  213.26  5540.4   212.7  5565.8  213.46
  5752.5  218.01  5827.6   221.6  5878.3  222.53  5897.7  224.34  5955.6  226.34
#Mann= 10 ,-1 , 0
  3922.9     .17       0  4081.3     .15       0  4868.7     .12       0
  4876.6     .09       0  5077.4     .15       0  5328.4     .17       0
  5540.4     .11       0  5565.8     .17       0  5752.5     .11       0
  5827.6     .17       0
Bank Sta=4876.6,5077.4
XS Rating Curve= 0 ,0
Exp/Cntr=0.3,0.1

Type RM Length L Ch R = 1 ,2199    ,288,288,288
BEGIN DESCRIPTION:
CANEY CREEK NORTH TRIB NO 4 12.0
END DESCRIPTION:
XS GIS Cut Line= 3
      3771347.07     10162961.06      3772795.94     10162833.26
       3772113.4     10161769.03
#Sta/Elev= 30
  3545.5  230.64  3686.7  220.43  3826.1  212.35  3927.8  208.77  4038.2  207.07
  4068.3  204.77  4118.5  203.57  4520.1  200.87  4570.2     201  4580.3  202.61
    4771     201  4881.5  201.97  4990.1  200.24  5022.3  201.92  5110.5  203.78
  5137.3  204.79    5204   203.9  5382.8  207.51  5418.2  206.89  5469.7  209.25
  5589.4  210.21  5727.6  212.44  5758.2  212.81  5797.4  214.68    5882  215.09
  6068.3  220.21  6178.7  223.37  6193.9  221.85  6251.4   227.8  6264.3  227.48
#Mann= 11 ,-1 , 0
  3545.5     .17       0  3686.7     .15       0  4881.5     .06       0
  5022.3     .11       0  5110.5     .17       0  5418.2     .15       0
  5469.7     .17       0  5589.4     .11       0  5727.6     .17       0
  5758.2     .11       0  6068.3     .17       0
#XS Ineff= 2 , 0
       0  4580.3  202.61               0
Permanent Ineff=
       F       F
Bank Sta=4881.5,5022.3
XS Rating Curve= 0 ,0
Exp/Cntr=0.3,0.1

Type RM Length L Ch R = 1 ,1911    ,500,500,500
BEGIN DESCRIPTION:
CANEY CREEK NORTH TRIB NO 4 12.5
END DESCRIPTION:
XS GIS Cut Line= 4
       3771325.3     10163026.16      3772931.23     10162991.44
      3773067.91     10162925.41      3772595.35     10161565.58
#Sta/Elev= 30
  3241.9  233.17  3275.1  230.73  3304.5  227.25  3401.6  220.36  3544.5  212.31
  3704.1  207.28  3774.6  206.35  3824.6  207.38  4054.6     202  4124.7  201.77
  4224.7  200.45    5106     201  5137.1     200  5140.6  198.72  5230.4  201.71
  5292.7  202.45  5343.4  201.33  5428.1   204.4  5501.4  204.59  5542.1  205.24
  5606.9  205.98  5671.6  207.93  5805.7   208.6    5811  209.57  5836.8  207.92
  5883.3   211.3  5923.3  211.83  6158.5  218.96  6239.7   222.6  6439.6  229.41
#Mann= 10 ,-1 , 0
  3241.9     .11       0  3275.1     .17       0  3401.6     .15       0
  4124.7     .06       0  5230.4     .17       0  5501.4     .11       0
  5542.1     .17       0  5606.9     .11       0  5923.3     .17       0
  6239.7     .11       0
#XS Ineff= 2 ,-1
  5256.3  5292.7  202.08  5292.7  5380.7  202.45
Permanent Ineff=
       F       F
Bank Sta=4124.7,5230.4
XS Rating Curve= 0 ,0
Exp/Cntr=0.3,0.1

Type RM Length L Ch R = 1 ,1411    ,500,500,500
BEGIN DESCRIPTION:
CANEY CREEK NORTH TRIB NO 4 13.0
END DESCRIPTION:
XS GIS Cut Line= 4
      3771321.01     10163082.59      3773365.26     10163112.97
      3773547.76     10163058.27      3772709.47       10161539.
#Sta/Elev= 30
    2765   233.8    2829  226.85  2918.6  220.97  2926.5  220.45  3031.9  214.06
  3241.9  206.83  3715.7  203.22  3814.3  202.25    3862  202.05  5158.7  200.13
  5174.8  202.05  5520.2   199.6  5579.7  200.51  5668.7  201.51  5793.5  205.55
  5821.1  204.75  5908.2  206.32  5938.9  206.52  6049.2  208.34  6081.3  210.29
    6087  209.06  6190.2  210.87  6315.1  214.85    6367  217.92  6418.2  218.83
  6532.8  224.87  6624.5  230.97  6689.8  232.45  6727.7  235.59  6735.2  234.68
#Mann= 14 ,-1 , 0
    2765     .17       0    2829     .11       0  2918.6     .17       0
  2926.5     .15       0  3715.7     .11       0  3814.3     .15       0
    3862     .06       0  5174.8     .15       0  5579.7     .17       0
  5793.5     .11       0  5908.2     .17       0  5938.9     .11       0
    6367     .17       0  6532.8     .11       0
#XS Ineff= 2 , 0
       0                  5180.5       0  202.15
Permanent Ineff=
       F       F
Bank Sta=3862,5174.8
XS Rating Curve= 0 ,0
Exp/Cntr=0.3,0.1

Type RM Length L Ch R = 1 ,911     ,500,500,500
BEGIN DESCRIPTION:
CANEY CREEK NORTH TRIB NO 4 14.0
END DESCRIPTION:
XS GIS Cut Line= 4
      3771273.25     10163160.71      3773942.52     10163178.07
      3774044.04     10163119.17      3772805.13     10161495.82
#Sta/Elev= 30
  2213.3  234.04  2222.3  233.62    2361  222.85  2457.9  215.65  2518.3  213.33
  2677.9  207.59  2831.8  205.86  2887.9  204.33  2917.9  206.82  2935.3  205.26
  3097.9  203.94  3137.9  206.86  3208.9  206.54  3257.9  206.57  3297.9  204.78
  3317.9  202.11  3487.9  200.44  5744.9  200.99  5757.5  198.99  5802.7  201.96
  5815.6  204.94  5865.6  202.51  5924.4  203.88  6190.3  209.77  6234.2   209.8
  6416.1  210.79  6700.9  218.56  6794.4  224.03  6929.5  235.17  7042.1  241.02
#Mann= 12 ,-1 , 0
  2213.3     .11       0  2222.3     .17       0    2361     .11       0
  2518.3     .15       0  2831.8     .11       0  2935.3     .15       0
  3208.9     .11       0  3317.9     .06       0  5802.7     .15       0
  5924.4     .11       0  6190.3     .17       0  6234.2     .11       0
#XS Ineff= 2 , 0
       0  3447.9  201.79               0
Permanent Ineff=
       F       F
Bank Sta=3317.9,5802.7
XS Rating Curve= 0 ,0
Exp/Cntr=0.3,0.1

Type RM Length L Ch R = 1 ,411     ,0,0,0
BEGIN DESCRIPTION:
CANEY CREEK NORTH TRIB NO 4 15.0
END DESCRIPTION:
XS GIS Cut Line= 4
      3771217.71     10163213.66      3774459.01     10163243.18
      3774541.89      10163163.5      3774017.84     10161161.04
#Sta/Elev= 30
  1643.6  236.18  1706.1  231.26  1873.7  219.72    2002  213.33  2100.7  209.24
  2123.8  208.52  2173.8  209.99  2203.8  206.53  2313.8  206.38  2353.8  204.29
  2383.8  206.25  2433.8  206.48  2583.8  203.69  2623.8     207  2693.8  205.22
  2743.8  205.91  2773.8  203.28  2803.8  202.58  2973.8  201.81  2993.8  200.54
  6129.2     201    6148  199.15  6178.4  201.59    6224  202.44  6293.2  206.09
  6340.1  206.43  6370.1  208.51  6400.4  209.63  6677.1  221.86  7069.9   247.2
#Mann= 10 ,-1 , 0
  1643.6     .11       0  1706.1     .17       0  1873.7     .11       0
    2002     .17       0  2100.7     .11       0  2803.8     .06       0
    6224     .11       0  6293.2     .17       0  6370.1     .11       0
  6400.4     .17       0
Bank Sta=2803.8,6224
XS Rating Curve= 0 ,0
Exp/Cntr=0.3,0.1

Chan Stop Cuts=-1
Use User Specified Reach Order=0
Composite Channel Slope=5