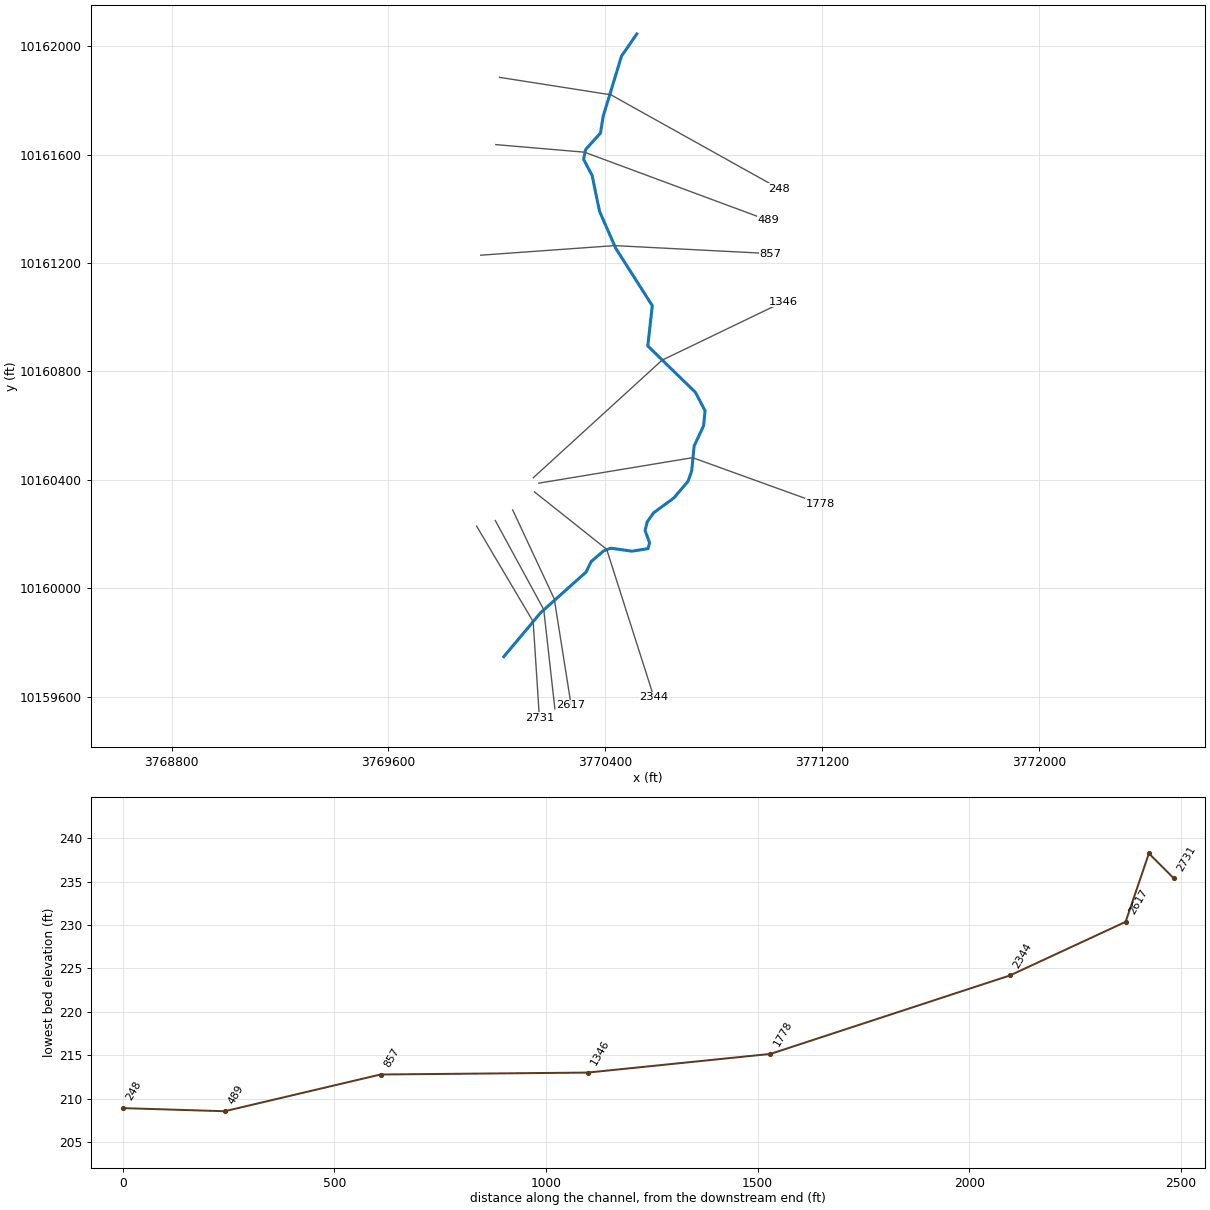
--- CANEY CREEK NORTH TRIB NO 4_1.prj (project) ---

Proj Title=CANEY CREEK NORTH TRIB NO 4_1 Base Level Engineering
Current Plan=p01
Default Exp/Contr=0.3,0.1
English Units
Geom File=g01
Flow File=f01
Flow File=f02
Plan File=p01
Y Axis Title=Elevation
X Axis Title(PF)=Main Channel Distance
X Axis Title(XS)=Station
BEGIN DESCRIPTION:
CANEY CREEK NORTH TRIB NO 4_1
END DESCRIPTION:
DSS Export Rating Curves= 0
DSS Export Rating Curve Sorted= 0
DSS Export Volume Flow Curves= 0
DXF OffsetX= 0
DXF OffsetY= 0
DXF ScaleX= 1
DXF ScaleY= 10

--- CANEY CREEK NORTH TRIB NO 4_1.p01 (plan) ---

Plan Title=Multiple Run
Short Identifier=Multiple
Geom File=g01
Flow File=f01
Subcritical Flow
K Sum by GR= 0
Std Step Tol= 0.01
Critical Tol= 0.01
Num of Std Step Trials= 20
Max Error Tol= 0.3
Flow Tol Ratio= 0.001
Split Flow NTrial= 30
Split Flow Tol= 0.02
Split Flow Ratio= 0.02
Log Output Level= 0
Friction Slope Method= 1
Unsteady Friction Slope Method= 2
Unsteady Bridges Friction Slope Method= 1
Parabolic Critical Depth
Global Vel Dist=  1 , 1 , 1
Global Log Level= 0
CheckData=True
Encroach Param= -1, 0, 0, 0
BEGIN DESCRIPTION:
Multiple Run
END DESCRIPTION:

--- CANEY CREEK NORTH TRIB NO 4_1.f01 (steady flow) ---

Flow Title=Multiple
Program Version=4.10
Number of Profiles= 7
Profile Names=10-year,25-year,50-year,1pct_min,100-year,1pct_plu,500-year
River Rch & RM=CANEY CREEK NORT,Reach-1         ,2731
     435     578     771     339    1024    3092    1864
Boundary for River Rch & Prof#=CANEY CREEK NORT,Reach-1         , 1
Up Type= 0
Dn Type= 3
Dn Slope=0.011
Boundary for River Rch & Prof#=CANEY CREEK NORT,Reach-1         , 2
Up Type= 0
Dn Type= 3
Dn Slope=0.011
Boundary for River Rch & Prof#=CANEY CREEK NORT,Reach-1         , 3
Up Type= 0
Dn Type= 3
Dn Slope=0.011
Boundary for River Rch & Prof#=CANEY CREEK NORT,Reach-1         , 4
Up Type= 0
Dn Type= 3
Dn Slope=0.011
Boundary for River Rch & Prof#=CANEY CREEK NORT,Reach-1         , 5
Up Type= 0
Dn Type= 3
Dn Slope=0.011
Boundary for River Rch & Prof#=CANEY CREEK NORT,Reach-1         , 6
Up Type= 0
Dn Type= 3
Dn Slope=0.011
Boundary for River Rch & Prof#=CANEY CREEK NORT,Reach-1         , 7
Up Type= 0
Dn Type= 3
Dn Slope=0.011
DSS Import GetInterval= 0
DSS Import GetPeak= 0
DSS Import FillOption= 0

--- CANEY CREEK NORTH TRIB NO 4_1.f02 (steady flow) ---

Flow Title=Orig_BLE_Flow
Program Version=4.10
Number of Profiles= 7
Profile Names=10-year,25-year,50-year,1pct_min,100-year,1pct_plu,500-year
River Rch & RM=CANEY CREEK NORT,Reach-1         ,2731
     435     567     670     261     788    2379    1084
Boundary for River Rch & Prof#=CANEY CREEK NORT,Reach-1         , 1
Up Type= 0
Dn Type= 3
Dn Slope=0.011
Boundary for River Rch & Prof#=CANEY CREEK NORT,Reach-1         , 2
Up Type= 0
Dn Type= 3
Dn Slope=0.011
Boundary for River Rch & Prof#=CANEY CREEK NORT,Reach-1         , 3
Up Type= 0
Dn Type= 3
Dn Slope=0.011
Boundary for River Rch & Prof#=CANEY CREEK NORT,Reach-1         , 4
Up Type= 0
Dn Type= 3
Dn Slope=0.011
Boundary for River Rch & Prof#=CANEY CREEK NORT,Reach-1         , 5
Up Type= 0
Dn Type= 3
Dn Slope=0.011
Boundary for River Rch & Prof#=CANEY CREEK NORT,Reach-1         , 6
Up Type= 0
Dn Type= 3
Dn Slope=0.011
Boundary for River Rch & Prof#=CANEY CREEK NORT,Reach-1         , 7
Up Type= 0
Dn Type= 3
Dn Slope=0.011
DSS Import GetInterval= 0
DSS Import GetPeak= 0
DSS Import FillOption= 0

--- CANEY CREEK NORTH TRIB NO 4_1.g01 (geometry) ---

Geom Title=Existing Conditions
Program Version=4.10

River Reach=CANEY CREEK NORT,Reach-1
Reach XY= 30
      3770025.89     10159747.21      3770162.16     10159909.83
      3770329.17     10160059.22      3770348.51     10160098.36
      3770393.35     10160136.98      3770420.34     10160147.64
      3770498.79     10160136.54      3770558.18     10160145.87
      3770563.74     10160167.16      3770547.29     10160212.48
      3770555.08     10160244.84      3770578.89     10160278.19
      3770653.86     10160333.27      3770705.93     10160394.96
       3770719.3     10160432.62      3770728.18     10160524.35
      3770763.05     10160598.92      3770768.68     10160654.75
      3770733.05     10160722.63      3770557.26     10160893.78
      3770573.79     10161042.45      3770439.11     10161254.08
      3770379.24     10161390.39      3770351.65     10161523.41
      3770320.19     10161582.74      3770327.72     10161618.58
      3770382.76     10161679.78      3770392.68     10161741.83
      3770460.32     10161963.56      3770516.62     10162045.14

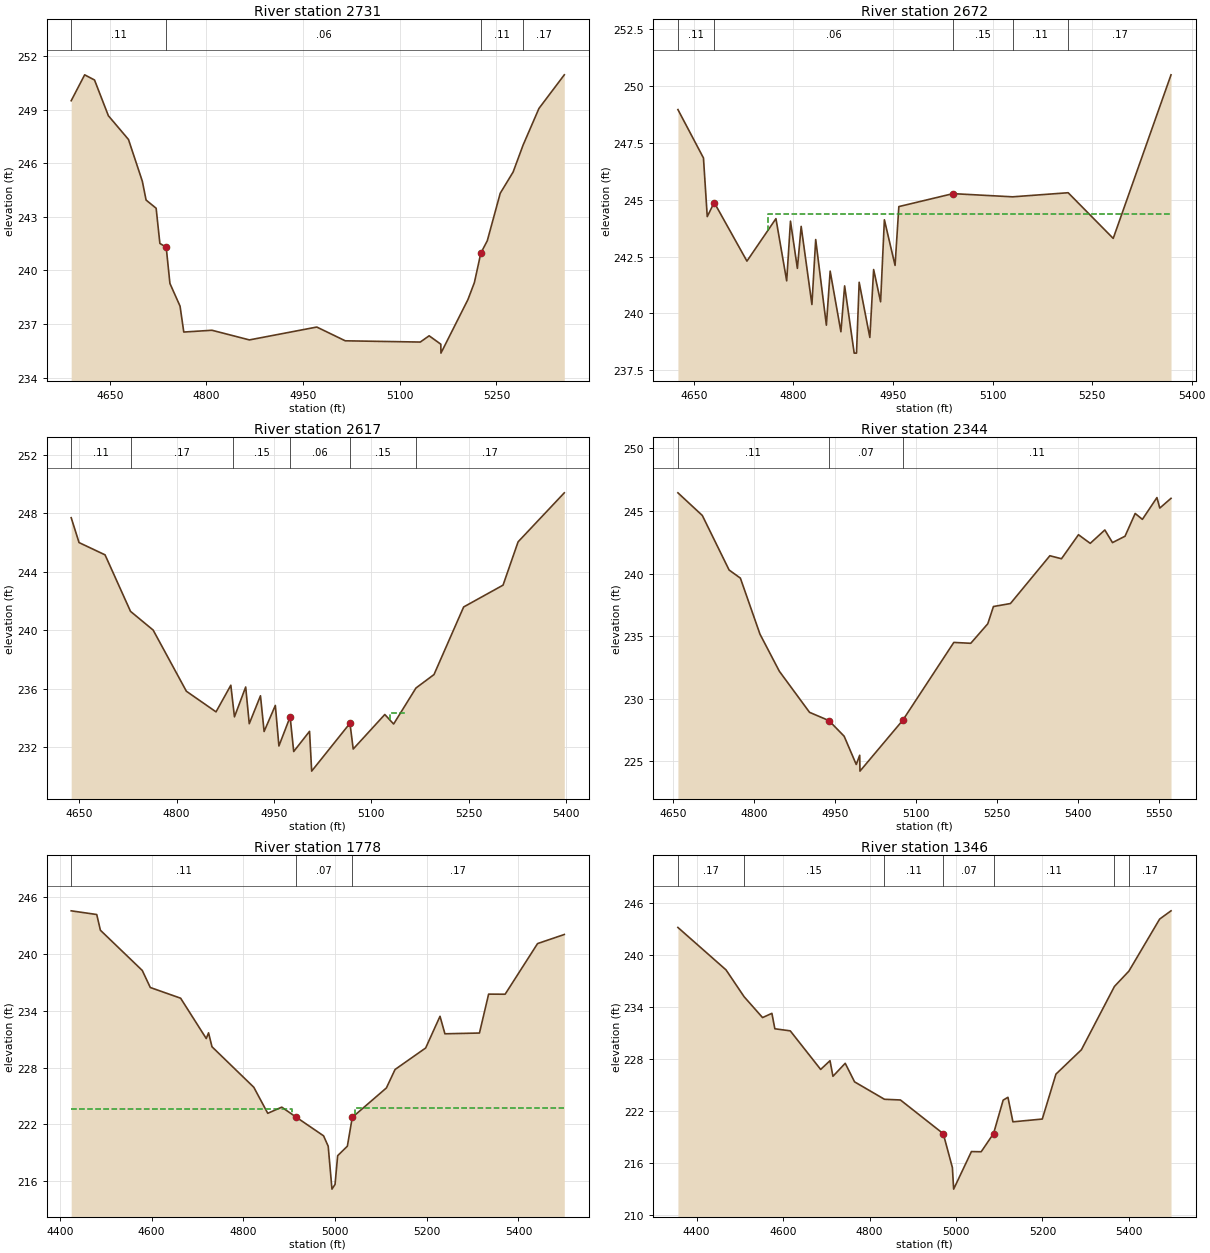
Type RM Length L Ch R = 1 ,2731    ,59,59,59
BEGIN DESCRIPTION:
CANEY CREEK NORTH TRIB NO 4_1 1.0
END DESCRIPTION:
XS GIS Cut Line= 3
      3769925.45     10160229.03      3770134.24     10159876.29
      3770157.24     10159521.84
#Sta/Elev= 30
  4590.1   249.5    4611  250.95  4626.3  250.66  4647.8  248.66    4679  247.33
  4700.5  244.99  4706.3  243.94  4721.9  243.48  4727.7  241.51  4737.5   241.3
  4743.3  239.27    4759     238  4764.8  236.55  4808.5  236.65  4866.6  236.11
  4971.2  236.83  5015.3  236.06  5131.7  235.99  5145.5  236.34  5163.6  235.87
  5163.8  235.37  5205.7  238.37  5215.7  239.32  5225.7  240.97  5235.7  241.66
  5255.8  244.32  5275.8  245.51  5291.3  247.02  5315.9  249.07  5355.2  250.95
#Mann= 4 ,-1 , 0
  4590.1     .11       0  4737.5     .06       0  5225.7     .11       0
  5291.3     .17       0
Bank Sta=4737.5,5225.7
XS Rating Curve= 0 ,0
Exp/Cntr=0.3,0.1

Type RM Length L Ch R = 1 ,2672    ,55,55,55
BEGIN DESCRIPTION:
Mapping XS 6ad34ffb
END DESCRIPTION:
XS GIS Cut Line= 3
      3769994.32     10160249.69      3770173.21     10159921.13
      3770214.37     10159554.54
#Sta/Elev= 30
  4625.9  248.97  4664.4  246.84  4670.1  244.26  4680.6  244.88  4729.9   242.3
  4773.6  244.17  4789.8  241.43  4795.5  244.06  4805.9  241.98  4811.6  243.83
  4827.8  240.39  4833.5  243.25  4849.6  239.48  4855.3  241.86  4871.5  239.19
  4877.1  241.21  4891.5  238.25    4895  238.25    4899  241.37  4915.1  238.94
  4920.8  241.93  4931.3  240.51    4937  244.12  4953.1  242.11  4958.8   244.7
  5040.3  245.27  5130.2  245.13  5213.9  245.31  5281.8   243.3  5368.9   250.5
#Mann= 5 ,-1 , 0
  4625.9     .11       0  4680.6     .06       0  5040.3     .15       0
  5130.2     .11       0  5213.9     .17       0
#XS Ineff= 5 ,-1
    4761  4664.4  244.36  4833.5  4783.7  243.25  4855.3  4833.5  241.86
  4920.8    4937  241.93    4937  4958.8  244.12
Permanent Ineff=
       F       F       F       F       F
Bank Sta=4680.6,5040.3
XS Rating Curve= 0 ,0
Exp/Cntr=0.3,0.1

Type RM Length L Ch R = 1 ,2617    ,273,273,273
BEGIN DESCRIPTION:
CANEY CREEK NORTH TRIB NO 4_1 2.0
END DESCRIPTION:
XS GIS Cut Line= 3
      3770058.57     10160288.78      3770211.99     10159960.56
      3770274.38     10159567.89
#Sta/Elev= 30
  4637.7  247.69  4649.8  245.99  4689.9  245.15  4729.1  241.29    4764  240.01
  4815.2  235.83  4860.9  234.42  4883.7  236.24  4887.1  234.93  4889.3  234.08
  4906.6  236.12  4912.1  233.61  4929.4  235.52    4935  233.08  4952.3  234.86
  4957.8  232.09  4975.1  234.08  4980.6  231.71    5005  233.09  5008.3  230.37
  5067.3  233.64  5072.3  231.88    5121  234.24  5134.6  233.59    5169  236.05
  5196.8  236.97  5242.5  241.59  5303.2  243.08  5326.4  246.04  5397.6  249.39
#Mann= 6 ,-1 , 0
  4637.7     .11       0  4729.1     .17       0  4887.1     .15       0
  4975.1     .06       0  5067.3     .15       0    5169     .17       0
#XS Ineff= 4 ,-1
  4929.4  4800.7  235.52  4952.3  4929.4  234.86  4975.1  4952.3  234.08
  5129.5  5151.4  234.31
Permanent Ineff=
       F       F       F       F
Bank Sta=4975.1,5067.3
XS Rating Curve= 0 ,0
Exp/Cntr=0.3,0.1

Type RM Length L Ch R = 1 ,2344    ,566,566,566
BEGIN DESCRIPTION:
Mapping XS 4710a750
END DESCRIPTION:
XS GIS Cut Line= 3
      3770138.91     10160355.33      3770405.51     10160143.35
      3770579.69     10159597.78
#Sta/Elev= 30
  4659.4  246.45  4704.6  244.64  4754.2  240.28  4775.1  239.63  4811.4  235.15
  4847.2  232.19  4903.2   228.9  4939.1  228.24  4967.3  226.99  4989.7  224.73
  4996.1  225.47  4996.6   224.2  5075.9  228.27  5170.4  234.49  5201.8  234.42
  5233.3  235.98  5243.8  237.36  5275.3   237.6  5348.3  241.42  5369.8  241.18
  5401.3   243.1  5423.1  242.41  5450.1  243.48  5464.3  242.47  5487.5  242.98
  5506.3   244.8  5519.7  244.33  5546.6  246.07  5551.9  245.23  5572.7  246.01
#Mann= 3 , 0 , 0
  4659.4     .11       0  4939.1     .07       0  5075.9     .11       0
Bank Sta=4939.1,5075.9
XS Rating Curve= 0 ,0
Exp/Cntr=0.3,0.1

Type RM Length L Ch R = 1 ,1778    ,432,432,432
BEGIN DESCRIPTION:
CANEY CREEK NORTH TRIB NO 4_1 3.0
END DESCRIPTION:
XS GIS Cut Line= 3
      3770154.98     10160387.46      3770722.53     10160481.58
      3771192.68     10160311.69
#Sta/Elev= 30
  4424.7  244.56  4480.4  244.17  4488.4  242.51  4579.7  238.26  4597.2  236.46
  4663.3  235.33  4719.2  231.07  4724.2  231.67  4731.7   230.2  4822.9  225.92
  4853.3  223.17  4883.8  223.82  4914.2   222.8    4975  220.79  4985.1  219.69
  4993.3  215.16    5000  215.66  5005.7  218.69  5026.9   219.7  5037.6  222.74
    5112  225.85  5130.9   227.8  5197.6  230.07  5228.9  233.42  5239.6  231.57
  5314.9  231.65  5334.9  235.76  5370.9  235.75  5441.6   241.1  5499.9  242.06
#Mann= 3 , 0 , 0
  4424.7     .11       0  4914.2     .07       0  5037.6     .17       0
#XS Ineff= 2 , 0
       0  4907.2  223.61  5044.3       0  223.73
Permanent Ineff=
       F       F
Bank Sta=4914.2,5037.6
XS Rating Curve= 0 ,0
Exp/Cntr=0.3,0.1

Type RM Length L Ch R = 1 ,1346    ,489,489,489
BEGIN DESCRIPTION:
Mapping XS e661a211
END DESCRIPTION:
XS GIS Cut Line= 3
      3770134.57     10160407.44      3770609.64     10160841.19
       3771057.7     10161056.94
#Sta/Elev= 30
  4356.7  243.18    4468  238.29  4509.9  235.19  4552.5  232.79  4574.1  233.28
  4580.9   231.5  4616.6  231.26  4686.9  226.81  4708.5  227.82  4715.3  226.02
  4743.7  227.52  4765.3  225.38  4834.5  223.37  4871.4  223.29  4970.5   219.4
  4991.6  215.49  4994.5  213.01  5035.6  217.34  5058.2  217.32  5086.8  219.42
    5109  223.27  5120.1   223.6  5131.6  220.77  5199.5  221.09  5231.1  226.27
    5290  229.08  5366.4  236.38  5399.9  238.15    5471  244.15  5497.3   245.1
#Mann= 7 ,-1 , 0
  4356.7     .17       0  4509.9     .15       0  4834.5     .11       0
  4970.5     .07       0  5086.8     .11       0  5366.4     .11       0
  5399.9     .17       0
#XS Ineff= 2 , 0
       0                  5120.1       0   223.6
Permanent Ineff=
       F       F
Bank Sta=4970.5,5086.8
XS Rating Curve= 0 ,0
Exp/Cntr=0.3,0.1

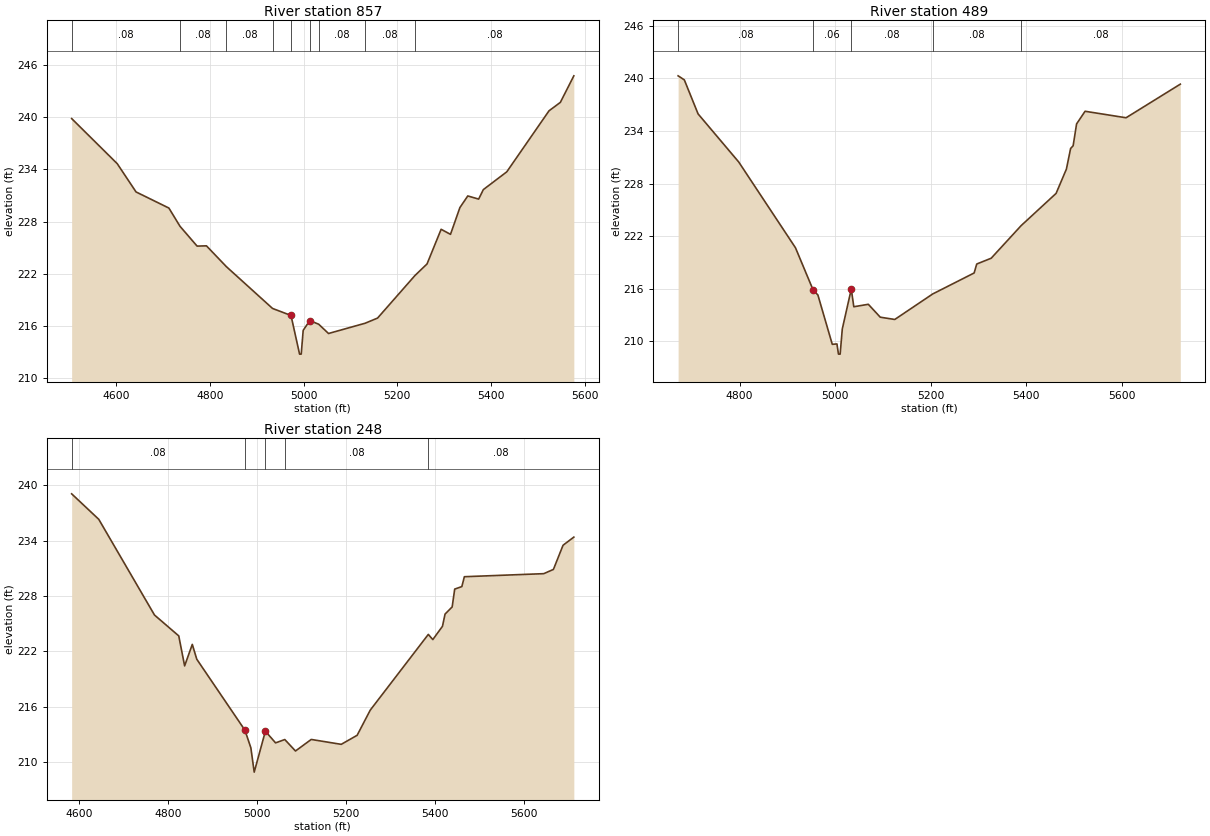
Type RM Length L Ch R = 1 ,857     ,368,368,368
BEGIN DESCRIPTION:
CANEY CREEK NORTH TRIB NO 4_1 4.0
END DESCRIPTION:
XS GIS Cut Line= 3
      3769940.74     10161228.77      3770434.67     10161264.15
      3771010.81     10161234.55
#Sta/Elev= 30
  4504.8  239.85  4602.1  234.67  4642.3  231.42  4712.4  229.57  4736.2  227.47
  4772.6   225.2  4792.6  225.23  4834.9  222.85  4933.6  218.04  4973.1  217.23
  4991.4  212.79  4994.9  212.79  4999.1  215.52  5013.2  216.65  5032.3  216.22
  5053.2  215.16  5131.4  216.34  5157.9  216.93  5237.9  221.83  5263.5  223.15
  5293.6  227.13  5313.6  226.55  5333.6  229.62  5350.5  230.96  5373.7   230.6
  5383.7  231.69  5433.7  233.73  5523.9  240.74  5548.1  241.71  5576.9  244.76
#Mann= 9 ,-1 , 0
  4504.8     .08       0  4736.2     .08       0  4834.9     .08       0
  4933.6     .08       0  4973.1     .06       0  5013.2     .08       0
  5032.3     .08       0  5131.4     .08       0  5237.9     .08       0
Bank Sta=4973.1,5013.2
XS Rating Curve= 0 ,0
Exp/Cntr=0.3,0.1

Type RM Length L Ch R = 1 ,489     ,241,241,241
BEGIN DESCRIPTION:
Mapping XS 88ab1232
END DESCRIPTION:
XS GIS Cut Line= 3
      3769996.23     10161636.86      3770323.63     10161608.88
      3771001.46     10161357.33
#Sta/Elev= 30
  4671.4  240.28  4684.4  239.82  4713.2  235.94  4798.3  230.46  4917.2  220.68
  4954.1  215.87  4964.1   215.3  4994.2  209.68    5004  209.72  5007.2  208.56
  5010.7  208.56  5015.2  211.43    5034  215.97  5039.3  213.96  5069.7  214.24
  5094.7  212.77  5125.1  212.51  5204.6  215.42  5291.3  217.81  5296.7  218.83
    5327  219.49  5389.6   223.2  5462.9  226.88  5484.5  229.65  5493.3     232
  5498.6  232.31  5505.8   234.8  5523.6  236.24  5609.4   235.5    5723  239.33
#Mann= 5 ,-1 , 0
  4671.4     .08       0  4954.1     .06       0    5034     .08       0
  5204.6     .08       0  5389.6     .08       0
#XS Ineff= 2 , 0
       0                    5034       0  215.97
Permanent Ineff=
       F       F
Bank Sta=4954.1,5034
XS Rating Curve= 0 ,0
Exp/Cntr=0.3,0.1

Type RM Length L Ch R = 1 ,248     ,0,0,0
BEGIN DESCRIPTION:
CANEY CREEK NORTH TRIB NO 4_1 5.0
END DESCRIPTION:
XS GIS Cut Line= 3
      3770010.12     10161885.12      3770421.09     10161820.58
        3771043.     10161473.72
#Sta/Elev= 30
    4584  239.07  4644.9  236.31  4770.1  225.94  4824.6  223.68  4837.8  220.43
    4855  222.76  4865.1  221.15  4973.3  213.46  4986.6  211.55  4994.1  208.92
  5019.2  213.35  5042.1  212.09  5062.8  212.45  5086.8  211.21  5122.2  212.46
  5189.6  211.93  5225.3  212.91  5254.8  215.64  5385.2  223.84  5395.3  223.28
    5417  224.72  5422.8  226.04  5438.8  226.82  5444.5  228.75  5460.5  229.02
  5466.2  230.09  5644.5  230.42  5666.2  230.88  5687.9   233.5  5712.1  234.38
#Mann= 5 ,-1 , 0
    4584     .08       0  4973.3     .06       0  5019.2     .08       0
  5062.8     .08       0  5385.2     .08       0
Bank Sta=4973.3,5019.2
XS Rating Curve= 0 ,0
Exp/Cntr=0.3,0.1

Chan Stop Cuts=-1
Use User Specified Reach Order=0
Composite Channel Slope=5