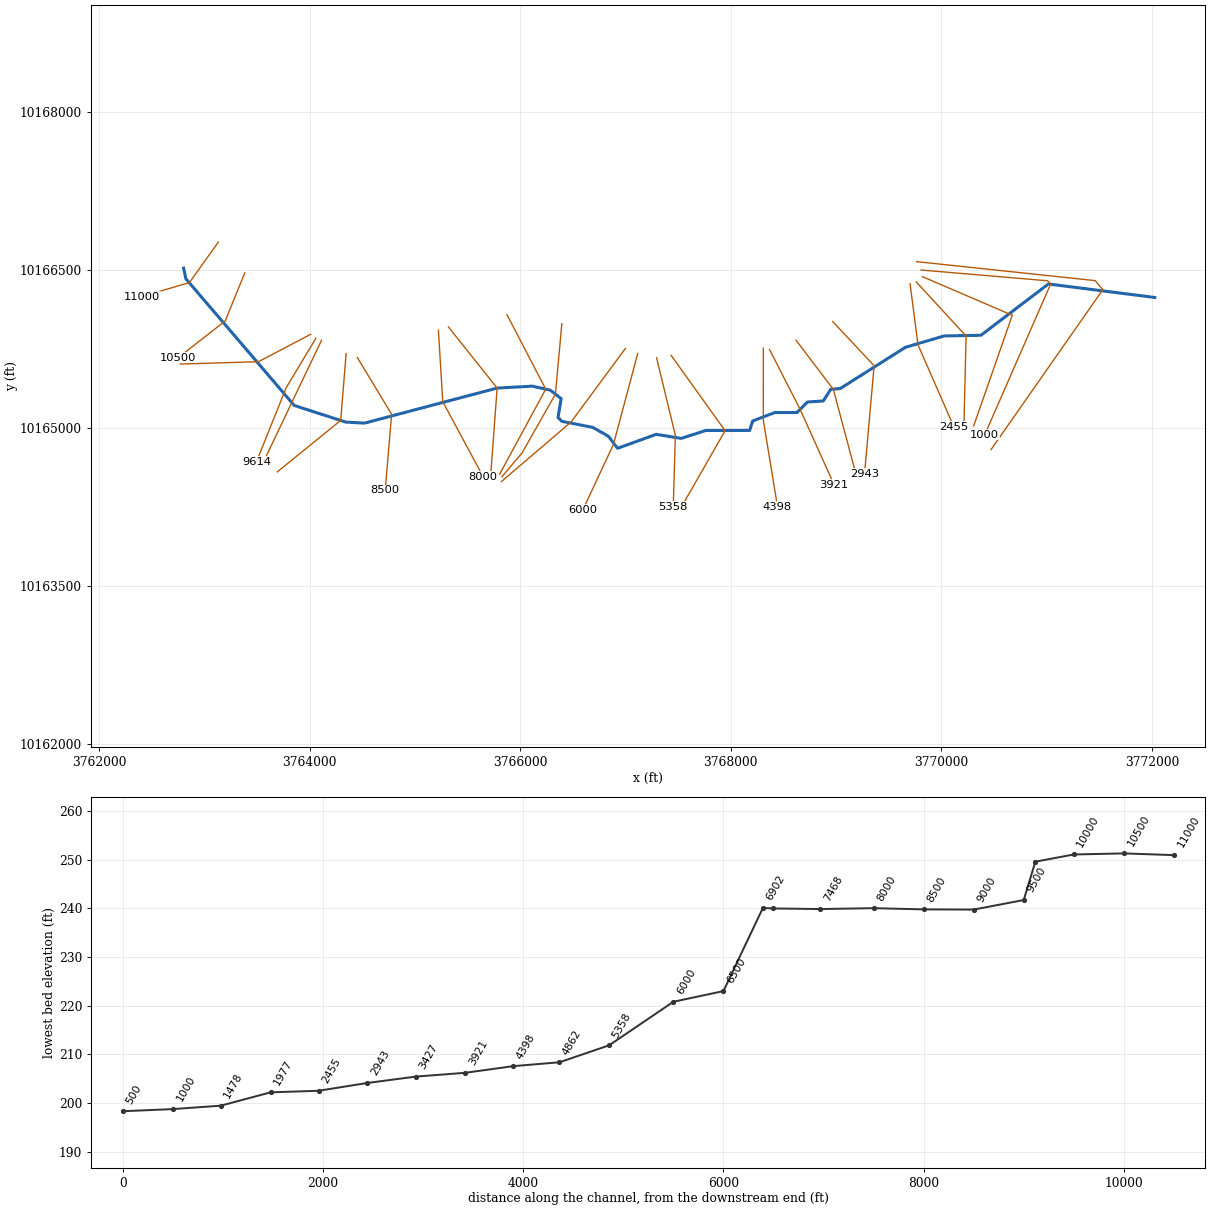
--- CANEY CREEK NORTH TRIB NO 5.prj (project) ---

Proj Title=CANEY CREEK NORTH TRIB NO 5 Base Level Engineering
Current Plan=p01
Default Exp/Contr=0.3,0.1
English Units
Geom File=g01
Flow File=f01
Flow File=f02
Plan File=p01
Y Axis Title=Elevation
X Axis Title(PF)=Main Channel Distance
X Axis Title(XS)=Station
BEGIN DESCRIPTION:
CANEY CREEK NORTH TRIB NO 5
END DESCRIPTION:
DSS Export Rating Curves= 0
DSS Export Rating Curve Sorted= 0
DSS Export Volume Flow Curves= 0
DXF OffsetX= 0
DXF OffsetY= 0
DXF ScaleX= 1
DXF ScaleY= 10

--- CANEY CREEK NORTH TRIB NO 5.p01 (plan) ---

Plan Title=Multiple Run
Short Identifier=Multiple
Geom File=g01
Flow File=f01
Subcritical Flow
K Sum by GR= 0
Std Step Tol= 0.01
Critical Tol= 0.01
Num of Std Step Trials= 20
Max Error Tol= 0.3
Flow Tol Ratio= 0.001
Split Flow NTrial= 30
Split Flow Tol= 0.02
Split Flow Ratio= 0.02
Log Output Level= 0
Friction Slope Method= 1
Unsteady Friction Slope Method= 2
Unsteady Bridges Friction Slope Method= 1
Parabolic Critical Depth
Global Vel Dist=  1 , 1 , 1
Global Log Level= 0
CheckData=True
Encroach Param= -1, 0, 0, 0
BEGIN DESCRIPTION:
Multiple Run
END DESCRIPTION:

--- CANEY CREEK NORTH TRIB NO 5.f01 (steady flow) ---

Flow Title=Multiple
Program Version=4.10
Number of Profiles= 7
Profile Names=10-year,25-year,50-year,1pct_min,100-year,1pct_plu,500-year
River Rch & RM=CANEY CREEK NORT,Reach-1         ,11000
     245     312     405     174     524    1582     903
River Rch & RM=CANEY CREEK NORT,Reach-1         ,10000
     859    1179    1608     720    2175    6568    4118
River Rch & RM=CANEY CREEK NORT,Reach-1         ,3427
    1058    1469    2018     910    2748    8299    5274
Boundary for River Rch & Prof#=CANEY CREEK NORT,Reach-1         , 1
Up Type= 0
Dn Type= 3
Dn Slope=0.003
Boundary for River Rch & Prof#=CANEY CREEK NORT,Reach-1         , 2
Up Type= 0
Dn Type= 3
Dn Slope=0.003
Boundary for River Rch & Prof#=CANEY CREEK NORT,Reach-1         , 3
Up Type= 0
Dn Type= 3
Dn Slope=0.003
Boundary for River Rch & Prof#=CANEY CREEK NORT,Reach-1         , 4
Up Type= 0
Dn Type= 3
Dn Slope=0.003
Boundary for River Rch & Prof#=CANEY CREEK NORT,Reach-1         , 5
Up Type= 0
Dn Type= 3
Dn Slope=0.003
Boundary for River Rch & Prof#=CANEY CREEK NORT,Reach-1         , 6
Up Type= 0
Dn Type= 3
Dn Slope=0.003
Boundary for River Rch & Prof#=CANEY CREEK NORT,Reach-1         , 7
Up Type= 0
Dn Type= 3
Dn Slope=0.003
DSS Import GetInterval= 0
DSS Import GetPeak= 0
DSS Import FillOption= 0

--- CANEY CREEK NORTH TRIB NO 5.f02 (steady flow) ---

Flow Title=Orig_BLE_Flow
Program Version=4.10
Number of Profiles= 7
Profile Names=10-year,25-year,50-year,1pct_min,100-year,1pct_plu,500-year
River Rch & RM=CANEY CREEK NORT,Reach-1         ,11000
     245     306     352     133     403    1216     525
River Rch & RM=CANEY CREEK NORT,Reach-1         ,10000
     859    1156    1398     554    1673    5053    2394
River Rch & RM=CANEY CREEK NORT,Reach-1         ,3427
    1058    1440    1755     700    2114    6383    3066
Boundary for River Rch & Prof#=CANEY CREEK NORT,Reach-1         , 1
Up Type= 0
Dn Type= 3
Dn Slope=0.003
Boundary for River Rch & Prof#=CANEY CREEK NORT,Reach-1         , 2
Up Type= 0
Dn Type= 3
Dn Slope=0.003
Boundary for River Rch & Prof#=CANEY CREEK NORT,Reach-1         , 3
Up Type= 0
Dn Type= 3
Dn Slope=0.003
Boundary for River Rch & Prof#=CANEY CREEK NORT,Reach-1         , 4
Up Type= 0
Dn Type= 3
Dn Slope=0.003
Boundary for River Rch & Prof#=CANEY CREEK NORT,Reach-1         , 5
Up Type= 0
Dn Type= 3
Dn Slope=0.003
Boundary for River Rch & Prof#=CANEY CREEK NORT,Reach-1         , 6
Up Type= 0
Dn Type= 3
Dn Slope=0.003
Boundary for River Rch & Prof#=CANEY CREEK NORT,Reach-1         , 7
Up Type= 0
Dn Type= 3
Dn Slope=0.003
DSS Import GetInterval= 0
DSS Import GetPeak= 0
DSS Import FillOption= 0

--- CANEY CREEK NORTH TRIB NO 5.g01 (geometry) ---

Geom Title=Existing Conditions
Program Version=4.10

River Reach=CANEY CREEK NORT,Reach-1
Reach XY= 30
      3762804.17       10166519.        3762825.      10166418.3
      3763854.77     10165213.72      3764343.89     10165055.94
      3764521.24     10165046.09      3765781.03     10165379.16
      3766115.33      10165397.5        3766286.     10165359.41
      3766388.97     10165279.01      3766359.35     10165101.29
      3766394.61      10165063.2      3766688.25     10165006.11
      3766836.31     10164922.43      3766924.29     10164806.56
      3767291.22     10164939.59       3767529.4     10164900.97
      3767761.14     10164976.07      3768178.23     10164976.84
      3768208.23     10165066.84      3768418.23     10165146.84
      3768628.23     10165146.84      3768728.23     10165246.84
      3768878.23     10165256.84      3768948.23     10165366.84
      3769040.03     10165375.19      3769657.07     10165766.13
      3770025.99     10165874.64      3770375.38     10165881.15
      3771015.57     10166368.35      3772025.69     10166240.13

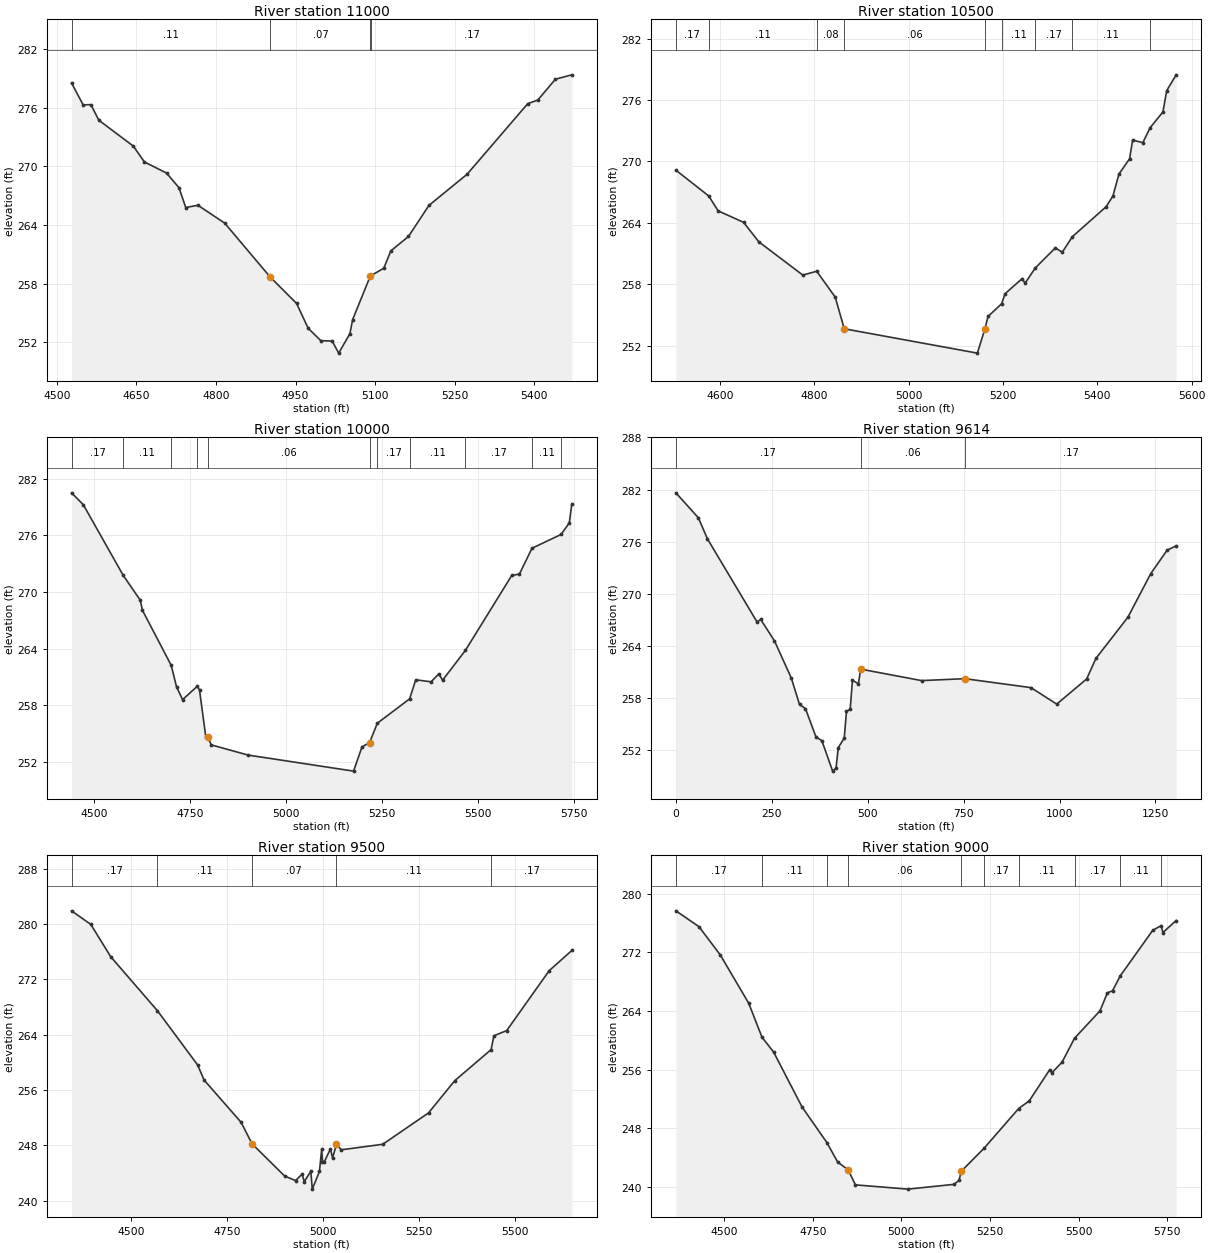
Type RM Length L Ch R = 1 ,11000   ,500,500,500
BEGIN DESCRIPTION:
CANEY CREEK NORTH TRIB NO 5 22.0
END DESCRIPTION:
XS GIS Cut Line= 3
      3763133.77     10166766.24      3762859.52     10166381.96
      3762408.12     10166248.92
#Sta/Elev= 30
  4527.9  278.54  4549.7   276.3  4564.4  276.32  4579.2  274.73  4644.3  272.08
  4665.2  270.46    4707  269.32  4730.4  267.82  4743.1   265.8    4766  266.03
  4816.4  264.21  4902.4  258.68    4952  255.99  4973.7  253.46  4997.5  252.19
  5019.1  252.14  5031.3  250.91  5052.4   252.9  5057.6  254.34    5091  258.81
  5092.5  258.84  5116.4   259.6  5129.5  261.36  5162.8  262.84  5201.4  266.02
  5273.2   269.2  5387.5  276.42  5406.5  276.79  5439.6  278.92  5470.6  279.37
#Mann= 4 ,-1 , 0
  4527.9     .11       0  4902.4     .07       0    5091     .11       0
  5092.5     .17       0
Bank Sta=4902.4,5091
XS Rating Curve= 0 ,0
Exp/Cntr=0.3,0.1

Type RM Length L Ch R = 1 ,10500   ,500,500,500
BEGIN DESCRIPTION:
CANEY CREEK NORTH TRIB NO 5 21.0
END DESCRIPTION:
XS GIS Cut Line= 3
      3763384.66     10166473.85      3763198.97     10166017.05
      3762752.25     10165667.54
#Sta/Elev= 30
  4506.9  269.14  4576.5  266.62  4596.5  265.16  4650.2  264.05  4682.6  262.14
  4775.8  258.89  4805.3  259.26  4844.5  256.74 4863.72  253.64  5145.8  251.26
    5162  253.65  5168.4  254.84  5197.3  256.09  5204.6  257.07  5240.7  258.54
    5247   258.1  5268.5  259.58  5311.2  261.55  5325.7  261.12  5347.4  262.65
  5418.8  265.57  5433.1  266.61    5446  268.77  5468.5  270.26  5474.9  272.08
  5496.6  271.83  5511.8  273.28  5539.1  274.83  5547.2  276.92  5567.2  278.46
#Mann= 9 ,-1 , 0
  4506.9     .17       0  4576.5     .11       0  4805.3     .08       0
 4863.72     .06       0    5162     .08       0  5197.3     .11       0
  5268.5     .17       0  5347.4     .11       0  5511.8     .17       0
Bank Sta=4863.72,5162
XS Rating Curve= 0 ,0
Exp/Cntr=0.3,0.1

Type RM Length L Ch R = 1 ,10000   ,384,384,384
BEGIN DESCRIPTION:
CANEY CREEK NORTH TRIB NO 5 20.0
END DESCRIPTION:
XS GIS Cut Line= 3
      3764009.87     10165890.22      3763515.16     10165629.73
       3762771.4      10165607.5
#Sta/Elev= 30
  4440.9  280.51  4471.4  279.26  4575.6  271.76  4619.9  269.14  4625.6  268.07
  4700.4  262.25  4714.4  259.96  4730.1  258.61  4768.5  260.03  4774.2  259.64
  4790.5   254.7  4796.2  254.61  4804.8  253.82  4900.7  252.74  5175.6  251.04
  5197.4   253.6  5217.4  254.07  5237.4  256.11  5321.5  258.69  5337.5  260.71
  5377.5   260.5  5397.5  261.33  5407.5  260.67  5467.1  263.84  5587.6  271.76
  5607.6  271.91  5640.3  274.64    5716   276.1  5737.6  277.33  5744.1  279.35
#Mann= 11 ,-1 , 0
  4440.9     .17       0  4575.6     .11       0  4700.4     .17       0
  4768.5     .08       0  4796.2     .06       0  5217.4     .08       0
  5237.4     .17       0  5321.5     .11       0  5467.1     .17       0
  5640.3     .11       0    5716     .17       0
Bank Sta=4796.2,5217.4
XS Rating Curve= 0 ,0
Exp/Cntr=0.3,0.1

Type RM Length L Ch R = 1 ,9614    ,116,116,116
XS GIS Cut Line= 3
      3764059.21     10165851.35      3763778.12     10165382.87
      3763495.83     10164679.73
#Sta/Elev= 30
       0  281.62    58.6  278.74      82  276.33   211.4  266.75   221.1  267.03
   256.9  264.57   300.8  260.28   322.2  257.24   337.7  256.76   364.9  253.52
   380.5  253.06   408.5  249.56   417.4  249.91   423.3  252.27   438.8  253.37
   444.6  256.45   454.3  256.68   460.2  260.03   475.7  259.62   481.6  261.31
   640.4  259.99   753.4  260.21   925.4  259.18   992.7  257.28  1070.7  260.18
  1094.9  262.55  1178.2  267.29  1237.9  272.32  1280.4  275.01    1304  275.51
#Mann= 3 , 0 , 0
       0     .17       0   481.6     .06       0   753.4     .17       0
#XS Ineff= 2 , 0
       0   481.6  261.31   753.4       0  260.21
Permanent Ineff=
       T       T
Bank Sta=481.6,753.4
XS Rating Curve= 0 ,0
Exp/Cntr=0.3,0.1

Type RM Length L Ch R = 1 ,9500    ,500,500,500
BEGIN DESCRIPTION:
CANEY CREEK NORTH TRIB NO 5 19.0
END DESCRIPTION:
XS GIS Cut Line= 3
      3764113.61     10165833.13      3763831.36      10165242.4
      3763553.27     10164657.99
#Sta/Elev= 30
  4345.3  281.89  4395.5  279.92  4447.3  275.26  4568.8  267.46  4673.2  259.64
  4690.3  257.44  4786.6  251.34  4814.8  248.25    4900  243.57  4928.2  242.93
  4945.3  243.85  4950.9  242.77    4968  244.27  4971.8  241.69  4990.4  244.24
  4996.2  247.43  4998.3  245.68  5003.5  245.68  5018.9   247.5  5024.5  246.21
  5034.7  248.15  5047.2  247.37  5155.2  248.17  5274.3   252.7  5342.4  257.35
  5437.1  261.84  5444.4  263.84  5477.7  264.59  5588.4  273.25  5647.2  276.16
#Mann= 5 ,-1 , 0
  4345.3     .17       0  4568.8     .11       0  4814.8     .07       0
  5034.7     .11       0  5437.1     .17       0
#XS Ineff= 2 , 0
       0                  4996.2       0  247.43
Permanent Ineff=
       F       F
Bank Sta=4814.8,5034.7
XS Rating Curve= 0 ,0
Exp/Cntr=0.3,0.1

Type RM Length L Ch R = 1 ,9000    ,500,500,500
BEGIN DESCRIPTION:
CANEY CREEK NORTH TRIB NO 5 18.0
END DESCRIPTION:
XS GIS Cut Line= 3
      3764347.08     10165705.99      3764295.39     10165071.59
      3763693.34     10164582.77
#Sta/Elev= 30
  4363.5  277.68  4428.6  275.52  4488.8  271.66  4569.1  265.07  4606.5  260.44
  4639.3  258.42  4719.6  250.93  4789.9  246.06  4819.9  243.43    4850  242.35
  4870.1  240.31  5018.6  239.73  5148.2  240.38  5162.6  240.92  5169.1  242.18
    5233  245.29    5331  250.72  5360.9  251.77  5418.4     256  5424.8   255.6
  5453.5  257.05  5488.7  260.31  5560.6  264.05  5581.4   266.5  5595.8  266.77
  5617.7  268.81  5709.3  275.02  5733.3  275.67    5738  274.72  5775.5  276.36
#Mann= 10 ,-1 , 0
  4363.5     .17       0  4606.5     .11       0  4789.9     .08       0
    4850     .06       0  5169.1     .08       0    5233     .17       0
    5331     .11       0  5488.7     .17       0  5617.7     .11       0
  5733.3     .17       0
Bank Sta=4850,5169.1
XS Rating Curve= 0 ,0
Exp/Cntr=0.3,0.1

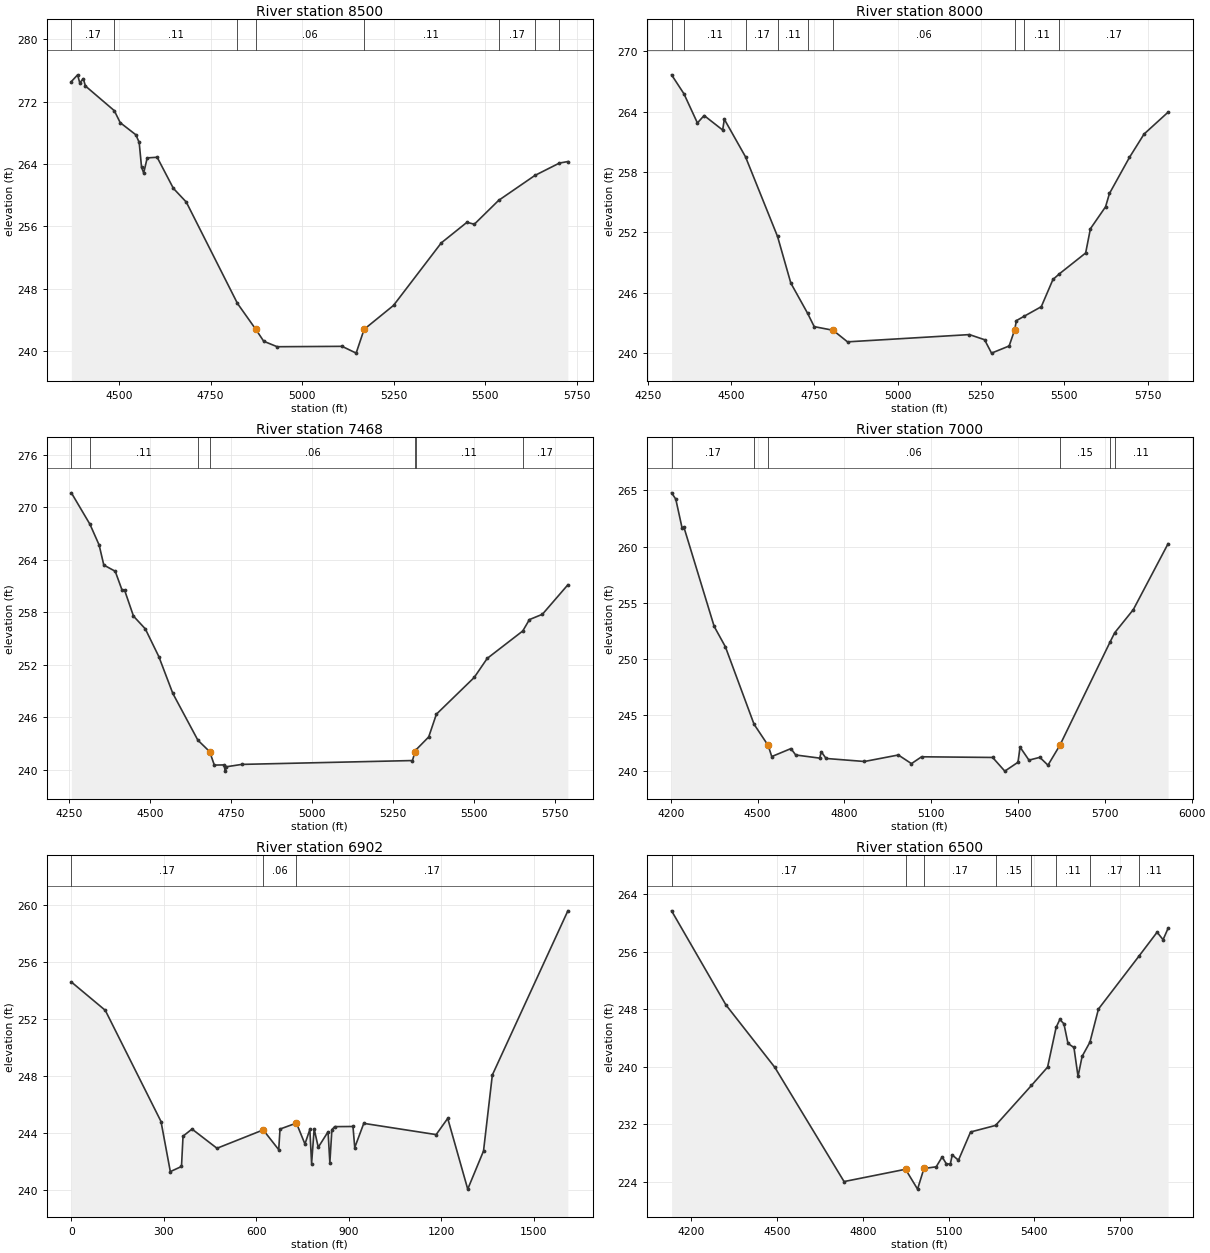
Type RM Length L Ch R = 1 ,8500    ,500,500,500
BEGIN DESCRIPTION:
CANEY CREEK NORTH TRIB NO 5 17.0
END DESCRIPTION:
XS GIS Cut Line= 3
      3764453.45      10165669.7      3764779.25     10165130.02
      3764718.03      10164406.4
#Sta/Elev= 30
  4369.6  274.56  4386.7  275.42  4392.5  274.39  4402.2  274.93    4408  273.99
  4486.9  270.83  4503.1  269.29  4545.8  267.74  4554.9  266.76  4561.3  263.61
  4567.2  262.84  4576.8  264.78    4604  264.86  4648.3  260.88  4683.6  259.12
  4823.5  246.13  4873.8   242.8  4895.2  241.29    4932  240.59  5109.3  240.64
  5147.7  239.77  5169.5  242.82  5249.8  245.88  5380.3  253.89  5450.5  256.53
  5470.6  256.28  5537.1  259.34  5636.1  262.53  5703.3  264.12  5726.2  264.31
#Mann= 8 ,-1 , 0
  4369.6     .17       0  4486.9     .11       0  4823.5     .15       0
  4873.8     .06       0  5169.5     .11       0  5537.1     .17       0
  5636.1     .11       0  5703.3     .17       0
Bank Sta=4873.8,5169.5
XS Rating Curve= 0 ,0
Exp/Cntr=0.3,0.1

Type RM Length L Ch R = 1 ,8000    ,532,532,532
BEGIN DESCRIPTION:
CANEY CREEK NORTH TRIB NO 5 16.0
END DESCRIPTION:
XS GIS Cut Line= 3
      3765223.57     10165928.56      3765264.47     10165250.69
      3765648.71      10164535.7
#Sta/Elev= 30
  4320.9  267.65    4358  265.77  4398.5  262.87  4418.6  263.61  4474.3  262.17
  4479.3  263.24  4542.9  259.51  4639.1   251.6    4679  246.97  4729.1  243.99
  4749.2  242.65  4805.7  242.29  4849.2  241.14  5215.3  241.86  5260.7  241.35
  5281.6  240.02  5334.5  240.73  5350.8   242.3  5356.4  243.25  5378.4  243.66
    5431  244.63    5466  247.33  5485.6   247.9  5564.2  249.96  5578.5  252.37
    5624  254.55  5635.7  255.87  5695.7  259.45  5739.6  261.77  5811.7  263.94
#Mann= 9 ,-1 , 0
  4320.9     .17       0    4358     .11       0  4542.9     .17       0
  4639.1     .11       0  4729.1     .08       0  4805.7     .06       0
  5350.8     .08       0  5378.4     .11       0  5485.6     .17       0
Bank Sta=4805.7,5350.8
XS Rating Curve= 0 ,0
Exp/Cntr=0.3,0.1

Type RM Length L Ch R = 1 ,7468    ,468,468,468
BEGIN DESCRIPTION:
CANEY CREEK NORTH TRIB NO 5 15.0
END DESCRIPTION:
XS GIS Cut Line= 3
      3765317.88     10165961.04      3765781.03     10165379.16
      3765722.78     10164592.71
#Sta/Elev= 30
  4256.3  271.67  4313.7  268.07    4342   265.7  4356.4  263.41  4391.6   262.7
  4412.4  260.58  4420.4  260.55    4448  257.57  4484.5  256.11  4526.1  252.95
  4569.4  248.73  4646.7  243.38  4683.1  242.07  4697.5  240.53  4726.4  240.55
  4730.7  240.34    4731  239.84  4734.7  240.34  4782.4  240.61  5308.9  241.05
 5317.33  242.08    5319  242.24  5359.1  243.75  5382.8  246.35  5499.5  250.55
  5539.6  252.73  5649.4  255.87  5669.9  257.17    5710  257.78  5788.6  261.15
#Mann= 7 ,-1 , 0
  4256.3     .17       0  4313.7     .11       0  4646.7     .17       0
  4683.1     .06       0 5317.33     .08       0    5319     .11       0
  5649.4     .17       0
Bank Sta=4683.1,5317.33
XS Rating Curve= 0 ,0
Exp/Cntr=0.3,0.1

Type RM Length L Ch R = 1 ,7000    ,106,106,106
BEGIN DESCRIPTION:
CANEY CREEK NORTH TRIB NO 5 14.0
END DESCRIPTION:
XS GIS Cut Line= 3
      3765874.63     10166076.08      3766242.44     10165369.13
      3765805.19     10164561.38
#Sta/Elev= 30
  4203.1  264.79  4217.6  264.23  4239.7  261.62  4245.4  261.75  4350.3  252.87
  4388.9  251.06  4488.1  244.14 4536.82  242.25  4549.2  241.26  4615.5  241.97
    4632   241.4  4714.8  241.12  4720.4  241.69  4736.9  241.09  4869.5  240.82
  4986.5   241.4  5031.9  240.63  5066.9  241.24  5312.4  241.18  5354.4  239.96
  5399.9  240.75  5407.2   242.1  5437.9  240.94  5475.4  241.19  5503.5  240.49
 5544.53  242.26  5717.7  251.46  5734.2  252.31  5798.4  254.37  5918.5  260.25
#Mann= 6 ,-1 , 0
  4203.1     .17       0  4488.1     .15       0 4536.82     .06       0
 5544.53     .15       0  5717.7     .17       0  5734.2     .11       0
Bank Sta=4536.82,5544.53
XS Rating Curve= 0 ,0
Exp/Cntr=0.3,0.1

Type RM Length L Ch R = 1 ,6902    ,394,394,394
XS GIS Cut Line= 4
       3766395.5     10165990.61       3766334.2     10165321.01
      3766018.02     10164763.56      3765826.92     10164536.61
#Sta/Elev= 30
       0  254.61     110  252.62   290.7  244.81   320.9  241.29   357.1  241.65
   362.1  243.78   391.2  244.28   472.2  242.93   622.1  244.22   672.4  242.83
   676.6  244.28   729.8   244.7   757.4  243.23   773.3  244.25     779  241.86
   787.3  244.29   800.6     243   832.4  244.09   838.2  241.92   844.8  244.24
     854  244.45   913.2  244.46   918.9  242.98   948.2  244.68  1182.9  243.89
  1220.4  245.03  1285.3  240.06  1336.5  242.74  1365.1  248.08    1610  259.61
#Mann= 3 , 0 , 0
       0     .17       0   622.1     .06       0   729.8     .17       0
#XS Ineff= 2 , 0
       0   622.1  244.22   729.8       0   244.7
Permanent Ineff=
       T       T
Bank Sta=622.1,729.8
XS Rating Curve= 0 ,0
Exp/Cntr=0.3,0.1

Type RM Length L Ch R = 1 ,6500    ,500,500,500
BEGIN DESCRIPTION:
CANEY CREEK NORTH TRIB NO 5 13.0
END DESCRIPTION:
XS GIS Cut Line= 3
      3766998.75     10165754.92      3766482.16     10165055.77
      3765822.67     10164492.02
#Sta/Elev= 30
  4130.7  261.67  4320.8   248.6  4491.9  239.92  4734.1  224.05  4949.1  225.76
  4991.2     223  5013.6  225.87  5056.4   226.1  5077.3  227.48  5091.5  226.54
  5105.8  226.46  5112.4  227.75  5134.3  227.02  5176.7  230.94    5264  231.85
  5389.7  237.41  5446.1  239.95    5476  245.48  5488.9  246.58  5503.2  245.97
  5517.5  243.24  5538.3  242.68  5552.6  238.66  5566.9  241.45  5594.2  243.42
    5624  248.02  5766.8  255.43  5829.2   258.7  5850.1  257.66  5867.6  259.24
#Mann= 8 ,-1 , 0
  4130.7     .17       0  4949.1     .09       0  5013.6     .17       0
    5264     .15       0  5389.7     .17       0    5476     .11       0
  5594.2     .17       0  5766.8     .11       0
#XS Ineff= 2 , 0
       0                  5112.4       0  227.75
Permanent Ineff=
       F       F
Bank Sta=4949.1,5013.6
XS Rating Curve= 0 ,0
Exp/Cntr=0.3,0.1

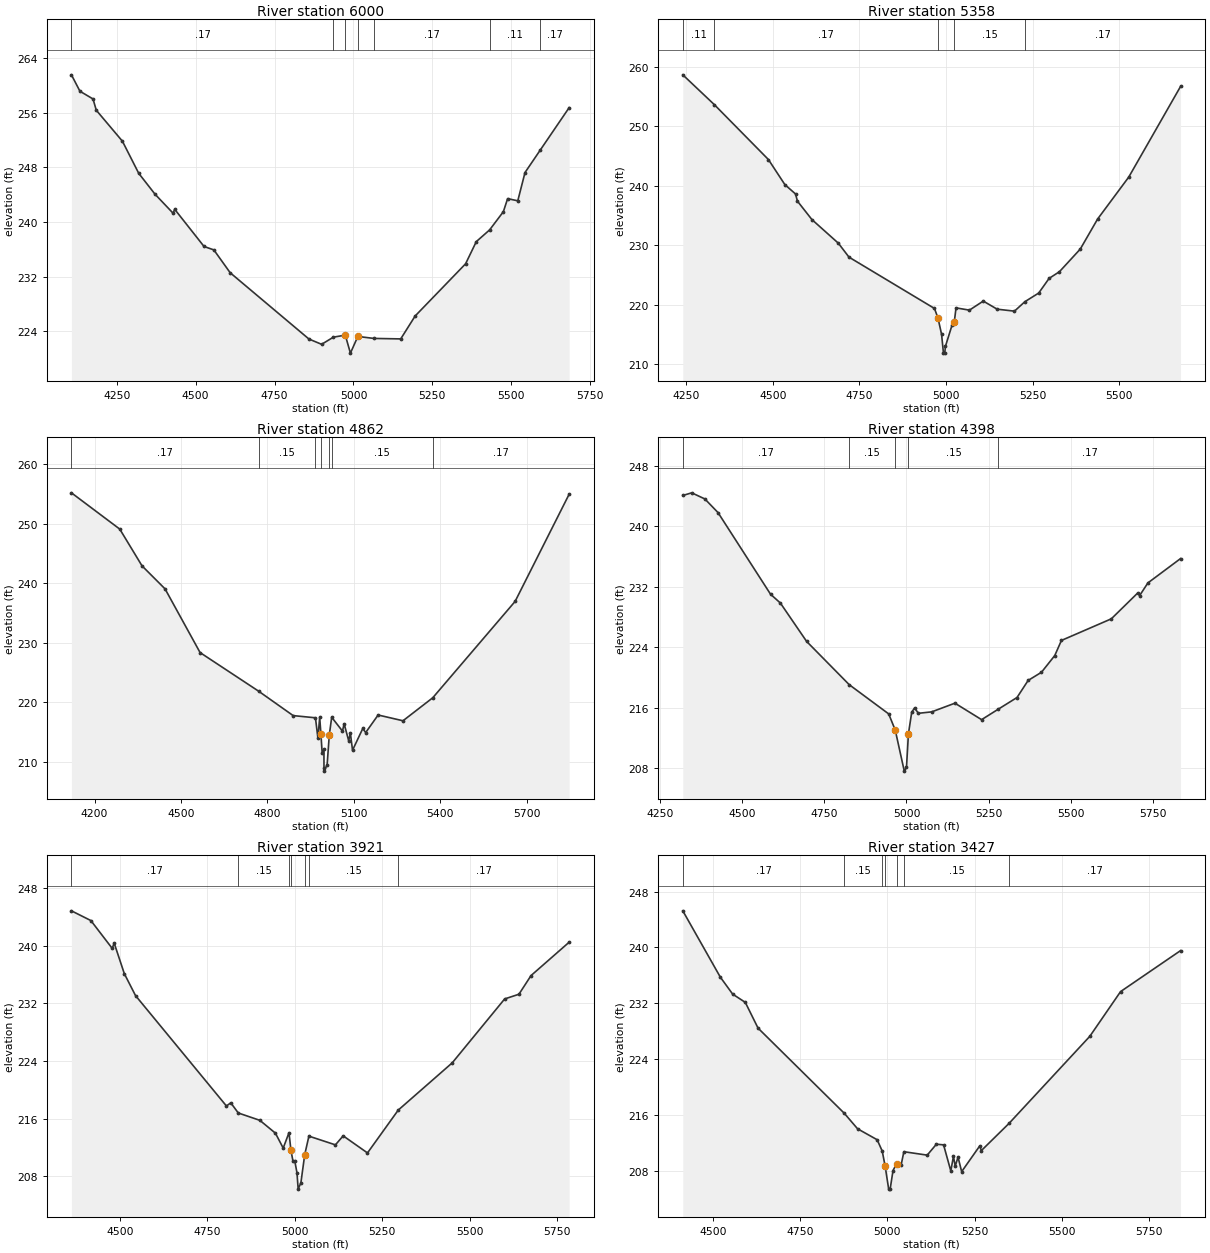
Type RM Length L Ch R = 1 ,6000    ,642,642,642
BEGIN DESCRIPTION:
CANEY CREEK NORTH TRIB NO 5 12.0
END DESCRIPTION:
XS GIS Cut Line= 3
      3767115.94      10165707.2      3766885.47     10164843.62
      3766595.85      10164224.4
#Sta/Elev= 30
  4106.2  261.52  4133.2  259.12  4174.6  257.99    4185  256.34  4267.8  251.81
  4319.5  247.11  4371.3  244.05  4428.3  241.28  4433.5  241.85  4526.5  236.41
  4557.6  235.91  4609.3  232.57    4859  222.87  4899.1   222.1  4936.6  223.15
  4974.1  223.44  4990.4  220.81  5013.9  223.25    5065  222.96  5149.8  222.89
  5195.5  226.24  5355.4  233.88  5389.3  237.12  5431.6  238.84  5475.1   241.5
  5488.6  243.41  5520.8  243.09  5543.7  247.23  5592.7  250.56  5683.6  256.72
#Mann= 7 ,-1 , 0
  4106.2     .17       0  4936.6     .11       0  4974.1     .06       0
  5013.9     .11       0    5065     .17       0  5431.6     .11       0
  5592.7     .17       0
Bank Sta=4974.1,5013.9
XS Rating Curve= 0 ,0
Exp/Cntr=0.3,0.1

Type RM Length L Ch R = 1 ,5358    ,496,496,496
BEGIN DESCRIPTION:
CANEY CREEK NORTH TRIB NO 5 10.0
END DESCRIPTION:
XS GIS Cut Line= 3
      3767295.02     10165667.58      3767473.61     10164928.86
      3767453.33     10164251.67
#Sta/Elev= 30
    4240  258.61  4331.3  253.59  4487.3  244.38  4534.8  240.17  4565.6   238.6
    4571   237.4  4612.9   234.3  4689.1  230.34    4720  227.99  4966.9  219.37
  4977.2  217.71  4987.4  215.02  4992.8  211.87  4996.6  211.87  4998.4  212.99
  5017.8  216.61  5024.1  217.11  5029.1  219.47  5067.8  219.09  5107.8  220.61
  5147.9  219.25  5197.9  218.92    5228  220.51  5267.9  221.96  5297.9  224.42
  5327.9  225.55    5388  229.35    5438  234.39    5528  241.44  5677.5  256.65
#Mann= 5 ,-1 , 0
    4240     .11       0  4331.3     .17       0  4977.2     .09       0
  5024.1     .15       0    5228     .17       0
Bank Sta=4977.2,5024.1
XS Rating Curve= 0 ,0
Exp/Cntr=0.3,0.1

Type RM Length L Ch R = 1 ,4862    ,464,464,464
BEGIN DESCRIPTION:
CANEY CREEK NORTH TRIB NO 5 9.0
END DESCRIPTION:
XS GIS Cut Line= 3
      3767433.28     10165689.85      3767945.68     10164973.93
      3767524.67     10164238.28
#Sta/Elev= 30
  4119.6   255.2  4287.4   249.1  4364.8  242.91  4444.7  239.04  4566.3  228.33
  4769.1  221.85  4889.4  217.73  4966.8  217.36  4975.4  213.92  4981.5  217.43
 4985.72  214.69  4990.1  211.43  4996.3  212.05  4996.4  208.89  4996.7  208.39
  5007.4  209.47  5014.8  214.43  5023.2  217.45  5060.6  215.12  5066.4  216.36
  5082.2  213.49    5088  214.82  5095.5   211.9  5131.1  215.56  5141.2  214.88
  5184.4  217.83  5270.7  216.86  5374.1  220.73    5660  236.94  5847.6  254.97
#Mann= 7 ,-1 , 0
  4119.6     .17       0  4769.1     .15       0  4966.8     .12       0
 4985.72     .09       0  5014.8     .12       0  5023.2     .15       0
  5374.1     .17       0
Bank Sta=4985.72,5014.8
XS Rating Curve= 0 ,0
Exp/Cntr=0.3,0.1

Type RM Length L Ch R = 1 ,4398    ,477,477,477
BEGIN DESCRIPTION:
CANEY CREEK NORTH TRIB NO 5 8.0
END DESCRIPTION:
XS GIS Cut Line= 3
      3768308.93     10165758.24      3768308.23     10165076.84
      3768443.03       10164253.
#Sta/Elev= 30
  4318.6  244.06  4345.8  244.41  4385.8   243.6  4425.8   241.8  4585.8     231
  4615.8  229.83  4695.8  224.75  4825.5  219.03  4945.8  215.16  4965.8  213.01
  4993.3  207.59    5000  208.09  5005.9  212.52    5016   215.4  5024.8  215.95
  5036.2  215.24  5076.8  215.43  5147.6  216.58  5228.8   214.4  5280.1   215.8
  5336.7  217.33  5370.6  219.59  5411.2  220.67  5451.7  222.88    5472  224.88
    5624  227.74  5704.9  231.18    5710   230.8  5735.4  232.49  5834.8  235.71
#Mann= 5 ,-1 , 0
  4318.6     .17       0  4825.5     .15       0  4965.8     .09       0
  5005.9     .15       0  5280.1     .17       0
Bank Sta=4965.8,5005.9
XS Rating Curve= 0 ,0
Exp/Cntr=0.3,0.1

Type RM Length L Ch R = 1 ,3921    ,494,494,494
BEGIN DESCRIPTION:
CANEY CREEK NORTH TRIB NO 5 7.0
END DESCRIPTION:
XS GIS Cut Line= 3
      3768367.65     10165745.73      3768658.23     10165176.84
      3768980.29     10164461.72
#Sta/Elev= 30
  4361.2  244.83  4416.8  243.48  4477.8  239.62  4483.4  240.36  4512.4  236.12
  4544.5  233.07  4804.4  217.76  4816.8   218.2  4838.3  216.79    4900  215.77
  4944.5  213.99  4966.7  211.92  4983.3  214.06  4988.9  211.59  4994.8  210.08
    5000  210.08  5006.1  208.49  5009.5  206.23  5017.3  207.11  5028.3  211.03
  5040.2  213.58    5116  212.37  5138.2  213.62  5207.7  211.25  5295.6  217.19
  5450.1  223.75  5599.9  232.61  5640.7  233.26  5675.3  235.85  5784.3  240.48
#Mann= 7 ,-1 , 0
  4361.2     .17       0  4838.3     .15       0  4983.3     .12       0
  4988.9     .09       0  5028.3     .12       0  5040.2     .15       0
  5295.6     .17       0
Bank Sta=4988.9,5028.3
XS Rating Curve= 0 ,0
Exp/Cntr=0.3,0.1

Type RM Length L Ch R = 1 ,3427    ,484,484,484
BEGIN DESCRIPTION:
CANEY CREEK NORTH TRIB NO 5 6.0
END DESCRIPTION:
XS GIS Cut Line= 3
      3768619.44     10165833.79      3768973.49     10165366.84
       3769189.8     10164555.07
#Sta/Elev= 30
    4414  245.24  4521.5  235.76  4556.9  233.33  4593.1  232.15  4629.6  228.47
  4876.4  216.31  4914.7  214.08  4970.9  212.51  4985.4  210.89  4993.7  208.75
  5003.9  205.45  5008.1  205.45  5016.3   208.1  5026.7  209.11  5039.3  208.84
  5047.4   210.8  5114.3  210.31  5140.5  211.87  5161.2  211.78  5181.9  208.05
  5189.4  210.12  5194.6  208.75  5202.6  210.02    5213  207.95  5264.4   211.6
  5269.6  210.97  5348.6  214.84  5580.2   227.3  5668.3  233.69  5840.1  239.55
#Mann= 7 ,-1 , 0
    4414     .17       0  4876.4     .15       0  4985.4     .12       0
  4993.7     .09       0  5026.7     .12       0  5047.4     .15       0
  5348.6     .17       0
Bank Sta=4993.7,5026.7
XS Rating Curve= 0 ,0
Exp/Cntr=0.3,0.1

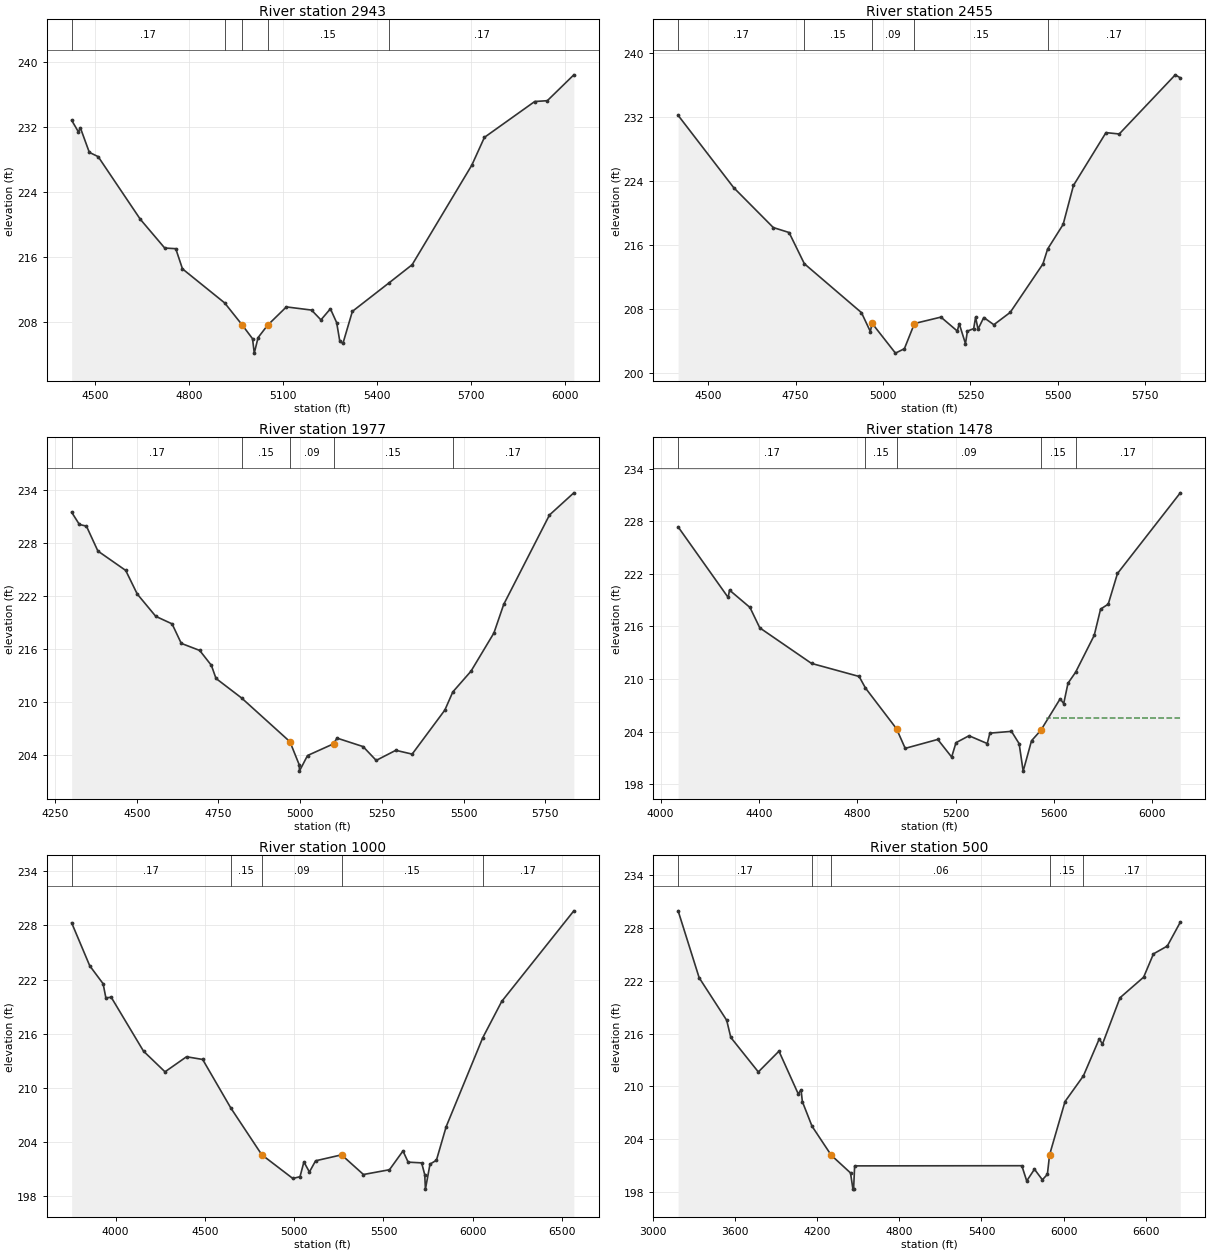
Type RM Length L Ch R = 1 ,2943    ,488,488,488
BEGIN DESCRIPTION:
CANEY CREEK NORTH TRIB NO 5 5.0
END DESCRIPTION:
XS GIS Cut Line= 3
      3768967.87     10166011.06      3769360.84     10165591.44
       3769269.8     10164566.67
#Sta/Elev= 30
  4425.1  232.86  4446.3  231.45  4453.2   231.9  4481.5   228.9  4509.8  228.37
  4644.3  220.65  4722.3   217.1  4757.5  217.02    4779  214.53  4913.8  210.33
    4970   207.6  5002.7  205.92  5008.3  204.14  5020.4  206.05  5050.6  207.57
  5110.8  209.84  5191.1  209.45  5221.2  208.24  5251.4  209.61  5271.4   207.9
  5281.5  205.59  5291.5  205.35  5321.6  209.29  5438.5   212.8  5512.4  215.04
  5703.1  227.33  5743.3  230.75  5903.9  235.17  5944.1  235.27  6028.8  238.46
#Mann= 5 ,-1 , 0
  4425.1     .17       0  4913.8     .15       0    4970     .09       0
  5050.6     .15       0  5438.5     .17       0
Bank Sta=4970,5050.6
XS Rating Curve= 0 ,0
Exp/Cntr=0.3,0.1

Type RM Length L Ch R = 1 ,2455    ,478,478,478
BEGIN DESCRIPTION:
CANEY CREEK NORTH TRIB NO 5 4.0
END DESCRIPTION:
XS GIS Cut Line= 3
      3769701.98     10166370.91      3769777.51       10165790.
      3770117.84     10165011.11
#Sta/Elev= 30
  4414.2  232.25  4573.2  223.21  4686.3  218.23  4731.4  217.61  4775.1  213.71
  4938.4   207.6  4963.8  205.24  4968.8  206.26  5035.6  202.54  5061.1  203.09
  5089.9  206.24  5165.6  207.04  5212.4   205.3  5217.9  206.22  5235.8  203.72
  5241.3  205.29  5259.2   205.6  5264.7  207.02  5271.7  205.54  5288.1  206.99
  5316.9  206.09  5363.7  207.63  5457.2  213.68  5470.6  215.54    5515  218.62
  5544.5  223.49  5637.5  230.09  5675.4  229.92  5835.6  237.31    5850  236.93
#Mann= 5 ,-1 , 0
  4414.2     .17       0  4775.1     .15       0  4968.8     .09       0
  5089.9     .15       0  5470.6     .17       0
Bank Sta=4968.8,5089.9
XS Rating Curve= 0 ,0
Exp/Cntr=0.3,0.1

Type RM Length L Ch R = 1 ,1977    ,499,499,499
BEGIN DESCRIPTION:
CANEY CREEK NORTH TRIB NO 5 3.0
END DESCRIPTION:
XS GIS Cut Line= 3
      3769760.73     10166387.67      3770234.32     10165873.55
      3770213.89      10165036.6
#Sta/Elev= 30
    4301  231.44  4324.6  230.06  4346.2  229.87  4381.3  227.06  4466.4  224.87
  4501.6  222.21  4558.3  219.69  4608.2  218.84  4636.3  216.64  4692.7  215.84
  4728.4  214.16  4742.6  212.68  4820.7  210.48  4968.8  205.54  4997.2  202.93
  4997.7  202.22  5022.5  203.98  5102.5  205.31  5112.5  205.95  5192.5  204.99
  5232.6  203.43  5292.6  204.57  5342.6  204.14  5442.6  209.11    5467  211.16
  5522.6   213.5  5592.7  217.81  5622.7  221.04  5762.7  231.13  5837.2  233.63
#Mann= 5 ,-1 , 0
    4301     .17       0  4820.7     .15       0  4968.8     .09       0
  5102.5     .15       0    5467     .17       0
Bank Sta=4968.8,5102.5
XS Rating Curve= 0 ,0
Exp/Cntr=0.3,0.1

Type RM Length L Ch R = 1 ,1478    ,478,478,478
BEGIN DESCRIPTION:
CANEY CREEK NORTH TRIB NO 5 2.0
END DESCRIPTION:
XS GIS Cut Line= 3
      3769819.47     10166438.02      3770672.69     10166071.04
       3770306.2     10165019.79
#Sta/Elev= 30
  4071.2  227.37  4274.7  219.31  4280.2  220.15  4363.4  218.17  4403.3  215.84
  4613.7  211.78  4807.2  210.29    4833  208.97  4959.3  204.32  4994.6  202.08
    5127   203.1  5183.5  201.09  5201.2  202.73  5254.1  203.52  5328.3  202.63
  5338.9  203.82  5426.8  204.02  5457.9  202.62  5474.3  199.48  5508.3  202.95
  5545.8  204.13  5624.8  207.74  5639.1  207.19  5656.6  209.52  5687.5  210.77
  5763.3  214.99  5789.1  217.98  5820.2  218.55  5857.8  222.05  6113.3  231.26
#Mann= 5 ,-1 , 0
  4071.2     .17       0    4833     .15       0  4959.3     .09       0
  5545.8     .15       0  5687.5     .17       0
#XS Ineff= 2 , 0
       0                  5571.6       0  205.58
Permanent Ineff=
       F       F
Bank Sta=4959.3,5545.8
XS Rating Curve= 0 ,0
Exp/Cntr=0.3,0.1

Type RM Length L Ch R = 1 ,1000    ,500,500,500
BEGIN DESCRIPTION:
CANEY CREEK NORTH TRIB NO 5 2.5
END DESCRIPTION:
XS GIS Cut Line= 4
       3769806.9     10166500.96      3771005.59     10166399.12
       3771038.4     10166371.03      3770411.12     10164935.93
#Sta/Elev= 30
  3753.8  228.29  3855.1  223.53    3930  221.54  3945.4  219.98  3975.5  220.04
  4156.2  214.07  4276.6  211.78  4397.1  213.45  4487.4  213.15  4645.2  207.77
  4818.6  202.59  4992.5  199.96  5032.7  200.16  5054.5  201.79  5085.3  200.68
    5120  201.92  5265.4  202.58  5387.9   200.4  5533.7  200.93  5609.4  203.01
  5638.2  201.77  5713.9  201.69  5731.2  200.38    5735  198.78  5760.7  201.55
  5796.6  201.98  5851.2   205.7  6055.9  215.55  6162.3  219.58  6566.2  229.62
#Mann= 5 ,-1 , 0
  3753.8     .17       0  4645.2     .15       0  4818.6     .09       0
  5265.4     .15       0  6055.9     .17       0
Bank Sta=4818.6,5265.4
XS Rating Curve= 0 ,0
Exp/Cntr=0.3,0.1

Type RM Length L Ch R = 1 ,500     ,0,0,0
BEGIN DESCRIPTION:
CANEY CREEK NORTH TRIB NO 5 1.0
END DESCRIPTION:
XS GIS Cut Line= 4
      3769764.89     10166580.69      3771460.08     10166400.26
      3771532.14     10166313.95      3770470.83     10164794.63
#Sta/Elev= 30
  3182.8  229.95  3336.6  222.35  3537.8  217.52  3567.9  215.57  3769.1  211.65
  3919.9  214.01  4060.7  209.16  4081.3  209.63  4090.9  208.28  4161.4  205.49
  4302.1  202.19  4442.8  200.18  4460.6  198.34  4465.4  198.34    4473  200.98
    5695     201  5730.7  199.27  5787.4   200.6  5845.2   199.4  5881.8  200.02
 5897.98  202.25  6010.7  208.29  6144.9   211.2    6261  215.41  6284.3  214.81
  6412.8  220.08  6585.5  222.42    6657  225.06  6758.2  225.95  6853.3  228.66
#Mann= 5 ,-1 , 0
  3182.8     .17       0  4161.4     .15       0  4302.1     .06       0
 5897.98     .15       0  6144.9     .17       0
Bank Sta=4302.1,5897.98
XS Rating Curve= 0 ,0
Exp/Cntr=0.3,0.1

Chan Stop Cuts=-1
Use User Specified Reach Order=0
Composite Channel Slope=5