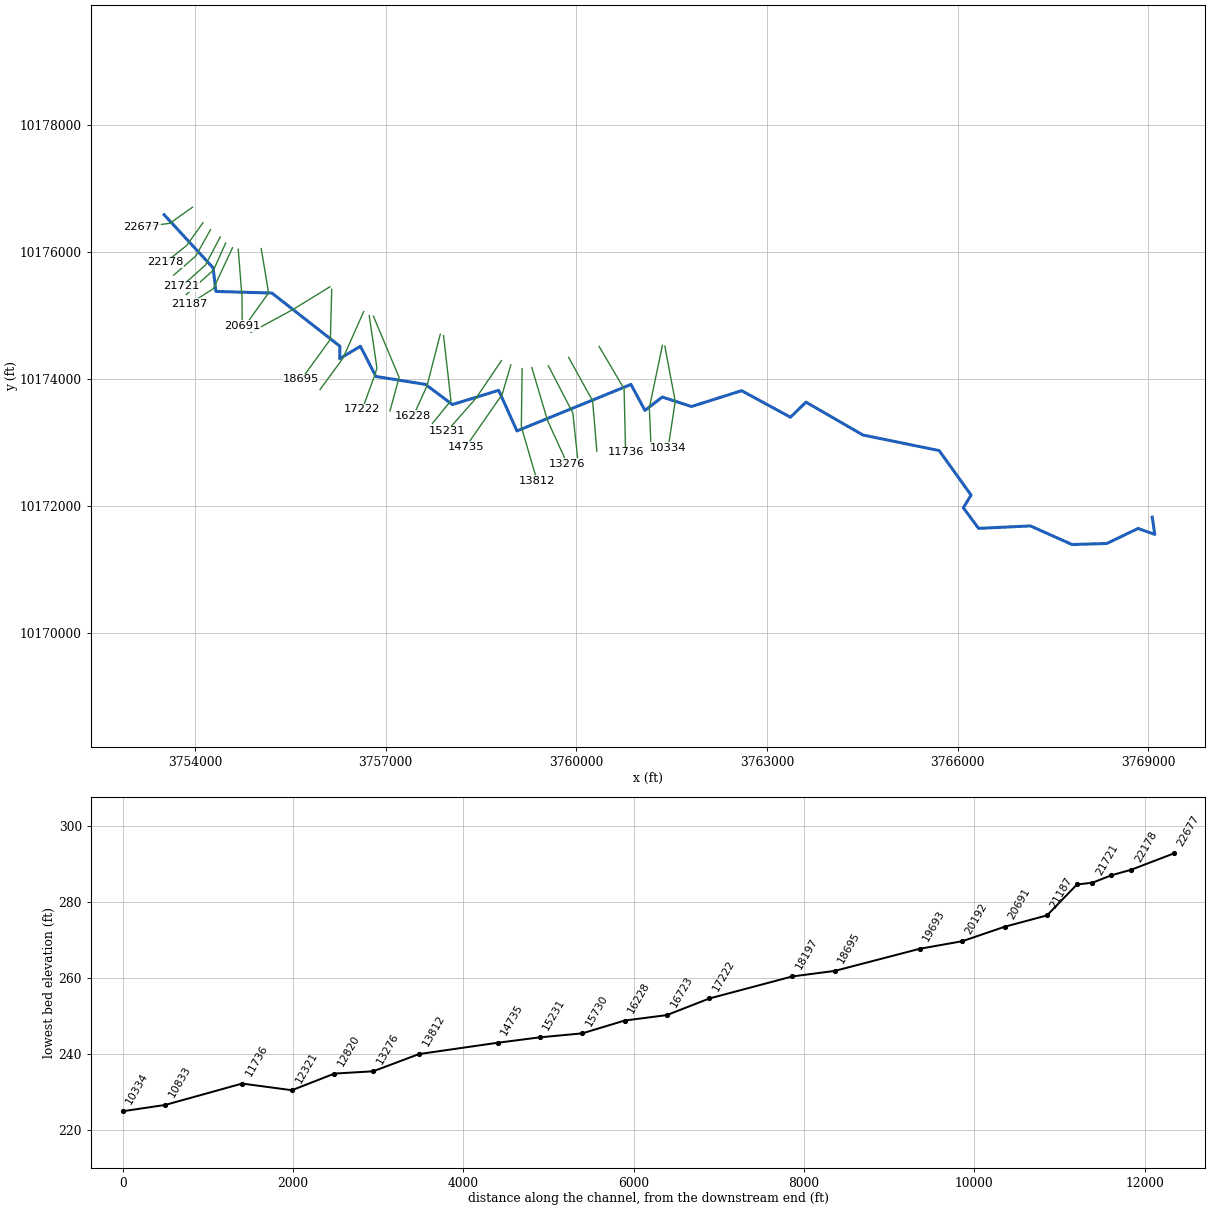
--- CANEY CREEK NORTH TRIB NO 6.prj (project) ---

Proj Title=CANEY CREEK NORTH TRIB NO 6 Base Level Engineering
Current Plan=p01
Default Exp/Contr=0.3,0.1
English Units
Geom File=g01
Flow File=f01
Flow File=f02
Plan File=p01
Y Axis Title=Elevation
X Axis Title(PF)=Main Channel Distance
X Axis Title(XS)=Station
BEGIN DESCRIPTION:
CANEY CREEK NORTH TRIB NO 6
END DESCRIPTION:
DSS Export Rating Curves= 0
DSS Export Rating Curve Sorted= 0
DSS Export Volume Flow Curves= 0
DXF OffsetX= 0
DXF OffsetY= 0
DXF ScaleX= 1
DXF ScaleY= 10

--- CANEY CREEK NORTH TRIB NO 6.p01 (plan) ---

Plan Title=Multiple Run
Short Identifier=Multiple
Geom File=g01
Flow File=f01
Subcritical Flow
K Sum by GR= 0
Std Step Tol= 0.01
Critical Tol= 0.01
Num of Std Step Trials= 20
Max Error Tol= 0.3
Flow Tol Ratio= 0.001
Split Flow NTrial= 30
Split Flow Tol= 0.02
Split Flow Ratio= 0.02
Log Output Level= 0
Friction Slope Method= 1
Unsteady Friction Slope Method= 2
Unsteady Bridges Friction Slope Method= 1
Parabolic Critical Depth
Global Vel Dist=  1 , 1 , 1
Global Log Level= 0
CheckData=True
Encroach Param= -1, 0, 0, 0
BEGIN DESCRIPTION:
Multiple Run
END DESCRIPTION:

--- CANEY CREEK NORTH TRIB NO 6.f01 (steady flow) ---

Flow Title=Multiple
Program Version=4.10
Number of Profiles= 7
Profile Names=10-year,25-year,50-year,1pct_min,100-year,1pct_plu,500-year
River Rch & RM=CANEY CREEK NORT,Reach-1         ,22677
     244     313     408     176     533    1610     936
River Rch & RM=CANEY CREEK NORT,Reach-1         ,21539
     905    1253    1717     774    2337    7058    4482
River Rch & RM=CANEY CREEK NORT,Reach-1         ,13276
    1034    1432    1965     885    2673    8072    5115
River Rch & RM=CANEY CREEK NORT,Reach-1         ,6356
    1538    2179    3034    1385    4183   12632    8235
River Rch & RM=CANEY CREEK NORT,Reach-1         ,4379
    1564    2200    3049    1383    4178   12617    8129
Boundary for River Rch & Prof#=CANEY CREEK NORT,Reach-1         , 1
Up Type= 0
Dn Type= 3
Dn Slope=0.005
Boundary for River Rch & Prof#=CANEY CREEK NORT,Reach-1         , 2
Up Type= 0
Dn Type= 3
Dn Slope=0.005
Boundary for River Rch & Prof#=CANEY CREEK NORT,Reach-1         , 3
Up Type= 0
Dn Type= 3
Dn Slope=0.005
Boundary for River Rch & Prof#=CANEY CREEK NORT,Reach-1         , 4
Up Type= 0
Dn Type= 3
Dn Slope=0.005
Boundary for River Rch & Prof#=CANEY CREEK NORT,Reach-1         , 5
Up Type= 0
Dn Type= 3
Dn Slope=0.005
Boundary for River Rch & Prof#=CANEY CREEK NORT,Reach-1         , 6
Up Type= 0
Dn Type= 3
Dn Slope=0.005
Boundary for River Rch & Prof#=CANEY CREEK NORT,Reach-1         , 7
Up Type= 0
Dn Type= 3
Dn Slope=0.005
DSS Import GetInterval= 0
DSS Import GetPeak= 0
DSS Import FillOption= 0

--- CANEY CREEK NORTH TRIB NO 6.f02 (steady flow) ---

Flow Title=Orig_BLE_Flow
Program Version=4.10
Number of Profiles= 7
Profile Names=10-year,25-year,50-year,1pct_min,100-year,1pct_plu,500-year
River Rch & RM=CANEY CREEK NORT,Reach-1         ,22677
     244     307     355     136     410    1239     544
River Rch & RM=CANEY CREEK NORT,Reach-1         ,21539
     905    1228    1493     596    1798    5431    2606
River Rch & RM=CANEY CREEK NORT,Reach-1         ,13276
    1034    1404    1709     681    2056    6209    2974
River Rch & RM=CANEY CREEK NORT,Reach-1         ,6356
    1538    2136    2638    1066    3218    9719    4788
River Rch & RM=CANEY CREEK NORT,Reach-1         ,4379
    1564    2157    2651    1064    3214    9707    4726
Boundary for River Rch & Prof#=CANEY CREEK NORT,Reach-1         , 1
Up Type= 0
Dn Type= 3
Dn Slope=0.005
Boundary for River Rch & Prof#=CANEY CREEK NORT,Reach-1         , 2
Up Type= 0
Dn Type= 3
Dn Slope=0.005
Boundary for River Rch & Prof#=CANEY CREEK NORT,Reach-1         , 3
Up Type= 0
Dn Type= 3
Dn Slope=0.005
Boundary for River Rch & Prof#=CANEY CREEK NORT,Reach-1         , 4
Up Type= 0
Dn Type= 3
Dn Slope=0.005
Boundary for River Rch & Prof#=CANEY CREEK NORT,Reach-1         , 5
Up Type= 0
Dn Type= 3
Dn Slope=0.005
Boundary for River Rch & Prof#=CANEY CREEK NORT,Reach-1         , 6
Up Type= 0
Dn Type= 3
Dn Slope=0.005
Boundary for River Rch & Prof#=CANEY CREEK NORT,Reach-1         , 7
Up Type= 0
Dn Type= 3
Dn Slope=0.005
DSS Import GetInterval= 0
DSS Import GetPeak= 0
DSS Import FillOption= 0

--- CANEY CREEK NORTH TRIB NO 6.g01 (geometry) ---

Geom Title=Existing Conditions
Program Version=4.10

River Reach=CANEY CREEK NORT,Reach-1
Reach XY= 30
      3753513.23     10176586.84      3754283.66     10175750.84
      3754327.39     10175379.38      3755208.94     10175354.12
      3756280.01     10174515.56      3756275.01     10174320.75
      3756602.61     10174515.65      3756845.02     10174040.62
      3757626.66     10173915.17      3758049.65     10173598.27
      3758778.21     10173822.01      3759065.54      10173182.8
      3760860.44     10173915.04      3761079.54     10173506.46
      3761353.28     10173716.34      3761811.35     10173566.86
      3762601.23     10173816.57      3763369.87      10173398.5
      3763613.95      10173636.2      3764510.77     10173118.34
       3765710.5     10172873.06      3766212.64     10172171.48
       3766090.3     10171972.56      3766330.69     10171648.16
      3767146.12     10171686.81       3767801.3     10171393.78
      3768349.13     10171410.03      3768841.24      10171646.8
      3769103.55     10171552.79      3769063.77     10171824.75

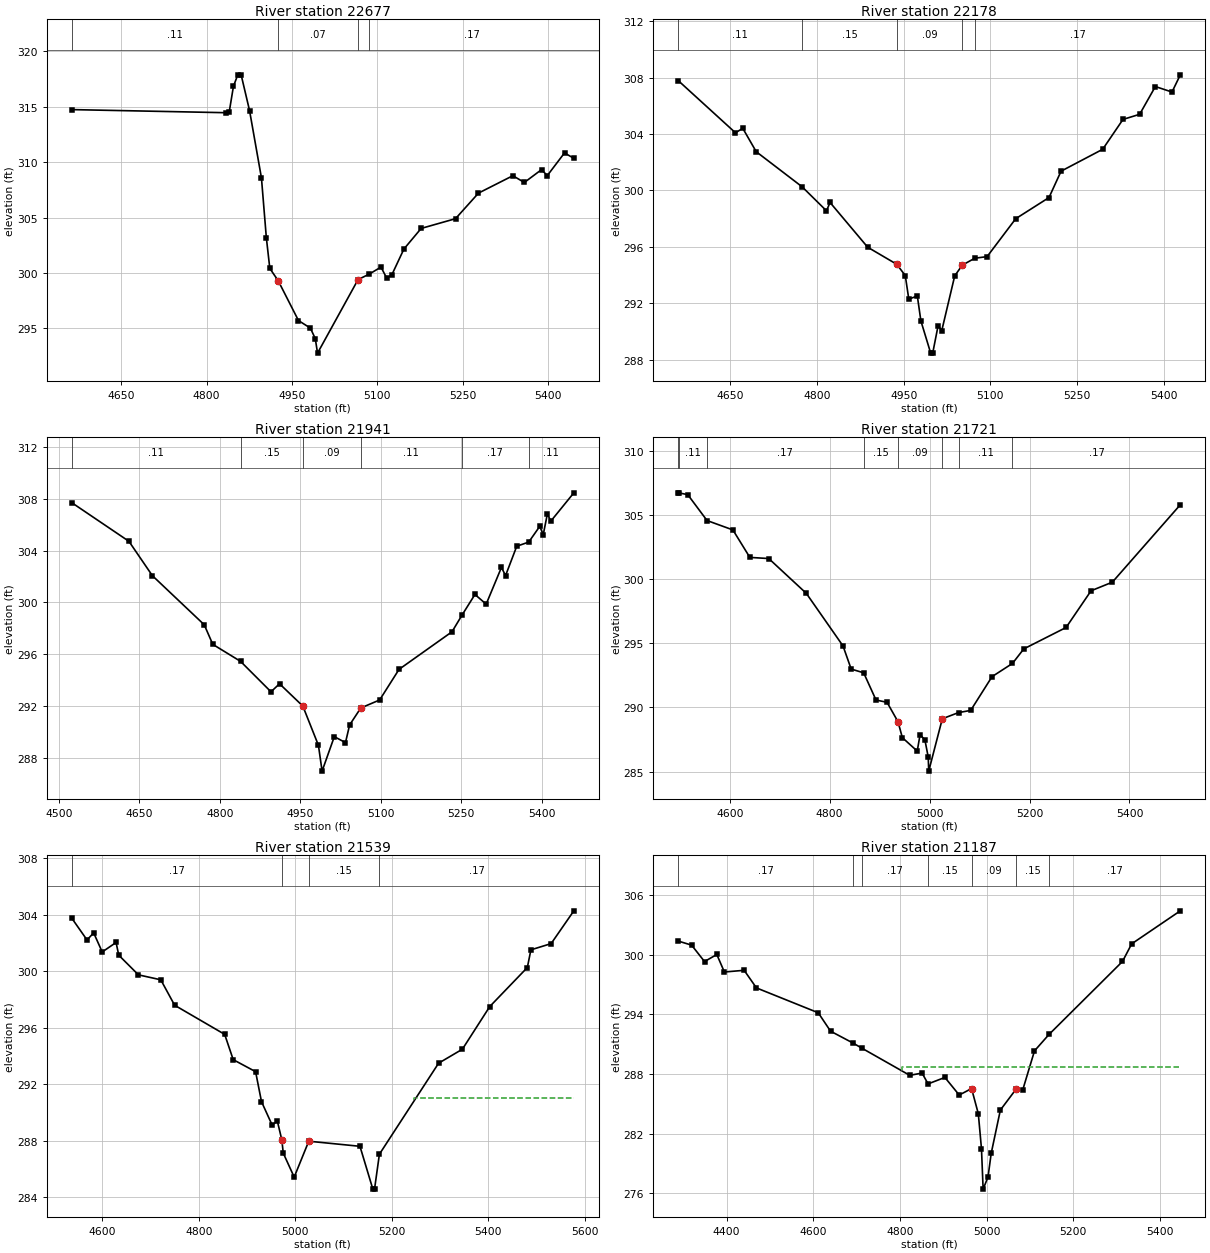
Type RM Length L Ch R = 1 ,22677   ,499,499,499
BEGIN DESCRIPTION:
CANEY CREEK NORTH TRIB NO 6 41.0
END DESCRIPTION:
XS GIS Cut Line= 3
      3753959.18     10176706.18      3753603.52     10176452.26
      3753161.53     10176396.41
#Sta/Elev= 30
    4563  314.75  4833.7  314.47  4839.8  314.55  4847.2  316.86  4854.6  317.86
  4860.7  317.89  4875.5  314.66  4896.4  308.58    4905  303.18  4911.1  300.41
  4925.8   299.3  4961.5   295.7  4982.4  295.02    4991  294.07    4995  292.76
  5066.2   299.4    5086   299.9  5106.5  300.53  5116.6  299.53  5125.4  299.81
  5146.8  302.16  5177.1  304.02  5237.5   304.9  5277.9  307.21  5338.3  308.78
  5358.5  308.17  5388.7  309.33  5398.8  308.79  5429.1  310.84  5445.5  310.35
#Mann= 4 ,-1 , 0
    4563     .11       0  4925.8     .07       0  5066.2     .11       0
    5086     .17       0
Bank Sta=4925.8,5066.2
XS Rating Curve= 0 ,0
Exp/Cntr=0.3,0.1

Type RM Length L Ch R = 1 ,22178   ,237,237,237
BEGIN DESCRIPTION:
CANEY CREEK NORTH TRIB NO 6 40.0
END DESCRIPTION:
XS GIS Cut Line= 3
      3754124.48     10176461.65      3753868.14     10176103.78
      3753533.27     10175835.79
#Sta/Elev= 30
  4559.8  307.79  4658.9  304.09  4671.5  304.41  4694.8  302.75  4774.3  300.26
  4816.4  298.56  4822.6  299.15  4887.7  295.98    4938  294.77  4952.8  293.97
  4958.9   292.3  4973.7  292.52  4979.8  290.76  4996.8  288.47  5000.3  288.47
  5009.6  290.41    5016  290.07  5038.4  293.95  5051.6  294.71  5073.2   295.2
  5094.4  295.31    5144     298  5201.6   299.5  5222.5  301.37  5294.5  302.92
  5329.7  305.04  5358.5   305.4  5385.7  307.37  5414.5  306.98  5428.9   308.2
#Mann= 5 ,-1 , 0
  4559.8     .11       0  4774.3     .15       0    4938     .09       0
  5051.6     .15       0  5073.2     .17       0
Bank Sta=4938,5051.6
XS Rating Curve= 0 ,0
Exp/Cntr=0.3,0.1

Type RM Length L Ch R = 1 ,21941   ,220,220,220
BEGIN DESCRIPTION:
Mapping XS 0ba891e3
END DESCRIPTION:
XS GIS Cut Line= 3
       3754243.2     10176352.07      3754010.46     10175936.85
       3753662.8     10175636.08
#Sta/Elev= 30
    4524  307.69  4630.5  304.71  4674.2  302.06  4770.9  298.27  4786.8  296.76
  4838.5  295.45  4895.3   293.1  4911.2  293.72  4954.6     292  4983.7  288.97
  4990.5  286.98  5013.3  289.64  5034.1  289.18  5041.8  290.54  5062.6  291.85
  5097.8  292.47  5133.9  294.83  5232.6  297.73  5251.2  299.01  5275.4  300.61
  5296.3  299.86  5324.8   302.7  5332.4  302.06  5353.3  304.33  5375.6  304.65
  5396.1  305.86  5402.7  305.23  5410.3  306.81  5416.9  306.27  5459.7  308.45
#Mann= 6 ,-1 , 0
    4524     .11       0  4838.5     .15       0  4954.6     .09       0
  5062.6     .11       0  5251.2     .17       0  5375.6     .11       0
Bank Sta=4954.6,5062.6
XS Rating Curve= 0 ,0
Exp/Cntr=0.3,0.1

Type RM Length L Ch R = 1 ,21721   ,182,182,182
BEGIN DESCRIPTION:
CANEY CREEK NORTH TRIB NO 6 39.0
END DESCRIPTION:
XS GIS Cut Line= 3
      3754396.57     10176237.84      3754162.07     10175792.85
      3753786.99      10175459.5
#Sta/Elev= 30
    4497   306.7  4497.6  306.72    4516  306.58  4554.7  304.56  4606.4  303.83
  4640.3  301.69  4678.2   301.6  4753.3  298.89  4826.8  294.79  4843.1  292.99
  4868.1   292.7  4892.8  290.58  4914.9   290.4  4936.9  288.88  4945.5  287.65
  4975.3   286.6    4981  287.89  4990.7  287.46  4997.3  286.14  4998.3  285.04
  5025.5  289.12  5057.9   289.6  5082.3  289.77    5125   292.4  5165.9  293.43
  5188.5  294.56  5273.2  296.23  5323.2  299.09  5365.8  299.76  5501.8  305.79
#Mann= 8 ,-1 , 0
    4497     .17       0  4497.6     .11       0  4554.7     .17       0
  4868.1     .15       0  4936.9     .09       0  5025.5     .15       0
  5057.9     .11       0  5165.9     .17       0
Bank Sta=4936.9,5025.5
XS Rating Curve= 0 ,0
Exp/Cntr=0.3,0.1

Type RM Length L Ch R = 1 ,21539   ,352,352,352
BEGIN DESCRIPTION:
Mapping XS bfb5d1a4
END DESCRIPTION:
XS GIS Cut Line= 3
      3754480.31     10176139.95       3754290.9     10175717.02
      3753861.68     10175331.11
#Sta/Elev= 30
  4536.6  303.74  4568.2   302.2    4582   302.7  4599.7  301.35  4628.4  302.02
    4634  301.12  4674.8  299.73  4721.1  299.38  4749.8  297.58  4853.5  295.52
  4871.2  293.73  4917.6  292.88  4929.8  290.76  4951.8  289.11  4962.7  289.38
 4972.04  288.04  4974.9  287.12  4997.6  285.42  5027.8  287.96  5133.9   287.6
  5160.6  284.57  5164.1  284.57  5174.2  287.04  5296.9  293.48  5346.2  294.47
    5403  297.49  5480.8  300.25  5488.2   301.5  5530.1  301.94  5577.2  304.26
#Mann= 4 ,-1 , 0
  4536.6     .17       0 4972.04     .09       0  5027.8     .15       0
  5174.2     .17       0
#XS Ineff= 2 , 0
       0                  5246.8       0  291.01
Permanent Ineff=
       F       F
Bank Sta=4972.04,5027.8
XS Rating Curve= 0 ,0
Exp/Cntr=0.3,0.1

Type RM Length L Ch R = 1 ,21187   ,496,496,496
BEGIN DESCRIPTION:
CANEY CREEK NORTH TRIB NO 6 38.0
END DESCRIPTION:
XS GIS Cut Line= 3
      3754589.44     10176069.11       3754288.7     10175423.96
      3753910.98       10175184.
#Sta/Elev= 30
  4288.2  301.36  4319.1  300.95  4348.9   299.3  4377.3  300.01  4394.7  298.25
  4440.4  298.42  4468.8  296.65  4611.5  294.15  4639.9   292.3  4691.6  291.11
  4713.5  290.56  4822.8  287.86  4851.2  288.09  4865.1     287  4903.9  287.65
    4937  285.88  4965.5  286.53  4981.1     284  4988.4  280.47  4992.2  276.42
  5003.5  277.64  5010.8  280.01    5032  284.37  5068.4  286.48  5083.7   286.4
  5110.8  290.32  5144.3  291.97    5314  299.31  5335.2  301.08  5447.5   304.4
#Mann= 7 ,-1 , 0
  4288.2     .17       0  4691.6     .15       0  4713.5     .17       0
  4865.1     .15       0  4965.5     .09       0  5068.4     .15       0
  5144.3     .17       0
#XS Ineff= 2 ,-1
  4805.5  4793.6  288.65  4903.9  4851.2  287.65
Permanent Ineff=
       F       F
Bank Sta=4965.5,5068.4
XS Rating Curve= 0 ,0
Exp/Cntr=0.3,0.1

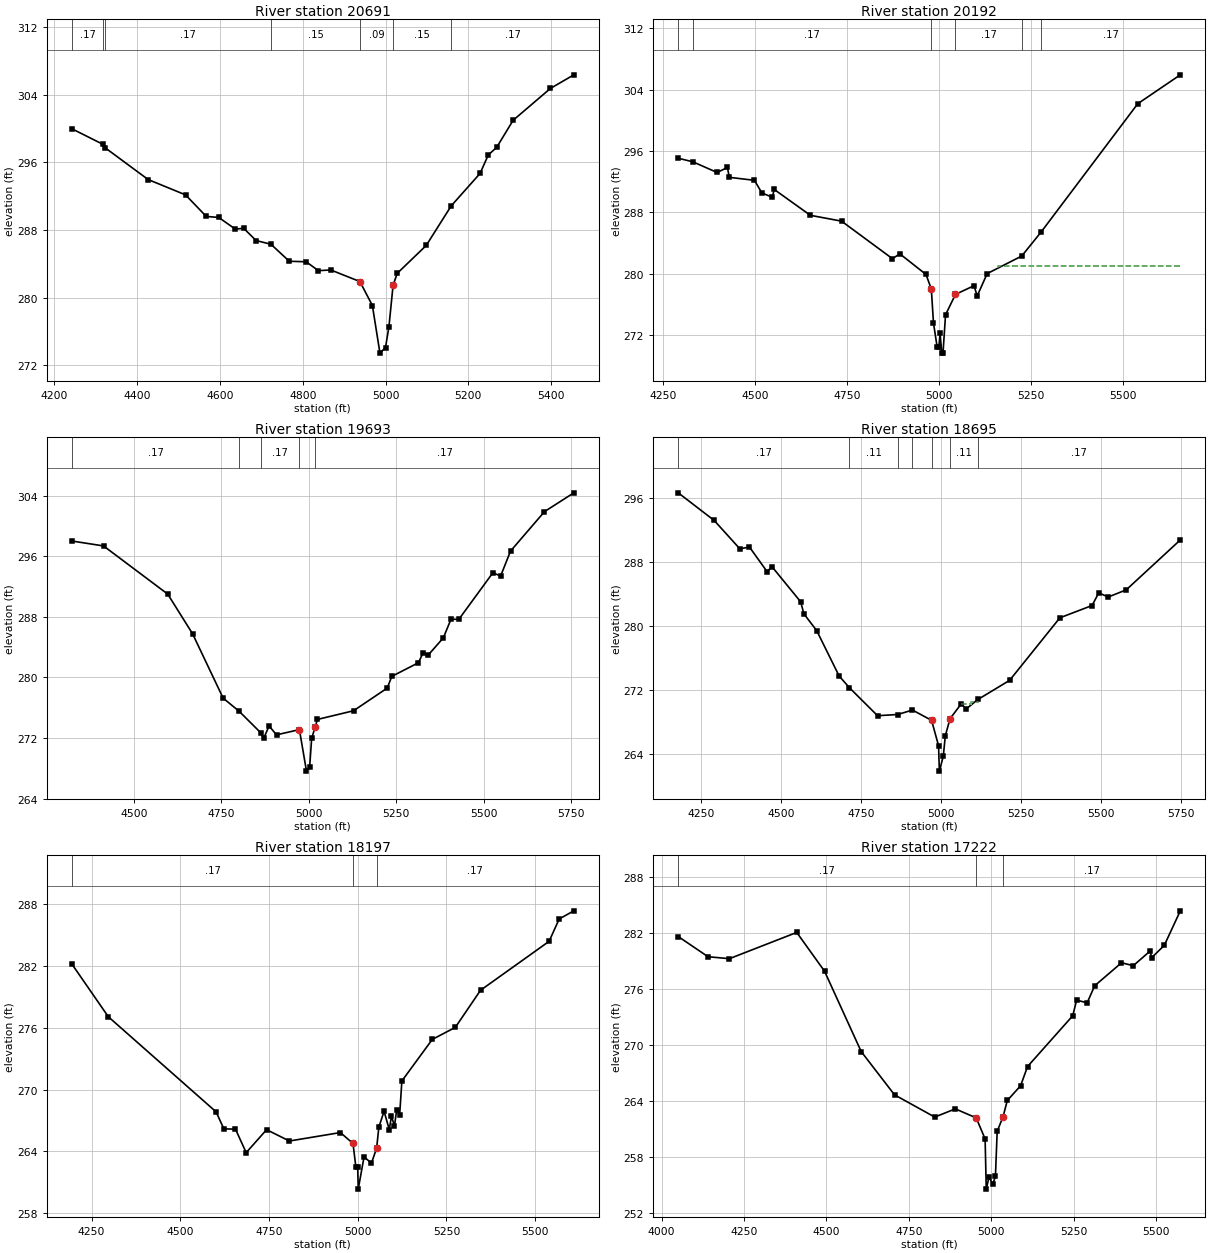
Type RM Length L Ch R = 1 ,20691   ,499,499,499
BEGIN DESCRIPTION:
CANEY CREEK NORTH TRIB NO 6 37.0
END DESCRIPTION:
XS GIS Cut Line= 3
      3754678.96       10176045.      3754738.19     10175289.42
      3754740.95     10174834.43
#Sta/Elev= 30
  4242.1  299.97  4317.5  298.12  4322.6  297.72  4426.6  293.96  4516.9  292.15
    4567   289.6  4597.1  289.48  4637.2   288.1  4657.3   288.2  4687.4  286.75
  4723.3  286.31  4767.6   284.3  4808.3  284.24  4837.9  283.19  4867.9  283.27
  4938.2   281.9  4968.3  279.07  4986.6  273.44    5000   274.1  5008.3  276.57
  5018.3  281.45  5028.3  282.87  5098.4  286.17  5158.9  290.86  5228.4  294.68
  5248.4  296.88  5268.4  297.75  5308.4  300.97  5398.4  304.73    5455  306.34
#Mann= 7 ,-1 , 0
  4242.1     .17       0  4317.5     .11       0  4322.6     .17       0
  4723.3     .15       0  4938.2     .09       0  5018.3     .15       0
  5158.9     .17       0
Bank Sta=4938.2,5018.3
XS Rating Curve= 0 ,0
Exp/Cntr=0.3,0.1

Type RM Length L Ch R = 1 ,20192   ,499,499,499
BEGIN DESCRIPTION:
CANEY CREEK NORTH TRIB NO 6 36.0
END DESCRIPTION:
XS GIS Cut Line= 3
      3755040.57     10176055.31      3755156.34     10175356.43
      3754775.38     10174822.38
#Sta/Elev= 30
  4291.6  295.06  4331.1   294.6  4397.3   293.2  4425.3  293.86  4430.3  292.57
  4498.6  292.18  4518.9  290.54  4547.3  289.96  4552.3  290.99  4650.7  287.61
  4735.4  286.85  4873.7  281.95  4893.9  282.58  4964.9  279.89  4979.4  277.98
  4985.2  273.57  4995.1  270.45    5000  270.45  5003.2  272.24  5007.6  269.62
  5011.1  269.62    5018  274.62    5045  277.29  5095.4  278.42    5104  277.08
  5131.1     280  5225.2   282.3  5278.4  285.47  5540.4  302.18    5656  305.95
#Mann= 6 ,-1 , 0
  4291.6     .11       0  4331.1     .17       0  4979.4     .09       0
    5045     .17       0  5225.2     .15       0  5278.4     .17       0
#XS Ineff= 2 , 0
       0                  5160.6       0  280.98
Permanent Ineff=
       F       F
Bank Sta=4979.4,5045
XS Rating Curve= 0 ,0
Exp/Cntr=0.3,0.1

Type RM Length L Ch R = 1 ,19693   ,998,998,998
BEGIN DESCRIPTION:
CANEY CREEK NORTH TRIB NO 6 35.0
END DESCRIPTION:
XS GIS Cut Line= 3
      3756121.95     10175452.63      3755545.35     10175097.47
       3754878.7      10174736.3
#Sta/Elev= 30
  4322.8  298.01  4413.6  297.36  4597.1     291  4668.2  285.76  4755.5  277.27
  4801.3  275.53  4863.2  272.69  4871.5  271.96  4886.9  273.59  4908.2  272.42
  4973.6  273.11  4993.8  267.63  5002.9  268.18  5008.6  271.94  5019.1  273.52
  5024.8  274.45  5128.4   275.6  5224.6  278.59  5237.8  280.14  5313.9  281.94
    5327  283.24  5341.4  282.93  5385.2  285.23    5407  287.69  5429.3  287.66
  5526.9  293.83  5548.8  293.38  5577.2  296.68  5674.3  301.89  5758.2  304.37
#Mann= 5 ,-1 , 0
  4322.8     .17       0  4801.3     .15       0  4863.2     .17       0
  4973.6     .09       0  5019.1     .17       0
Bank Sta=4973.6,5019.1
XS Rating Curve= 0 ,0
Exp/Cntr=0.3,0.1

Type RM Length L Ch R = 1 ,18695   ,498,498,498
BEGIN DESCRIPTION:
CANEY CREEK NORTH TRIB NO 6 34.0
END DESCRIPTION:
XS GIS Cut Line= 4
      3756150.12     10175413.38      3756129.74     10174634.31
      3756110.02     10174598.52      3755670.93      10173993.2
#Sta/Elev= 30
  4179.8  296.65  4292.1  293.19  4372.2  289.64  4402.2  289.86  4457.5  286.77
  4472.2  287.42  4562.2     283  4572.2   281.5  4612.3  279.39  4682.3  273.71
  4714.5  272.24  4802.3  268.74    4865  268.89  4911.3  269.45    4971  268.16
  4992.8  264.98  4995.3   261.8  5007.6  263.66  5013.8  266.21  5028.5  268.35
    5064  270.25  5078.7  269.57  5115.6  270.77  5214.8  273.17  5371.7     281
  5472.3  282.54  5493.1  284.13  5522.5   283.6  5578.9   284.5  5747.8  290.75
#Mann= 7 ,-1 , 0
  4179.8     .17       0  4714.5     .11       0    4865     .17       0
  4911.3     .11       0    4971     .06       0  5028.5     .11       0
  5115.6     .17       0
#XS Ineff= 2 ,-1
    5064  5093.4  270.25  5093.4  5120.5  270.49
Permanent Ineff=
       F       F
Bank Sta=4971,5028.5
XS Rating Curve= 0 ,0
Exp/Cntr=0.3,0.1

Type RM Length L Ch R = 1 ,18197   ,975,975,975
BEGIN DESCRIPTION:
CANEY CREEK NORTH TRIB NO 6 33.0
END DESCRIPTION:
XS GIS Cut Line= 3
      3756653.57     10175062.64      3756326.37     10174326.48
      3755967.03     10173834.79
#Sta/Elev= 30
  4194.4   282.2  4297.4  277.07    4601  267.84  4622.9  266.19  4655.7  266.16
  4685.8  263.88  4743.3  266.11  4807.6  265.01  4951.2  265.83  4986.8  264.77
  4994.8  262.49    5000  262.49  5001.5  260.34  5017.9  263.47  5038.8  262.86
  5053.4  264.33  5059.6  266.35  5074.3   267.9    5089  266.12  5095.1  267.41
  5103.6  266.48  5109.8  268.02  5118.2  267.55  5124.5  270.84  5210.2  274.87
  5275.1  276.04  5346.1  279.64  5539.3  284.39  5567.7  286.56    5609  287.35
#Mann= 3 , 0 , 0
  4194.4     .17       0  4986.8     .09       0  5053.4     .17       0
Bank Sta=4986.8,5053.4
XS Rating Curve= 0 ,0
Exp/Cntr=0.3,0.1

Type RM Length L Ch R = 1 ,17222   ,499,499,499
BEGIN DESCRIPTION:
CANEY CREEK NORTH TRIB NO 6 31.0
END DESCRIPTION:
XS GIS Cut Line= 4
       3756740.4     10175000.19      3756862.16     10174170.99
      3756828.37     10174064.73      3756633.09     10173525.39
#Sta/Elev= 30
  4050.4  281.66  4140.8  279.49  4205.6  279.28  4409.9   282.1  4494.2  277.94
  4605.4  269.31  4706.5  264.66  4828.6  262.27  4891.1  263.15  4954.4  262.18
  4981.4  259.92  4984.9  254.53  4993.3  255.85  5004.6  255.06  5012.7  255.89
    5018  260.74  5035.8   262.3  5048.7  264.05    5089  265.63  5110.2   267.7
  5247.2  273.15  5259.1  274.83    5291  274.54  5313.8  276.37  5395.1  278.84
    5431  278.53  5481.7  280.09    5487   279.4    5525  280.71  5573.6  284.42
#Mann= 3 , 0 , 0
  4050.4     .17       0  4954.4     .09       0  5035.8     .17       0
Bank Sta=4954.4,5035.8
XS Rating Curve= 0 ,0
Exp/Cntr=0.3,0.1

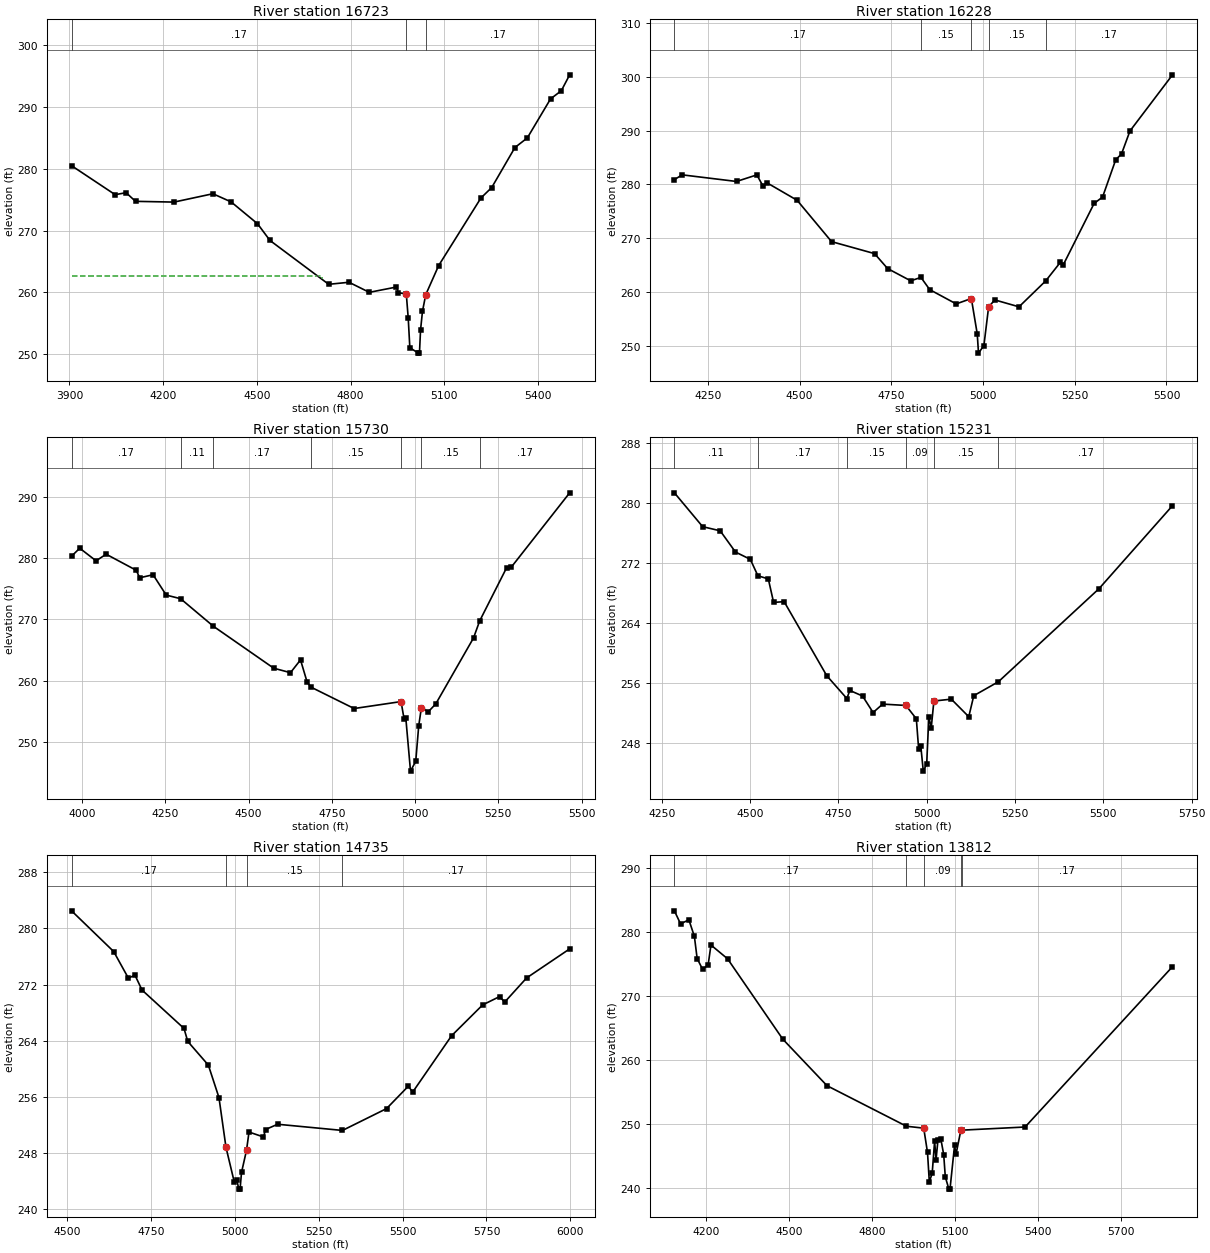
Type RM Length L Ch R = 1 ,16723   ,495,495,495
BEGIN DESCRIPTION:
CANEY CREEK NORTH TRIB NO 6 30.0
END DESCRIPTION:
XS GIS Cut Line= 4
      3756806.39     10174989.73      3757211.55      10174024.5
      3757198.84       10173980.      3757066.79     10173496.71
#Sta/Elev= 30
  3906.9  280.49  4046.4   275.8  4081.5  276.12  4111.5  274.72  4234.9   274.6
  4359.2  275.95  4417.5  274.63  4501.9   271.1  4541.8  268.39  4729.8  261.29
  4794.8  261.62  4859.8  259.99  4946.6  260.85  4952.9  259.92  4978.1  259.75
  4984.3  255.85  4989.5  251.03  5016.8  250.15  5020.3  250.15  5023.8  253.92
    5030  256.94  5040.4  259.61  5081.8  264.33  5217.1  275.27  5251.6  276.96
  5325.8  283.43  5365.5  284.99  5439.8   291.3  5474.3  292.63    5501   295.2
#Mann= 3 , 0 , 0
  3906.9     .17       0  4978.1     .09       0  5040.4     .17       0
#XS Ineff= 2 , 0
       0    4708  262.63               0
Permanent Ineff=
       F       F
Bank Sta=4978.1,5040.4
XS Rating Curve= 0 ,0
Exp/Cntr=0.3,0.1

Type RM Length L Ch R = 1 ,16228   ,498,498,498
BEGIN DESCRIPTION:
CANEY CREEK NORTH TRIB NO 6 29.0
END DESCRIPTION:
XS GIS Cut Line= 3
      3757858.45     10174705.03      3757649.05     10173890.21
      3757434.85     10173420.33
#Sta/Elev= 30
  4158.7   280.9  4179.7  281.79    4328  280.56  4383.4  281.78  4400.3  279.69
  4410.6  280.33  4493.2  277.07  4587.1   269.4  4704.2  267.18  4739.8  264.41
  4802.9  262.13  4830.7  262.77  4854.6   260.5  4926.8  257.85  4968.1  258.85
  4984.2  252.28  4987.6  248.72  5002.3  250.12  5015.2  257.29    5032  258.59
    5098  257.31  5170.7  262.11  5210.6  265.55  5218.9  265.13  5302.8  276.49
  5325.8  277.67  5361.7   284.6  5377.4  285.66  5400.4  289.92  5516.4  300.34
#Mann= 5 ,-1 , 0
  4158.7     .17       0  4830.7     .15       0  4968.1     .09       0
  5015.2     .15       0  5170.7     .17       0
Bank Sta=4968.1,5015.2
XS Rating Curve= 0 ,0
Exp/Cntr=0.3,0.1

Type RM Length L Ch R = 1 ,15730   ,499,499,499
BEGIN DESCRIPTION:
CANEY CREEK NORTH TRIB NO 6 28.0
END DESCRIPTION:
XS GIS Cut Line= 3
      3757910.53     10174684.24      3758026.05     10173659.43
      3757733.46     10173298.79
#Sta/Elev= 30
  3968.7   280.3  3993.2  281.59  4042.3  279.54  4072.5  280.62    4163     278
  4173.2  276.78  4213.4  277.28  4252.9  273.97  4296.1  273.38  4394.5   268.9
  4575.7  262.08    4626  261.35  4656.2  263.43  4676.3  259.77  4688.3  258.98
  4817.2  255.52  4958.1  256.65  4967.3  253.78  4972.3  254.02  4986.5  245.34
  5002.2  246.95  5011.1  252.69  5019.1  255.65  5039.9     255  5062.2  256.26
  5175.7     267  5194.1  269.76  5274.8  278.39  5289.2  278.52  5464.4   290.6
#Mann= 7 ,-1 , 0
  3968.7     .17       0  4296.1     .11       0  4394.5     .17       0
  4688.3     .15       0  4958.1     .09       0  5019.1     .15       0
  5194.1     .17       0
#XS Ineff= 2 , 0
       0  4726.6  257.77               0
Permanent Ineff=
       F       F
Bank Sta=4958.1,5019.1
XS Rating Curve= 0 ,0
Exp/Cntr=0.3,0.1

Type RM Length L Ch R = 1 ,15231   ,496,496,496
BEGIN DESCRIPTION:
CANEY CREEK NORTH TRIB NO 6 27.0
END DESCRIPTION:
XS GIS Cut Line= 3
      3758820.28      10174288.4      3758420.33     10173696.81
      3757960.15     10173174.92
#Sta/Elev= 30
  4285.9  281.37  4365.9  276.86  4415.5  276.31  4458.8  273.48  4500.8  272.51
  4522.2  270.32  4551.7   269.9  4566.7  266.77  4596.5  266.87  4717.2     257
  4774.1  253.96  4782.4  255.04  4818.4   254.3  4848.3   252.1  4875.4  253.22
  4941.2  253.04  4970.7  251.26  4977.2  247.28  4983.2  247.69  4990.4  244.29
    5000  245.23  5006.1  251.56  5012.8  250.02  5020.4  253.63  5069.7  253.88
  5119.1  251.54  5133.3  254.34    5203   256.2  5487.6  268.59  5695.8  279.66
#Mann= 6 ,-1 , 0
  4285.9     .11       0  4522.2     .17       0  4774.1     .15       0
  4941.2     .09       0  5020.4     .15       0    5203     .17       0
#XS Ineff= 2 , 0
       0  4782.4  255.04               0
Permanent Ineff=
       F       F
Bank Sta=4941.2,5020.4
XS Rating Curve= 0 ,0
Exp/Cntr=0.3,0.1

Type RM Length L Ch R = 1 ,14735   ,923,923,923
BEGIN DESCRIPTION:
CANEY CREEK NORTH TRIB NO 6 26.0
END DESCRIPTION:
XS GIS Cut Line= 3
      3758969.56     10174222.37      3758831.99     10173755.93
      3758262.71     10172936.34
#Sta/Elev= 30
  4513.7   282.5  4639.2   276.7  4682.9  272.92  4702.7  273.33  4723.6  271.22
  4848.7  265.75  4859.9   263.9  4921.3  260.52  4952.9   255.9  4973.8  248.82
  4998.4  243.89    5006   244.1  5012.3  242.86  5015.8  242.86  5020.1  245.24
    5035  248.39  5042.4  250.99  5085.6  250.29  5091.7  251.35  5127.7   252.1
  5320.9  251.22  5452.3  254.33  5517.3  257.53    5530  256.67  5646.1  264.71
  5738.6   269.1  5789.3  270.29  5804.1  269.49  5869.6  272.94  5997.9  277.08
#Mann= 4 ,-1 , 0
  4513.7     .17       0  4973.8     .09       0    5035     .15       0
  5320.9     .17       0
Bank Sta=4973.8,5035
XS Rating Curve= 0 ,0
Exp/Cntr=0.3,0.1

Type RM Length L Ch R = 1 ,13812   ,536,536,536
BEGIN DESCRIPTION:
CANEY CREEK NORTH TRIB NO 6 25.0
END DESCRIPTION:
XS GIS Cut Line= 3
      3759146.65     10174163.36      3759134.69     10173247.34
      3759382.75     10172396.04
#Sta/Elev= 30
  4083.9  283.25  4106.2  281.21  4136.2  281.86  4156.2  279.27  4166.2  275.82
  4186.2  274.11  4206.2  274.88  4216.2  277.92  4276.2  275.78  4476.2  263.25
  4636.2     256  4923.8  249.68  4986.3  249.38    5000  245.59  5006.5  241.02
  5016.9  242.34  5025.7  247.34  5030.9  244.47  5037.8  247.53  5048.2   247.7
  5058.6  245.27  5064.4  241.78  5077.4  239.88  5081.4  239.88  5097.9   246.7
  5103.1  245.29  5121.1  249.16    5124  249.07  5353.2  249.56  5886.7  274.55
#Mann= 5 ,-1 , 0
  4083.9     .17       0  4923.8     .15       0  4986.3     .09       0
  5121.1     .15       0    5124     .17       0
Bank Sta=4986.3,5121.1
XS Rating Curve= 0 ,0
Exp/Cntr=0.3,0.1

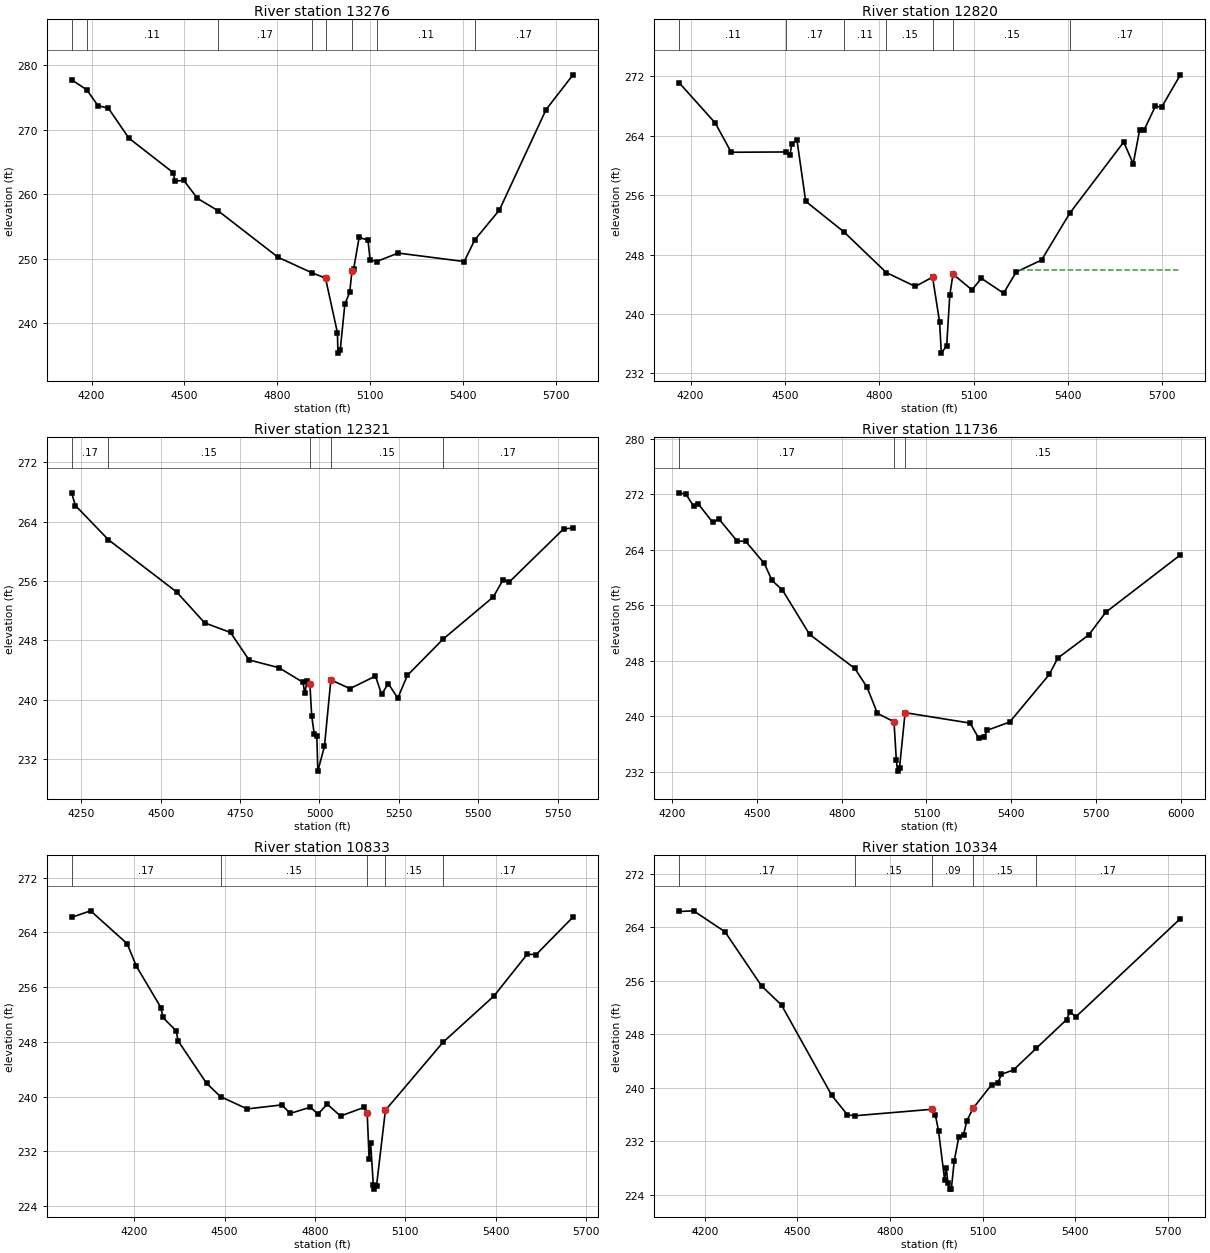
Type RM Length L Ch R = 1 ,13276   ,456,456,456
BEGIN DESCRIPTION:
CANEY CREEK NORTH TRIB NO 6 24.0
END DESCRIPTION:
XS GIS Cut Line= 3
      3759299.43     10174180.73      3759544.95     10173351.82
      3759857.85     10172664.71
#Sta/Elev= 30
  4135.5  277.74  4184.5   276.2  4220.9  273.72  4254.1  273.35  4320.6  268.69
  4464.1  263.33  4469.3     262  4497.3  262.18  4541.9  259.36  4607.5  257.47
  4802.6  250.21  4911.5  247.82  4955.6  246.99  4994.1  238.52  4995.8  235.35
  5003.2  235.85  5018.2  242.96  5033.8   244.8  5041.2  248.13  5046.7  248.45
  5064.3  253.32  5092.8  252.85  5099.7  249.81  5120.6  249.56  5190.5  250.87
  5403.5  249.56    5438  252.93  5517.3  257.55  5668.1  273.13    5755  278.52
#Mann= 8 ,-1 , 0
  4135.5     .17       0  4184.5     .11       0  4607.5     .17       0
  4911.5     .15       0  4955.6     .09       0  5041.2     .15       0
  5120.6     .11       0    5438     .17       0
Bank Sta=4955.6,5041.2
XS Rating Curve= 0 ,0
Exp/Cntr=0.3,0.1

Type RM Length L Ch R = 1 ,12820   ,499,499,499
BEGIN DESCRIPTION:
CANEY CREEK NORTH TRIB NO 6 23.0
END DESCRIPTION:
XS GIS Cut Line= 3
      3759559.85     10174208.51      3759944.92     10173465.46
      3760025.12     10172712.01
#Sta/Elev= 30
  4163.1  271.15  4278.4  265.71  4329.2  261.77  4504.4  261.81  4516.2  261.39
  4521.8   262.9  4538.3  263.44  4566.1  255.17  4688.1  251.04  4822.6  245.58
  4914.8  243.71  4969.6  244.97  4991.8  238.98  4997.6  234.74  5014.5  235.73
  5024.5  242.56  5034.6  245.37  5094.9  243.25  5125.1   244.8  5195.5   242.8
  5235.7  245.66  5316.2  247.26  5406.2  253.58  5577.6  263.15  5607.8  260.21
  5627.9   264.7  5642.4  264.77  5678.2  267.95  5698.3  267.85  5757.7  272.19
#Mann= 7 ,-1 , 0
  4163.1     .11       0  4504.4     .17       0  4688.1     .11       0
  4822.6     .15       0  4969.6     .09       0  5034.6     .15       0
  5406.2     .17       0
#XS Ineff= 2 , 0
       0                  5245.8       0  245.95
Permanent Ineff=
       F       F
Bank Sta=4969.6,5034.6
XS Rating Curve= 0 ,0
Exp/Cntr=0.3,0.1

Type RM Length L Ch R = 1 ,12321   ,585,585,585
BEGIN DESCRIPTION:
CANEY CREEK NORTH TRIB NO 6 22.0
END DESCRIPTION:
XS GIS Cut Line= 3
      3759879.27     10174340.49      3760255.87     10173656.75
      3760323.73     10172861.34
#Sta/Elev= 30
  4219.4   267.9  4231.3  266.19  4335.3  261.57  4549.8  254.54  4638.4  250.36
  4719.8  249.06  4778.1  245.36  4872.3  244.31    4948  242.34  4953.7  240.87
  4960.8  242.45  4969.8  242.07  4975.5   237.8  4983.6  235.34  4991.5  235.15
  4994.8  230.36  5015.7  233.72  5035.8  242.67    5096  241.49  5176.3  243.18
  5195.6  240.71  5216.5  242.17  5246.6  240.21  5276.7  243.27  5388.5  248.14
  5547.7  253.87  5577.8  256.15  5597.8  255.88  5768.5  263.02  5798.3  263.16
#Mann= 5 ,-1 , 0
  4219.4     .17       0  4335.3     .15       0  4969.8     .09       0
  5035.8     .15       0  5388.5     .17       0
#XS Ineff= 2 , 0
       0  4872.3  244.31               0
Permanent Ineff=
       F       F
Bank Sta=4969.8,5035.8
XS Rating Curve= 0 ,0
Exp/Cntr=0.3,0.1

Type RM Length L Ch R = 1 ,11736   ,903,903,903
BEGIN DESCRIPTION:
CANEY CREEK NORTH TRIB NO 6 21.0
END DESCRIPTION:
XS GIS Cut Line= 3
      3760358.46     10174514.05      3760751.74     10173845.32
      3760775.12      10172847.4
#Sta/Elev= 30
  4224.2   272.2  4248.8     272  4276.1  270.28  4291.8  270.64  4343.7  267.94
    4366  268.41  4430.4  265.23  4459.7  265.23  4526.1  262.03  4553.4  259.58
  4590.5  258.19  4686.2  251.81  4846.4   246.9  4889.3  244.23  4926.4  240.43
    4985  239.22  4993.3  233.71  4997.5  232.11  5004.6  232.61  5024.3  240.53
  5254.3  239.03  5284.3  236.88  5304.3  236.98  5314.3  237.99  5394.4  239.18
  5534.4  246.03  5564.4  248.39  5674.4  251.74  5734.5     255  5998.2  263.25
#Mann= 3 , 0 , 0
  4224.2     .17       0    4985     .09       0  5024.3     .15       0
Bank Sta=4985,5024.3
XS Rating Curve= 0 ,0
Exp/Cntr=0.3,0.1

Type RM Length L Ch R = 1 ,10833   ,499,499,499
BEGIN DESCRIPTION:
CANEY CREEK NORTH TRIB NO 6 20.0
END DESCRIPTION:
XS GIS Cut Line= 3
      3761354.99     10174531.47      3761149.01     10173545.04
       3761177.9     10172889.08
#Sta/Elev= 30
  3992.3   266.2  4055.4  267.15  4176.6  262.35  4207.2  259.06    4289  252.99
  4295.2  251.58    4340  249.57  4345.2  248.19  4440.1  241.95  4486.6     240
    4575   238.2  4690.1  238.79    4718  237.54    4785  238.46    4810  237.43
  4840.6   238.9    4885  237.16  4963.2  238.43  4973.4  237.67  4979.9  230.89
    4985  233.15  4993.8  227.09  4997.2  226.48  5004.5  226.98    5034  238.01
  5224.9  247.93  5394.4  254.71  5504.5   260.8  5534.5  260.76  5656.6  266.24
#Mann= 5 ,-1 , 0
  3992.3     .17       0  4486.6     .15       0  4973.4     .09       0
    5034     .15       0  5224.9     .17       0
Bank Sta=4973.4,5034
XS Rating Curve= 0 ,0
Exp/Cntr=0.3,0.1

Type RM Length L Ch R = 1 ,10334   ,495,495,495
BEGIN DESCRIPTION:
CANEY CREEK NORTH TRIB NO 6 19.0
END DESCRIPTION:
XS GIS Cut Line= 3
      3761393.18     10174517.52       3761556.3     10173649.21
      3761445.26     10172916.88
#Sta/Elev= 30
  4116.5  266.39  4163.8  266.49  4265.5  263.36    4384  255.25  4448.7  252.38
  4611.5  238.86  4662.3  235.94  4687.1  235.81  4937.1  236.78  4947.2  235.91
  4957.4  233.52    4977  226.25  4982.1  228.04  4987.9  225.71  4994.2  224.82
  4998.8  224.82  5008.2  229.05  5023.2  232.65  5038.6  232.99  5048.7  234.99
  5068.9  236.91  5129.6  240.47  5149.8  240.73  5160.7     242  5200.4  242.67
  5273.8   245.9  5372.3   250.2  5382.5  251.35  5402.7  250.64  5740.7  265.32
#Mann= 5 ,-1 , 0
  4116.5     .17       0  4687.1     .15       0  4937.1     .09       0
  5068.9     .15       0  5273.8     .17       0
Bank Sta=4937.1,5068.9
XS Rating Curve= 0 ,0
Exp/Cntr=0.3,0.1