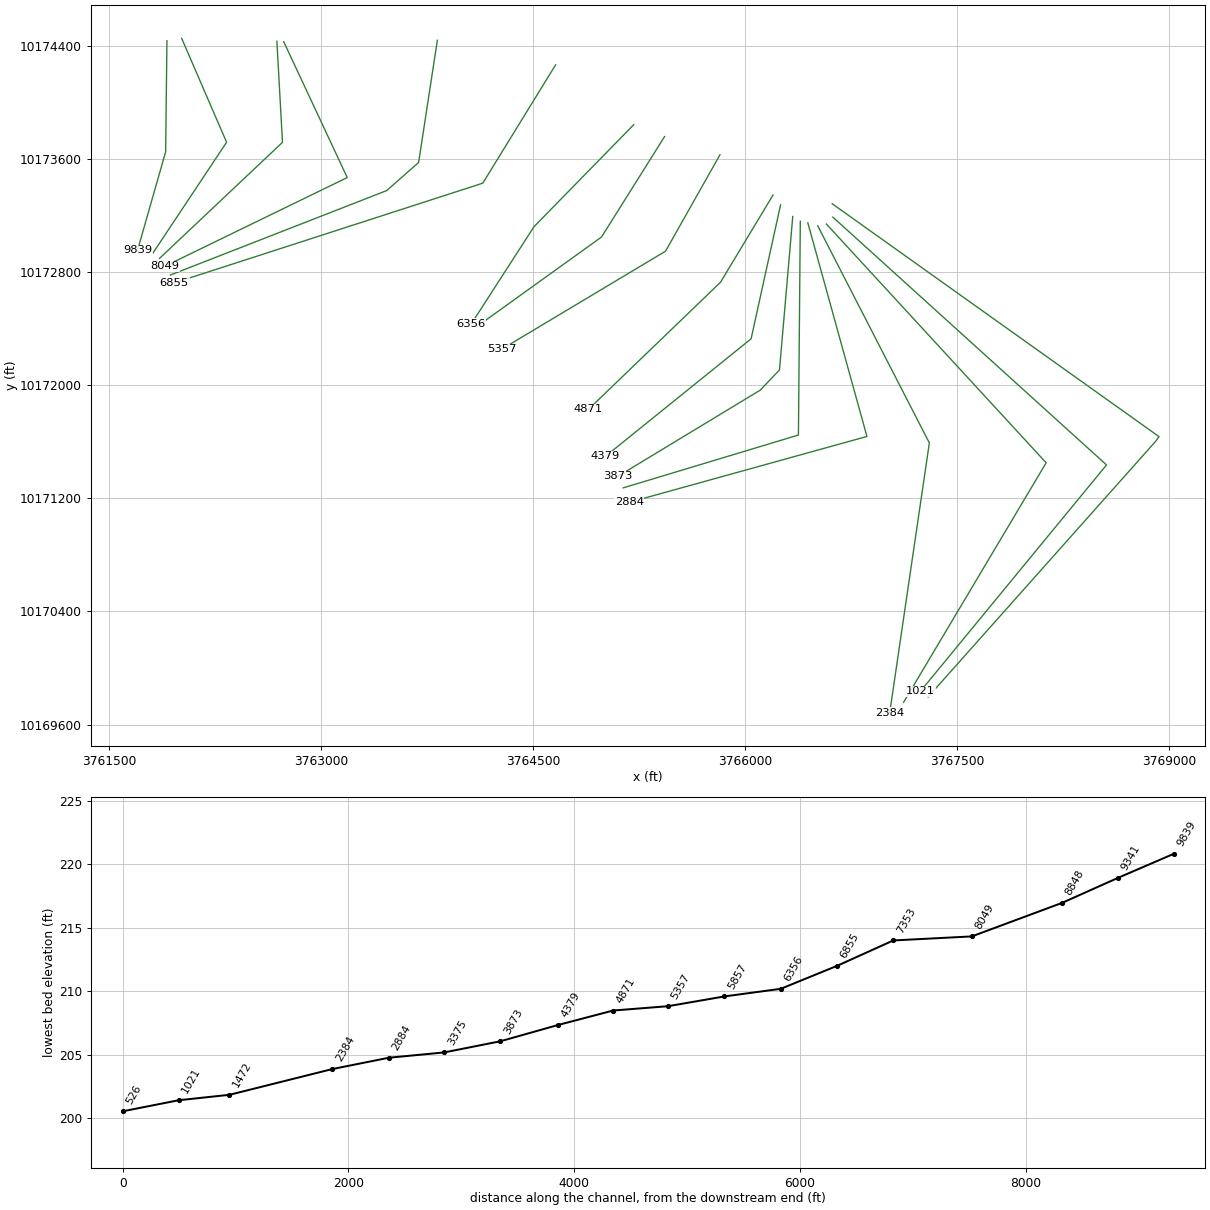
HEC-RAS study CANEY CREEK NORTH TRIB NO 6.prj: CANEY CREEK NORTH TRIB NO 6 Base Level Engineering

--- CANEY CREEK NORTH TRIB NO 6.g01 (geometry) --- (continued)

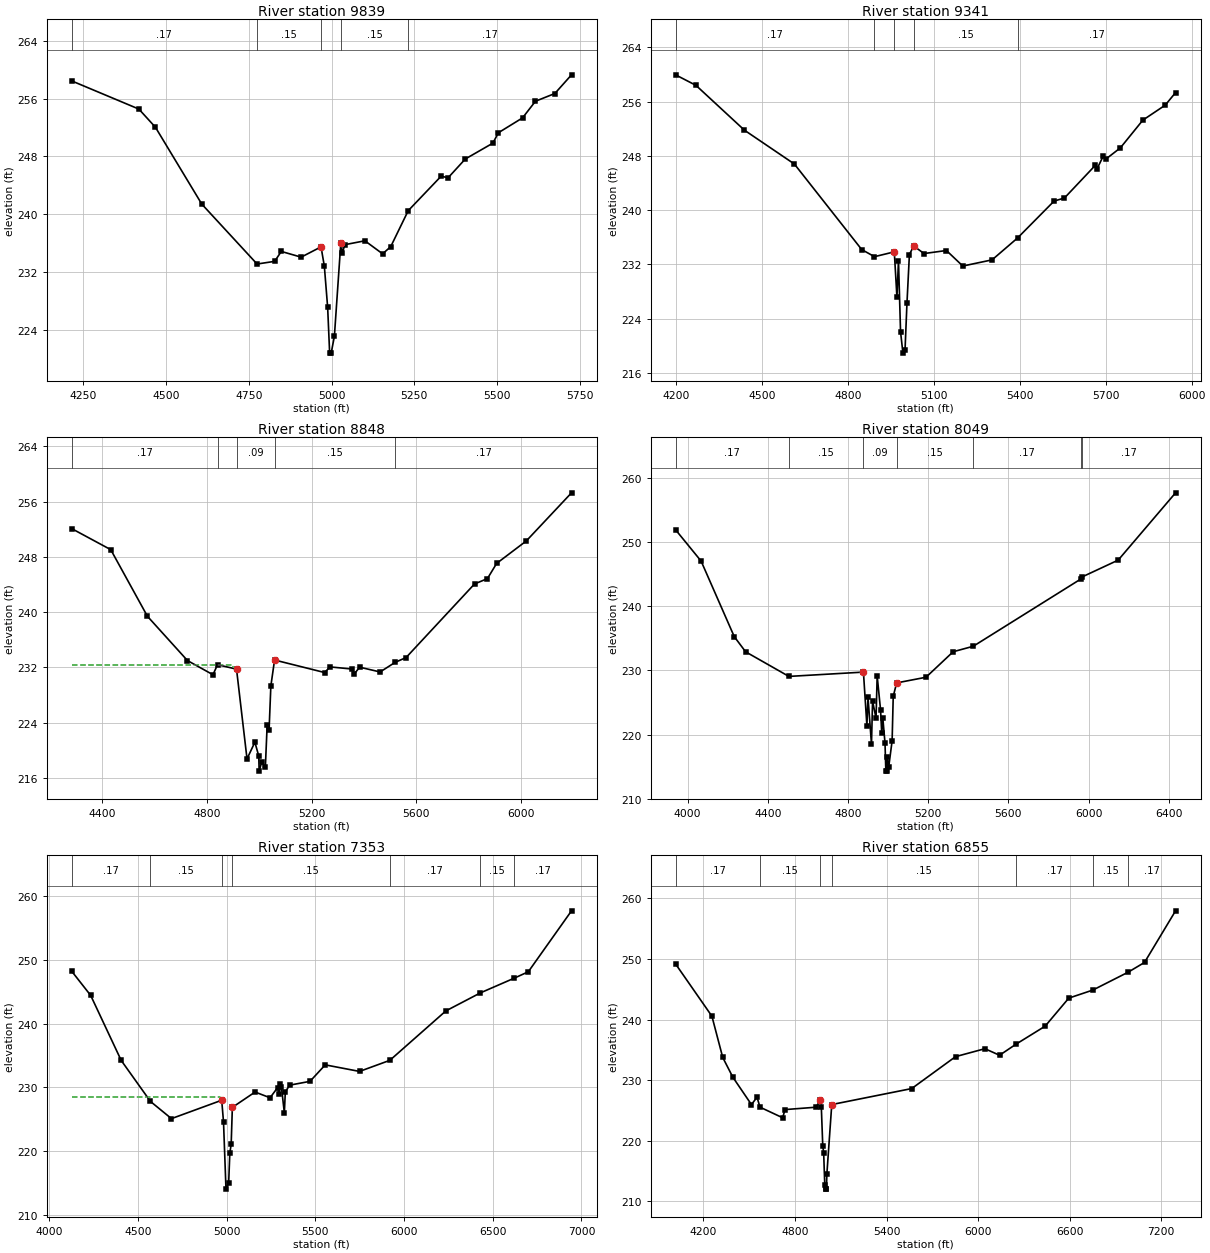
Type RM Length L Ch R = 1 ,9839    ,498,498,498
BEGIN DESCRIPTION:
CANEY CREEK NORTH TRIB NO 6 18.0
END DESCRIPTION:
XS GIS Cut Line= 3
      3761910.54     10174434.23      3761901.53     10173649.48
      3761702.54     10172952.74
#Sta/Elev= 30
  4215.2  258.45  4418.4  254.55  4468.4  252.04  4608.4  241.42  4775.3  233.14
  4828.4  233.51  4848.4  234.88  4908.4  234.09  4968.4  235.51  4978.4  232.84
  4988.4  227.14  4994.4  220.83    4999  220.83  5008.7  223.15    5028  235.98
  5033.2  234.67  5039.9  235.81  5100.8  236.35  5154.3  234.55  5178.8  235.54
  5231.6  240.51  5331.1  245.28  5351.9  245.05  5403.9  247.65  5487.1  249.84
  5503.9  251.28  5576.7  253.33  5615.7  255.63  5674.3   256.7  5724.6  259.28
#Mann= 5 ,-1 , 0
  4215.2     .17       0  4775.3     .15       0  4968.4     .09       0
    5028     .15       0  5231.6     .17       0
#XS Ineff= 2 , 0
       0  4968.4  235.51    5028       0  235.98
Permanent Ineff=
       F       F
Bank Sta=4968.4,5028
XS Rating Curve= 0 ,0
Exp/Cntr=0.3,0.1

Type RM Length L Ch R = 1 ,9341    ,493,493,493
BEGIN DESCRIPTION:
CANEY CREEK NORTH TRIB NO 6 17.0
END DESCRIPTION:
XS GIS Cut Line= 3
      3762014.72     10174451.54       3762332.6     10173716.64
      3761809.84     10172930.73
#Sta/Elev= 30
  4199.3  259.95  4270.4   258.4  4439.5  251.79  4613.8   246.8  4848.8  234.19
  4893.4  233.14  4962.5  233.85  4971.7  227.16  4977.1  232.57  4984.3  222.07
  4992.6  218.92    5000  219.42  5006.7  226.29  5015.2  233.46  5030.2  234.71
  5066.3   233.6  5144.4  234.05  5201.5  231.76  5303.7  232.67  5392.7   235.9
  5520.1  241.34  5556.2  241.79  5664.4  246.63  5670.4  246.13  5691.5  247.96
  5700.5  247.52  5751.3  249.18  5829.8  253.27  5907.9  255.48  5943.9  257.33
#Mann= 5 ,-1 , 0
  4199.3     .17       0  4893.4     .15       0  4962.5     .09       0
  5030.2     .15       0  5392.7     .17       0
#XS Ineff= 2 , 0
       0  4977.1  232.57               0
Permanent Ineff=
       F       F
Bank Sta=4962.5,5030.2
XS Rating Curve= 0 ,0
Exp/Cntr=0.3,0.1

Type RM Length L Ch R = 1 ,8848    ,799,799,799
BEGIN DESCRIPTION:
CANEY CREEK NORTH TRIB NO 6 16.0
END DESCRIPTION:
XS GIS Cut Line= 3
      3762688.32     10174430.72      3762728.14     10173716.19
       3761858.5     10172896.06
#Sta/Elev= 30
  4281.8  252.09  4431.7  249.03  4571.9  239.38  4724.9  232.97  4822.3  230.92
  4839.8  232.37  4912.4  231.73  4952.5  218.73  4982.5  221.15  4997.4  219.15
  4998.8  216.96  5008.4  218.23  5022.6  217.54  5029.5  223.64  5036.8  222.88
  5043.6  229.29  5057.8  233.05  5248.8  231.24  5270.2  232.05  5355.2  231.74
    5362  231.02  5383.1  232.01  5461.2  231.32    5519  232.72  5560.3   233.4
    5822  244.06  5871.4  244.84  5906.6  247.04  6019.9  250.29  6192.8  257.26
#Mann= 5 ,-1 , 0
  4281.8     .17       0  4839.8     .15       0  4912.4     .09       0
  5057.8     .15       0    5519     .17       0
#XS Ineff= 2 , 0
       0  4899.9  232.36  5057.8       0  233.05
Permanent Ineff=
       F       F
Bank Sta=4912.4,5057.8
XS Rating Curve= 0 ,0
Exp/Cntr=0.3,0.1

Type RM Length L Ch R = 1 ,8049    ,696,696,696
BEGIN DESCRIPTION:
CANEY CREEK NORTH TRIB NO 6 15.0
END DESCRIPTION:
XS GIS Cut Line= 3
      3762736.94     10174427.23      3763186.21     10173467.03
      3761896.67     10172840.47
#Sta/Elev= 30
  3939.9  251.88  4067.2  247.01  4232.6  235.25  4289.3  232.89  4505.1  229.06
  4876.9  229.73  4894.2  221.36  4899.7  225.82    4917  218.51  4922.5   225.2
  4939.8  222.56  4945.4  229.14  4962.4  223.82  4968.2  220.21  4973.7  222.54
  4984.5  218.67  4988.7  214.32  4993.4  214.32    4996  216.47    5003  214.97
    5020  219.05  5025.5  225.95  5042.5  228.05    5189  228.93  5324.4   232.9
  5424.6  233.75  5959.8  244.19  5967.4  244.54  6147.6  247.16  6433.7  257.63
#Mann= 7 ,-1 , 0
  3939.9     .17       0  4505.1     .15       0  4876.9     .09       0
  5042.5     .15       0  5424.6     .17       0  5959.8     .15       0
  5967.4     .17       0
#XS Ineff= 2 , 0
       0  4876.9  229.73               0
Permanent Ineff=
       F       F
Bank Sta=4876.9,5042.5
XS Rating Curve= 0 ,0
Exp/Cntr=0.3,0.1

Type RM Length L Ch R = 1 ,7353    ,498,498,498
BEGIN DESCRIPTION:
CANEY CREEK NORTH TRIB NO 6 14.0
END DESCRIPTION:
XS GIS Cut Line= 4
      3763823.73     10174437.64      3763691.29     10173573.84
      3763465.66     10173375.18      3761934.85     10172777.96
#Sta/Elev= 30
  4126.1  248.28  4233.9  244.45  4405.9  234.23  4570.9  227.78  4689.2  225.08
  4972.4  227.97  4982.6  224.54  4996.5     214  5011.5  214.92  5018.2   219.7
  5025.7  221.02  5032.4  226.85  5160.4  229.26  5244.9  228.36  5287.6  229.96
  5295.2  228.99  5299.9  230.59    5309  230.05  5325.4  225.99  5330.8  229.27
  5355.2  230.34    5470  230.94  5555.9  233.53  5749.1   232.5  5919.8  234.24
  6235.6  242.01  6430.7  244.85  6619.6  247.14  6700.2  248.16  6943.8  257.74
#Mann= 7 ,-1 , 0
  4126.1     .17       0  4570.9     .15       0  4972.4     .09       0
  5032.4     .15       0  5919.8     .17       0  6430.7     .15       0
  6619.6     .17       0
#XS Ineff= 2 , 0
       0  4962.3  228.54  5160.4       0  229.26
Permanent Ineff=
       F       F
Bank Sta=4972.4,5032.4
XS Rating Curve= 0 ,0
Exp/Cntr=0.3,0.1

Type RM Length L Ch R = 1 ,6855    ,499,499,499
BEGIN DESCRIPTION:
CANEY CREEK NORTH TRIB NO 6 13.0
END DESCRIPTION:
XS GIS Cut Line= 3
      3764660.56      10174264.1      3764145.14     10173427.41
      3761962.77     10172722.45
#Sta/Elev= 30
  4017.3  249.17  4255.3  240.55  4326.2  233.74  4392.5  230.48  4514.3  225.96
    4551  227.17  4570.4  225.53    4719  223.78  4734.4  225.13    4937  225.52
  4966.3  226.68  4972.2   225.6  4981.7  219.18  4987.6  218.03  4994.9  212.69
    5001     212  5005.8     212  5008.6  214.48  5040.7  225.96  5564.6   228.6
  5851.9  233.87  6044.1  235.18  6140.2   234.1  6248.3  235.93  6438.9   238.9
  6593.8  243.53  6751.4  244.86  6981.9   247.8    7090  249.42  7293.4  257.94
#Mann= 7 ,-1 , 0
  4017.3     .17       0  4570.4     .15       0  4966.3     .09       0
  5040.7     .15       0  6248.3     .17       0  6751.4     .15       0
  6981.9     .17       0
Bank Sta=4966.3,5040.7
XS Rating Curve= 0 ,0
Exp/Cntr=0.3,0.1

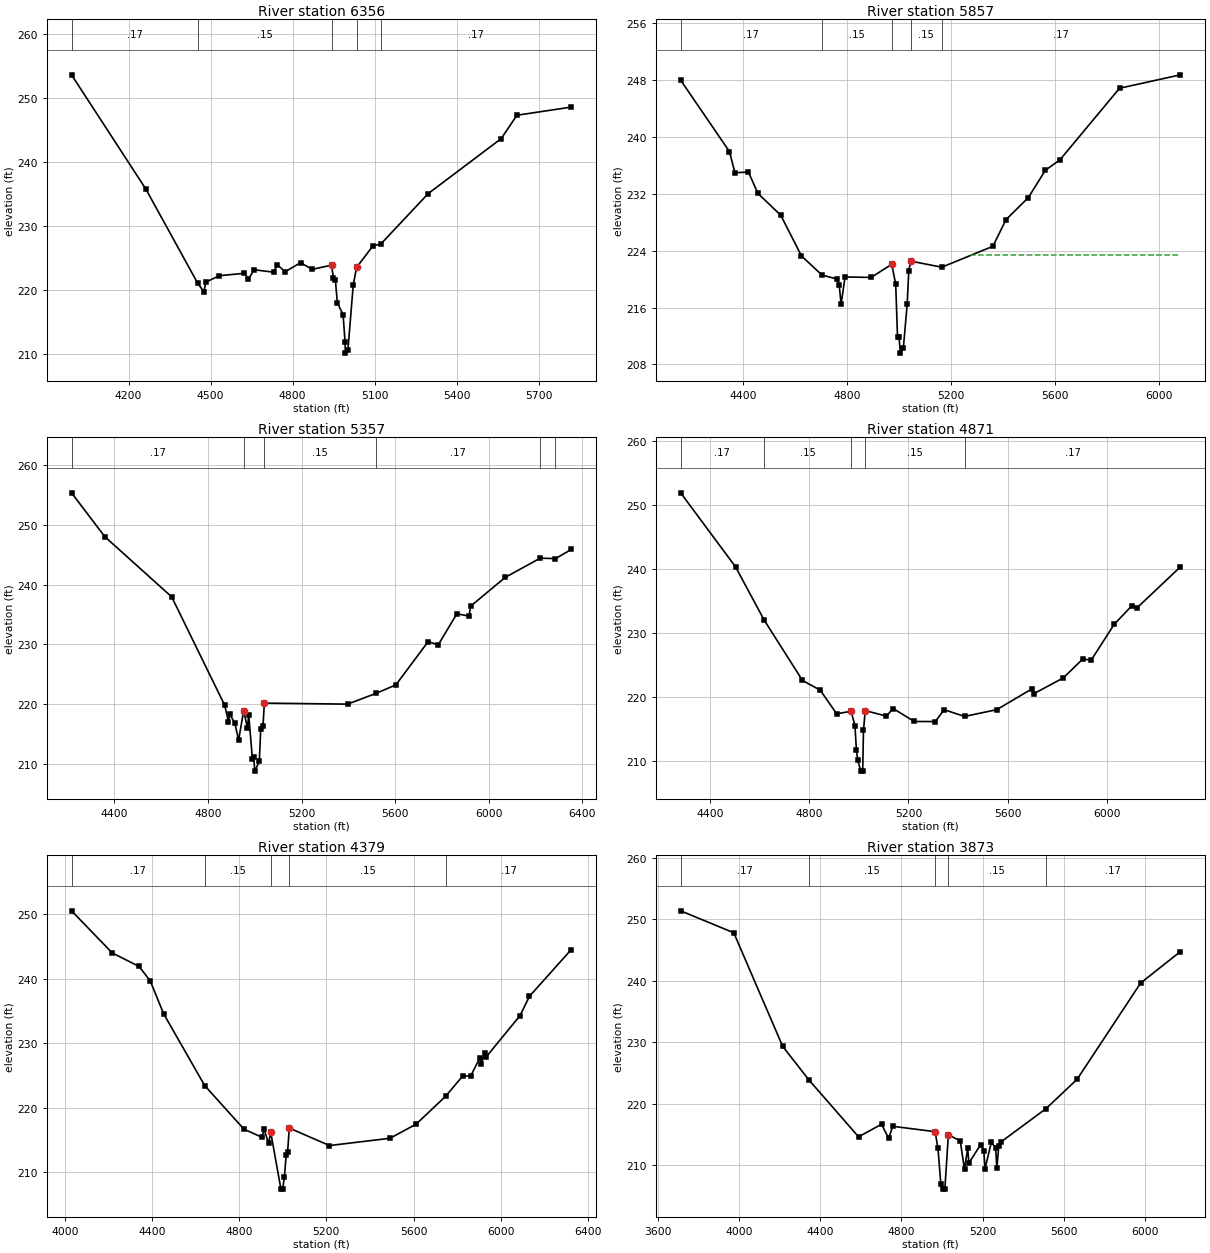
Type RM Length L Ch R = 1 ,6356    ,499,499,499
BEGIN DESCRIPTION:
CANEY CREEK NORTH TRIB NO 6 12.0
END DESCRIPTION:
XS GIS Cut Line= 3
      3765212.81     10173840.62      3764507.56     10173119.72
      3764063.21     10172431.62
#Sta/Elev= 30
  3991.5  253.65  4263.4   235.8  4452.4  221.14  4475.6  219.77  4482.6  221.28
  4532.1  222.28    4624  222.66  4638.2  221.75  4659.4  223.21  4730.2  222.83
  4744.3  223.99  4772.6   222.9  4829.2  224.31  4871.6  223.27  4942.2  223.93
  4949.3  221.92  4956.3  221.67  4963.5  218.06  4984.6  216.18  4991.8   211.9
  4992.7  210.19  5002.2  210.69  5021.7  220.85  5034.1  223.59  5093.6  226.93
  5122.8  227.24    5296  235.11  5562.8  243.69  5620.2  247.34  5819.1  248.61
#Mann= 5 ,-1 , 0
  3991.5     .17       0  4452.4     .15       0  4942.2     .09       0
  5034.1     .15       0  5122.8     .17       0
Bank Sta=4942.2,5034.1
XS Rating Curve= 0 ,0
Exp/Cntr=0.3,0.1

Type RM Length L Ch R = 1 ,5857    ,500,500,500
BEGIN DESCRIPTION:
CANEY CREEK NORTH TRIB NO 6 11.0
END DESCRIPTION:
XS GIS Cut Line= 3
      3765431.24     10173756.55      3764985.33      10173046.8
      3764107.37     10172416.47
#Sta/Elev= 30
  4161.8     248    4349  237.96  4370.2  234.98  4422.1  235.06  4458.6  232.06
  4546.2  228.99  4625.8  223.26  4704.4  220.58  4762.5  220.01  4770.6  219.19
  4777.8  216.48  4793.1  220.31  4893.2  220.24  4972.2  222.09  4987.5  219.32
  4994.5  211.89    5000  211.89  5005.7  209.59  5016.9  210.28  5031.6   216.5
  5037.8  221.21  5046.1  222.53  5164.5  221.68  5360.7  224.62    5411  228.37
    5497  231.48  5562.1  235.32  5618.5   236.8  5846.9  246.86  6080.8  248.75
#Mann= 5 ,-1 , 0
  4161.8     .17       0  4704.4     .15       0  4972.2     .09       0
  5046.1     .15       0  5164.5     .17       0
#XS Ineff= 2 , 0
       0                  5274.7       0   223.4
Permanent Ineff=
       F       F
Bank Sta=4972.2,5046.1
XS Rating Curve= 0 ,0
Exp/Cntr=0.3,0.1

Type RM Length L Ch R = 1 ,5357    ,486,486,486
BEGIN DESCRIPTION:
CANEY CREEK NORTH TRIB NO 6 10.0
END DESCRIPTION:
XS GIS Cut Line= 3
       3765823.5      10173628.6      3765438.44     10172946.83
      3764277.39     10172252.55
#Sta/Elev= 30
    4217  255.35  4359.2  248.02  4645.1  237.95  4871.8  219.81  4887.7   217.1
  4893.4  218.36  4915.1  216.79    4931  214.01  4952.6   218.9  4968.6   216.1
  4974.3  218.19  4990.2  210.78  4995.5  211.11  5000.2  208.82  5019.6  210.44
  5025.4  215.79  5035.1  216.29    5041  220.19  5396.9  220.02  5518.7  221.83
  5603.1  223.24  5741.2  230.48    5784  229.93  5863.8  235.13  5916.3  234.73
  5922.1  236.38    6070   241.2    6220  244.43  6285.1  244.35  6352.8  245.88
#Mann= 6 ,-1 , 0
    4217     .17       0  4952.6     .09       0    5041     .15       0
  5518.7     .17       0    6220     .11       0  6285.1     .17       0
Bank Sta=4952.6,5041
XS Rating Curve= 0 ,0
Exp/Cntr=0.3,0.1

Type RM Length L Ch R = 1 ,4871    ,492,492,492
BEGIN DESCRIPTION:
CANEY CREEK NORTH TRIB NO 6 9.0
END DESCRIPTION:
XS GIS Cut Line= 3
      3766198.56     10173343.58       3765827.6     10172727.67
      3764892.64     10171828.18
#Sta/Elev= 30
    4281  251.88  4502.6  240.33  4617.3  232.08  4772.5  222.62  4844.3   221.1
  4910.4  217.42  4968.6  217.81  4984.2  215.59    4990   211.8  4995.1  210.26
  5007.8  208.48  5015.5  208.48  5018.6  214.85  5025.8  217.92  5110.7  217.06
  5138.7  218.24  5223.6  216.22  5308.5  216.21    5344  218.06  5426.4  217.01
    5556  218.06  5697.5  221.29  5704.7  220.53  5824.9  223.02  5902.6  225.93
  5938.1  225.83  6029.9  231.36  6100.7  234.24    6122  233.93  6297.4  240.34
#Mann= 5 ,-1 , 0
    4281     .17       0  4617.3     .15       0  4968.6     .09       0
  5025.8     .15       0  5426.4     .17       0
Bank Sta=4968.6,5025.8
XS Rating Curve= 0 ,0
Exp/Cntr=0.3,0.1

Type RM Length L Ch R = 1 ,4379    ,506,506,506
BEGIN DESCRIPTION:
CANEY CREEK NORTH TRIB NO 6 8.0
END DESCRIPTION:
XS GIS Cut Line= 3
      3766251.98     10173273.81      3766043.41     10172327.32
      3765012.66     10171496.17
#Sta/Elev= 30
  4030.8  250.57  4217.9  244.02  4340.8  241.93    4392  239.68  4453.4  234.58
  4641.8  223.42  4822.1  216.64    4904   215.4  4914.5  216.66  4934.7  214.42
    4945  216.14  4991.7  207.33  4999.4  207.33  5007.8  209.23  5015.7  212.62
  5022.2  213.07  5030.1  216.82  5214.1   214.1  5492.4  215.23  5612.3  217.43
  5746.9  221.74  5826.6  224.94  5861.8  224.87    5905  227.75  5911.4  226.82
  5925.8  228.42  5932.2  227.82    6089   234.3  6132.1  237.29  6324.1  244.56
#Mann= 5 ,-1 , 0
  4030.8     .17       0  4641.8     .15       0    4945     .09       0
  5030.1     .15       0  5746.9     .17       0
Bank Sta=4945,5030.1
XS Rating Curve= 0 ,0
Exp/Cntr=0.3,0.1

Type RM Length L Ch R = 1 ,3873    ,498,498,498
BEGIN DESCRIPTION:
CANEY CREEK NORTH TRIB NO 6 7.0
END DESCRIPTION:
XS GIS Cut Line= 4
      3766338.22     10173191.59      3766244.25      10172106.9
      3766107.72     10171964.12      3765102.73     10171356.11
#Sta/Elev= 30
  3713.7  251.37  3975.2   247.8  4216.1   229.3  4346.2   223.8  4589.7  214.58
  4702.8  216.62    4738  214.31  4758.1  216.29  4966.6  215.41  4980.8  212.69
  4994.9  206.86  5006.8  206.06  5014.5  206.06    5032  214.91  5090.2  213.92
  5111.5  209.27    5127   212.7  5132.9   210.3  5191.1  213.32  5206.6  212.27
  5212.4  209.38  5243.4  213.67  5264.8  212.81  5270.6  209.42  5280.3   213.1
    5292  213.77  5512.2  219.15    5666  223.95  5978.6  239.61  6174.6  244.74
#Mann= 5 ,-1 , 0
  3713.7     .17       0  4346.2     .15       0  4966.6     .09       0
    5032     .15       0  5512.2     .17       0
Bank Sta=4966.6,5032
XS Rating Curve= 0 ,0
Exp/Cntr=0.3,0.1

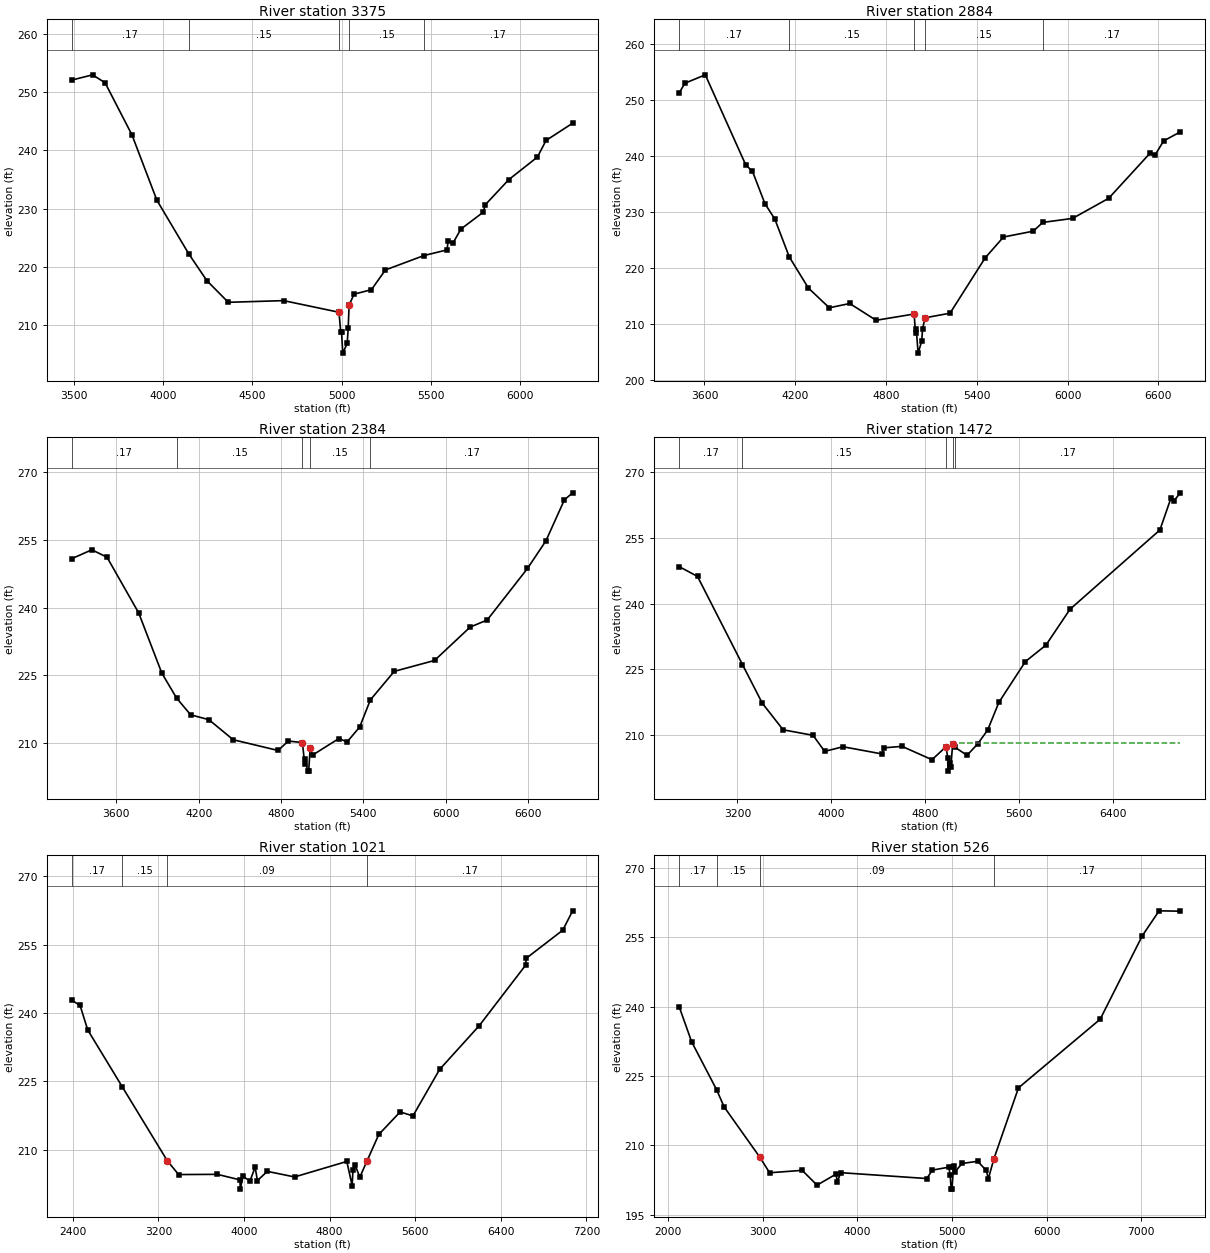
Type RM Length L Ch R = 1 ,3375    ,491,491,491
BEGIN DESCRIPTION:
CANEY CREEK NORTH TRIB NO 6 6.0
END DESCRIPTION:
XS GIS Cut Line= 3
      3766391.62     10173158.75       3766378.3      10171646.9
      3765138.84     10171273.45
#Sta/Elev= 30
  3488.1  252.08  3605.8  252.99  3675.8  251.62  3825.8   242.7  3965.8  231.45
    4144  222.25  4245.8  217.63  4365.8  213.91  4675.8   214.2  4985.8   212.2
  4995.4  208.86    5000  208.86  5006.9  205.18  5031.8  206.85  5037.3  209.44
  5042.5  213.44  5070.3  215.31  5167.6  216.08  5245.7  219.47  5461.3  221.94
  5591.4  222.92  5596.6  224.44  5624.4   224.1  5668.9   226.5  5794.2   229.4
    5805  230.66    5937  234.99  6097.1  238.86  6145.4  241.71  6294.5  244.68
#Mann= 5 ,-1 , 0
  3488.1     .17       0    4144     .15       0  4985.8     .09       0
  5042.5     .15       0  5461.3     .17       0
Bank Sta=4985.8,5042.5
XS Rating Curve= 0 ,0
Exp/Cntr=0.3,0.1

Type RM Length L Ch R = 1 ,2884    ,500,500,500
BEGIN DESCRIPTION:
CANEY CREEK NORTH TRIB NO 6 5.0
END DESCRIPTION:
XS GIS Cut Line= 3
      3766445.02     10173146.42      3766862.96      10171636.8
      3765181.34     10171171.16
#Sta/Elev= 30
  3433.6   251.3  3470.3     253  3605.2   254.5  3872.5  238.41  3917.2  237.24
  3999.5  231.47  4064.8  228.72  4160.1  221.97  4286.1  216.41  4424.9  212.86
  4559.8  213.63  4734.1  210.63  4985.2  211.75    4995  208.36  4999.8  208.99
  5011.6  204.76  5035.7   206.9  5040.9  209.01  5057.2  211.07  5222.8   211.9
  5454.5  221.77    5576  225.51  5773.1  226.56  5835.2  228.12  6032.6  228.84
  6271.2  232.43  6542.7  240.44    6577  240.14  6634.4  242.69  6744.9  244.31
#Mann= 5 ,-1 , 0
  3433.6     .17       0  4160.1     .15       0  4985.2     .09       0
  5057.2     .15       0  5835.2     .17       0
Bank Sta=4985.2,5057.2
XS Rating Curve= 0 ,0
Exp/Cntr=0.3,0.1

Type RM Length L Ch R = 1 ,2384    ,912,912,912
BEGIN DESCRIPTION:
CANEY CREEK NORTH TRIB NO 6 4.0
END DESCRIPTION:
XS GIS Cut Line= 3
      3766514.83     10173125.94      3767304.55     10171591.09
      3767024.33     10169684.97
#Sta/Elev= 30
  3273.9  250.77  3421.3  252.75  3532.1  251.11    3763  238.81  3931.6  225.52
  4039.2  220.01  4141.8  216.31  4274.8  215.23  4452.2   210.8  4779.2  208.43
  4853.8  210.52  4956.6  210.17  4973.2  205.49  4978.8  206.54  4994.1  203.87
  5002.2  203.87  5013.4  209.07  5030.3  207.41  5222.7  211.07  5282.3  210.32
    5374  213.61    5452   219.6    5626   225.9  5919.8  228.31    6179  235.67
  6303.9  237.25  6597.5  248.63    6732  254.74  6866.4  263.78  6926.6  265.33
#Mann= 5 ,-1 , 0
  3273.9     .17       0  4039.2     .15       0  4956.6     .09       0
  5013.4     .15       0    5452     .17       0
Bank Sta=4956.6,5013.4
XS Rating Curve= 0 ,0
Exp/Cntr=0.3,0.1

Type RM Length L Ch R = 1 ,1472    ,451,451,451
BEGIN DESCRIPTION:
CANEY CREEK NORTH TRIB NO 6 3.0
END DESCRIPTION:
XS GIS Cut Line= 3
      3766576.46     10173138.22      3768130.93     10171450.65
       3767122.8     10169757.91
#Sta/Elev= 30
  2705.6  248.38  2860.4  246.17  3243.3  226.09  3412.1  217.29  3589.1  211.25
  3843.8  209.99  3942.9  206.34  4098.9  207.39  4431.2  205.75  4445.4  207.14
  4601.3  207.48    4856  204.44  4976.2  207.41  4990.4  204.72  4991.7  201.84
  5010.6  203.78  5016.4  202.77    5032  207.95  5049.4  207.31  5154.6  205.44
  5243.9     208  5329.8  211.18  5425.3  217.48  5651.3  226.79  5825.9  230.52
  6030.8  238.69    6796  256.74  6891.4   264.1  6912.8  263.29  6970.2   265.2
#Mann= 5 ,-1 , 0
  2705.6     .17       0  3243.3     .15       0  4976.2     .09       0
    5032     .15       0  5049.4     .17       0
#XS Ineff= 2 , 0
       0                  5037.8       0  208.22
Permanent Ineff=
       F       F
Bank Sta=4976.2,5032
XS Rating Curve= 0 ,0
Exp/Cntr=0.3,0.1

Type RM Length L Ch R = 1 ,1021    ,495,495,495
BEGIN DESCRIPTION:
CANEY CREEK NORTH TRIB NO 6 2.0
END DESCRIPTION:
XS GIS Cut Line= 3
      3766621.66      10173187.5      3768558.04     10171435.56
      3767242.48      10169836.6
#Sta/Elev= 30
  2388.7  242.83  2468.3  241.64  2539.3  236.29  2862.6  223.81 3282.61  207.64
  3388.9   204.6  3749.8  204.65    3962  203.44  3964.7  201.41  3990.4  204.23
  4054.6  203.15  4103.9   206.2  4124.9  203.28  4217.5   205.3  4472.3  204.08
  4960.3  207.47  5010.2   202.2  5018.1  205.63  5038.9  206.63    5082  204.03
 5150.22  207.64  5259.2  213.38  5458.6  218.32  5578.4  217.45  5827.4  227.63
  6197.2   237.2  6630.2  250.44  6637.5  251.99  6978.1  258.14  7070.6  262.38
#Mann= 4 ,-1 , 0
  2388.7     .17       0  2862.6     .15       0 3282.61     .09       0
 5150.22     .17       0
Bank Sta=3282.61,5150.22
XS Rating Curve= 0 ,0
Exp/Cntr=0.3,0.1

Type RM Length L Ch R = 1 ,526     ,0,0,0
BEGIN DESCRIPTION:
CANEY CREEK NORTH TRIB NO 6 1.0
END DESCRIPTION:
XS GIS Cut Line= 4
      3766617.26     10173281.86      3768929.67      10171635.5
      3768902.75     10171599.21      3767295.87     10169795.46
#Sta/Elev= 30
  2116.2   239.9  2246.3  232.41  2510.7  222.03  2590.6  218.31 2967.54  207.45
  3071.4  204.08  3415.7   204.6    3573   201.4  3774.1  203.79    3787  202.07
  3823.2   204.1  4733.7  202.83  4792.8  204.65  4966.4  205.29    4981  203.69
  4990.9  200.54  5000.3  200.54  5016.2  205.43  5023.8  205.58  5030.5  204.28
  5108.2  206.09  5271.3  206.56  5363.2  204.58    5385  202.78 5443.18  207.08
  5703.5  222.44  6567.2  237.27  7013.7  255.35    7191  260.72  7415.7  260.64
#Mann= 4 ,-1 , 0
  2116.2     .17       0  2510.7     .15       0 2967.54     .09       0
 5443.18     .17       0
Bank Sta=2967.54,5443.18
XS Rating Curve= 0 ,0
Exp/Cntr=0.3,0.1

Chan Stop Cuts=-1
Use User Specified Reach Order=0
Composite Channel Slope=5