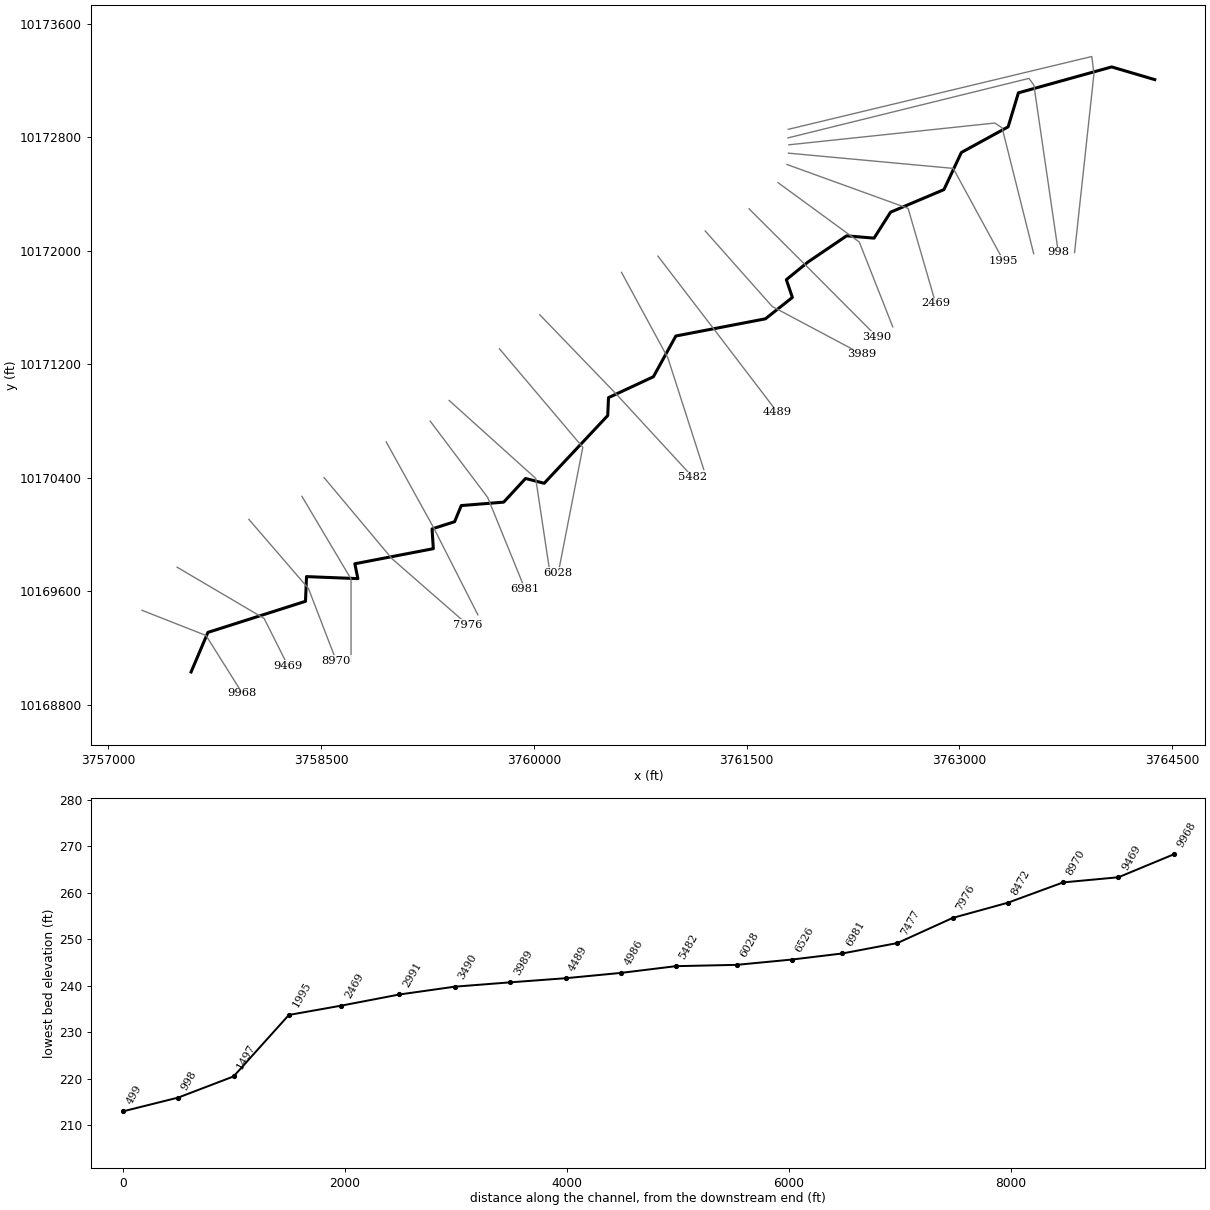
--- CANEY CREEK NORTH TRIB NO 6_1.prj (project) ---

Proj Title=CANEY CREEK NORTH TRIB NO 6_1 Base Level Engineering
Current Plan=p01
Default Exp/Contr=0.3,0.1
English Units
Geom File=g01
Flow File=f01
Flow File=f02
Plan File=p01
Y Axis Title=Elevation
X Axis Title(PF)=Main Channel Distance
X Axis Title(XS)=Station
BEGIN DESCRIPTION:
CANEY CREEK NORTH TRIB NO 6_1
END DESCRIPTION:
DSS Export Rating Curves= 0
DSS Export Rating Curve Sorted= 0
DSS Export Volume Flow Curves= 0
DXF OffsetX= 0
DXF OffsetY= 0
DXF ScaleX= 1
DXF ScaleY= 10

--- CANEY CREEK NORTH TRIB NO 6_1.p01 (plan) ---

Plan Title=Multiple Run
Short Identifier=Multiple
Geom File=g01
Flow File=f01
Subcritical Flow
K Sum by GR= 0
Std Step Tol= 0.01
Critical Tol= 0.01
Num of Std Step Trials= 20
Max Error Tol= 0.3
Flow Tol Ratio= 0.001
Split Flow NTrial= 30
Split Flow Tol= 0.02
Split Flow Ratio= 0.02
Log Output Level= 0
Friction Slope Method= 1
Unsteady Friction Slope Method= 2
Unsteady Bridges Friction Slope Method= 1
Parabolic Critical Depth
Global Vel Dist=  1 , 1 , 1
Global Log Level= 0
CheckData=True
Encroach Param= -1, 0, 0, 0
BEGIN DESCRIPTION:
Multiple Run
END DESCRIPTION:

--- CANEY CREEK NORTH TRIB NO 6_1.f01 (steady flow) ---

Flow Title=Multiple
Program Version=4.10
Number of Profiles= 7
Profile Names=10-year,25-year,50-year,1pct_min,100-year,1pct_plu,500-year
River Rch & RM=CANEY CREEK NORT,Reach-1         ,9968
     271     351     461     201     607    1833    1078
River Rch & RM=CANEY CREEK NORT,Reach-1         ,8970
     668     907    1227     547    1651    4986    3086
Boundary for River Rch & Prof#=CANEY CREEK NORT,Reach-1         , 1
Up Type= 0
Dn Type= 3
Dn Slope=0.008
Boundary for River Rch & Prof#=CANEY CREEK NORT,Reach-1         , 2
Up Type= 0
Dn Type= 3
Dn Slope=0.008
Boundary for River Rch & Prof#=CANEY CREEK NORT,Reach-1         , 3
Up Type= 0
Dn Type= 3
Dn Slope=0.008
Boundary for River Rch & Prof#=CANEY CREEK NORT,Reach-1         , 4
Up Type= 0
Dn Type= 3
Dn Slope=0.008
Boundary for River Rch & Prof#=CANEY CREEK NORT,Reach-1         , 5
Up Type= 0
Dn Type= 3
Dn Slope=0.008
Boundary for River Rch & Prof#=CANEY CREEK NORT,Reach-1         , 6
Up Type= 0
Dn Type= 3
Dn Slope=0.008
Boundary for River Rch & Prof#=CANEY CREEK NORT,Reach-1         , 7
Up Type= 0
Dn Type= 3
Dn Slope=0.008
DSS Import GetInterval= 0
DSS Import GetPeak= 0
DSS Import FillOption= 0

--- CANEY CREEK NORTH TRIB NO 6_1.f02 (steady flow) ---

Flow Title=Orig_BLE_Flow
Program Version=4.10
Number of Profiles= 7
Profile Names=10-year,25-year,50-year,1pct_min,100-year,1pct_plu,500-year
River Rch & RM=CANEY CREEK NORT,Reach-1         ,9968
     271     344     401     155     467    1409     627
River Rch & RM=CANEY CREEK NORT,Reach-1         ,8970
     668     889    1067     420    1270    3834    1794
Boundary for River Rch & Prof#=CANEY CREEK NORT,Reach-1         , 1
Up Type= 0
Dn Type= 3
Dn Slope=0.01
Boundary for River Rch & Prof#=CANEY CREEK NORT,Reach-1         , 2
Up Type= 0
Dn Type= 3
Dn Slope=0.01
Boundary for River Rch & Prof#=CANEY CREEK NORT,Reach-1         , 3
Up Type= 0
Dn Type= 3
Dn Slope=0.01
Boundary for River Rch & Prof#=CANEY CREEK NORT,Reach-1         , 4
Up Type= 0
Dn Type= 3
Dn Slope=0.01
Boundary for River Rch & Prof#=CANEY CREEK NORT,Reach-1         , 5
Up Type= 0
Dn Type= 3
Dn Slope=0.01
Boundary for River Rch & Prof#=CANEY CREEK NORT,Reach-1         , 6
Up Type= 0
Dn Type= 3
Dn Slope=0.01
Boundary for River Rch & Prof#=CANEY CREEK NORT,Reach-1         , 7
Up Type= 0
Dn Type= 3
Dn Slope=0.01
DSS Import GetInterval= 0
DSS Import GetPeak= 0
DSS Import FillOption= 0

--- CANEY CREEK NORTH TRIB NO 6_1.g01 (geometry) ---

Geom Title=Existing Conditions
Program Version=4.10

River Reach=CANEY CREEK NORT,Reach-1
Reach XY= 30
      3757583.23     10169031.84      3757701.74     10169310.64
      3758389.77     10169529.97      3758397.14     10169704.01
      3758759.24     10169689.65      3758737.81     10169794.46
      3759291.23     10169900.83      3759282.29     10170040.01
      3759441.21     10170090.83       3759488.2     10170204.66
      3759787.39     10170228.89      3759941.55     10170395.77
      3760072.85     10170361.77      3760520.88      10170839.1
      3760526.47     10170965.28      3760842.93     10171112.64
      3761001.27     10171399.82      3761633.08     10171520.99
      3761822.96     10171671.71      3761780.37     10171796.89
      3761934.24     10171922.27      3762205.52     10172105.88
      3762398.91     10172089.55      3762515.12     10172272.55
      3762891.71     10172431.62      3763014.53      10172693.3
      3763344.18     10172873.94      3763416.75     10173113.66
      3764074.37     10173296.34      3764378.23     10173206.84

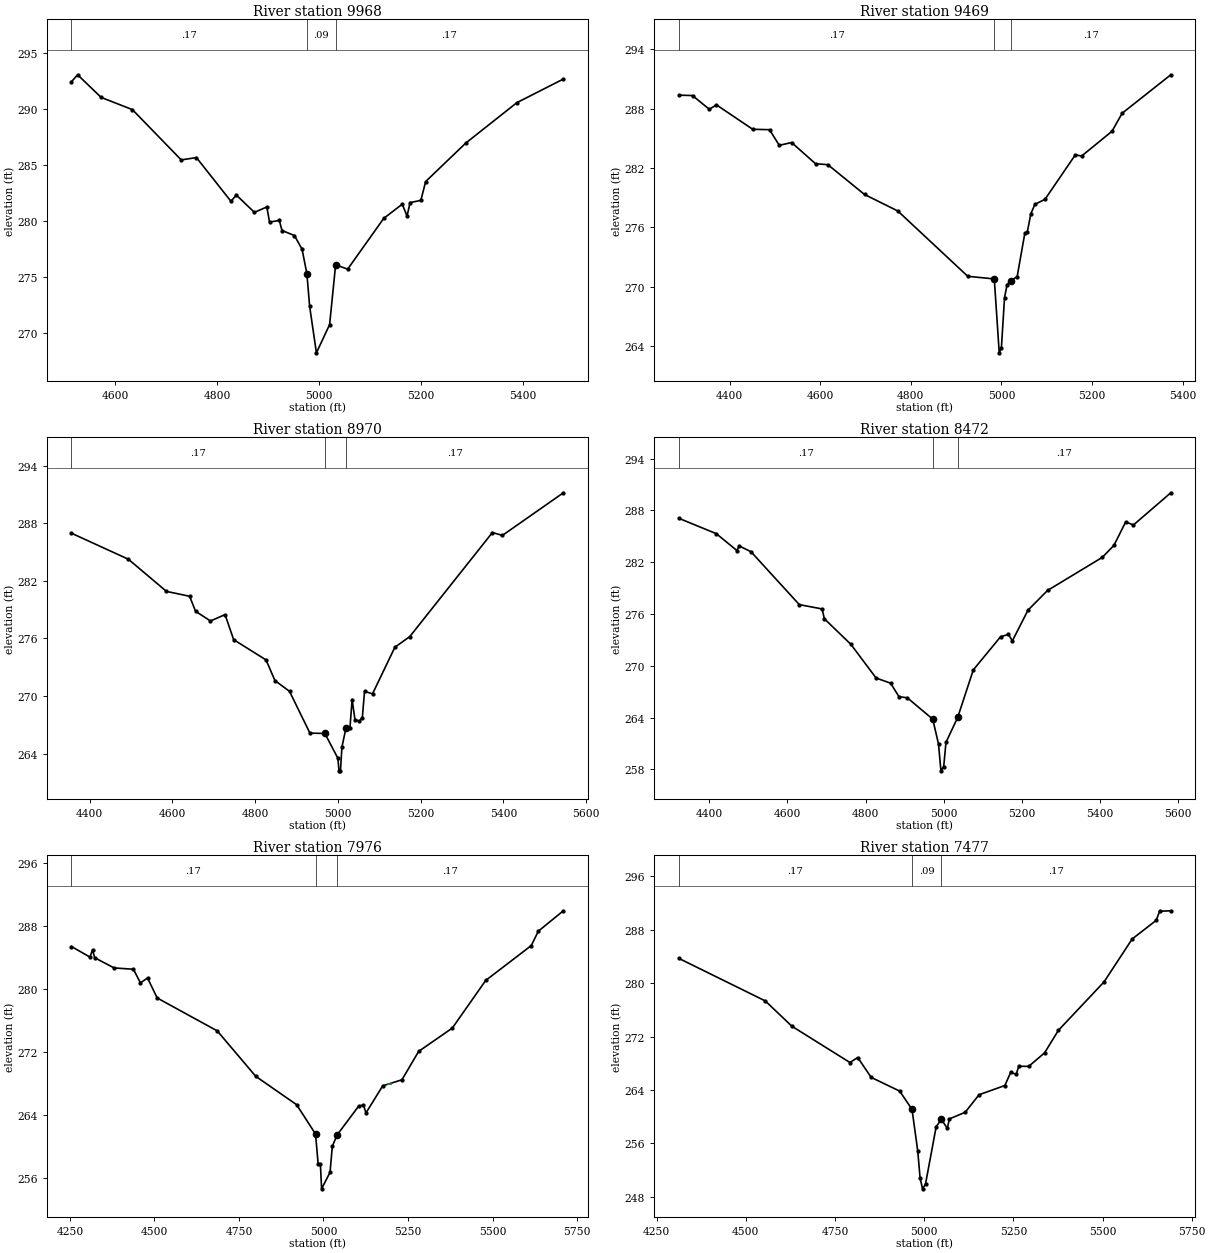
Type RM Length L Ch R = 1 ,9968    ,499,499,499
BEGIN DESCRIPTION:
CANEY CREEK NORTH TRIB NO 6_1 20.0
END DESCRIPTION:
XS GIS Cut Line= 3
      3757236.56      10169466.6       3757688.4     10169288.98
      3757943.74     10168882.53
#Sta/Elev= 30
  4514.5  292.45  4526.6  293.07  4572.8  291.05  4634.1  289.96    4730  285.47
  4759.8  285.68  4827.5  281.78  4838.2  282.33  4873.6  280.79    4898  281.27
  4903.3  279.92  4922.4  280.07  4927.8  279.17  4952.2  278.72  4967.2  277.49
  4976.6  275.31    4982   272.4  4995.3  268.25  5021.2  270.77    5033  276.11
  5056.6  275.72  5127.4  280.25  5163.8  281.52  5173.2  280.46  5179.1  281.66
  5200.3  281.86  5209.7  283.54  5288.6  286.98  5388.7  290.58    5480  292.69
#Mann= 3 , 0 , 0
  4514.5     .17       0  4976.6     .09       0    5033     .17       0
Bank Sta=4976.6,5033
XS Rating Curve= 0 ,0
Exp/Cntr=0.3,0.1

Type RM Length L Ch R = 1 ,9469    ,499,499,499
BEGIN DESCRIPTION:
CANEY CREEK NORTH TRIB NO 6_1 19.0
END DESCRIPTION:
XS GIS Cut Line= 3
      3757484.81     10169770.09      3758098.18     10169409.13
      3758266.04     10169075.14
#Sta/Elev= 30
  4288.3  289.36  4318.4  289.32  4355.5  287.93  4371.2  288.38  4451.2  285.91
  4488.3  285.87  4509.8  284.29  4537.1  284.57  4589.8  282.43  4617.1  282.33
  4697.9  279.32  4771.4  277.65  4925.7  271.05  4984.3  270.78  4995.2  263.31
    5000  263.81  5006.9   268.9  5012.5  270.19  5020.2  270.58  5034.8  271.02
  5051.6  275.38  5057.2  275.54    5065  277.37  5073.9  278.32  5096.2  278.83
  5163.2  283.33  5176.9   283.2  5244.1  285.71  5266.4  287.53  5373.8  291.42
#Mann= 3 , 0 , 0
  4288.3     .17       0  4984.3     .09       0  5020.2     .17       0
Bank Sta=4984.3,5020.2
XS Rating Curve= 0 ,0
Exp/Cntr=0.3,0.1

Type RM Length L Ch R = 1 ,8970    ,498,498,498
BEGIN DESCRIPTION:
CANEY CREEK NORTH TRIB NO 6_1 18.0
END DESCRIPTION:
XS GIS Cut Line= 3
      3757990.59     10170107.29      3758411.01     10169619.58
      3758606.74     10169111.05
#Sta/Elev= 30
  4356.1  286.95  4493.6  284.24  4585.7  280.89  4641.7  280.38    4656  278.82
  4692.1  277.81  4727.3  278.47  4748.1  275.86  4826.4  273.75  4847.9   271.6
  4883.1  270.48  4932.4  266.13  4968.6  266.09    5000  263.51  5002.7   262.2
  5006.2   262.2  5009.8  264.69  5019.8  266.71  5029.1  266.65  5034.4  269.61
  5041.3  267.54    5052  267.37  5059.1  267.75  5064.4  270.48  5083.7  270.22
  5137.7  275.07  5173.7  276.18  5373.4  287.02  5397.6  286.72  5544.9  291.16
#Mann= 3 , 0 , 0
  4356.1     .17       0  4968.6     .09       0  5019.8     .17       0
#XS Ineff= 2 , 0
       0                  5034.4       0  269.61
Permanent Ineff=
       F       F
Bank Sta=4968.6,5019.8
XS Rating Curve= 0 ,0
Exp/Cntr=0.3,0.1

Type RM Length L Ch R = 1 ,8472    ,496,496,496
BEGIN DESCRIPTION:
CANEY CREEK NORTH TRIB NO 6_1 17.0
END DESCRIPTION:
XS GIS Cut Line= 3
      3758364.58     10170269.74      3758710.97      10169686.9
      3758710.96      10169105.5
#Sta/Elev= 30
    4322  287.09  4417.9  285.31  4470.5  283.36  4476.3  283.89  4506.6  283.22
  4630.3  277.09  4688.7  276.59  4694.5  275.45  4762.5  272.48    4827  268.58
    4864  267.99  4885.4  266.43  4906.9  266.29  4971.9  263.82  4986.7  260.94
  4992.9  257.83    5000  258.33  5005.8  261.13  5035.8  264.02  5075.8  269.53
  5145.8  273.38  5165.8  273.63  5175.8  272.89  5215.8  276.45  5265.8  278.73
  5405.8  282.56  5435.8  283.95  5465.8  286.67  5485.8  286.32  5581.4  290.05
#Mann= 3 , 0 , 0
    4322     .17       0  4971.9     .09       0  5035.8     .17       0
Bank Sta=4971.9,5035.8
XS Rating Curve= 0 ,0
Exp/Cntr=0.3,0.1

Type RM Length L Ch R = 1 ,7976    ,499,499,499
BEGIN DESCRIPTION:
CANEY CREEK NORTH TRIB NO 6_1 16.0
END DESCRIPTION:
XS GIS Cut Line= 3
      3758520.91     10170401.55      3758999.73     10169830.16
      3759534.22     10169363.55
#Sta/Elev= 30
  4254.5  285.36    4309  284.02  4316.8  284.91  4323.3  283.93  4380.6  282.64
  4437.8  282.47  4458.6  280.74  4479.5  281.36  4508.1  278.82  4685.7  274.64
  4799.5  268.87  4920.5  265.26  4976.5  261.53  4984.3  257.67  4990.8  257.74
  4994.4  254.57  5019.4  256.67  5026.1  259.97  5040.3  261.42  5103.9  265.07
  5118.1  265.22  5125.7  264.22  5175.1  267.65  5232.1  268.43  5281.4  272.03
  5381.1     275  5479.8  281.05  5614.6  285.48  5635.5  287.31  5709.5   289.9
#Mann= 3 , 0 , 0
  4254.5     .17       0  4976.5     .09       0  5040.3     .17       0
#XS Ineff= 2 ,-1
  5118.1  5146.6  265.22  5189.3  5203.6  267.85
Permanent Ineff=
       F       F
Bank Sta=4976.5,5040.3
XS Rating Curve= 0 ,0
Exp/Cntr=0.3,0.1

Type RM Length L Ch R = 1 ,7477    ,496,496,496
BEGIN DESCRIPTION:
CANEY CREEK NORTH TRIB NO 6_1 15.0
END DESCRIPTION:
XS GIS Cut Line= 3
      3758959.23     10170652.95      3759292.02     10170051.02
      3759605.22     10169434.52
#Sta/Elev= 30
  4312.2  283.71  4554.3  277.34  4629.1  273.54  4791.8   268.1  4813.6  268.85
  4851.4  265.87  4931.4  263.81  4965.9  261.07  4981.9  254.86  4988.5   250.8
  4995.4  249.16  5003.7  249.87  5033.6  258.47  5048.2  259.58  5064.9  258.22
  5070.5  259.64    5115  260.64  5153.9  263.27  5226.2  264.65  5242.9  266.66
  5257.9  266.31  5265.2  267.54    5293  267.52  5337.5  269.54  5376.4  272.93
  5504.4  280.19  5583.2  286.62  5650.5  289.41  5660.1  290.78  5691.5  290.85
#Mann= 3 ,-1 , 0
  4312.2     .17       0  4965.9     .09       0  5048.2     .17       0
#XS Ineff= 2 , 0
       0                  5048.2       0  259.58
Permanent Ineff=
       F       F
Bank Sta=4965.9,5048.2
XS Rating Curve= 0 ,0
Exp/Cntr=0.3,0.1

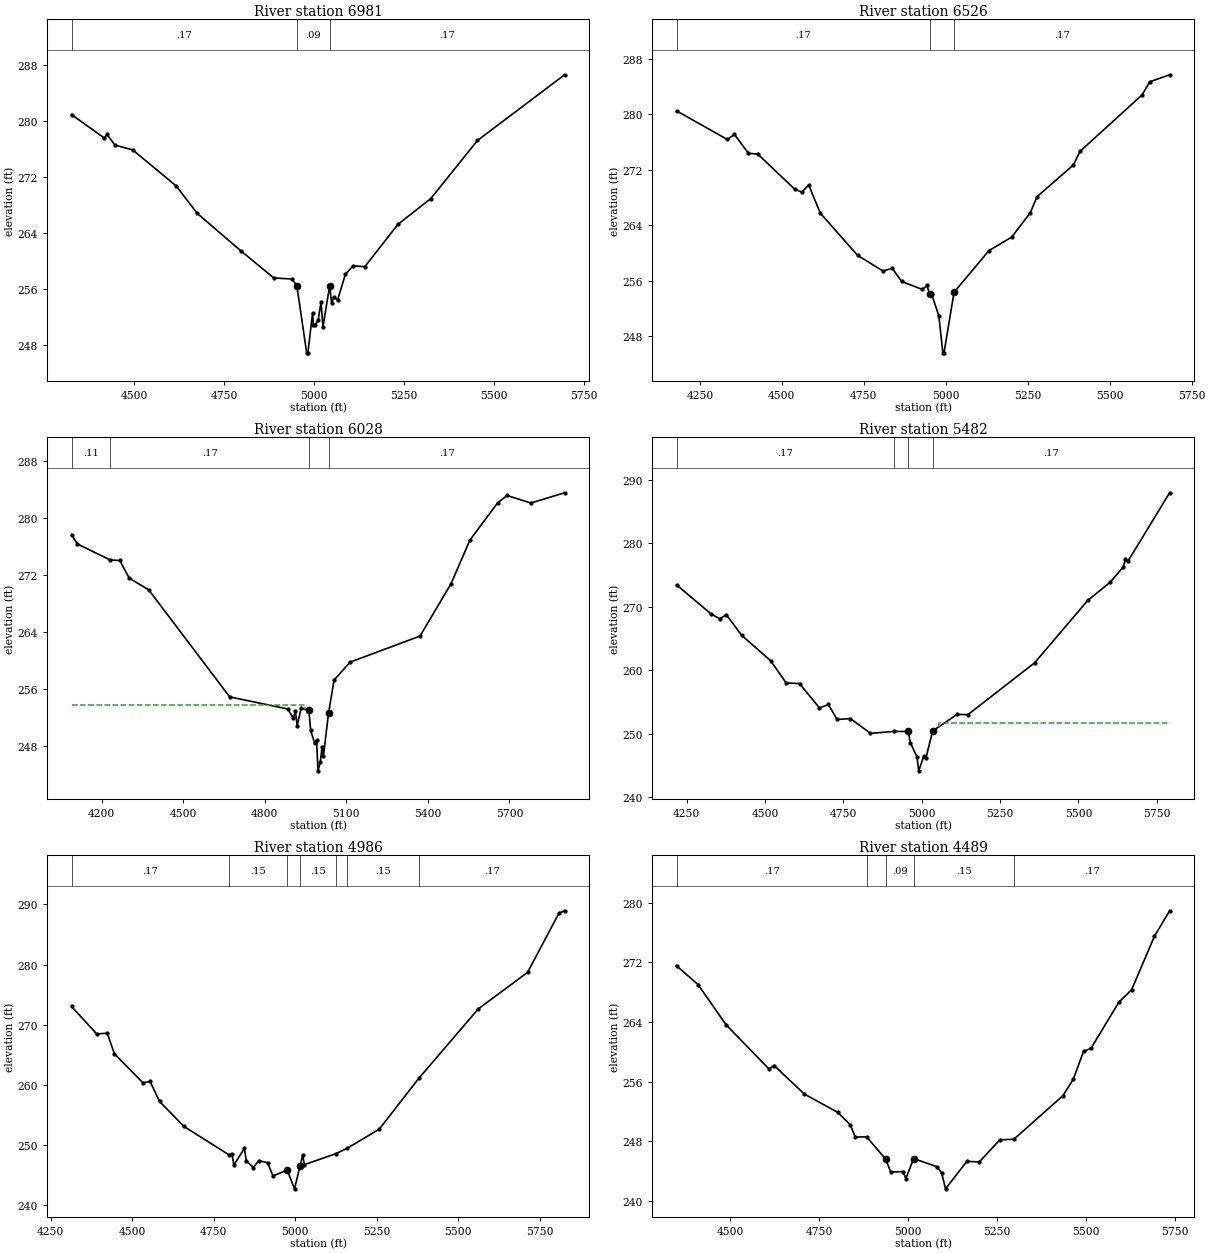
Type RM Length L Ch R = 1 ,6981    ,455,455,455
BEGIN DESCRIPTION:
CANEY CREEK NORTH TRIB NO 6_1 14.0
END DESCRIPTION:
XS GIS Cut Line= 3
      3759268.85     10170800.05      3759674.45       10170262.
       3759937.1     10169616.82
#Sta/Elev= 30
  4326.2  280.97  4417.4  277.62  4425.1  278.14  4446.5  276.62  4496.5  275.92
  4617.2  270.77  4675.5  266.86  4796.3  261.52  4888.5  257.62  4938.6  257.47
  4952.4  256.54  4979.8  246.92  4983.3  246.92  4996.1   252.6  4998.7  250.89
  5003.2  250.89  5011.8  251.64  5019.7  254.12  5025.1  250.67  5043.8  256.51
  5049.2  254.01    5055  254.84  5065.8  254.48  5087.4  258.14    5109  259.36
  5141.4  259.23  5233.8   265.3  5324.9  268.97  5454.5  277.27  5696.6  286.66
#Mann= 3 , 0 , 0
  4326.2     .17       0  4952.4     .09       0  5043.8     .17       0
#XS Ineff= 2 , 0
       0                  5043.8       0  256.51
Permanent Ineff=
       F       F
Bank Sta=4952.4,5043.8
XS Rating Curve= 0 ,0
Exp/Cntr=0.3,0.1

Type RM Length L Ch R = 1 ,6526    ,498,498,498
BEGIN DESCRIPTION:
CANEY CREEK NORTH TRIB NO 6_1 13.0
END DESCRIPTION:
XS GIS Cut Line= 3
      3759402.96      10170945.4      3760013.08      10170396.2
       3760114.9     10169721.04
#Sta/Elev= 30
  4179.1  280.46    4334  276.34  4355.7  277.07  4398.3  274.35  4426.7  274.24
  4539.5  269.18  4561.2  268.76  4582.1  269.79  4617.3  265.75  4730.9  259.66
  4808.6  257.39    4837  257.79  4865.4  255.89  4928.9  254.74  4943.1  255.31
  4950.6  254.03  4957.3  254.02    4979  250.93  4991.2  245.61  4994.7  245.61
  5025.4  254.34  5132.1  260.35    5201  262.27    5258   265.8  5278.2  268.09
  5389.5  272.68  5409.7  274.64  5599.4  282.79  5622.1  284.65  5682.8  285.66
#Mann= 3 , 0 , 0
  4179.1     .17       0  4950.6     .09       0  5025.4     .17       0
#XS Ineff= 2 , 0
       0    4837  257.79               0
Permanent Ineff=
       F       F
Bank Sta=4950.6,5025.4
XS Rating Curve= 0 ,0
Exp/Cntr=0.3,0.1

Type RM Length L Ch R = 1 ,6028    ,546,546,546
BEGIN DESCRIPTION:
CANEY CREEK NORTH TRIB NO 6_1 12.0
END DESCRIPTION:
XS GIS Cut Line= 3
      3759757.07     10171310.04      3760345.24     10170615.27
      3760172.01     10169729.25
#Sta/Elev= 30
  4089.7  277.69  4111.1  276.38  4232.2  274.12  4267.1  274.05  4302.2  271.56
  4373.6  269.92  4671.3  254.87  4884.5  253.17  4905.3  251.88  4913.1  252.82
  4919.6   250.8  4933.9  253.25  4962.5  253.02  4969.1  250.16  4983.3  248.42
  4991.1  248.75  4995.9  244.47  5004.7  245.65  5010.9  247.88    5016  246.53
  5034.8  252.57  5055.2  257.23    5114  259.75  5371.1  263.42  5484.9  270.75
  5554.5   276.9  5656.4  282.14    5691  283.19  5778.7  282.13  5902.8  283.57
#Mann= 4 ,-1 , 0
  4089.7     .11       0  4232.2     .17       0  4962.5     .09       0
  5034.8     .17       0
#XS Ineff= 2 , 0
       0  4948.2  253.71               0
Permanent Ineff=
       F       F
Bank Sta=4962.5,5034.8
XS Rating Curve= 0 ,0
Exp/Cntr=0.3,0.1

Type RM Length L Ch R = 1 ,5482    ,496,496,496
BEGIN DESCRIPTION:
CANEY CREEK NORTH TRIB NO 6_1 11.0
END DESCRIPTION:
XS GIS Cut Line= 3
       3760041.8     10171549.61      3760584.61     10170986.83
      3761120.58     10170404.95
#Sta/Elev= 30
  4218.1  273.45  4327.3  268.91  4355.6  268.11    4377  268.75  4426.3  265.49
  4518.4  261.51  4567.8  258.02  4610.3  257.92  4674.1  254.08  4702.3  254.63
  4730.4  252.27  4772.9  252.41  4836.7  250.09  4912.1  250.39  4956.8  250.38
    4964  248.64  4985.1  246.35  4990.6  244.19  5006.6  246.46  5013.4  246.15
    5035  250.46  5112.6  253.06  5147.8  253.04  5360.5  261.19    5530  271.01
  5600.9  273.83  5643.4  276.28  5650.2  277.49  5657.6  277.13  5791.1  287.94
#Mann= 4 ,-1 , 0
  4218.1     .17       0  4912.1     .15       0  4956.8     .09       0
    5035     .17       0
#XS Ineff= 2 , 0
       0                  5055.9       0  251.76
Permanent Ineff=
       F       F
Bank Sta=4956.8,5035
XS Rating Curve= 0 ,0
Exp/Cntr=0.3,0.1

Type RM Length L Ch R = 1 ,4986    ,497,497,497
BEGIN DESCRIPTION:
CANEY CREEK NORTH TRIB NO 6_1 10.0
END DESCRIPTION:
XS GIS Cut Line= 3
       3760618.2     10171848.21      3760945.05     10171245.42
      3761198.06     10170459.33
#Sta/Elev= 30
  4314.3  273.03  4391.7  268.47    4424  268.59  4445.9  265.17  4533.4  260.35
  4555.2  260.58  4584.1  257.26  4658.9  253.11  4797.3  248.38  4806.2  248.59
  4811.9  246.69  4844.3  249.46    4850   247.4  4871.8  246.27    4888  247.43
  4915.6  247.07  4931.7  244.89  4975.5  245.85  4997.9  242.74  5015.1  246.56
  5022.9  248.37  5028.1  246.76  5124.4  248.57  5158.5  249.45  5257.9  252.66
  5378.7  261.08  5561.3  272.63  5712.3  278.69  5808.5  288.52  5825.8  288.93
#Mann= 7 ,-1 , 0
  4314.3     .17       0  4797.3     .15       0  4975.5     .09       0
  5015.1     .15       0  5124.4     .17       0  5158.5     .15       0
  5378.7     .17       0
#XS Ineff= 2 , 0
       0  4844.3  249.46               0
Permanent Ineff=
       F       F
Bank Sta=4975.5,5015.1
XS Rating Curve= 0 ,0
Exp/Cntr=0.3,0.1

Type RM Length L Ch R = 1 ,4489    ,500,500,500
BEGIN DESCRIPTION:
CANEY CREEK NORTH TRIB NO 6_1 9.0
END DESCRIPTION:
XS GIS Cut Line= 3
      3760875.12     10171962.82      3761271.59     10171445.71
      3761717.85     10170861.07
#Sta/Elev= 30
  4348.4  271.54  4408.9  269.01  4487.7  263.62  4608.3  257.69  4622.8  258.15
    4708  254.32  4801.4  251.88  4836.7  250.23  4851.2  248.54  4882.9  248.59
  4936.4   245.6    4951  243.85  4986.3  243.92  4993.3  242.95  5015.3  245.66
  5079.8  244.59  5093.9  243.78  5105.1   241.6    5165  245.29  5200.3  245.21
  5257.4  248.17  5297.5  248.26  5435.2   254.1  5464.3  256.29  5493.3  260.05
  5514.2  260.46  5593.1  266.68  5628.5  268.31  5692.9  275.51  5735.5  278.92
#Mann= 5 ,-1 , 0
  4348.4     .17       0  4882.9     .15       0  4936.4     .09       0
  5015.3     .15       0  5297.5     .17       0
Bank Sta=4936.4,5015.3
XS Rating Curve= 0 ,0
Exp/Cntr=0.3,0.1

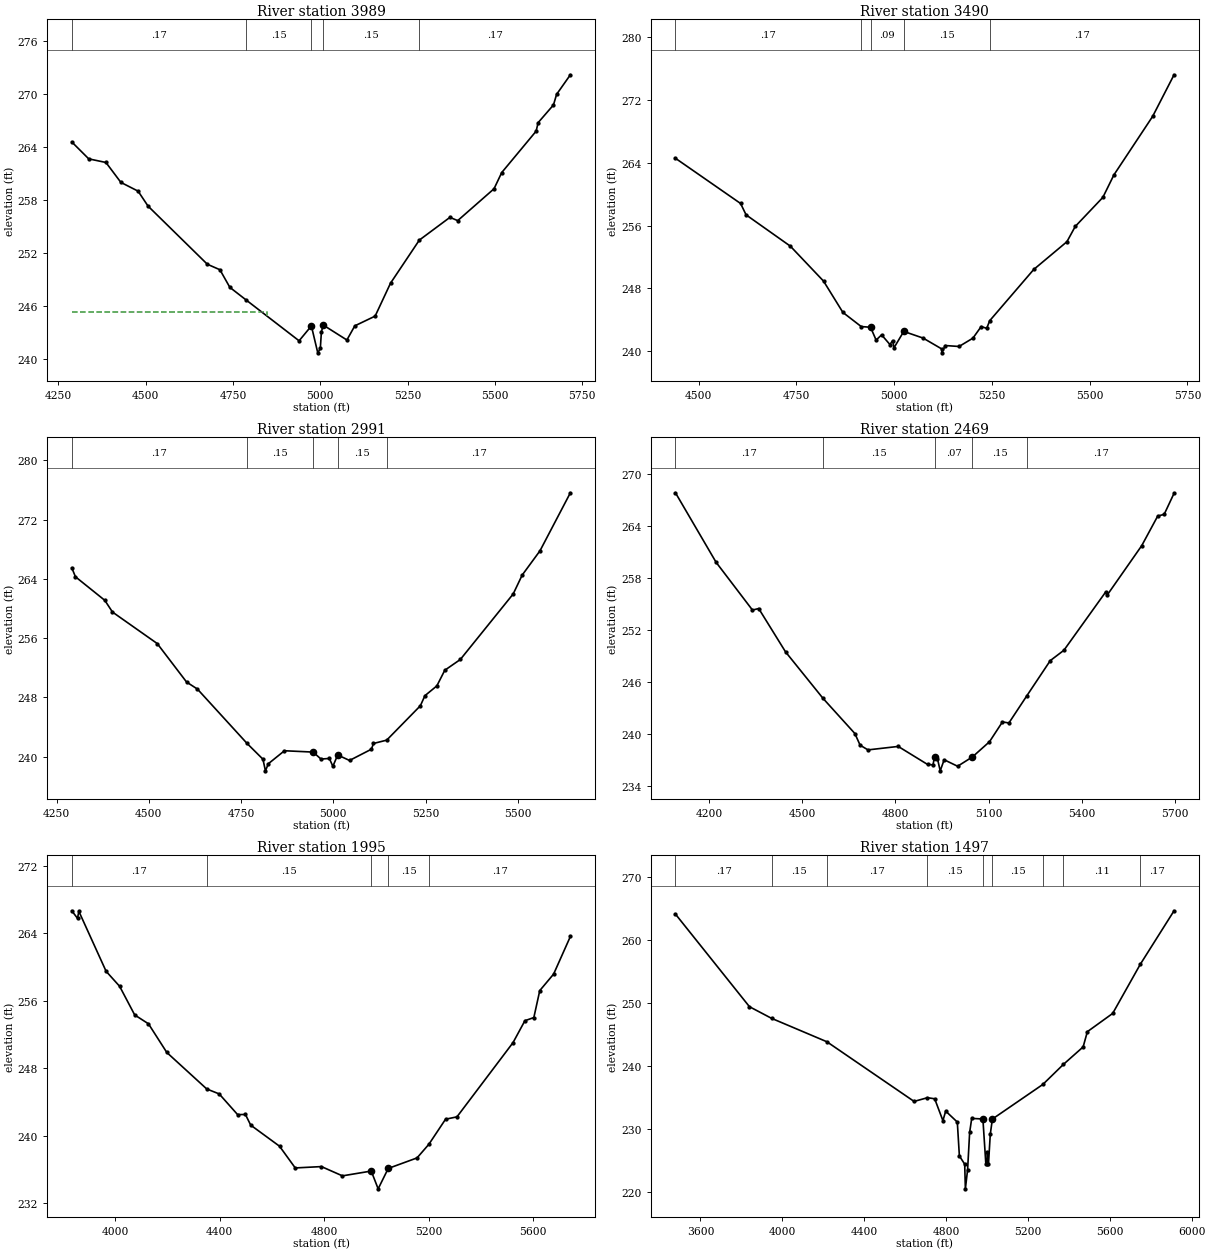
Type RM Length L Ch R = 1 ,3989    ,499,499,499
BEGIN DESCRIPTION:
CANEY CREEK NORTH TRIB NO 6_1 8.0
END DESCRIPTION:
XS GIS Cut Line= 3
      3761208.47     10172139.88      3761680.71     10171607.83
      3762312.64     10171271.83
#Sta/Elev= 30
  4288.6  264.54  4337.1  262.63  4386.4  262.22  4429.1  259.97  4478.4  258.98
  4506.9  257.29  4676.6  250.72  4712.6   250.1    4741  248.11  4786.7  246.71
  4939.2  242.07  4974.4  243.75  4992.7  240.71    5000  241.21  5003.1  243.11
  5008.7  243.84    5076  242.16  5098.7  243.76  5156.9  244.86  5200.9  248.58
  5283.4  253.45    5371  256.02  5393.2  255.65  5497.2  259.25  5519.2  261.08
  5617.7  265.76  5623.4  266.72  5667.3  268.72  5676.3  269.92  5715.7  272.13
#Mann= 5 ,-1 , 0
  4288.6     .17       0  4786.7     .15       0  4974.4     .09       0
  5008.7     .15       0  5283.4     .17       0
#XS Ineff= 2 , 0
       0  4847.2  245.31               0
Permanent Ineff=
       F       F
Bank Sta=4974.4,5008.7
XS Rating Curve= 0 ,0
Exp/Cntr=0.3,0.1

Type RM Length L Ch R = 1 ,3490    ,499,499,499
BEGIN DESCRIPTION:
CANEY CREEK NORTH TRIB NO 6_1 7.0
END DESCRIPTION:
XS GIS Cut Line= 3
      3761517.48     10172296.15      3761913.44     10171901.56
       3762418.9     10171394.73
#Sta/Elev= 30
    4441  264.57  4607.5  258.81  4621.6  257.36  4734.8  253.37  4819.6  248.92
  4869.1  244.93  4915.9  243.13  4939.8  243.04    4954  241.41  4968.1  242.07
  4989.3  240.84  4996.4  241.34  4999.6  240.41  5024.7  242.51  5074.2  241.66
  5121.7  240.28  5121.9  239.78  5130.7  240.71  5166.1  240.59  5201.5  241.65
  5222.7  243.13  5236.8   242.9  5244.4  243.87    5357   250.4  5441.9  253.94
  5463.1  255.88  5533.8  259.59  5562.1  262.46  5661.1  269.91  5715.8  275.21
#Mann= 5 ,-1 , 0
    4441     .17       0  4915.9     .15       0  4939.8     .09       0
  5024.7     .15       0  5244.4     .17       0
Bank Sta=4939.8,5024.7
XS Rating Curve= 0 ,0
Exp/Cntr=0.3,0.1

Type RM Length L Ch R = 1 ,2991    ,522,522,522
BEGIN DESCRIPTION:
CANEY CREEK NORTH TRIB NO 6_1 6.0
END DESCRIPTION:
XS GIS Cut Line= 3
      3761722.37     10172480.15      3762294.86     10172062.07
      3762530.74     10171464.44
#Sta/Elev= 30
  4291.1  265.49    4301  264.28  4380.6   261.1  4401.4  259.52  4522.7  255.27
  4602.2  250.08  4631.6  249.13  4766.3  241.79  4809.2  239.67    4816   238.1
  4823.9  239.06  4867.5  240.81  4945.2  240.63  4966.6  239.69  4989.2  239.77
  4998.8  238.71  5011.8  240.24  5043.9   239.5  5103.3  241.02  5108.7  241.79
  5144.6  242.24  5235.9  246.88  5248.3  248.24  5280.6  249.56  5302.1  251.67
  5344.2  253.12  5487.5  261.96  5511.9  264.51  5560.1  267.78  5642.5  275.61
#Mann= 5 ,-1 , 0
  4291.1     .17       0  4766.3     .15       0  4945.2     .07       0
  5011.8     .15       0  5144.6     .17       0
Bank Sta=4945.2,5011.8
XS Rating Curve= 0 ,0
Exp/Cntr=0.3,0.1

Type RM Length L Ch R = 1 ,2469    ,474,474,474
BEGIN DESCRIPTION:
CANEY CREEK NORTH TRIB NO 6_1 5.0
END DESCRIPTION:
XS GIS Cut Line= 3
      3761784.83     10172608.64      3762638.83     10172299.62
      3762833.16     10171630.56
#Sta/Elev= 30
  4091.8  267.83  4222.6   259.8  4339.7  254.28  4359.7  254.46    4446  249.46
  4566.8  244.08  4669.3  240.02  4686.2  238.67  4711.5  238.13  4808.8  238.53
  4903.2  236.45  4920.7   236.4    4926  237.35  4935.1  237.12    4944  235.71
  4956.7  236.99    5000  236.24  5047.8  237.32  5102.6  239.07  5144.3  241.36
  5165.1  241.24  5223.2   244.4  5298.2  248.44  5342.2  249.64  5476.4  256.36
  5481.6  256.02  5592.6  261.72  5644.1  265.14  5664.9  265.34  5696.7  267.77
#Mann= 5 ,-1 , 0
  4091.8     .17       0  4566.8     .15       0    4926     .07       0
  5047.8     .15       0  5223.2     .17       0
Bank Sta=4926,5047.8
XS Rating Curve= 0 ,0
Exp/Cntr=0.3,0.1

Type RM Length L Ch R = 1 ,1995    ,498,498,498
BEGIN DESCRIPTION:
CANEY CREEK NORTH TRIB NO 6_1 4.0
END DESCRIPTION:
XS GIS Cut Line= 3
      3761795.29     10172688.49      3762957.24     10172581.14
      3763312.64     10171928.08
#Sta/Elev= 30
  3833.1  266.69  3855.1  265.79  3860.1  266.63  3964.6  259.51  4016.4  257.73
  4074.2  254.33  4126.9  253.28  4197.2  249.88  4350.2  245.55    4398  244.96
  4468.4  242.51  4498.5  242.52  4518.6  241.26    4629  238.76  4689.3  236.18
  4789.7  236.34  4870.1  235.24  4980.5  235.81    5007   233.7  5045.6  236.12
    5156  237.37  5201.4  238.99  5265.2  241.96  5308.9  242.24  5523.8  251.05
  5569.3  253.65  5603.5  254.02  5626.2  257.22  5679.3  259.18  5743.5  263.64
#Mann= 5 ,-1 , 0
  3833.1     .17       0  4350.2     .15       0  4980.5     .07       0
  5045.6     .15       0  5201.4     .17       0
Bank Sta=4980.5,5045.6
XS Rating Curve= 0 ,0
Exp/Cntr=0.3,0.1

Type RM Length L Ch R = 1 ,1497    ,499,499,499
BEGIN DESCRIPTION:
Mapping XS 248e8cb9
END DESCRIPTION:
XS GIS Cut Line= 4
      3761798.39     10172747.33      3763250.62     10172900.94
      3763301.98     10172866.81      3763524.44     10171980.19
#Sta/Elev= 30
    3478  264.13  3839.5  249.42  3947.6  247.57  4217.8  243.85  4643.9  234.37
  4709.4  234.96  4744.5  234.79  4784.7  231.32  4798.4  232.83  4855.1  231.09
  4865.2  225.71  4891.2   224.4  4894.5  220.48  4905.4  223.54  4915.4  229.46
  4925.5  231.67  4980.1  231.58  4994.5  224.45    5000  224.45  5002.2  226.37
  5007.3  224.37  5016.2  229.16  5026.5  231.57  5273.1  237.07  5373.4  240.25
  5469.9  243.03  5490.5  245.45  5614.2  248.35    5749  256.15  5914.1  264.66
#Mann= 9 ,-1 , 0
    3478     .17       0  3947.6     .15       0  4217.8     .17       0
  4709.4     .15       0  4980.1     .07       0  5026.5     .15       0
  5273.1     .17       0  5373.4     .11       0    5749     .17       0
#XS Ineff= 2 , 0
       0  4925.5  231.67               0
Permanent Ineff=
       T       F
Bank Sta=4980.1,5026.5
XS Rating Curve= 0 ,0
Exp/Cntr=0.3,0.1

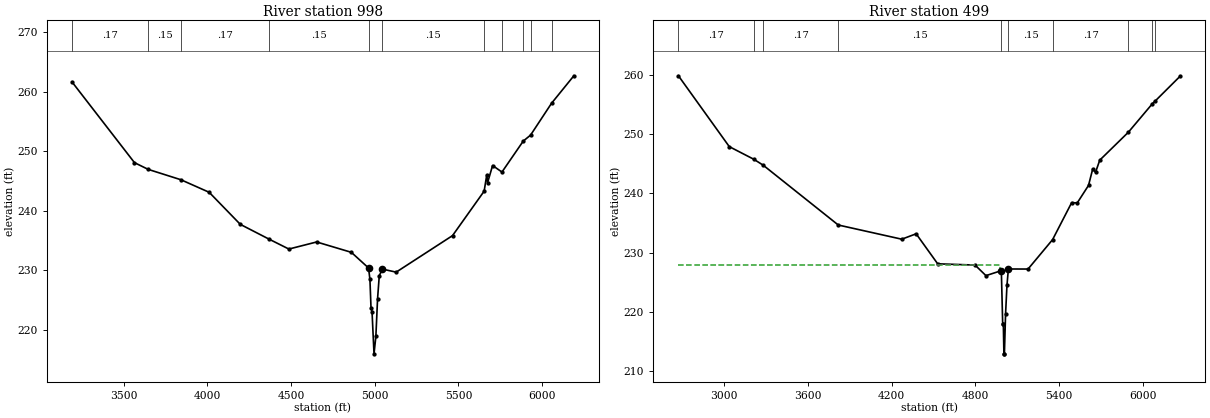
Type RM Length L Ch R = 1 ,998     ,499,499,499
BEGIN DESCRIPTION:
CANEY CREEK NORTH TRIB NO 6_1 2.0
END DESCRIPTION:
XS GIS Cut Line= 4
      3761791.82     10172796.13      3763491.07     10173215.49
      3763525.79     10173167.94      3763698.06     10171990.58
#Sta/Elev= 30
  3190.9  261.64  3564.5  248.06  3646.5  246.93  3841.7  245.19  4010.8  243.08
  4196.8  237.69  4368.4  235.21  4487.1  233.54    4653  234.73  4860.3  232.99
  4963.1  230.36  4971.4  228.44  4977.8  223.71    4984     223  4995.8  215.93
  5006.9  218.86  5017.1  225.21  5027.2  229.05  5045.6  230.17  5128.2  229.66
    5465   235.8  5653.9  243.27  5669.7  246.03  5674.7  244.72  5704.3  247.58
  5760.3  246.48  5887.4  251.68  5931.3  252.69  6056.6  258.04  6189.9  262.66
#Mann= 11 ,-1 , 0
  3190.9     .17       0  3646.5     .15       0  3841.7     .17       0
  4368.4     .15       0  4963.1     .07       0  5045.6     .15       0
  5653.9     .17       0  5760.3     .11       0  5887.4     .17       0
  5931.3     .11       0  6056.6     .17       0
Bank Sta=4963.1,5045.6
XS Rating Curve= 0 ,0
Exp/Cntr=0.3,0.1

Type RM Length L Ch R = 1 ,499     ,0,0,0
BEGIN DESCRIPTION:
Mapping XS 775d0776
END DESCRIPTION:
XS GIS Cut Line= 4
      3761793.97     10172856.48      3763934.16     10173369.74
      3763949.35     10173246.95      3763812.74     10171988.04
#Sta/Elev= 30
  2675.4  259.82  3039.3  247.88  3214.8  245.75    3282  244.75  3819.1  234.67
  4273.3  232.28  4376.2  233.19  4530.4  228.13  4797.8  227.92  4875.6  226.14
  4985.8  226.98  4995.4  218.01    5000  218.01  5004.2  212.96  5007.7  212.96
    5016  219.67    5026  224.49  5036.1  227.26  5176.9  227.25  5352.5  232.21
  5488.7  238.43    5529   238.4  5609.4  241.34  5639.6  244.13  5659.7  243.55
  5689.9   245.6    5895  250.32  6066.7  255.12  6085.8  255.55  6266.3  259.78
#Mann= 10 ,-1 , 0
  2675.4     .17       0  3214.8     .15       0    3282     .17       0
  3819.1     .15       0  4985.8     .07       0  5036.1     .15       0
  5352.5     .17       0    5895     .11       0  6066.7     .17       0
  6085.8     .11       0
#XS Ineff= 2 , 0
       0  4975.7  227.88  5036.1       0  227.26
Permanent Ineff=
       F       F
Bank Sta=4985.8,5036.1
XS Rating Curve= 0 ,0
Exp/Cntr=0.3,0.1

Chan Stop Cuts=-1
Use User Specified Reach Order=0
Composite Channel Slope=5