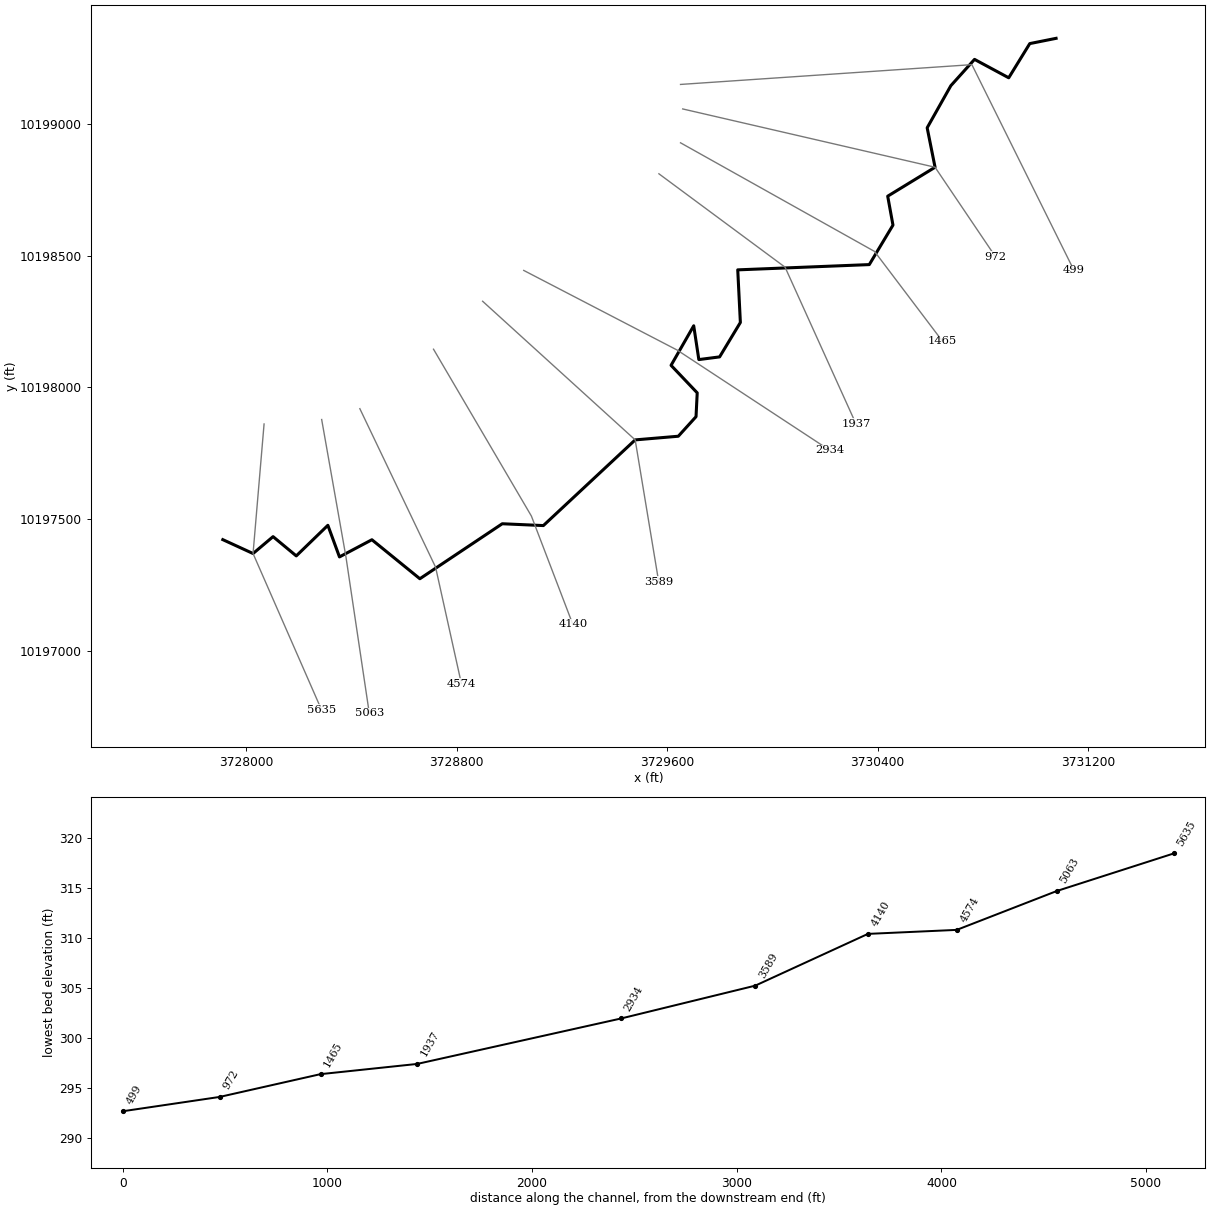
--- CANEY CREEK NORTH TRIB NO 7.prj (project) ---

Proj Title=CANEY CREEK NORTH TRIB NO 7 Base Level Engineering
Current Plan=p01
Default Exp/Contr=0.3,0.1
English Units
Geom File=g01
Flow File=f01
Flow File=f02
Plan File=p01
Y Axis Title=Elevation
X Axis Title(PF)=Main Channel Distance
X Axis Title(XS)=Station
BEGIN DESCRIPTION:
CANEY CREEK NORTH TRIB NO 7
END DESCRIPTION:
DSS Export Rating Curves= 0
DSS Export Rating Curve Sorted= 0
DSS Export Volume Flow Curves= 0
DXF OffsetX= 0
DXF OffsetY= 0
DXF ScaleX= 1
DXF ScaleY= 10

--- CANEY CREEK NORTH TRIB NO 7.p01 (plan) ---

Plan Title=Multiple Run
Short Identifier=Multiple
Geom File=g01
Flow File=f01
Subcritical Flow
K Sum by GR= 0
Std Step Tol= 0.01
Critical Tol= 0.01
Num of Std Step Trials= 20
Max Error Tol= 0.3
Flow Tol Ratio= 0.001
Split Flow NTrial= 30
Split Flow Tol= 0.02
Split Flow Ratio= 0.02
Log Output Level= 0
Friction Slope Method= 1
Unsteady Friction Slope Method= 2
Unsteady Bridges Friction Slope Method= 1
Parabolic Critical Depth
Global Vel Dist=  1 , 1 , 1
Global Log Level= 0
CheckData=True
Encroach Param= -1, 0, 0, 0
BEGIN DESCRIPTION:
Multiple Run
END DESCRIPTION:

--- CANEY CREEK NORTH TRIB NO 7.f01 (steady flow) ---

Flow Title=Multiple
Program Version=4.10
Number of Profiles= 7
Profile Names=10-year,25-year,50-year,1pct_min,100-year,1pct_plu,500-year
River Rch & RM=CANEY CREEK NORT,Reach-1         ,5635
     461     616     826     365    1101    3325    2024
River Rch & RM=CANEY CREEK NORT,Reach-1         ,3589
     562     759    1022     454    1370    4137    2546
Boundary for River Rch & Prof#=CANEY CREEK NORT,Reach-1         , 1
Up Type= 0
Dn Type= 3
Dn Slope=0.005
Boundary for River Rch & Prof#=CANEY CREEK NORT,Reach-1         , 2
Up Type= 0
Dn Type= 3
Dn Slope=0.005
Boundary for River Rch & Prof#=CANEY CREEK NORT,Reach-1         , 3
Up Type= 0
Dn Type= 3
Dn Slope=0.005
Boundary for River Rch & Prof#=CANEY CREEK NORT,Reach-1         , 4
Up Type= 0
Dn Type= 3
Dn Slope=0.005
Boundary for River Rch & Prof#=CANEY CREEK NORT,Reach-1         , 5
Up Type= 0
Dn Type= 3
Dn Slope=0.005
Boundary for River Rch & Prof#=CANEY CREEK NORT,Reach-1         , 6
Up Type= 0
Dn Type= 3
Dn Slope=0.005
Boundary for River Rch & Prof#=CANEY CREEK NORT,Reach-1         , 7
Up Type= 0
Dn Type= 3
Dn Slope=0.005
DSS Import GetInterval= 0
DSS Import GetPeak= 0
DSS Import FillOption= 0

--- CANEY CREEK NORTH TRIB NO 7.f02 (steady flow) ---

Flow Title=Orig_BLE_Flow
Program Version=4.10
Number of Profiles= 7
Profile Names=10-year,25-year,50-year,1pct_min,100-year,1pct_plu,500-year
River Rch & RM=CANEY CREEK NORT,Reach-1         ,5635
     461     604     718     281     847    2558    1177
River Rch & RM=CANEY CREEK NORT,Reach-1         ,3589
     562     744     889     349    1054    3184    1480
Boundary for River Rch & Prof#=CANEY CREEK NORT,Reach-1         , 1
Up Type= 0
Dn Type= 3
Dn Slope=0.005
Boundary for River Rch & Prof#=CANEY CREEK NORT,Reach-1         , 2
Up Type= 0
Dn Type= 3
Dn Slope=0.005
Boundary for River Rch & Prof#=CANEY CREEK NORT,Reach-1         , 3
Up Type= 0
Dn Type= 3
Dn Slope=0.005
Boundary for River Rch & Prof#=CANEY CREEK NORT,Reach-1         , 4
Up Type= 0
Dn Type= 3
Dn Slope=0.005
Boundary for River Rch & Prof#=CANEY CREEK NORT,Reach-1         , 5
Up Type= 0
Dn Type= 3
Dn Slope=0.005
Boundary for River Rch & Prof#=CANEY CREEK NORT,Reach-1         , 6
Up Type= 0
Dn Type= 3
Dn Slope=0.005
Boundary for River Rch & Prof#=CANEY CREEK NORT,Reach-1         , 7
Up Type= 0
Dn Type= 3
Dn Slope=0.005
DSS Import GetInterval= 0
DSS Import GetPeak= 0
DSS Import FillOption= 0

--- CANEY CREEK NORTH TRIB NO 7.g01 (geometry) ---

Geom Title=Existing Conditions
Program Version=4.10

River Reach=CANEY CREEK NORT,Reach-1
Reach XY= 30
      3727911.04      10197421.4      3728025.97     10197368.62
      3728102.01     10197432.85      3728190.21     10197359.59
      3728310.34     10197475.91      3728354.44     10197355.77
      3728477.71     10197421.05        3728660.     10197272.78
      3728973.19     10197481.81      3729129.44     10197474.87
      3729478.43     10197800.56      3729642.32     10197814.45
      3729709.68     10197888.76       3729714.2     10197979.38
      3729614.79     10198083.93       3729700.9     10198234.28
      3729720.34     10198105.81      3729799.34     10198116.05
      3729878.23     10198246.84      3729868.23     10198446.84
      3730368.23     10198466.84      3730458.23     10198616.84
      3730438.23     10198726.84      3730618.23     10198836.84
      3730588.23     10198986.84      3730678.23     10199146.84
      3730768.23     10199246.84      3730898.23     10199176.84
      3730978.23     10199306.84      3731078.23     10199326.84

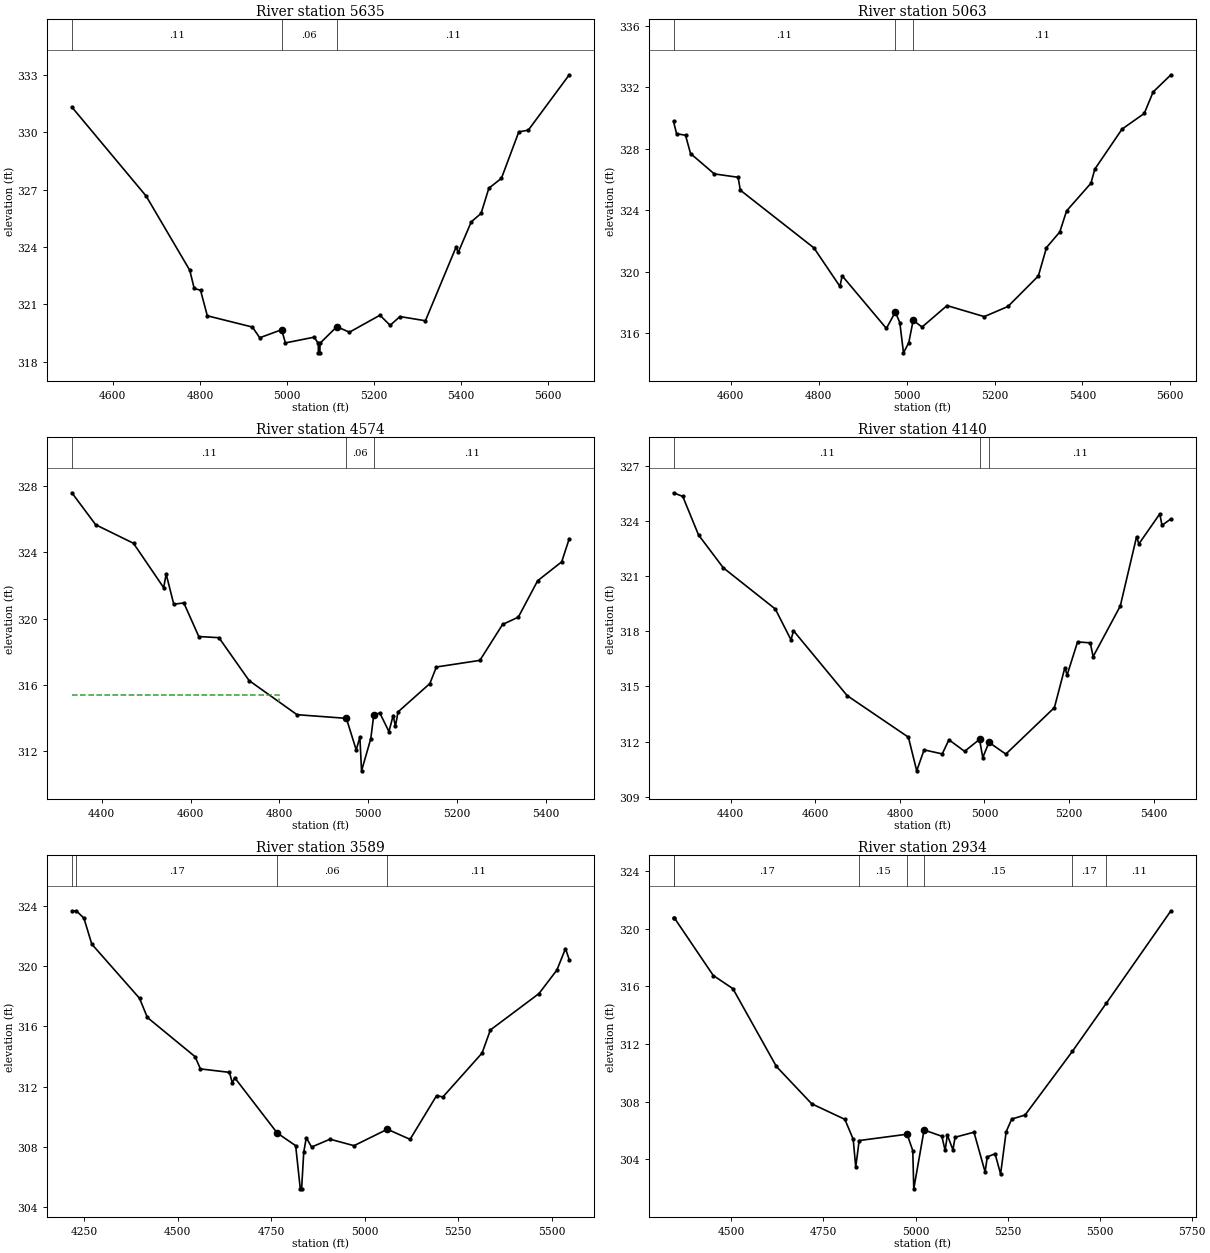
Type RM Length L Ch R = 1 ,5635    ,572,572,572
BEGIN DESCRIPTION:
CANEY CREEK NORTH TRIB NO 7 12.0
END DESCRIPTION:
XS GIS Cut Line= 3
      3728067.85     10197861.04      3728025.97     10197368.62
      3728286.05     10196774.88
#Sta/Elev= 30
  4505.8  331.33  4676.4  326.67  4776.7  322.78  4786.8  321.83  4801.3  321.74
  4816.9   320.4  4920.5  319.81  4937.3  319.25  4987.5  319.67  4996.3  318.98
  5062.2  319.28  5071.7  318.96    5072  318.46  5075.5  318.46  5075.7  318.96
  5114.4  319.83  5143.2  319.54  5213.4  320.43  5236.8   319.9  5259.3  320.36
  5317.8  320.14  5387.9  323.98  5393.4  323.73  5423.1  325.32  5445.6  325.76
  5463.5  327.08  5492.4   327.6  5532.3  330.03  5554.1  330.12  5648.2  333.02
#Mann= 3 , 0 , 0
  4505.8     .11       0  4987.5     .06       0  5114.4     .11       0
Bank Sta=4987.5,5114.4
XS Rating Curve= 0 ,0
Exp/Cntr=0.3,0.1

Type RM Length L Ch R = 1 ,5063    ,489,489,489
BEGIN DESCRIPTION:
CANEY CREEK NORTH TRIB NO 7 11.0
END DESCRIPTION:
XS GIS Cut Line= 3
      3728286.78     10197877.97      3728379.09     10197355.77
      3728467.85     10196761.06
#Sta/Elev= 30
  4469.7  329.78  4476.7  328.98    4497  328.88  4508.4  327.69  4562.5  326.36
  4616.6  326.14  4621.7   325.3  4789.1  321.54  4848.3  319.03  4853.4  319.72
    4954  316.29  4974.3  317.36  4984.5  316.67  4992.9   314.7  5004.9  315.36
  5014.9  316.82  5035.1  316.38  5091.9  317.78  5176.6  317.06  5230.5  317.72
  5299.7  319.71  5318.2  321.56  5348.5  322.58  5363.9  323.95  5419.3  325.75
  5428.1  326.67  5490.1  329.28  5540.6   330.3  5560.8   331.7  5601.3  332.82
#Mann= 3 , 0 , 0
  4469.7     .11       0  4974.3     .06       0  5014.9     .11       0
Bank Sta=4974.3,5014.9
XS Rating Curve= 0 ,0
Exp/Cntr=0.3,0.1

Type RM Length L Ch R = 1 ,4574    ,434,434,434
BEGIN DESCRIPTION:
CANEY CREEK NORTH TRIB NO 7 10.0
END DESCRIPTION:
XS GIS Cut Line= 3
      3728431.91     10197919.15      3728719.72     10197316.88
      3728817.77     10196874.42
#Sta/Elev= 30
  4332.5   327.6  4386.2  325.67  4471.4  324.55  4539.4  321.87    4545  322.69
  4562.1  320.87  4584.8  320.95  4618.5  318.92  4663.9  318.85  4731.9  316.26
  4839.8   314.2    4951  313.98  4973.2  312.07  4981.4  312.85  4985.2  310.81
    5006  312.75  5012.8   314.2  5026.4   314.3  5046.9  313.18  5056.4  314.15
  5061.5   313.5  5067.4  314.37  5139.1  316.08  5153.8  317.08  5251.8  317.48
    5303  319.65  5338.4  320.09    5382  322.29  5436.1  323.43  5453.2  324.83
#Mann= 3 , 0 , 0
  4332.5     .11       0    4951     .06       0  5012.8     .11       0
#XS Ineff= 2 , 0
       0    4800  315.39               0
Permanent Ineff=
       F       F
Bank Sta=4951,5012.8
XS Rating Curve= 0 ,0
Exp/Cntr=0.3,0.1

Type RM Length L Ch R = 1 ,4140    ,551,551,551
BEGIN DESCRIPTION:
CANEY CREEK NORTH TRIB NO 7 9.0
END DESCRIPTION:
XS GIS Cut Line= 3
      3728711.92     10198145.22      3729083.96     10197510.98
      3729241.45     10197099.17
#Sta/Elev= 30
  4264.7  325.53  4286.6  325.33  4323.8  323.24  4382.4  321.45  4505.4  319.21
  4542.6  317.53  4548.4  318.03  4675.3   314.5  4820.1  312.24  4839.8  310.41
  4857.2  311.55  4900.2  311.33  4915.9   312.1    4953  311.47  4988.3  312.12
    4996  311.13  5010.6  311.96  5050.5  311.32  5165.4  313.85  5190.1  316.02
  5195.4  315.62  5220.1  317.42  5250.2  317.37  5256.9  316.62  5321.1  319.37
  5359.7  323.14  5365.1  322.75  5414.5  324.38  5419.8  323.76  5440.9  324.11
#Mann= 3 , 0 , 0
  4264.7     .11       0  4988.3     .06       0  5010.6     .11       0
Bank Sta=4988.3,5010.6
XS Rating Curve= 0 ,0
Exp/Cntr=0.3,0.1

Type RM Length L Ch R = 1 ,3589    ,655,655,655
BEGIN DESCRIPTION:
CANEY CREEK NORTH TRIB NO 7 8.0
END DESCRIPTION:
XS GIS Cut Line= 3
      3728898.58     10198327.48      3729478.43     10197800.56
      3729567.86     10197261.02
#Sta/Elev= 30
  4216.5  323.63  4228.4  323.66  4248.8  323.17  4269.8  321.45  4397.5  317.86
  4418.4  316.59  4546.1  313.99  4560.3  313.18    4638  312.95  4645.5  312.26
  4652.2  312.59  4765.8  308.93  4815.1  308.09  4827.5  305.23    4831  305.23
  4836.7  307.65  4843.5  308.62  4857.7     308    4907  308.52  4971.2  308.09
  5060.3  309.18  5121.1  308.51  5192.1  311.41  5208.9  311.32  5313.7  314.23
  5335.9  315.76  5465.8  318.17  5513.8  319.73  5536.7  321.15  5546.9  320.42
#Mann= 4 ,-1 , 0
  4216.5     .11       0  4228.4     .17       0  4765.8     .06       0
  5060.3     .11       0
Bank Sta=4765.8,5060.3
XS Rating Curve= 0 ,0
Exp/Cntr=0.3,0.1

Type RM Length L Ch R = 1 ,2934    ,997,997,997
BEGIN DESCRIPTION:
CANEY CREEK NORTH TRIB NO 7 6.0
END DESCRIPTION:
XS GIS Cut Line= 3
      3729054.77     10198444.72      3729638.05     10198141.92
      3730217.86     10197761.07
#Sta/Elev= 30
  4342.8  320.77  4344.4  320.77  4450.8  316.75    4504  315.84  4622.2  310.44
  4718.1  307.85  4808.2  306.77  4830.8  305.39  4837.7  303.46    4847   305.3
  4977.2  305.74  4992.6   304.6  4995.3  301.95  5023.3  306.03  5071.5   305.6
  5080.5  304.61  5086.5  305.68  5101.6  304.66  5107.6  305.53  5158.8  305.88
    5189  303.12    5195  304.17  5216.1  304.38  5231.1  302.98  5246.2  305.91
  5261.3  306.79  5297.5  307.07  5426.1  311.49  5518.6  314.84  5693.7  321.24
#Mann= 7 ,-1 , 0
  4342.8     .11       0  4344.4     .17       0    4847     .15       0
  4977.2     .09       0  5023.3     .15       0  5426.1     .17       0
  5518.6     .11       0
Bank Sta=4977.2,5023.3
XS Rating Curve= 0 ,0
Exp/Cntr=0.3,0.1

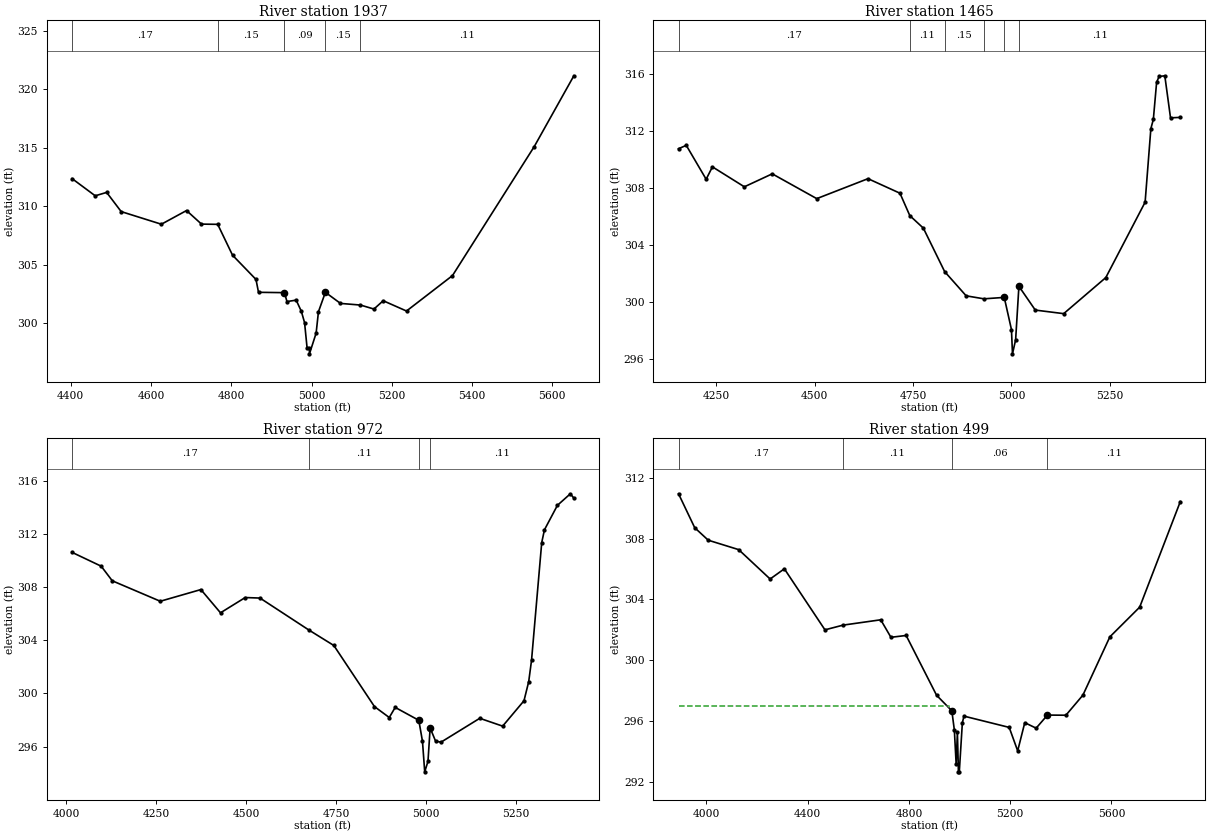
Type RM Length L Ch R = 1 ,1937    ,472,472,472
BEGIN DESCRIPTION:
CANEY CREEK NORTH TRIB NO 7 4.0
END DESCRIPTION:
XS GIS Cut Line= 3
       3729568.6     10198811.98      3730048.23     10198456.84
      3730317.83     10197861.11
#Sta/Elev= 30
  4403.2  312.38  4460.9  310.91  4489.4   311.2  4525.6  309.56  4625.8  308.48
  4688.5  309.65  4725.8  308.49  4766.2  308.47  4803.2  305.83  4861.6  303.76
  4867.9  302.66  4932.6  302.63  4938.8  301.87  4961.8  301.99  4974.6  301.04
  4982.7  300.07  4988.9  297.93  4994.7   297.9  4994.9   297.4  5011.5  299.17
  5017.3     301  5034.6  302.66  5072.2  301.71  5122.1  301.57  5155.6  301.23
  5178.7  301.94  5236.8  301.06  5351.4  304.09  5555.2  315.12  5653.9  321.17
#Mann= 5 ,-1 , 0
  4403.2     .17       0  4766.2     .15       0  4932.6     .09       0
  5034.6     .15       0  5122.1     .11       0
Bank Sta=4932.6,5034.6
XS Rating Curve= 0 ,0
Exp/Cntr=0.3,0.1

Type RM Length L Ch R = 1 ,1465    ,493,493,493
BEGIN DESCRIPTION:
CANEY CREEK NORTH TRIB NO 7 3.0
END DESCRIPTION:
XS GIS Cut Line= 3
      3729650.76     10198929.76      3730388.23     10198516.84
      3730646.87     10198174.95
#Sta/Elev= 30
  4154.8  310.77  4174.4  311.01  4224.9  308.63  4240.8   309.5  4321.9   308.1
  4392.7  309.01  4505.7  307.27  4635.8  308.67  4716.9  307.65  4741.9  306.08
  4776.3   305.2  4830.4  302.15    4885  300.45  4930.1  300.24  4981.7  300.34
    5000  298.08  5002.6  296.38  5010.6  297.37  5018.9  301.12  5060.5  299.45
  5132.6   299.2  5239.5  301.73  5339.3  307.02  5353.9  312.18  5360.2  312.83
  5368.5  315.43  5374.7  315.84  5389.3  315.89  5403.8  312.94  5428.7  312.97
#Mann= 6 ,-1 , 0
  4154.8     .17       0  4741.9     .11       0  4830.4     .15       0
  4930.1     .11       0  4981.7     .06       0  5018.9     .11       0
#XS Ineff= 2 , 0
       0    4863  301.05  5018.9       0  301.12
Permanent Ineff=
       F       T
Bank Sta=4981.7,5018.9
XS Rating Curve= 0 ,0
Exp/Cntr=0.3,0.1

Type RM Length L Ch R = 1 ,972     ,473,473,473
BEGIN DESCRIPTION:
CANEY CREEK NORTH TRIB NO 7 2.0
END DESCRIPTION:
XS GIS Cut Line= 3
        3729659.     10199058.49      3730618.23     10198836.84
      3730847.65     10198497.04
#Sta/Elev= 30
  4015.5  310.62  4096.4  309.58  4127.2  308.48  4260.6  306.94  4373.5  307.82
    4428  306.07  4496.7  307.22  4537.8  307.18  4673.3  304.78    4743  303.61
  4855.9  299.01    4897  298.19  4913.5  298.95  4979.1  297.98  4989.3   296.4
  4995.5   294.1  5004.6  294.89  5010.6   297.4  5025.6  296.42  5040.6  296.33
  5148.5  298.13  5212.1  297.54  5271.4  299.45  5284.5  300.89  5292.4   302.5
  5320.7  311.36  5328.3  312.32  5364.3  314.16  5400.3  315.03    5410   314.7
#Mann= 4 ,-1 , 0
  4015.5     .17       0  4673.3     .11       0  4979.1     .06       0
  5010.6     .11       0
#XS Ineff= 2 , 0
       0  4913.5  298.95               0
Permanent Ineff=
       F       F
Bank Sta=4979.1,5010.6
XS Rating Curve= 0 ,0
Exp/Cntr=0.3,0.1

Type RM Length L Ch R = 1 ,499     ,0,0,0
BEGIN DESCRIPTION:
CANEY CREEK NORTH TRIB NO 7 1.0
END DESCRIPTION:
XS GIS Cut Line= 3
      3729650.78     10199151.62      3730758.23     10199226.84
      3731145.92     10198445.55
#Sta/Elev= 30
    3890  310.94  3953.9  308.71  4007.3  307.89  4127.6  307.27  4251.8  305.34
    4308  306.01  4468.4     302    4540  302.31  4688.7  302.66    4729  301.51
  4789.1  301.63  4909.4   297.7  4969.6  296.68  4979.6  295.41  4986.6   293.2
  4991.6  295.26  4995.6  292.67  4999.1  292.67  5011.2   295.9  5017.6  296.33
  5196.2  295.59  5229.7  294.05  5257.7   295.9  5302.6  295.54  5347.4   296.4
  5420.2  296.39  5487.4  297.71  5593.9  301.54  5711.6  303.49  5872.2  310.43
#Mann= 4 ,-1 , 0
    3890     .17       0    4540     .11       0  4969.6     .06       0
  5347.4     .11       0
#XS Ineff= 2 , 0
       0  4959.5  296.98               0
Permanent Ineff=
       F       F
Bank Sta=4969.6,5347.4
XS Rating Curve= 0 ,0
Exp/Cntr=0.3,0.1

Chan Stop Cuts=-1
Use User Specified Reach Order=0
Composite Channel Slope=5