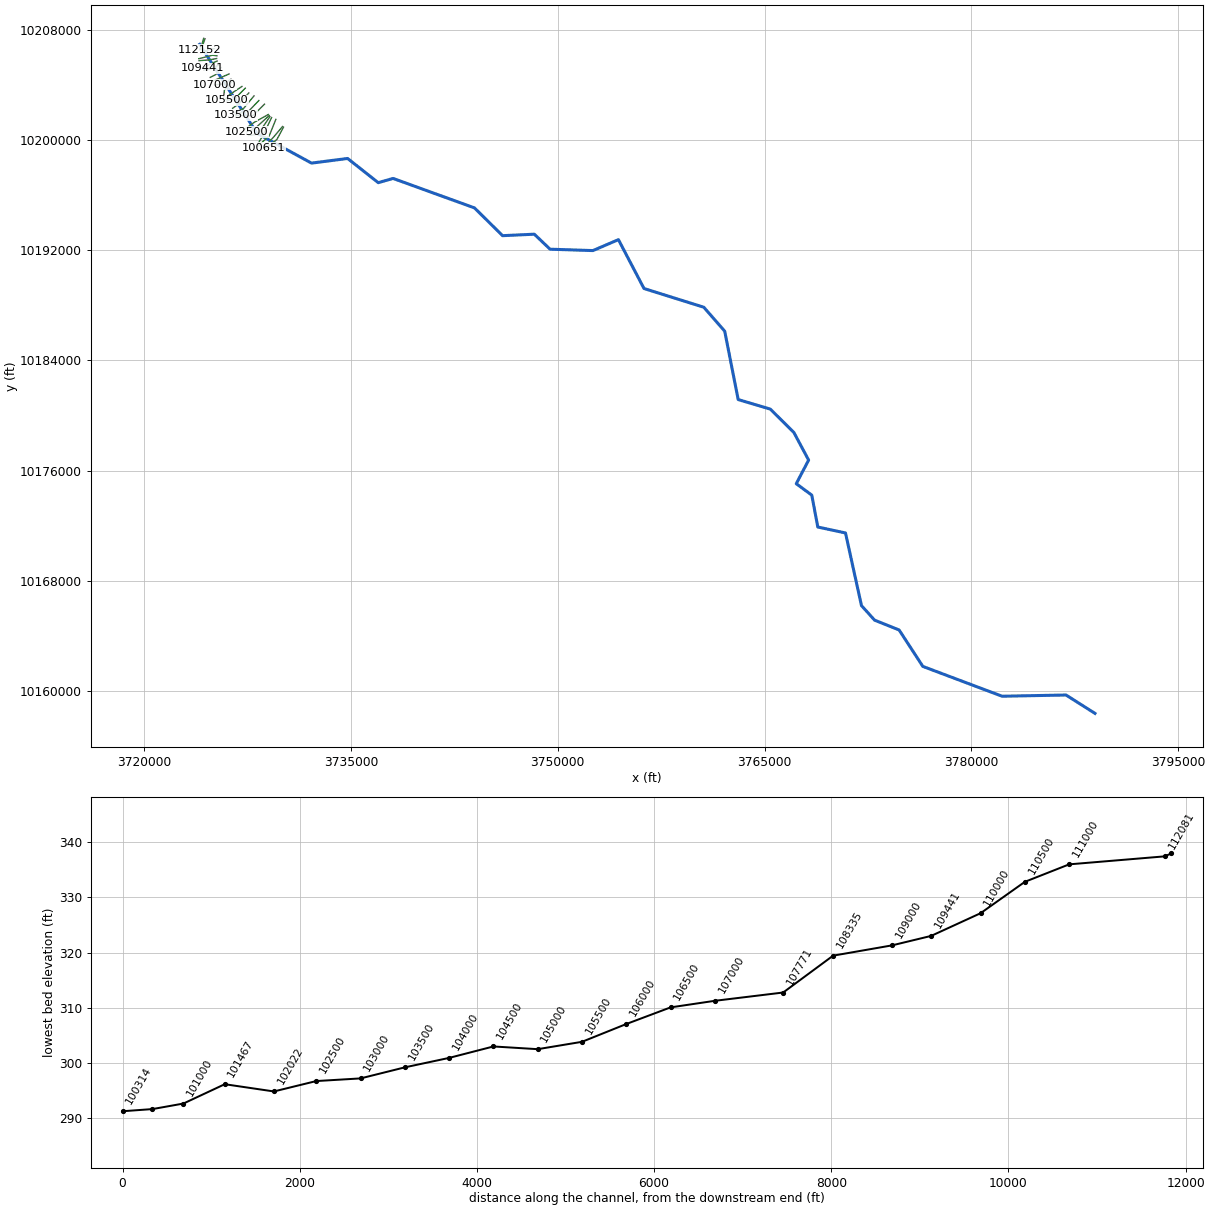
--- CANEY CREEK NORTH.prj (project) ---

Proj Title=CANEY CREEK NORTH Base Level Engineering
Current Plan=p01
Default Exp/Contr=0.3,0.1
English Units
Geom File=g01
Flow File=f01
Plan File=p01
Y Axis Title=Elevation
X Axis Title(PF)=Main Channel Distance
X Axis Title(XS)=Station
BEGIN DESCRIPTION:
CANEY CREEK NORTH
END DESCRIPTION:
DSS Export Rating Curves= 0
DSS Export Rating Curve Sorted= 0
DSS Export Volume Flow Curves= 0
DXF OffsetX= 0
DXF OffsetY= 0
DXF ScaleX= 1
DXF ScaleY= 10

--- CANEY CREEK NORTH.p01 (plan) ---

Plan Title=Multiple Run
Short Identifier=Multiple
Geom File=g01
Flow File=f01
Subcritical Flow
K Sum by GR= 0
Std Step Tol= 0.01
Critical Tol= 0.01
Num of Std Step Trials= 20
Max Error Tol= 0.3
Flow Tol Ratio= 0.001
Split Flow NTrial= 30
Split Flow Tol= 0.02
Split Flow Ratio= 0.02
Log Output Level= 0
Friction Slope Method= 1
Unsteady Friction Slope Method= 2
Unsteady Bridges Friction Slope Method= 1
Parabolic Critical Depth
Global Vel Dist=  1 , 1 , 1
Global Log Level= 0
CheckData=True
Encroach Param= -1, 0, 0, 0
BEGIN DESCRIPTION:
Multiple Run
END DESCRIPTION:

--- CANEY CREEK NORTH.f01 (steady flow) ---

Flow Title=Multiple
Program Version=4.10
Number of Profiles= 7
Profile Names=10-year,25-year,50-year,1pct_min,100-year,1pct_plu,500-year
River Rch & RM=CANEY CREEK NORT,Reach-1         ,112152
     452     600     799     351    1060    3201    1923
River Rch & RM=CANEY CREEK NORT,Reach-1         ,111000
     711     972    1320     590    1782    5382    3357
River Rch & RM=CANEY CREEK NORT,Reach-1         ,106500
    1063    1481    2038     921    2781    8398    5358
River Rch & RM=CANEY CREEK NORT,Reach-1         ,103000
    1157    1603    2200     989    2986    9018    5702
River Rch & RM=CANEY CREEK NORT,Reach-1         ,98500
    1628    2291    3174    1439    4347   13128    8450
River Rch & RM=CANEY CREEK NORT,Reach-1         ,95000
    1809    2572    3588    1640    4952   14955    9766
River Rch & RM=CANEY CREEK NORT,Reach-1         ,93500
    2299    3292    4613    2115    6387   19288   12690
River Rch & RM=CANEY CREEK NORT,Reach-1         ,86993
    2575    3701    5200    2390    7218   21798   14402
River Rch & RM=CANEY CREEK NORT,Reach-1         ,84866
    3346    4846    6845    3160    9542   28816   19209
River Rch & RM=CANEY CREEK NORT,Reach-1         ,79028
    3671    5322    7524    3476   10498   31703   21156
River Rch & RM=CANEY CREEK NORT,Reach-1         ,78128
    3671    5322    7524    3476   10498   31703   21156
River Rch & RM=CANEY CREEK NORT,Reach-1         ,77573
    3980    5785    8194    3791   11449   34575   23148
River Rch & RM=CANEY CREEK NORT,Reach-1         ,77000
    4200    6121    8685    4025   12156   36711   24665
River Rch & RM=CANEY CREEK NORT,Reach-1         ,75500
    3892    5625    7934    3655   11037   33331   22119
River Rch & RM=CANEY CREEK NORT,Reach-1         ,75000
    4305    6251    8847    4088   12347   37287   24906
River Rch & RM=CANEY CREEK NORT,Reach-1         ,74500
    4305    6251    8847    4088   12347   37287   24906
River Rch & RM=CANEY CREEK NORT,Reach-1         ,74000
    4305    6251    8847    4088   12347   37287   24906
River Rch & RM=CANEY CREEK NORT,Reach-1         ,66000
    4180    6035    8508    3916   11825   35711   23648
River Rch & RM=CANEY CREEK NORT,Reach-1         ,65520
    4612    6689    9459    4366   13186   39821   26529
River Rch & RM=CANEY CREEK NORT,Reach-1         ,59670
    4802    6977    9877    4565   13785   41630   27799
River Rch & RM=CANEY CREEK NORT,Reach-1         ,56954
    5329    7765   11016    5101   15404   46519   31173
River Rch & RM=CANEY CREEK NORT,Reach-1         ,56114
    5144    7437   10493    4830   14586   44049   29178
River Rch & RM=CANEY CREEK NORT,Reach-1         ,49000
    5405    7822   11045    5087   15363   46396   30769
River Rch & RM=CANEY CREEK NORT,Reach-1         ,48500
    5405    7822   11045    5087   15363   46396   30769
River Rch & RM=CANEY CREEK NORT,Reach-1         ,48000
    5405    7822   11045    5087   15363   46396   30769
River Rch & RM=CANEY CREEK NORT,Reach-1         ,47000
    5405    7822   11045    5087   15363   46396   30769
River Rch & RM=CANEY CREEK NORT,Reach-1         ,41585
    5331    7671   10788    4948   14944   45130   29675
River Rch & RM=CANEY CREEK NORT,Reach-1         ,40000
    5572    8033   11310    5194   15685   47368   31216
River Rch & RM=CANEY CREEK NORT,Reach-1         ,29906
    6037    8767   12407    5727   17295   52230   34780
River Rch & RM=CANEY CREEK NORT,Reach-1         ,29083
    5655    8151   11477    5270   15915   48063   31667
River Rch & RM=CANEY CREEK NORT,Reach-1         ,27500
    6095    8802   12407    5703   17222   52010   34342
River Rch & RM=CANEY CREEK NORT,Reach-1         ,23500
    6503    9447   13375    6174   18646   56310   37505
River Rch & RM=CANEY CREEK NORT,Reach-1         ,22500
    5892    8460   11880    5438   16422   49594   32477
River Rch & RM=CANEY CREEK NORT,Reach-1         ,20000
    6109    8778   12333    5648   17057   51511   33762
River Rch & RM=CANEY CREEK NORT,Reach-1         ,15000
    6142    8824   12395    5675   17139   51759   33912
River Rch & RM=CANEY CREEK NORT,Reach-1         ,12500
    6187    8887   12484    5716   17261   52127   34149
River Rch & RM=CANEY CREEK NORT,Reach-1         ,12000
    6261    8996   12639    5788   17479   52786   34586
River Rch & RM=CANEY CREEK NORT,Reach-1         ,9500
    6818    9834   13855    6364   19218   58037   38242
River Rch & RM=CANEY CREEK NORT,Reach-1         ,7000
    6366    9105   12751    5821   17579   53088   34553
River Rch & RM=CANEY CREEK NORT,Reach-1         ,2563
    6736    9688   13622    6243   18854   56938   37360
Boundary for River Rch & Prof#=CANEY CREEK NORT,Reach-1         , 1
Up Type= 0
Dn Type= 3
Dn Slope=0.005
Boundary for River Rch & Prof#=CANEY CREEK NORT,Reach-1         , 2
Up Type= 0
Dn Type= 3
Dn Slope=0.005
Boundary for River Rch & Prof#=CANEY CREEK NORT,Reach-1         , 3
Up Type= 0
Dn Type= 3
Dn Slope=0.005
Boundary for River Rch & Prof#=CANEY CREEK NORT,Reach-1         , 4
Up Type= 0
Dn Type= 3
Dn Slope=0.005
Boundary for River Rch & Prof#=CANEY CREEK NORT,Reach-1         , 5
Up Type= 0
Dn Type= 3
Dn Slope=0.005
Boundary for River Rch & Prof#=CANEY CREEK NORT,Reach-1         , 6
Up Type= 0
Dn Type= 3
Dn Slope=0.005
Boundary for River Rch & Prof#=CANEY CREEK NORT,Reach-1         , 7
Up Type= 0
Dn Type= 3
Dn Slope=0.005
DSS Import GetInterval= 0
DSS Import GetPeak= 0
DSS Import FillOption= 0

--- CANEY CREEK NORTH.f02 (steady flow) ---

Flow Title=Orig_BLE_Flow
Program Version=4.10
Number of Profiles= 7
Profile Names=10-year,25-year,50-year,1pct_min,100-year,1pct_plu,500-year
River Rch & RM=CANEY CREEK NORT,Reach-1         ,112152
     452     588     695     270     815    2461    1118
River Rch & RM=CANEY CREEK NORT,Reach-1         ,111000
     711     953    1148     454    1371    4140    1952
River Rch & RM=CANEY CREEK NORT,Reach-1         ,106500
    1063    1452    1772     708    2139    6459    3115
River Rch & RM=CANEY CREEK NORT,Reach-1         ,103000
    1157    1572    1913     761    2297    6938    3315
River Rch & RM=CANEY CREEK NORT,Reach-1         ,98500
    1628    2246    2760    1107    3344   10099    4913
River Rch & RM=CANEY CREEK NORT,Reach-1         ,95000
    1809    2522    3120    1261    3809   11503    5678
River Rch & RM=CANEY CREEK NORT,Reach-1         ,93500
    2299    3227    4011    1627    4913   14838    7378
River Rch & RM=CANEY CREEK NORT,Reach-1         ,86993
    2575    3628    4522    1838    5552   16766    8373
River Rch & RM=CANEY CREEK NORT,Reach-1         ,84866
    3346    4751    5952    2431    7340   22167   11168
River Rch & RM=CANEY CREEK NORT,Reach-1         ,79028
    3671    5218    6543    2674    8075   24386   12300
River Rch & RM=CANEY CREEK NORT,Reach-1         ,78128
    3671    5218    6543    2674    8075   24386   12300
River Rch & RM=CANEY CREEK NORT,Reach-1         ,77573
    3980    5672    7125    2916    8807   26597   13458
River Rch & RM=CANEY CREEK NORT,Reach-1         ,77000
    4200    6001    7552    3097    9351   28240   14340
River Rch & RM=CANEY CREEK NORT,Reach-1         ,75500
    3892    5515    6899    2811    8490   25640   12860
River Rch & RM=CANEY CREEK NORT,Reach-1         ,74500
    4305    6128    7693    3145    9498   28684   14480
River Rch & RM=CANEY CREEK NORT,Reach-1         ,74000
    4305    6128    7693    3145    9498   28684   14480
River Rch & RM=CANEY CREEK NORT,Reach-1         ,66000
    4180    5917    7398    3012    9096   27470   13749
River Rch & RM=CANEY CREEK NORT,Reach-1         ,65520
    4612    6558    8225    3359   10143   30631   15424
River Rch & RM=CANEY CREEK NORT,Reach-1         ,59670
    4802    6840    8589    3511   10604   32023   16162
River Rch & RM=CANEY CREEK NORT,Reach-1         ,56954
    5329    7613    9579    3923   11849   35782   18124
River Rch & RM=CANEY CREEK NORT,Reach-1         ,56114
    5144    7291    9124    3715   11220   33885   16964
River Rch & RM=CANEY CREEK NORT,Reach-1         ,49000
    5405    7669    9604    3913   11818   35690   17889
River Rch & RM=CANEY CREEK NORT,Reach-1         ,48500
    5405    7669    9604    3913   11818   35690   17889
River Rch & RM=CANEY CREEK NORT,Reach-1         ,48000
    5405    7669    9604    3913   11818   35690   17889
River Rch & RM=CANEY CREEK NORT,Reach-1         ,47000
    5405    7669    9604    3913   11818   35690   17889
River Rch & RM=CANEY CREEK NORT,Reach-1         ,41585
    5331    7521    9381    3806   11495   34715   17253
River Rch & RM=CANEY CREEK NORT,Reach-1         ,40000
    5572    7875    9835    3995   12065   36436   18149
River Rch & RM=CANEY CREEK NORT,Reach-1         ,29906
    6037    8595   10789    4405   13304   40176   20221
River Rch & RM=CANEY CREEK NORT,Reach-1         ,29083
    5655    7991    9980    4054   12242   36969   18411
River Rch & RM=CANEY CREEK NORT,Reach-1         ,27500
    6095    8629   10789    4387   13248   40010   19966
River Rch & RM=CANEY CREEK NORT,Reach-1         ,23500
    6503    9262   11630    4749   14343   43315   21805
River Rch & RM=CANEY CREEK NORT,Reach-1         ,22500
    5892    8294   10330    4183   12632   38149   18882
River Rch & RM=CANEY CREEK NORT,Reach-1         ,20000
    6109    8606   10724    4345   13121   39624   19629
River Rch & RM=CANEY CREEK NORT,Reach-1         ,15000
    6142    8651   10778    4366   13184   39815   19716
River Rch & RM=CANEY CREEK NORT,Reach-1         ,12500
    6187    8713   10856    4397   13278   40100   19854
River Rch & RM=CANEY CREEK NORT,Reach-1         ,12000
    6261    8820   10990    4452   13445   40602   20108
River Rch & RM=CANEY CREEK NORT,Reach-1         ,9500
    6818    9641   12048    4895   14783   44643   22234
River Rch & RM=CANEY CREEK NORT,Reach-1         ,7000
    6366    8926   11088    4478   13522   40836   20089
River Rch & RM=CANEY CREEK NORT,Reach-1         ,2563
    6736    9498   11845    4802   14503   43799   21721
Boundary for River Rch & Prof#=CANEY CREEK NORT,Reach-1         , 1
Up Type= 0
Dn Type= 3
Dn Slope=0.008
Boundary for River Rch & Prof#=CANEY CREEK NORT,Reach-1         , 2
Up Type= 0
Dn Type= 3
Dn Slope=0.008
Boundary for River Rch & Prof#=CANEY CREEK NORT,Reach-1         , 3
Up Type= 0
Dn Type= 3
Dn Slope=0.008
Boundary for River Rch & Prof#=CANEY CREEK NORT,Reach-1         , 4
Up Type= 0
Dn Type= 3
Dn Slope=0.008
Boundary for River Rch & Prof#=CANEY CREEK NORT,Reach-1         , 5
Up Type= 0
Dn Type= 3
Dn Slope=0.008
Boundary for River Rch & Prof#=CANEY CREEK NORT,Reach-1         , 6
Up Type= 0
Dn Type= 3
Dn Slope=0.008
Boundary for River Rch & Prof#=CANEY CREEK NORT,Reach-1         , 7
Up Type= 0
Dn Type= 3
Dn Slope=0.008
DSS Import GetInterval= 0
DSS Import GetPeak= 0
DSS Import FillOption= 0

--- CANEY CREEK NORTH.g01 (geometry) ---

Geom Title=Existing Conditions
Program Version=4.10

River Reach=CANEY CREEK NORT,Reach-1
Reach XY= 30
      3724026.11     10206950.59      3728188.02     10200486.91
      3732138.28     10198329.27      3734756.73      10198665.4
      3736978.23     10196909.22      3738054.89     10197215.73
      3743958.23     10195076.84      3745997.42     10193059.51
      3748298.23     10193166.84      3749441.79     10192077.62
      3752550.06     10191976.91      3754399.38     10192771.33
      3756254.62     10189221.44      3760589.84     10187863.78
      3762108.44     10186124.52      3763086.28       10181159.
      3765419.87     10180463.75      3767124.09     10178769.97
      3768195.63     10176762.62      3767298.32     10175046.16
      3768424.02     10174220.09      3768860.08     10171902.36
      3770869.67      10171470.3      3772028.61     10166196.11
      3772980.85     10165139.15      3774759.14     10164425.17
      3776479.33     10161780.55       3782228.2     10159614.52
      3786863.73     10159703.21      3788964.56     10158369.71

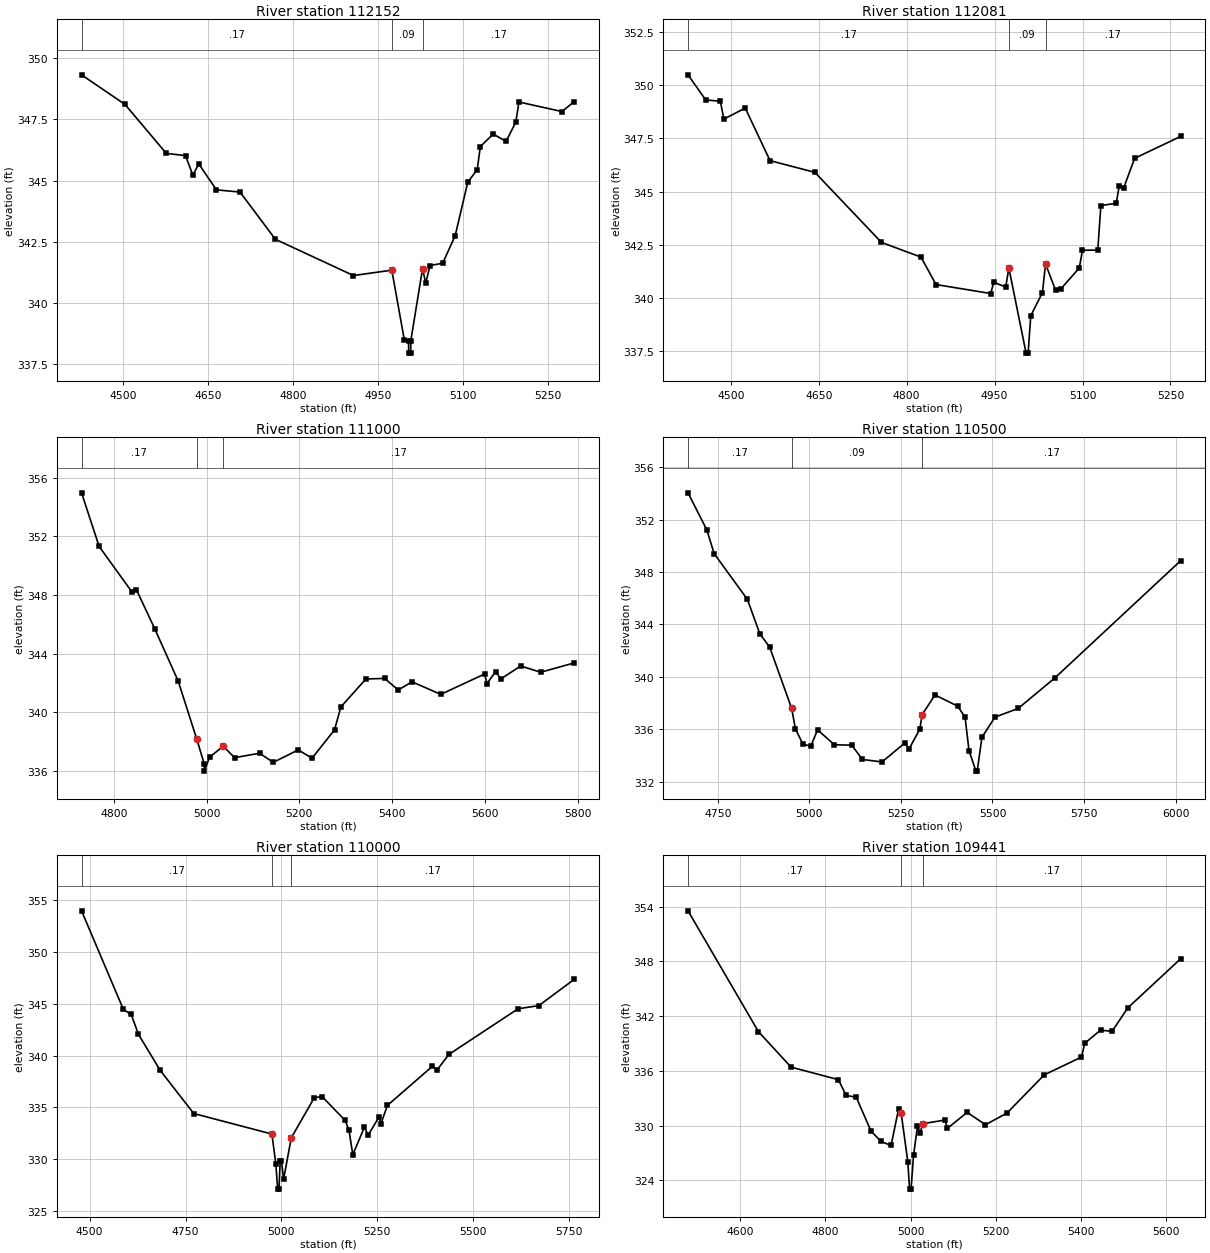
Type RM Length L Ch R = 1 ,112152  ,71,71,71
BEGIN DESCRIPTION:
CANEY CREEK NORTH 221.0
END DESCRIPTION:
XS GIS Cut Line= 3
      3724313.89     10207389.94      3724156.54     10206838.86
      3724029.29     10206571.27
#Sta/Elev= 30
  4426.9  349.32  4503.6  348.11  4576.4  346.11  4610.3  346.02  4623.3  345.22
  4633.7  345.68  4664.9  344.62  4706.5  344.53  4768.9   342.6  4906.7  341.12
  4974.3  341.34  4996.3   338.5  5003.8  338.45  5004.1  337.95  5007.6  337.95
  5007.8  338.45  5028.5   341.4  5034.1  340.81  5041.8  341.53    5064  341.62
  5086.1  342.75  5108.3  344.93    5125  345.45  5130.5  346.39  5153.2   346.9
  5175.9   346.6  5193.1  347.39  5198.6  348.21  5274.4  347.82  5296.3  348.23
#Mann= 3 , 0 , 0
  4426.9     .17       0  4974.3     .09       0  5028.5     .17       0
Bank Sta=4974.3,5028.5
XS Rating Curve= 0 ,0
Exp/Cntr=0.3,0.1

Type RM Length L Ch R = 1 ,112081  ,1081,1081,1081
BEGIN DESCRIPTION:
CANEY CREEK NORTH 220.0
END DESCRIPTION:
XS GIS Cut Line= 3
      3724413.31      10207363.1      3724224.24      10206822.2
      3724138.66     10206568.65
#Sta/Elev= 30
    4427  350.49  4457.2  349.31  4482.1  349.25  4488.2  348.41  4524.6  348.93
  4566.9  346.46  4643.4  345.91    4757  342.62  4824.4  341.93  4850.1  340.64
  4943.3  340.22  4948.6  340.75    4969  340.52  4974.3  341.42  5003.7  337.42
  5007.2  337.42  5011.7  339.18  5031.6  340.26  5036.9  341.61    5054  340.37
  5063.1  340.44  5094.5  341.42  5099.8  342.25    5126  342.26  5131.3  344.35
  5157.5  344.46  5162.7  345.29  5170.1  345.17  5188.9  346.57  5267.6   347.6
#Mann= 3 , 0 , 0
    4427     .17       0  4974.3     .09       0  5036.9     .17       0
Bank Sta=4974.3,5036.9
XS Rating Curve= 0 ,0
Exp/Cntr=0.3,0.1

Type RM Length L Ch R = 1 ,111000  ,500,500,500
BEGIN DESCRIPTION:
CANEY CREEK NORTH 219.0
END DESCRIPTION:
XS GIS Cut Line= 3
      3725105.65     10206637.23      3724836.75     10206619.23
      3724100.41     10206325.41
#Sta/Elev= 30
  4730.5  354.97  4768.4  351.31  4838.5  348.23  4848.6  348.37  4888.7  345.66
  4938.8  342.12  4978.9  338.15  4994.9  336.47  4995.2  335.97  5006.4  336.92
    5036  337.67  5060.3  336.89  5114.2  337.19  5143.8  336.57  5197.7  337.42
  5227.3  336.85  5275.9  338.79  5289.5  340.35  5343.4  342.26  5383.7   342.3
  5413.3  341.51  5442.9  342.07  5504.9  341.21  5599.3   342.6  5604.6  341.95
  5623.3  342.77  5634.3  342.26  5677.1  343.15  5720.2  342.72  5792.8  343.36
#Mann= 3 , 0 , 0
  4730.5     .17       0  4978.9     .09       0    5036     .17       0
Bank Sta=4978.9,5036
XS Rating Curve= 0 ,0
Exp/Cntr=0.3,0.1

Type RM Length L Ch R = 1 ,110500  ,500,500,500
BEGIN DESCRIPTION:
CANEY CREEK NORTH 218.0
END DESCRIPTION:
XS GIS Cut Line= 3
      3725278.71     10206122.12      3724950.13     10206162.84
      3723967.88     10205911.08
#Sta/Elev= 30
  4668.9  354.04  4720.2  351.21  4740.3   349.4    4831  345.91    4865  343.28
  4891.5  342.29  4951.9  337.59    4962  336.04  4982.1  334.89  5003.8   334.7
  5022.5  335.96  5068.5  334.82  5115.9  334.79  5144.9   333.7  5198.5  333.51
  5260.4  334.95  5272.4  334.51  5301.7  336.02    5308  337.12    5343  338.62
    5405  337.77  5425.2  336.92  5435.9  334.38  5454.8  332.81  5458.3  332.81
  5471.2  335.39  5506.8  336.93  5570.1  337.59  5669.9  339.91    6014  348.87
#Mann= 3 , 0 , 0
  4668.9     .17       0  4951.9     .09       0    5308     .17       0
Bank Sta=4951.9,5308
XS Rating Curve= 0 ,0
Exp/Cntr=0.3,0.1

Type RM Length L Ch R = 1 ,110000  ,559,559,559
BEGIN DESCRIPTION:
CANEY CREEK NORTH 217.0
END DESCRIPTION:
XS GIS Cut Line= 3
      3725254.92     10205925.42      3724743.53     10205824.79
      3723981.75     10205769.25
#Sta/Elev= 30
  4478.8  353.96  4587.9  344.45  4608.3  343.97  4627.2  342.05  4683.7  338.59
  4771.4  334.42  4975.2  332.44  4985.4  329.57  4990.2  327.13  4993.7  327.13
  4996.7  329.83    5000  329.83  5005.7  328.09  5025.7  332.08  5085.9  335.95
    5106  336.05  5166.1  333.76  5176.1  332.82  5186.2  330.45  5216.2  333.08
  5226.3  332.34  5254.4  334.08  5259.4  333.43  5276.4   335.2  5393.4  338.96
  5406.8  338.66  5436.8  340.12  5617.3  344.52  5671.2  344.82  5763.8  347.36
#Mann= 3 , 0 , 0
  4478.8     .17       0  4975.2     .09       0  5025.7     .17       0
Bank Sta=4975.2,5025.7
XS Rating Curve= 0 ,0
Exp/Cntr=0.3,0.1

Type RM Length L Ch R = 1 ,109441  ,441,441,441
BEGIN DESCRIPTION:
CANEY CREEK NORTH 216.0
END DESCRIPTION:
XS GIS Cut Line= 3
      3725293.15     10205741.39      3724811.73      10205537.8
      3724267.83     10205211.06
#Sta/Elev= 30
  4477.3  353.56  4642.7   340.3  4719.3  336.41  4830.5  335.03  4848.6   333.3
  4872.3  333.11  4906.8  329.41  4930.5  328.25  4954.2  327.81  4971.6  331.78
  4977.9  331.35  4993.4  326.05  4997.6  323.02  5001.1  323.02  5006.9  326.74
  5016.2  329.91  5022.4  329.16  5028.2   330.2  5080.7   330.6  5086.5  329.69
  5132.8  331.44  5175.9  330.09  5226.2  331.36  5313.9  335.56  5401.2  337.51
  5409.1  339.03    5446  340.46  5473.2  340.34  5510.1  342.91  5634.5  348.31
#Mann= 3 , 0 , 0
  4477.3     .17       0  4977.9     .09       0  5028.2     .17       0
Bank Sta=4977.9,5028.2
XS Rating Curve= 0 ,0
Exp/Cntr=0.3,0.1

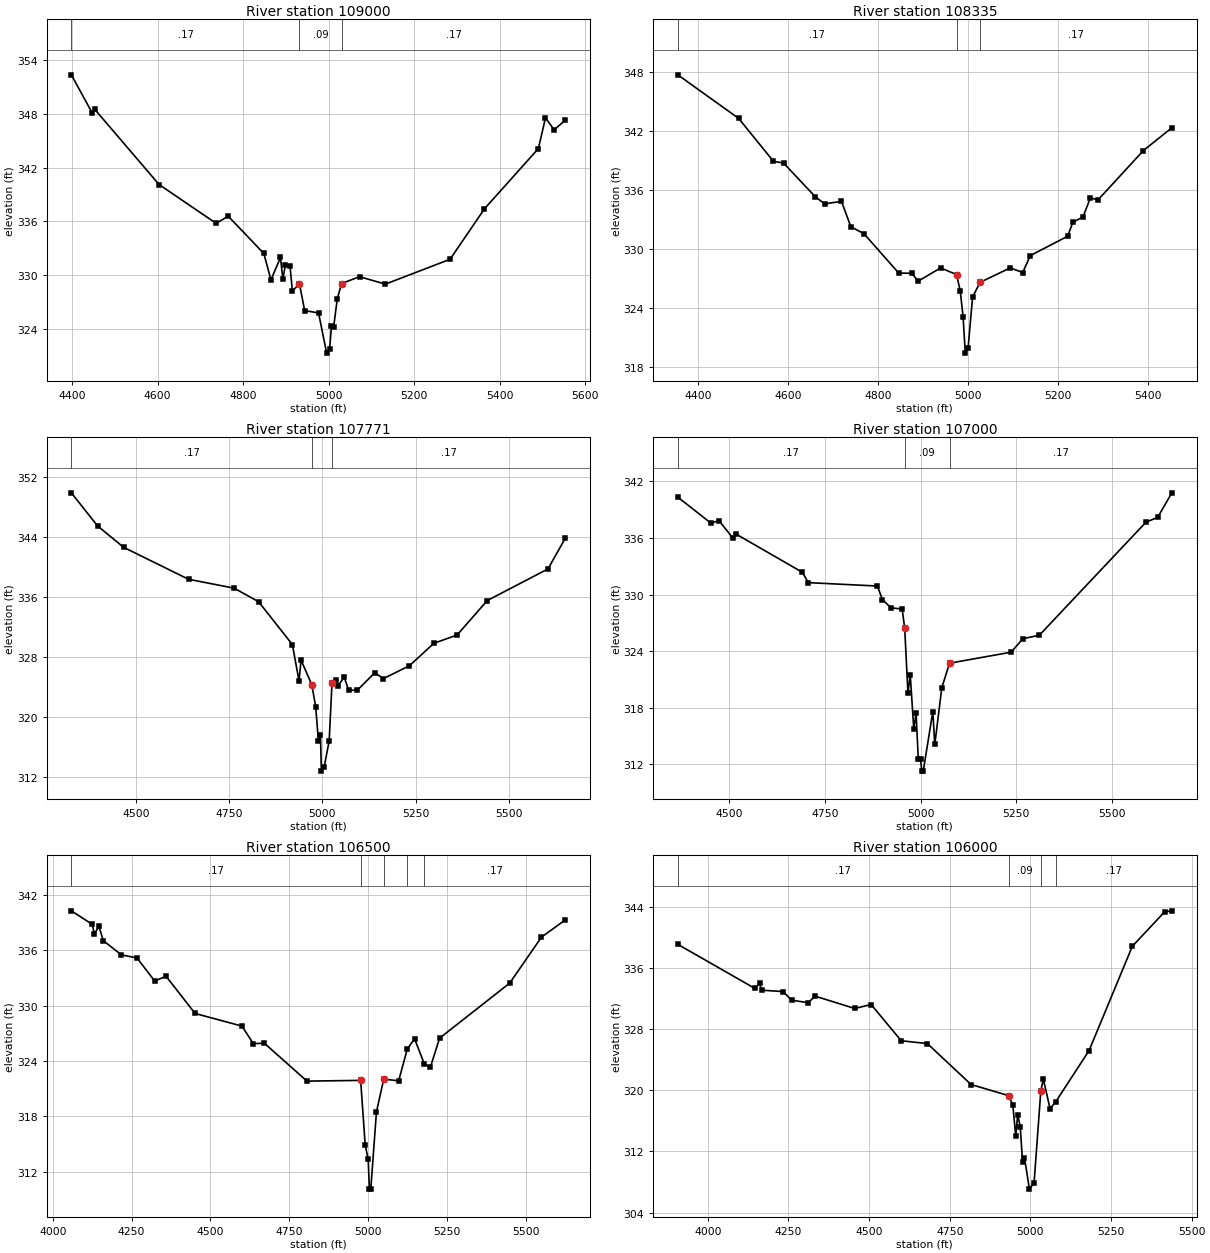
Type RM Length L Ch R = 1 ,109000  ,665,665,665
BEGIN DESCRIPTION:
CANEY CREEK NORTH 215.0
END DESCRIPTION:
XS GIS Cut Line= 3
      3725404.23     10205449.71      3724867.96     10205177.49
      3724321.89     10205085.31
#Sta/Elev= 30
  4398.6  352.33  4447.9  348.03  4453.5  348.47  4603.7   340.1  4737.3  335.77
  4765.2  336.58  4848.6  332.42  4865.3  329.47  4887.5  331.97  4893.1  329.57
  4899.2  331.17  4909.8  331.06  4915.4  328.24    4932  329.02  4944.1  326.05
  4976.6  325.79  4995.5  321.31  5002.6  321.81  5006.8  324.37  5011.9  324.23
  5020.4  327.38  5030.5  329.07  5072.4  329.83  5132.8     329  5284.1  331.77
  5364.6   337.4  5490.6  344.11  5507.2  347.53  5527.5   346.2  5553.8  347.28
#Mann= 3 , 0 , 0
  4398.6     .17       0    4932     .09       0  5030.5     .17       0
Bank Sta=4932,5030.5
XS Rating Curve= 0 ,0
Exp/Cntr=0.3,0.1

Type RM Length L Ch R = 1 ,108335  ,564,564,564
BEGIN DESCRIPTION:
CANEY CREEK NORTH 214.0
END DESCRIPTION:
XS GIS Cut Line= 3
       3725588.3     10205269.19      3725194.74     10204759.06
      3724791.24     10204554.69
#Sta/Elev= 30
  4355.7  347.73  4490.8   343.3    4568  338.94  4590.4  338.77    4661  335.33
  4681.8  334.62    4719  334.87  4739.8  332.29  4768.8  331.59  4845.9  327.59
  4874.8  327.56  4889.3  326.77  4939.1  328.11  4974.4  327.43  4982.6  325.77
  4988.9  323.16  4993.8  319.45    5000  319.95    5010  325.15  5026.6  326.64
  5093.5  328.11  5121.3  327.64    5138  329.36  5220.7  331.32  5232.7  332.75
    5255  333.29  5271.7  335.24    5288     335  5388.8  340.02  5452.3  342.35
#Mann= 3 , 0 , 0
  4355.7     .17       0  4974.4     .09       0  5026.6     .17       0
Bank Sta=4974.4,5026.6
XS Rating Curve= 0 ,0
Exp/Cntr=0.3,0.1

Type RM Length L Ch R = 1 ,107771  ,771,771,771
BEGIN DESCRIPTION:
CANEY CREEK NORTH 213.0
END DESCRIPTION:
XS GIS Cut Line= 3
      3726157.19     10204804.34      3725541.66     10204532.71
      3724945.09     10204269.88
#Sta/Elev= 30
  4327.2  349.86  4397.4  345.45  4467.3   342.6  4641.5  338.34  4763.5  337.16
  4829.3  335.35  4919.8  329.64  4937.6  324.81  4943.1  327.58  4971.9  324.29
  4982.3  321.36  4989.7  316.77  4995.2  317.57  4997.5  312.78  5004.8  313.28
  5018.5  316.81    5026   324.5  5036.4   324.9  5041.8  324.12  5058.8   325.3
  5070.6  323.57    5094  323.56  5140.6  325.88  5163.9  325.11  5233.6  326.82
  5299.2  329.81  5361.5  330.92  5442.4  335.51  5605.2  339.72  5651.9  343.84
#Mann= 3 , 0 , 0
  4327.2     .17       0  4971.9     .09       0    5026     .17       0
Bank Sta=4971.9,5026
XS Rating Curve= 0 ,0
Exp/Cntr=0.3,0.1

Type RM Length L Ch R = 1 ,107000  ,500,500,500
BEGIN DESCRIPTION:
CANEY CREEK NORTH 211.0
END DESCRIPTION:
XS GIS Cut Line= 3
      3726296.08     10204422.39      3725763.11     10204079.77
      3725110.94     10204008.12
#Sta/Elev= 30
  4366.4  340.32  4452.8  337.57  4473.9  337.83  4510.2  335.98  4518.8   336.4
  4691.8  332.35    4707  331.26  4887.4   330.9  4900.5  329.46    4923  328.59
  4952.1  328.46  4958.7  326.43  4967.2  319.54  4973.2  321.48  4982.4  315.73
  4988.4  317.45  4994.2  312.54    5000  312.54  5003.5  311.28  5007.1  311.28
  5032.1  317.59  5037.2  314.11  5055.6  320.12  5075.7  322.72  5236.7  323.89
  5266.9  325.31  5310.3  325.69  5588.8  337.68    5619  338.17  5656.1  340.78
#Mann= 3 , 0 , 0
  4366.4     .17       0  4958.7     .09       0  5075.7     .17       0
Bank Sta=4958.7,5075.7
XS Rating Curve= 0 ,0
Exp/Cntr=0.3,0.1

Type RM Length L Ch R = 1 ,106500  ,500,500,500
BEGIN DESCRIPTION:
CANEY CREEK NORTH 210.0
END DESCRIPTION:
XS GIS Cut Line= 3
      3726429.92      10204341.8      3725818.04     10203627.04
      3725749.65     10203005.69
#Sta/Elev= 30
  4059.1  340.29  4125.4  338.82    4132  337.75  4146.2  338.63  4160.5  337.05
  4217.6  335.51    4267  335.18  4323.3  332.67  4359.2  333.19  4451.4  329.15
  4599.8  327.78  4635.8  325.88  4670.9  325.92  4805.9  321.81  4976.1  321.89
  4990.4  314.91    5000  313.31  5003.8  310.09  5008.2  310.09  5026.1  318.46
  5049.3  322.03  5096.5  321.84  5123.7  325.27  5146.8  326.42    5178  323.67
  5197.1  323.31  5226.2  326.47  5448.7  332.45  5549.3  337.44  5625.1  339.31
#Mann= 5 ,-1 , 0
  4059.1     .17       0  4976.1     .09       0  5049.3     .17       0
  5123.7     .11       0    5178     .17       0
Bank Sta=4976.1,5049.3
XS Rating Curve= 0 ,0
Exp/Cntr=0.3,0.1

Type RM Length L Ch R = 1 ,106000  ,500,500,500
BEGIN DESCRIPTION:
CANEY CREEK NORTH 209.0
END DESCRIPTION:
XS GIS Cut Line= 3
      3727092.68     10203897.15      3726181.68     10203293.23
      3725900.03       10202957.
#Sta/Elev= 30
    3907  339.07  4145.5  333.32  4160.5  333.98  4166.5  333.08  4232.7   332.9
  4260.7  331.77  4310.9  331.44  4332.7   332.3  4455.3  330.69  4506.4   331.2
  4599.7  326.47  4680.6   326.1  4816.2  320.75  4932.6   319.3  4945.6  318.07
  4954.6  314.01  4960.6   316.8  4968.6  315.26  4975.7  310.64  4981.7  311.21
    4997  307.08  5011.5  307.91  5032.4  319.93  5040.2  321.44    5061   317.6
  5079.1  318.53    5182  325.19    5316  338.81  5416.2  343.32  5438.6  343.45
#Mann= 4 ,-1 , 0
    3907     .17       0  4932.6     .09       0  5032.4     .15       0
  5079.1     .17       0
Bank Sta=4932.6,5032.4
XS Rating Curve= 0 ,0
Exp/Cntr=0.3,0.1

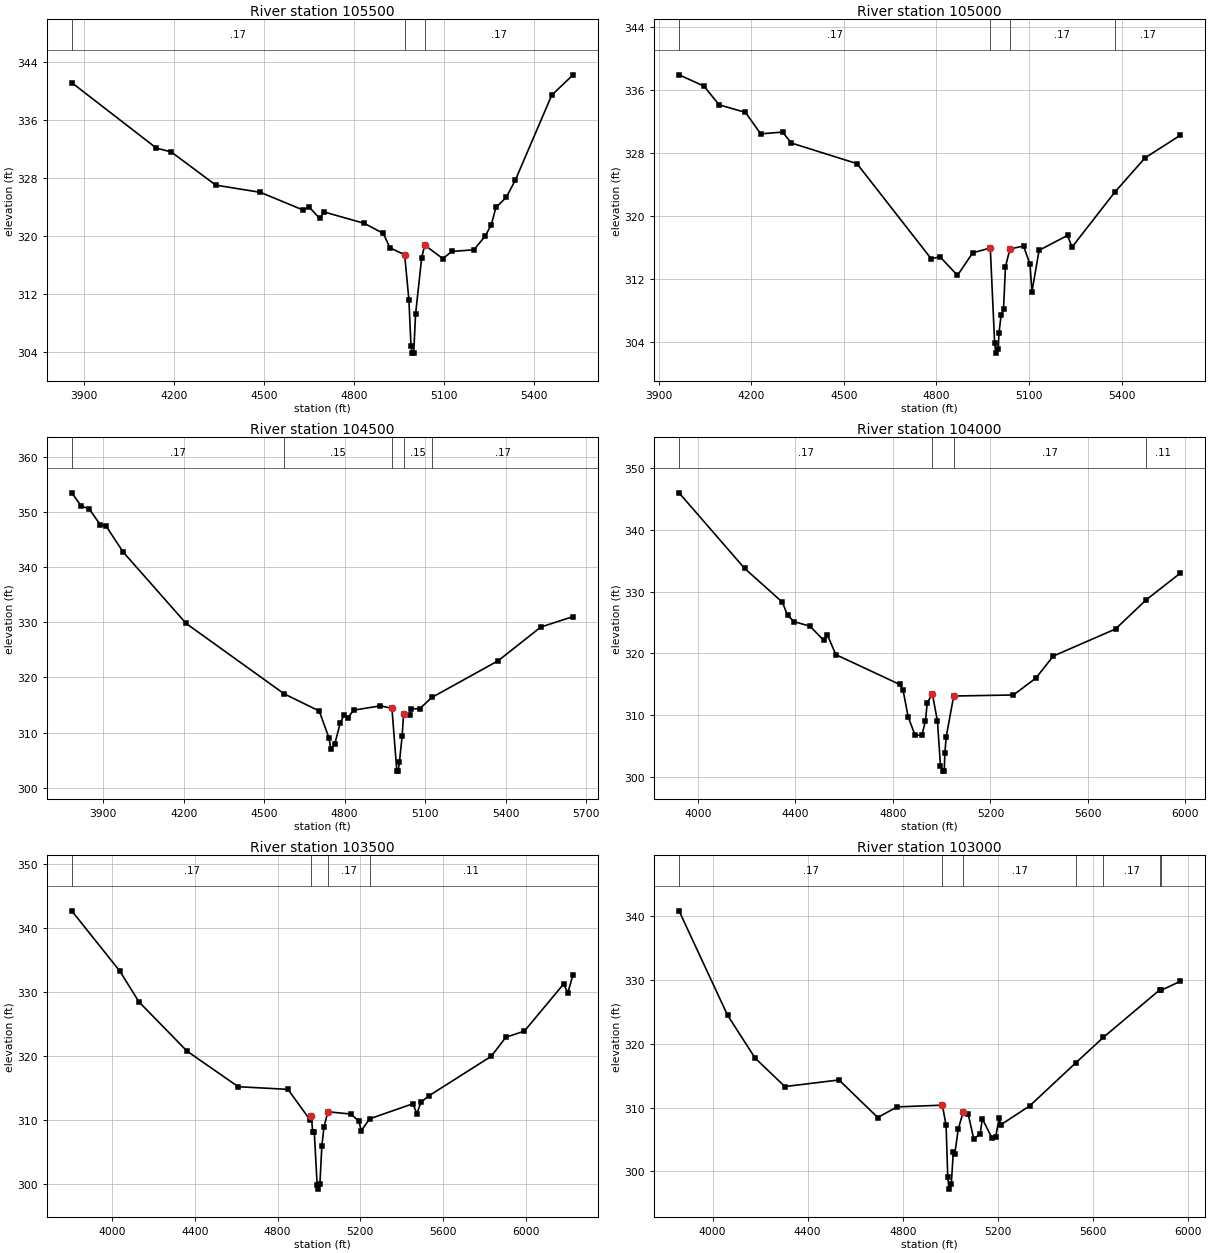
Type RM Length L Ch R = 1 ,105500  ,500,500,500
BEGIN DESCRIPTION:
CANEY CREEK NORTH 208.0
END DESCRIPTION:
XS GIS Cut Line= 3
      3727334.42     10203773.58      3726533.35     10202961.92
      3726007.51     10202892.54
#Sta/Elev= 30
  3859.6   341.1  4141.8  332.09  4191.3  331.56  4339.8  326.99  4488.3     326
  4629.7  323.58  4650.9  323.98  4686.3   322.4  4700.4   323.3  4834.7  321.73
  4898.4  320.34  4919.6  318.38  4969.1   317.4  4983.3  311.23  4990.3  304.84
  4994.8  303.86  4999.4  303.86  5005.5   309.2  5025.7  316.92  5035.8  318.74
  5096.3  316.88  5126.6  317.86  5199.9  318.09  5237.5  319.97  5257.7  321.52
  5273.4  323.92  5308.1  325.33  5338.4  327.71  5459.4  339.38  5530.4  342.18
#Mann= 3 , 0 , 0
  3859.6     .17       0  4969.1     .09       0  5035.8     .17       0
Bank Sta=4969.1,5035.8
XS Rating Curve= 0 ,0
Exp/Cntr=0.3,0.1

Type RM Length L Ch R = 1 ,105000  ,500,500,500
BEGIN DESCRIPTION:
CANEY CREEK NORTH 207.0
END DESCRIPTION:
XS GIS Cut Line= 3
      3727588.94     10203423.54      3726895.41     10202657.01
      3726417.85     10202311.07
#Sta/Elev= 30
  3966.3  337.95  4046.8  336.52  4096.2  334.13  4181.3  333.17  4230.7  330.44
  4301.7  330.66    4330  329.27  4542.3  326.65  4782.9  314.54  4811.3  314.79
    4868  312.43  4917.4   315.3  4974.2  315.91  4988.3  303.83  4992.1  302.53
    5000  303.03  5002.4  305.14  5009.3  307.34  5017.1  308.13  5023.3  313.51
    5038   315.8    5082  316.15  5102.9  313.83  5109.1  310.34  5132.3  315.62
  5224.3  317.51    5239  316.03  5377.3  323.01  5475.6  327.39  5589.7  330.26
#Mann= 4 ,-1 , 0
  3966.3     .17       0  4974.2     .09       0    5038     .17       0
  5377.3     .17       0
Bank Sta=4974.2,5038
XS Rating Curve= 0 ,0
Exp/Cntr=0.3,0.1

Type RM Length L Ch R = 1 ,104500  ,500,500,500
BEGIN DESCRIPTION:
CANEY CREEK NORTH 206.0
END DESCRIPTION:
XS GIS Cut Line= 3
      3727967.86     10203211.08      3727191.32     10202273.76
      3726591.24     10202019.57
#Sta/Elev= 30
  3782.8  353.44  3818.6  351.02  3847.3  350.57  3888.9  347.68  3911.1  347.39
  3974.9  342.69  4209.4  329.77  4575.1  317.01  4705.5  313.91    4742     309
  4748.5  307.08  4762.9  307.85  4783.7  311.71    4798  313.19  4812.3  312.72
  4834.5  314.07  4933.5  314.85  4976.5  314.41  4994.8  303.02  4999.7  303.02
  5004.6  304.74  5014.5  309.34  5019.9  313.32  5043.6  313.22    5049  314.32
  5079.8  314.31  5125.1  316.36    5373  323.03  5531.5  329.12  5651.7  331.02
#Mann= 5 ,-1 , 0
  3782.8     .17       0  4575.1     .15       0  4976.5     .09       0
  5019.9     .15       0  5125.1     .17       0
Bank Sta=4976.5,5019.9
XS Rating Curve= 0 ,0
Exp/Cntr=0.3,0.1

Type RM Length L Ch R = 1 ,104000  ,500,500,500
BEGIN DESCRIPTION:
CANEY CREEK NORTH 205.0
END DESCRIPTION:
XS GIS Cut Line= 3
      3728322.28     10202876.52      3727576.17     10202098.72
      3726617.48     10201897.38
#Sta/Elev= 30
  3922.2  346.01    4191  333.79  4346.3   328.3  4367.7  326.16    4396  325.13
  4459.6  324.42  4516.2  322.13  4530.3  323.06  4565.8  319.81  4827.5  314.99
  4841.6  314.05  4862.7  309.72    4891  306.73  4919.3  306.82  4933.5   309.1
  4940.7  311.96  4961.8  313.48  4982.9  308.99  4995.2  301.79  5005.7  300.95
  5010.6  300.95  5013.3  303.96  5018.7  306.51  5049.4  313.11  5294.6  313.28
  5386.6  316.01  5458.1  319.58  5713.5  323.96  5839.9   328.7  5979.6  333.01
#Mann= 4 ,-1 , 0
  3922.2     .17       0  4961.8     .09       0  5049.4     .17       0
  5839.9     .11       0
Bank Sta=4961.8,5049.4
XS Rating Curve= 0 ,0
Exp/Cntr=0.3,0.1

Type RM Length L Ch R = 1 ,103500  ,500,500,500
BEGIN DESCRIPTION:
CANEY CREEK NORTH 204.0
END DESCRIPTION:
XS GIS Cut Line= 3
      3728727.85     10202611.06      3727881.64     10201764.74
      3726652.55     10201800.14
#Sta/Elev= 30
  3803.2  342.67  4036.5  333.24  4128.5  328.46  4361.8  320.76  4609.3  315.22
  4849.7  314.81  4955.8  310.08  4962.8  310.58  4969.9  308.09    4977  308.23
  4991.1  299.87  4995.7  299.24  5004.4   300.1  5013.8  305.98  5023.8  308.86
  5042.5  311.31  5153.9  310.96  5193.9  309.82  5203.9  308.33  5244.9  310.21
    5454  312.56    5474  311.03    5494  312.84    5534  313.84  5834.1  319.98
  5904.2  322.94  5994.2   323.9  6184.3  331.26  6204.3  329.87  6229.6  332.71
#Mann= 4 ,-1 , 0
  3803.2     .17       0  4962.8     .09       0  5042.5     .17       0
  5244.9     .11       0
Bank Sta=4962.8,5042.5
XS Rating Curve= 0 ,0
Exp/Cntr=0.3,0.1

Type RM Length L Ch R = 1 ,103000  ,500,500,500
BEGIN DESCRIPTION:
CANEY CREEK NORTH 203.0
END DESCRIPTION:
XS GIS Cut Line= 3
      3729006.33     10201859.18      3728008.25     10201306.67
      3727221.62     10200744.61
#Sta/Elev= 30
  3859.2  340.76  4063.2  324.43  4179.3  317.72  4304.1  313.28  4531.9  314.31
  4694.5  308.44  4775.8   310.1  4966.2  310.37  4981.9  307.22    4989  299.08
  4994.4  297.24  5003.8  298.02  5012.4   303.1  5018.6   302.8  5033.3  306.67
  5054.2  309.35  5075.1  308.92  5098.4  305.07  5125.5   305.9  5134.1  308.25
  5175.9  305.16  5190.6  305.43  5205.4  308.41  5211.5  307.29  5333.2  310.25
  5527.8  317.01  5643.1  320.97  5879.3  328.37  5885.2  328.32  5966.8  329.74
#Mann= 7 ,-1 , 0
  3859.2     .17       0  4966.2     .09       0  5054.2     .17       0
  5527.8     .11       0  5643.1     .17       0  5879.3     .11       0
  5885.2     .17       0
Bank Sta=4966.2,5054.2
XS Rating Curve= 0 ,0
Exp/Cntr=0.3,0.1

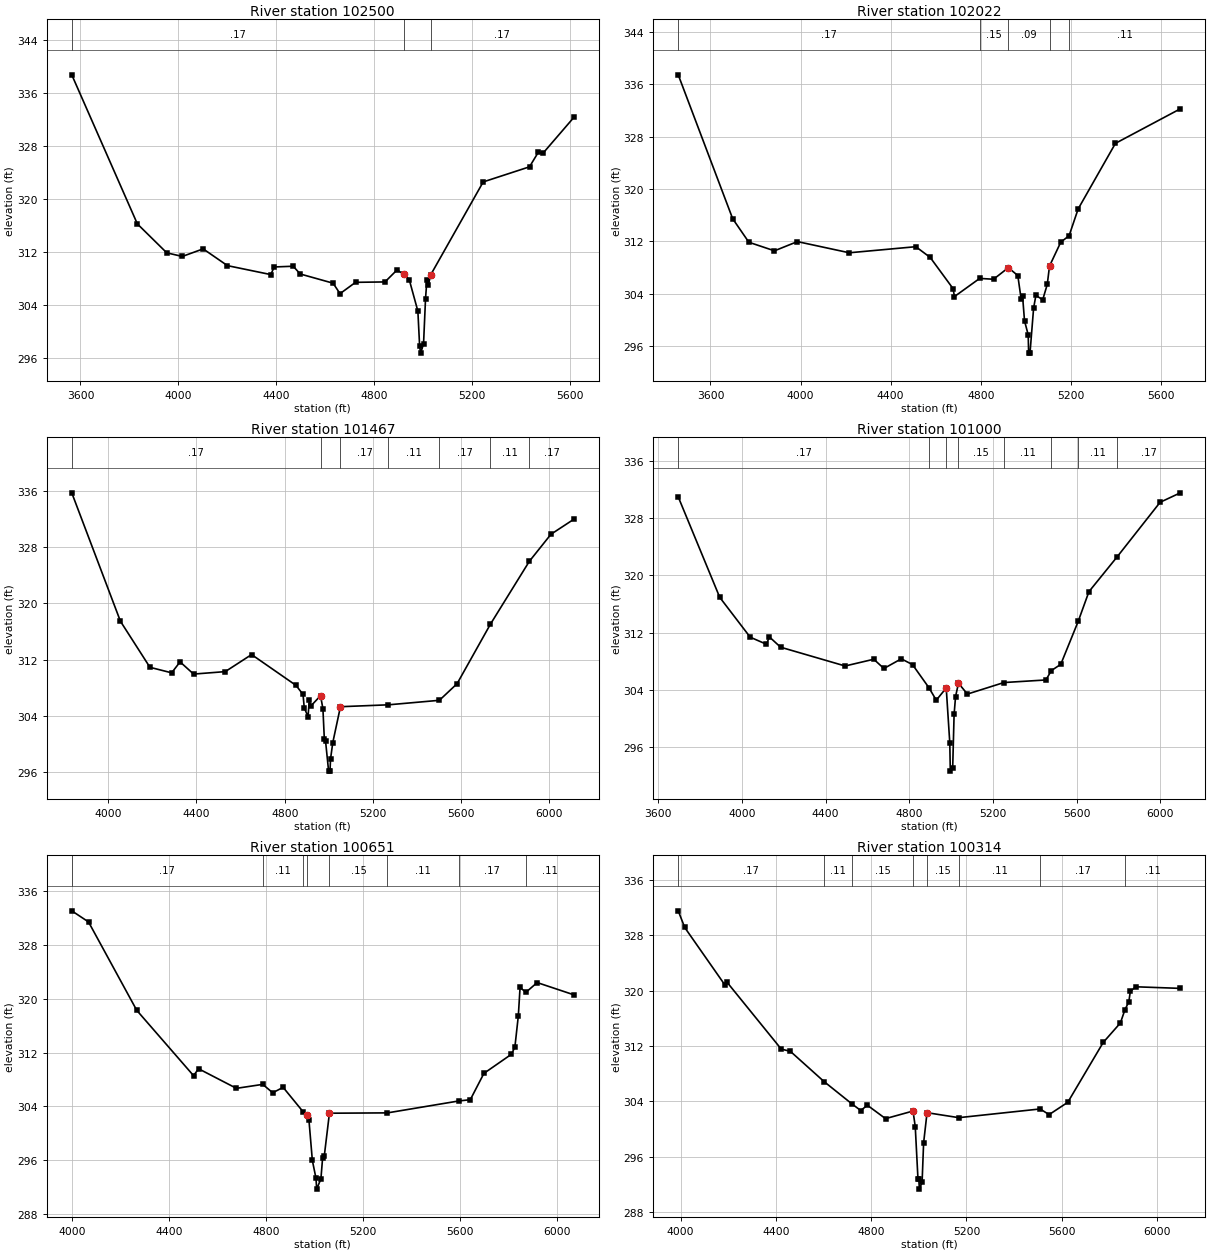
Type RM Length L Ch R = 1 ,102500  ,478,478,478
BEGIN DESCRIPTION:
CANEY CREEK NORTH 202.0
END DESCRIPTION:
XS GIS Cut Line= 3
      3729061.89     10201775.85      3727998.06     10200812.05
      3727421.14     10200592.43
#Sta/Elev= 30
  3564.5  338.78  3832.7  316.27    3953   311.9  4016.5  311.36  4101.7   312.5
    4201  309.97  4378.1  308.62  4392.3  309.77    4470  309.88  4498.4  308.71
  4632.9  307.32  4661.3  305.74  4724.8  307.45  4845.1  307.51  4894.4  309.32
  4922.8  308.65  4944.4  307.84  4979.6   303.1  4986.8  297.78  4990.8  296.76
  5002.8  298.17  5010.9     305  5016.5  307.77  5021.9  307.03  5032.3   308.6
  5246.7  322.61    5436  324.89  5471.5  327.06  5490.9  326.93  5617.3  332.35
#Mann= 3 , 0 , 0
  3564.5     .17       0  4922.8     .09       0  5032.3     .17       0
Bank Sta=4922.8,5032.3
XS Rating Curve= 0 ,0
Exp/Cntr=0.3,0.1

Type RM Length L Ch R = 1 ,102022  ,555,555,555
BEGIN DESCRIPTION:
CANEY CREEK NORTH 201.0
END DESCRIPTION:
XS GIS Cut Line= 3
      3729120.91     10201702.93      3728252.43     10200427.67
      3727572.53      10200334.9
#Sta/Elev= 30
  3457.1  337.45  3698.8  315.44  3770.7  311.84  3884.4  310.53  3986.1  311.94
  4216.5  310.23  4511.9  311.16  4575.7  309.52  4677.4  304.74  4683.4  303.53
  4795.5  306.31  4856.9  306.18  4922.7  307.95  4964.7  306.75  4979.6  303.13
  4985.7  303.68  4994.5  299.82  5010.8  297.69  5012.8  294.88  5018.8  294.88
  5034.9  301.78    5045  303.71  5075.3  303.04  5095.5  305.39  5105.5   308.2
  5155.4  311.85  5192.4  312.84  5232.7  316.94  5398.2  326.97  5686.2  332.25
#Mann= 5 ,-1 , 0
  3457.1     .17       0  4795.5     .15       0  4922.7     .09       0
  5105.5     .17       0  5192.4     .11       0
Bank Sta=4922.7,5105.5
XS Rating Curve= 0 ,0
Exp/Cntr=0.3,0.1

Type RM Length L Ch R = 1 ,101467  ,467,467,467
BEGIN DESCRIPTION:
CANEY CREEK NORTH 200.0
END DESCRIPTION:
XS GIS Cut Line= 3
      3729242.42      10201640.4      3728744.57     10200586.92
       3728196.4      10199620.8
#Sta/Elev= 30
  3834.8  335.68  4055.3  317.46  4189.2  310.92  4287.5  310.14  4325.8  311.69
  4387.1  309.96  4530.6  310.31    4650  312.73  4851.6  308.35  4883.1  307.07
  4888.7  305.18  4905.9  303.91  4911.4  306.28    4918  305.41  4962.5  306.89
  4973.3  305.05  4979.7  300.75  4985.2  300.47  4999.1  296.19  5005.3  296.19
    5008  297.96  5018.1  300.25  5052.7  305.33  5270.3   305.6  5501.3  306.24
  5581.6   308.6  5732.4  317.03  5908.8  325.95    6007   329.8  6110.8  331.93
#Mann= 7 ,-1 , 0
  3834.8     .17       0  4962.5     .09       0  5052.7     .17       0
  5270.3     .11       0  5501.3     .17       0  5732.4     .11       0
  5908.8     .17       0
Bank Sta=4962.5,5052.7
XS Rating Curve= 0 ,0
Exp/Cntr=0.3,0.1

Type RM Length L Ch R = 1 ,101000  ,349,349,349
BEGIN DESCRIPTION:
CANEY CREEK NORTH 199.0
END DESCRIPTION:
XS GIS Cut Line= 3
      3729551.46       10201505.      3729063.96     10200295.55
      3728247.04     10199565.05
#Sta/Elev= 30
    3696  330.95  3894.3  316.94  4039.9  311.38  4117.8  310.39  4131.5  311.42
  4185.4  309.98  4493.7  307.36  4630.7   308.3    4679  307.01  4762.2  308.36
  4815.9  307.55    4894  304.34  4929.4  302.59    4977  304.29    4994  296.63
  4996.5  292.69  5007.9  293.19  5014.6   300.6  5021.6  303.09  5035.5  304.96
  5078.1  303.44  5252.6  305.05  5453.4  305.41  5479.6  306.72  5524.5  307.59
  5607.6  313.57  5659.1  317.73  5794.5  322.61  5999.3   330.2  6095.9  331.52
#Mann= 8 ,-1 , 0
    3696     .17       0    4894     .15       0    4977     .09       0
  5035.5     .15       0  5252.6     .11       0  5479.6     .17       0
  5607.6     .11       0  5794.5     .17       0
Bank Sta=4977,5035.5
XS Rating Curve= 0 ,0
Exp/Cntr=0.3,0.1

Type RM Length L Ch R = 1 ,100651  ,337,337,337
BEGIN DESCRIPTION:
CANEY CREEK NORTH 198.0
END DESCRIPTION:
XS GIS Cut Line= 3
       3730037.2     10200988.91       3729391.2     10200223.61
      3728667.52     10199438.04
#Sta/Elev= 30
  3998.5  333.08  4067.5  331.43  4266.4  318.28  4500.4  308.57  4521.3  309.59
  4677.3  306.68  4785.8  307.27  4826.8  306.02  4869.7  306.83  4953.6  303.13
  4968.5  302.68  4976.3   301.9  4990.2  295.95  5005.1  293.32    5008  291.69
  5025.5  293.22  5032.3  296.25  5039.6  296.69  5060.6  302.98  5299.8  303.03
  5593.4   304.8  5641.3  304.99  5697.5  308.91  5810.9  311.75  5825.1  312.83
  5839.2  317.44  5846.4  321.68  5870.5  320.96  5916.9  322.41  6068.1  320.59
#Mann= 8 ,-1 , 0
  3998.5     .17       0  4785.8     .11       0  4953.6     .15       0
  4968.5     .09       0  5060.6     .15       0  5299.8     .11       0
  5593.4     .17       0  5870.5     .11       0
Bank Sta=4968.5,5060.6
XS Rating Curve= 0 ,0
Exp/Cntr=0.3,0.1

Type RM Length L Ch R = 1 ,100314  ,354,354,354
BEGIN DESCRIPTION:
Mapping XS 43936501
END DESCRIPTION:
XS GIS Cut Line= 3
      3730106.69     10200938.28      3729629.59     10200048.06
      3728771.35     10199363.05
#Sta/Elev= 30
    3990  331.53  4017.2  329.12    4187  320.76  4192.7   321.3  4422.6  311.54
  4460.8  311.22  4602.5  306.84  4719.7  303.61  4756.4  302.66    4784  303.43
  4860.4  301.49  4975.8  302.59  4985.2  300.32  4996.6  292.76    5000  292.76
  5002.6   291.3  5013.9  292.29  5020.3     298  5034.7  302.35  5168.1  301.63
  5509.6  302.89  5547.1  302.07  5625.6  303.85  5774.5  312.51  5846.5  315.32
  5865.7  317.24  5881.8  318.37  5888.2  319.88  5910.6  320.55  6098.1  320.32
#Mann= 8 ,-1 , 0
    3990     .17       0  4602.5     .11       0  4719.7     .15       0
  4975.8     .09       0  5034.7     .15       0  5168.1     .11       0
  5509.6     .17       0  5865.7     .11       0
Bank Sta=4975.8,5034.7
XS Rating Curve= 0 ,0
Exp/Cntr=0.3,0.1