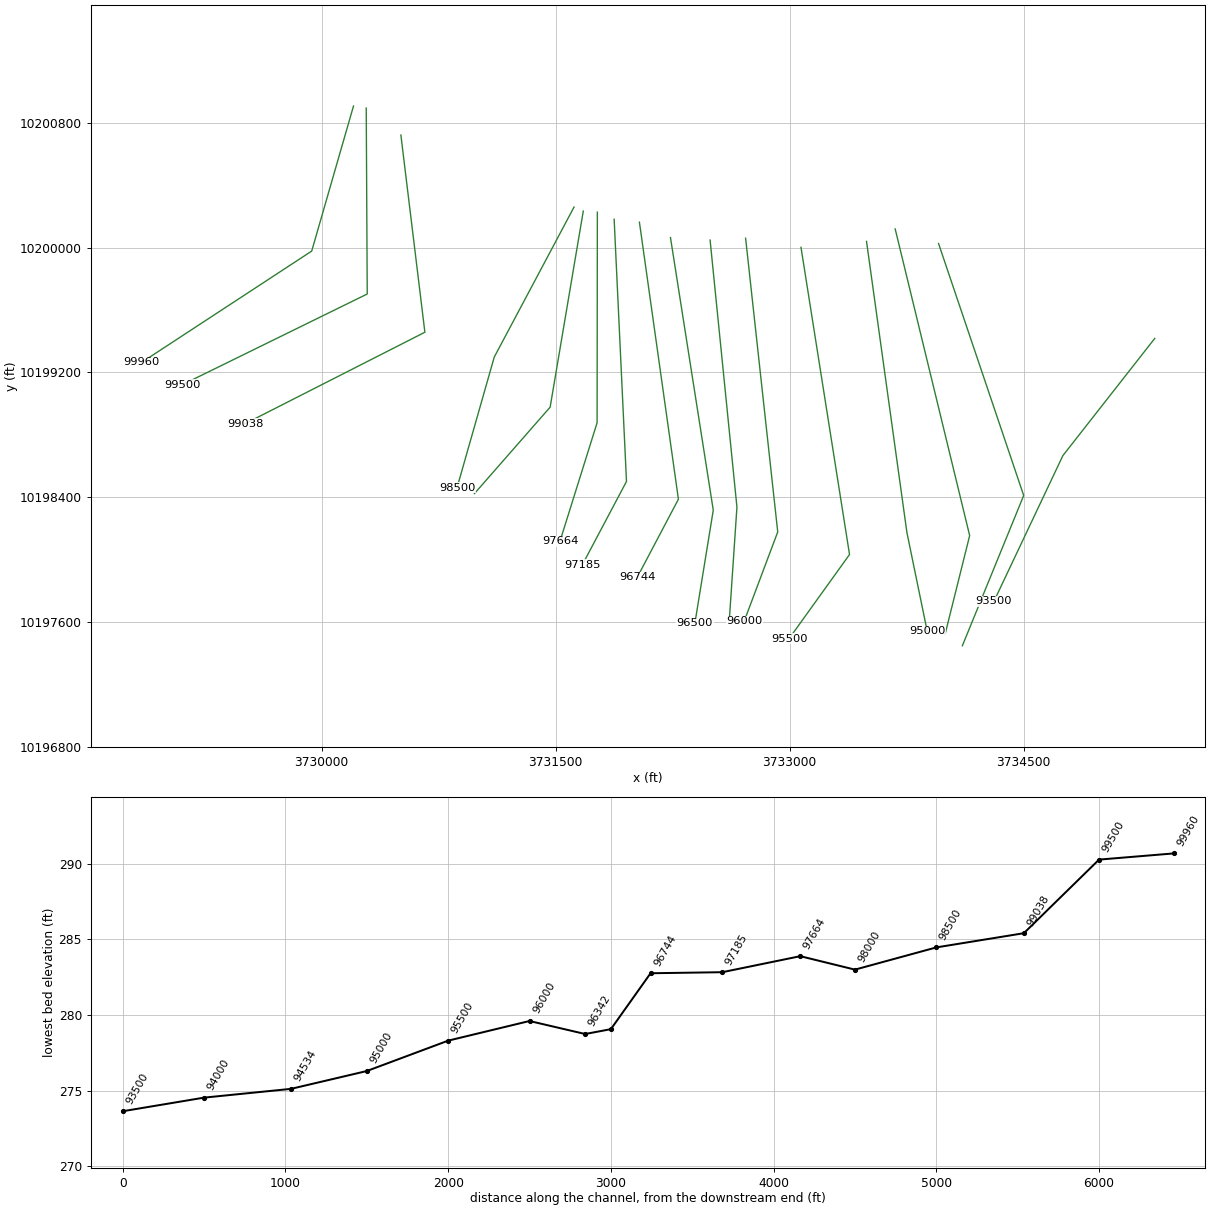
HEC-RAS study CANEY CREEK NORTH.prj: CANEY CREEK NORTH Base Level Engineering

--- CANEY CREEK NORTH.g01 (geometry) --- (continued)

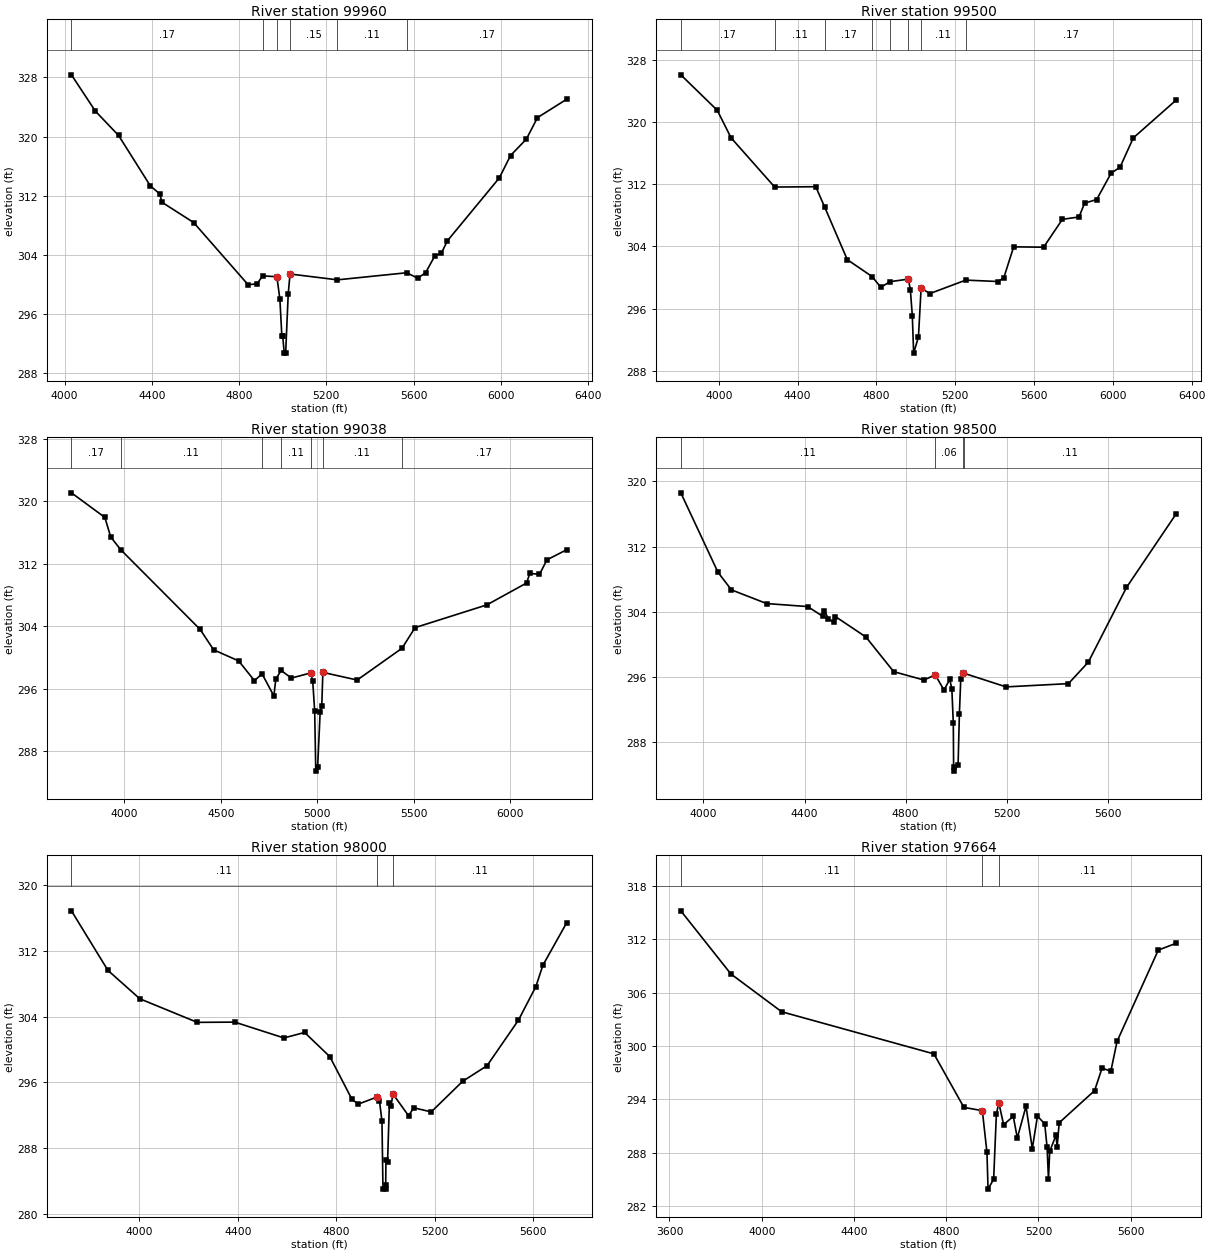
Type RM Length L Ch R = 1 ,99960   ,460,460,460
BEGIN DESCRIPTION:
CANEY CREEK NORTH 197.0
END DESCRIPTION:
XS GIS Cut Line= 3
      3730203.95     10200909.35      3729935.98     10199978.65
      3728846.72     10199265.23
#Sta/Elev= 30
  4031.5  328.36  4141.4  323.44  4247.7  320.15  4392.8  313.35  4436.9  312.23
    4446  311.12  4591.6  308.37  4841.4  299.95    4883  300.07  4907.4  301.15
  4973.3  301.03  4987.1  297.98  4996.1  293.01    5000  293.01  5006.9  290.69
  5013.5  290.69  5025.3  298.72  5033.6   301.4  5250.9  300.61  5568.5  301.57
  5619.3  300.83  5655.2  301.58  5697.7  303.87    5727   304.2  5754.9  305.89
  5993.1  314.41  6044.4  317.44  6116.8  319.65    6168  322.57  6302.1  325.06
#Mann= 6 ,-1 , 0
  4031.5     .17       0  4907.4     .15       0  4973.3     .09       0
  5033.6     .15       0  5250.9     .11       0  5568.5     .17       0
Bank Sta=4973.3,5033.6
XS Rating Curve= 0 ,0
Exp/Cntr=0.3,0.1

Type RM Length L Ch R = 1 ,99500   ,462,462,462
BEGIN DESCRIPTION:
CANEY CREEK NORTH 196.0
END DESCRIPTION:
XS GIS Cut Line= 3
      3730285.55     10200896.06      3730291.96     10199703.38
      3729105.85     10199121.16
#Sta/Elev= 30
  3807.3  326.07  3992.3  321.51  4062.3  317.97  4283.6  311.64  4492.3  311.68
  4537.5  309.06  4652.3   302.3    4778  300.13  4822.3  298.75  4869.3  299.47
  4962.3   299.8  4972.3  298.44  4982.3  295.09    4989  290.28  5013.4  292.36
  5026.9  298.65  5071.4  297.94  5253.5  299.67  5416.7  299.49  5446.2  299.94
  5496.7  303.95  5648.6   303.9  5744.1  307.49  5828.5  307.79  5856.5  309.57
    5918  310.03  5991.4  313.43  6036.4  314.18  6103.9  317.96  6321.3  322.82
#Mann= 8 ,-1 , 0
  3807.3     .17       0  4283.6     .11       0  4537.5     .17       0
    4778     .11       0  4869.3     .15       0  4962.3     .06       0
  5026.9     .11       0  5253.5     .17       0
Bank Sta=4962.3,5026.9
XS Rating Curve= 0 ,0
Exp/Cntr=0.3,0.1

Type RM Length L Ch R = 1 ,99038   ,538,538,538
BEGIN DESCRIPTION:
CANEY CREEK NORTH 195.0
END DESCRIPTION:
XS GIS Cut Line= 3
      3730507.65     10200723.13      3730661.57     10199458.06
      3729508.37     10198871.06
#Sta/Elev= 30
  3725.6  321.09  3898.9  317.94  3929.1  315.44  3980.7  313.81  4392.5  303.59
  4463.1  300.96  4592.8  299.54  4674.5  297.01  4714.1  297.88  4775.3  295.05
  4785.4   297.2  4812.7  298.32    4866  297.34  4966.7     298  4976.8  296.94
  4986.9  293.13  4992.6  285.41  5002.2  285.91  5015.4  293.02  5023.7  293.76
  5029.3  298.07  5207.3  297.09  5439.6  301.16  5507.5  303.81  5879.4  306.72
  6085.8  309.53  6102.4  310.77  6152.5  310.63  6191.4   312.5    6294   313.8
#Mann= 7 ,-1 , 0
  3725.6     .17       0  3980.7     .11       0  4714.1     .15       0
  4812.7     .11       0  4966.7     .06       0  5029.3     .11       0
  5439.6     .17       0
Bank Sta=4966.7,5029.3
XS Rating Curve= 0 ,0
Exp/Cntr=0.3,0.1

Type RM Length L Ch R = 1 ,98500   ,500,500,500
BEGIN DESCRIPTION:
CANEY CREEK NORTH 194.0
END DESCRIPTION:
XS GIS Cut Line= 3
      3731617.85     10200261.07      3731106.36     10199298.87
      3730867.85     10198461.06
#Sta/Elev= 30
  3910.3   318.6  4057.5  308.85  4110.6   306.7    4250  305.02  4412.6  304.65
  4472.9  303.44  4478.5  304.15  4494.9  303.12  4516.8   302.7  4522.5  303.42
    4643  300.92  4752.9  296.67  4872.9  295.64  4917.4  296.28  4952.2   294.4
  4974.9  295.74  4983.3  294.52    4989  290.35  4990.2  284.97  4990.7  284.47
  5007.9  285.21  5013.1  291.51  5018.5   295.8  5028.9   296.5  5031.4  296.47
  5197.9   294.8  5444.8   295.2  5523.5  297.84  5674.5  306.99  5871.1  316.02
#Mann= 4 ,-1 , 0
  3910.3     .11       0  4917.4     .06       0  5028.9     .15       0
  5031.4     .11       0
Bank Sta=4917.4,5028.9
XS Rating Curve= 0 ,0
Exp/Cntr=0.3,0.1

Type RM Length L Ch R = 1 ,98000   ,336,336,336
BEGIN DESCRIPTION:
CANEY CREEK NORTH 193.0
END DESCRIPTION:
XS GIS Cut Line= 3
      3731677.09     10200235.33      3731464.64     10198977.45
      3730979.16     10198422.81
#Sta/Elev= 30
  3724.3  316.91  3872.7  309.65  4002.4  306.19  4235.7  303.32  4387.8  303.35
    4588  301.42  4671.8  302.09  4774.4  299.14  4864.5  293.93  4890.2  293.36
  4965.9  294.22    4976  293.77  4986.2  291.28  4990.3     283  5000.9     283
  5001.4   283.5  5002.3  286.58  5008.9   286.3  5016.5  293.54  5023.2  293.13
  5030.7   294.6  5094.3  291.94  5115.2  292.91  5186.4  292.41  5314.1  296.14
  5413.2  298.04  5540.4  303.57  5611.6  307.68  5640.1  310.28  5737.1  315.47
#Mann= 3 , 0 , 0
  3724.3     .11       0  4965.9     .06       0  5030.7     .11       0
Bank Sta=4965.9,5030.7
XS Rating Curve= 0 ,0
Exp/Cntr=0.3,0.1

Type RM Length L Ch R = 1 ,97664   ,479,479,479
BEGIN DESCRIPTION:
CANEY CREEK NORTH 192.0
END DESCRIPTION:
XS GIS Cut Line= 3
      3731767.36     10200228.37      3731765.71     10198877.67
      3731527.77     10198117.22
#Sta/Elev= 30
  3649.3  315.21  3866.6   308.1  4086.6  303.85  4746.6  299.11  4876.6  293.09
  4956.6  292.72  4976.6  288.02  4981.3  283.89  5005.6     285  5017.4   292.3
  5027.9  293.63  5048.8  291.14  5090.7  292.08  5108.2  289.64  5145.9  293.22
  5173.2  288.44  5195.5  292.11    5227  291.23  5237.4  288.58  5243.3     285
  5248.6  288.14  5275.8  289.94    5281  288.65  5289.8  291.36  5443.3  294.98
  5475.8  297.53  5513.5  297.14  5540.7  300.52  5719.4  310.79  5796.8  311.56
#Mann= 3 , 0 , 0
  3649.3     .11       0  4956.6     .06       0  5027.9     .11       0
Bank Sta=4956.6,5027.9
XS Rating Curve= 0 ,0
Exp/Cntr=0.3,0.1

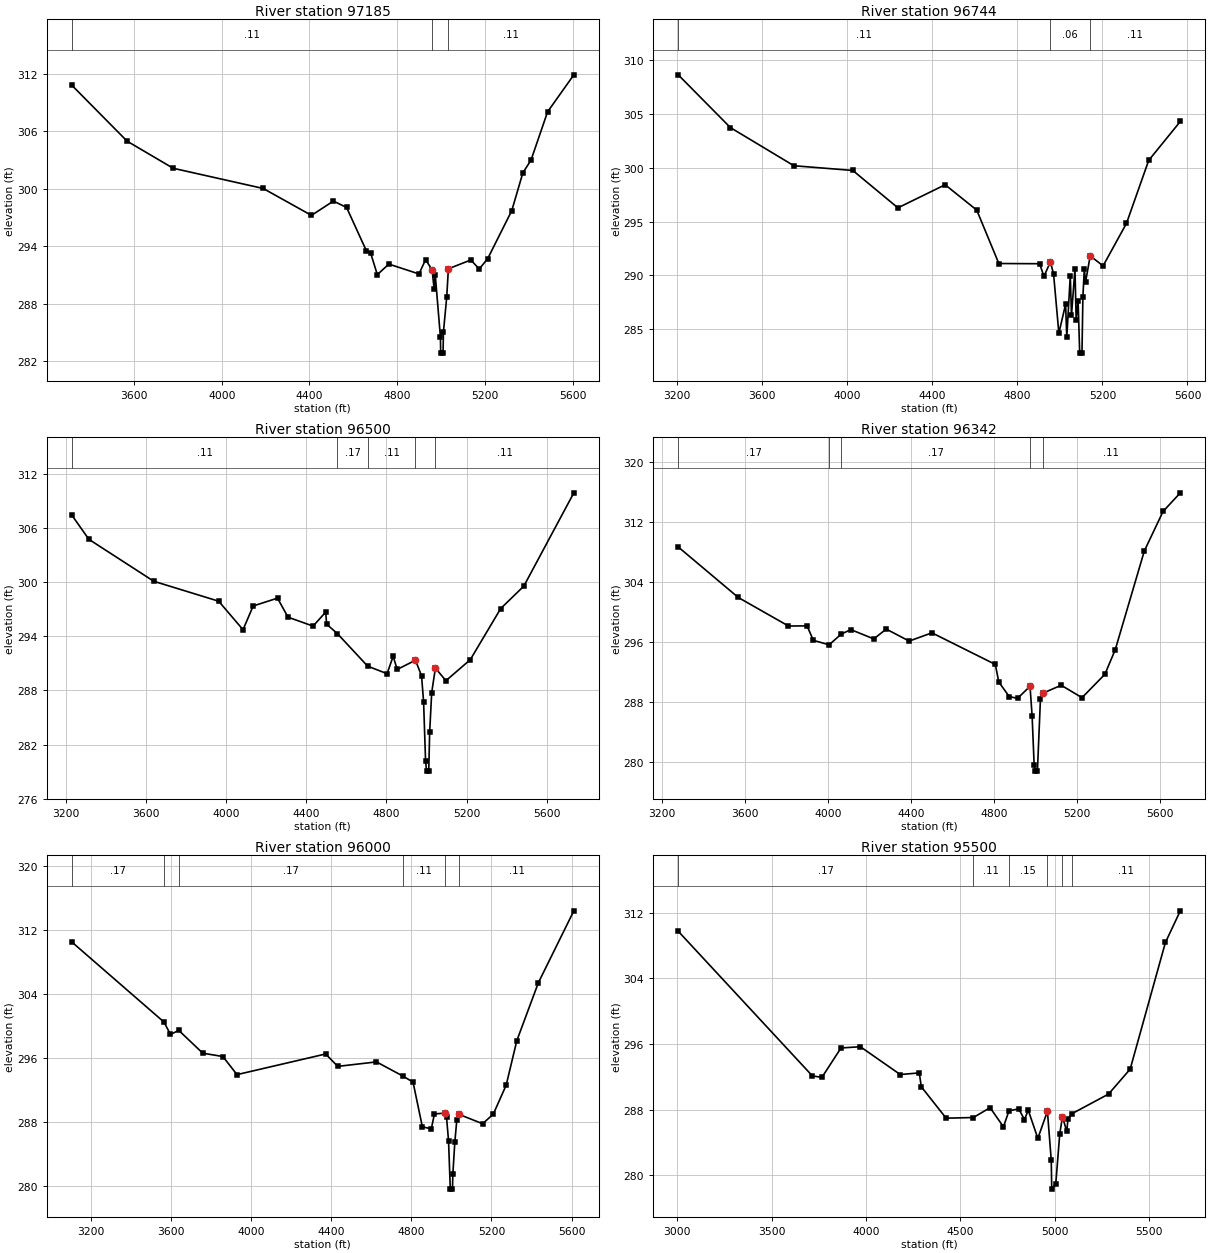
Type RM Length L Ch R = 1 ,97185   ,441,441,441
BEGIN DESCRIPTION:
CANEY CREEK NORTH 191.0
END DESCRIPTION:
XS GIS Cut Line= 3
        3731875.      10200183.2      3731954.14     10198500.86
      3731670.57      10197965.3
#Sta/Elev= 30
  3315.8  310.82  3568.2  304.97  3778.4  302.14  4188.9  300.03  4409.1  297.22
  4509.2  298.71  4569.3  298.05  4659.4  293.53  4679.4  293.26  4709.5  291.03
  4762.2  292.13  4899.7   291.1  4929.7   292.6  4959.7  291.51  4968.7   289.5
  4973.7  291.04  4997.4   284.5  4998.7  282.83  5009.4  282.83  5011.1  285.03
  5026.1  288.67  5033.7  291.64  5136.1  292.56  5174.4  291.62  5212.8  292.69
  5322.8  297.71  5373.2  301.65  5410.8     303  5486.3  308.04    5606   311.9
#Mann= 3 , 0 , 0
  3315.8     .11       0  4959.7     .06       0  5033.7     .11       0
Bank Sta=4959.7,5033.7
XS Rating Curve= 0 ,0
Exp/Cntr=0.3,0.1

Type RM Length L Ch R = 1 ,96744   ,244,244,244
BEGIN DESCRIPTION:
Mapping XS ee1e19f2
END DESCRIPTION:
XS GIS Cut Line= 3
      3732036.99     10200163.95      3732287.01     10198386.86
      3732022.97     10197885.77
#Sta/Elev= 30
  3205.4  308.66  3450.7  303.75  3749.3   300.2  4026.3  299.76  4238.4  296.28
  4460.5  298.43  4609.1  296.07    4713   291.1  4904.9  291.08  4925.1   289.9
  4955.3  291.24  4970.3  290.15  4995.3  284.61  5026.9  287.31  5032.6  284.24
    5049  289.97  5054.6  286.27    5071   290.6  5076.6  285.87  5085.7  287.63
  5093.3  282.76    5104  282.76  5108.3     288    5115  290.61  5120.7  289.37
  5142.7  291.81  5203.2  290.88  5313.3  294.84  5417.8   300.7  5566.4  304.32
#Mann= 3 , 0 , 0
  3205.4     .11       0  4955.3     .06       0  5142.7     .11       0
Bank Sta=4955.3,5142.7
XS Rating Curve= 0 ,0
Exp/Cntr=0.3,0.1

Type RM Length L Ch R = 1 ,96500   ,158,158,158
BEGIN DESCRIPTION:
CANEY CREEK NORTH 190.0
END DESCRIPTION:
XS GIS Cut Line= 3
      3732236.11     10200065.21      3732510.49      10198316.7
      3732392.61     10197591.02
#Sta/Elev= 30
  3230.1  307.44  3315.3  304.75  3639.2   300.1  3963.1  297.89  4084.6  294.73
  4135.2  297.36  4256.6  298.23    4309  296.12  4434.2  295.13  4496.9  296.68
  4501.9  295.34  4555.7  294.29  4706.5  290.69  4803.3  289.86  4833.6  291.78
  4853.9  290.33    4945  291.35  4975.3  289.62  4985.5  286.76  4995.3  280.22
  5000.3  279.06  5011.2  279.06  5015.8  283.38    5026  287.77  5044.4  290.48
  5096.9  289.08  5218.5  291.41  5370.4  297.08  5485.6  299.56  5735.2   309.9
#Mann= 5 ,-1 , 0
  3230.1     .11       0  4555.7     .17       0  4706.5     .11       0
    4945     .06       0  5044.4     .11       0
Bank Sta=4945,5044.4
XS Rating Curve= 0 ,0
Exp/Cntr=0.3,0.1

Type RM Length L Ch R = 1 ,96342   ,342,342,342
BEGIN DESCRIPTION:
Mapping XS 3875999e
END DESCRIPTION:
XS GIS Cut Line= 3
      3732490.11     10200049.36      3732662.21     10198336.38
      3732615.11     10197637.97
#Sta/Elev= 30
  3278.4  308.68  3568.1  301.93  3810.2  298.12  3899.8  298.14    3930  296.21
  4006.1  295.61  4064.5  297.04    4111  297.64  4221.4   296.4  4281.7  297.71
  4392.3  296.11    4502  297.21  4807.8  292.99  4824.4  290.65  4874.7   288.7
  4914.9  288.46  4975.2  290.07  4985.2  286.11  4995.1  279.52  4999.9  278.74
  5010.8  278.74  5025.4  288.38  5035.4  289.13  5125.6  290.21  5225.8  288.55
  5336.1  291.67  5386.2  294.96  5526.5  308.15  5616.7  313.42    5700  315.91
#Mann= 5 ,-1 , 0
  3278.4     .17       0  4006.1     .11       0  4064.5     .17       0
  4975.2     .06       0  5035.4     .11       0
Bank Sta=4975.2,5035.4
XS Rating Curve= 0 ,0
Exp/Cntr=0.3,0.1

Type RM Length L Ch R = 1 ,96000   ,500,500,500
BEGIN DESCRIPTION:
CANEY CREEK NORTH 189.0
END DESCRIPTION:
XS GIS Cut Line= 3
      3732717.85     10200061.07      3732923.81       10198177.
      3732708.85     10197604.74
#Sta/Elev= 30
  3104.7  310.49    3565  300.48  3597.6  298.93  3638.9  299.44  3758.6  296.59
  3859.2  296.17  3929.6  293.91  4372.2  296.49  4432.6  294.94  4625.9   295.5
  4759.2  293.71  4808.5  292.97  4855.1  287.38  4899.7  287.14  4915.4     289
  4965.7  289.09  4975.8  288.56  4985.8  285.61  4994.5   279.6  5005.4   279.6
  5007.2  281.46    5017  285.45  5026.8  288.19  5038.4  288.94  5155.9  287.77
  5209.3  288.98  5273.4  292.59  5326.8  298.17  5434.1  305.39  5611.3  314.38
#Mann= 6 ,-1 , 0
  3104.7     .17       0    3565     .11       0  3638.9     .17       0
  4759.2     .11       0  4965.7     .06       0  5038.4     .11       0
Bank Sta=4965.7,5038.4
XS Rating Curve= 0 ,0
Exp/Cntr=0.3,0.1

Type RM Length L Ch R = 1 ,95500   ,500,500,500
BEGIN DESCRIPTION:
CANEY CREEK NORTH 188.0
END DESCRIPTION:
XS GIS Cut Line= 3
      3733072.92     10200002.66       3733384.1     10198032.08
      3732996.55      10197492.3
#Sta/Elev= 30
    3005  309.74  3715.3  292.11  3765.9  291.92  3867.1  295.51  3969.8  295.66
    4181  292.27    4282  292.47  4292.3  290.79    4424  286.95  4568.3  287.03
  4656.8  288.23  4727.7   285.9  4756.9  287.84  4808.7  288.09    4839  286.77
    4859  287.92  4909.9  284.49  4960.5  287.79  4980.8  281.85  4983.5   278.3
  5004.8  278.93  5025.9  285.05  5040.4  287.14  5062.8  285.33  5069.8  286.87
  5090.7   287.5  5284.4  289.89  5398.9  292.93  5585.6  308.37  5664.5  312.23
#Mann= 6 ,-1 , 0
    3005     .17       0  4568.3     .11       0  4756.9     .15       0
  4960.5     .09       0  5040.4     .15       0  5090.7     .11       0
Bank Sta=4960.5,5040.4
XS Rating Curve= 0 ,0
Exp/Cntr=0.3,0.1

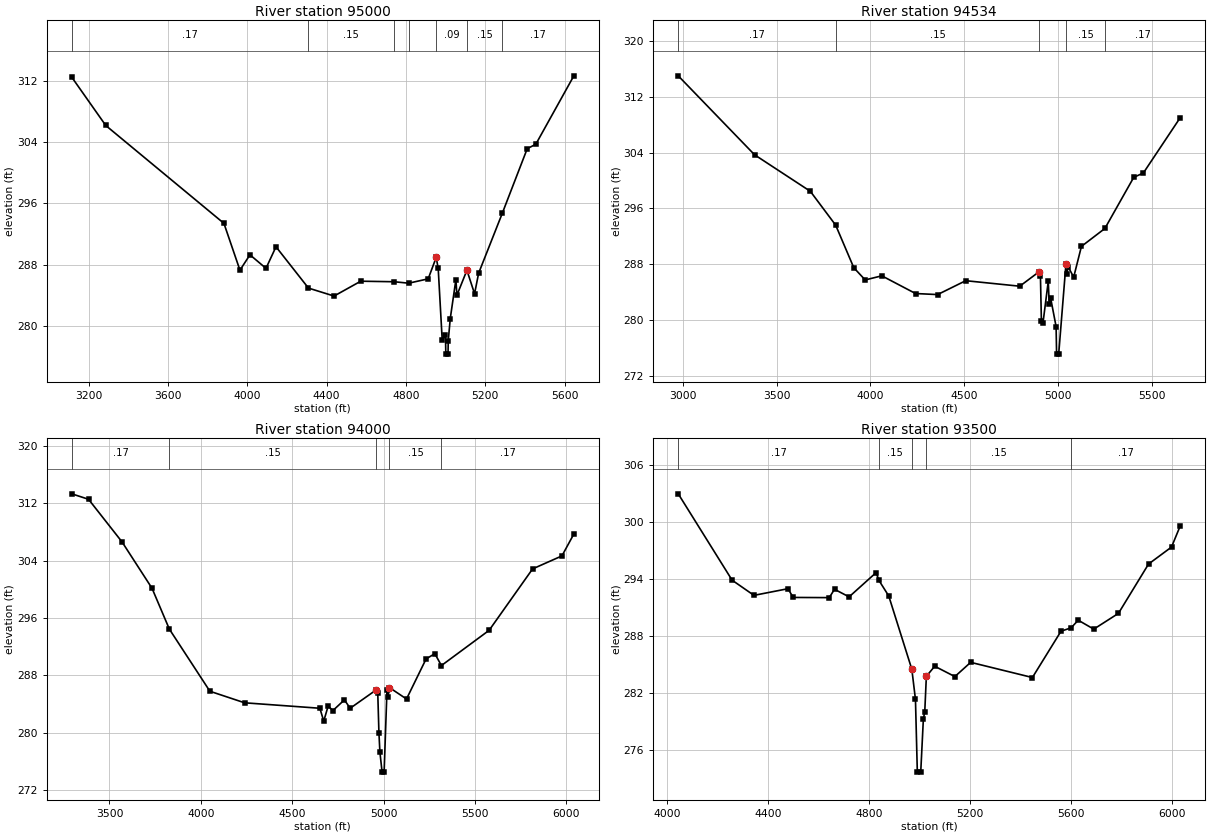
Type RM Length L Ch R = 1 ,95000   ,466,466,466
BEGIN DESCRIPTION:
CANEY CREEK NORTH 187.0
END DESCRIPTION:
XS GIS Cut Line= 3
      3733493.06     10200040.86       3733751.9     10198173.72
      3733881.95     10197540.85
#Sta/Elev= 30
    3115  312.48  3286.4  306.17  3882.1  293.38  3962.8  287.26  4013.3  289.27
  4094.1   287.5  4144.5  290.32  4308.2  284.92  4437.3  283.88  4571.8  285.82
  4740.1  285.75  4813.4  285.56  4911.8  286.13  4952.2  288.93  4962.3  287.49
  4982.5  278.12  4998.8  278.81  5000.7  276.29  5011.8  276.29  5012.9  278.04
  5023.1  280.94  5051.5  286.03  5056.6  283.98    5107  287.25  5145.6  284.18
    5166  286.86    5286  294.74  5411.1  303.14  5454.4  303.72  5646.1  312.66
#Mann= 7 ,-1 , 0
    3115     .17       0  4308.2     .15       0  4740.1     .11       0
  4813.4     .15       0  4952.2     .09       0    5107     .15       0
    5286     .17       0
Bank Sta=4952.2,5107
XS Rating Curve= 0 ,0
Exp/Cntr=0.3,0.1

Type RM Length L Ch R = 1 ,94534   ,534,534,534
BEGIN DESCRIPTION:
CANEY CREEK NORTH 186.0
END DESCRIPTION:
XS GIS Cut Line= 3
      3733676.72     10200120.87       3734154.3     10198153.61
      3733996.53     10197520.05
#Sta/Elev= 30
  2975.6  315.02  3382.5   303.7    3680  298.46  3815.2   293.6  3911.8   287.5
  3972.5  285.75  4061.2  286.34  4241.1   283.8  4358.7  283.65  4508.7  285.64
  4796.8  284.85  4899.7  286.92    4907  286.31  4912.1   279.9  4920.3  279.51
  4948.7  285.55  4953.9  282.27  4961.4  283.15  4990.5  279.07  4993.2  275.11
  5004.3  275.11    5043     288  5048.2  286.63  5054.1  287.67  5084.3  286.15
  5125.6  290.56  5250.7  293.13  5404.5  300.46    5456  301.09  5652.9  309.04
#Mann= 5 ,-1 , 0
  2975.6     .17       0  3815.2     .15       0  4899.7     .09       0
    5043     .15       0  5250.7     .17       0
Bank Sta=4899.7,5043
XS Rating Curve= 0 ,0
Exp/Cntr=0.3,0.1

Type RM Length L Ch R = 1 ,94000   ,500,500,500
BEGIN DESCRIPTION:
CANEY CREEK NORTH 185.0
END DESCRIPTION:
XS GIS Cut Line= 3
      3733954.87     10200026.97      3734500.71     10198410.65
      3734107.65     10197447.14
#Sta/Elev= 30
    3294  313.31  3385.7  312.55  3569.2   306.6    3733  300.15  3827.8  294.46
  4049.6   285.8  4239.6  284.19  4651.2  283.43  4672.4  281.64  4696.4  283.73
  4722.6  283.11  4785.5   284.6    4817  283.43  4957.3  285.95  4967.9  285.59
  4974.3  280.02  4979.6  277.34  4991.6  274.53  5002.7  274.53  5018.3  285.95
  5023.7  284.99  5031.9  286.31  5125.2  284.72  5232.2   290.3  5280.2  291.04
  5316.1  289.38  5577.1  294.29    5815  302.85  5975.4  304.66  6040.6  307.71
#Mann= 5 ,-1 , 0
    3294     .17       0  3827.8     .15       0  4957.3     .09       0
  5031.9     .15       0  5316.1     .17       0
Bank Sta=4957.3,5031.9
XS Rating Curve= 0 ,0
Exp/Cntr=0.3,0.1

Type RM Length L Ch R = 1 ,93500   ,500,500,500
BEGIN DESCRIPTION:
CANEY CREEK NORTH 184.0
END DESCRIPTION:
XS GIS Cut Line= 3
      3735341.06     10199418.49      3734751.92     10198666.62
      3734309.59     10197731.01
#Sta/Elev= 30
  4044.8  302.96  4258.3  293.86    4345  292.26  4479.7  292.96  4500.5  292.04
  4643.4  292.02  4664.2   292.9    4722   292.1  4829.2  294.66    4840  293.85
  4879.3  292.19  4970.7  284.47  4985.1  281.29  4992.5  273.63    5006  273.63
  5016.4  279.21    5022  280.01  5028.3  283.73  5061.4  284.79  5141.3   283.7
    5204   285.2  5448.6   283.6    5562  288.48    5602  288.84  5630.3  289.64
  5691.9   288.7  5789.6  290.36    5909  295.56    6000  297.35  6034.9   299.6
#Mann= 5 ,-1 , 0
  4044.8     .17       0    4840     .15       0  4970.7     .09       0
  5028.3     .15       0    5602     .17       0
Bank Sta=4970.7,5028.3
XS Rating Curve= 0 ,0
Exp/Cntr=0.3,0.1