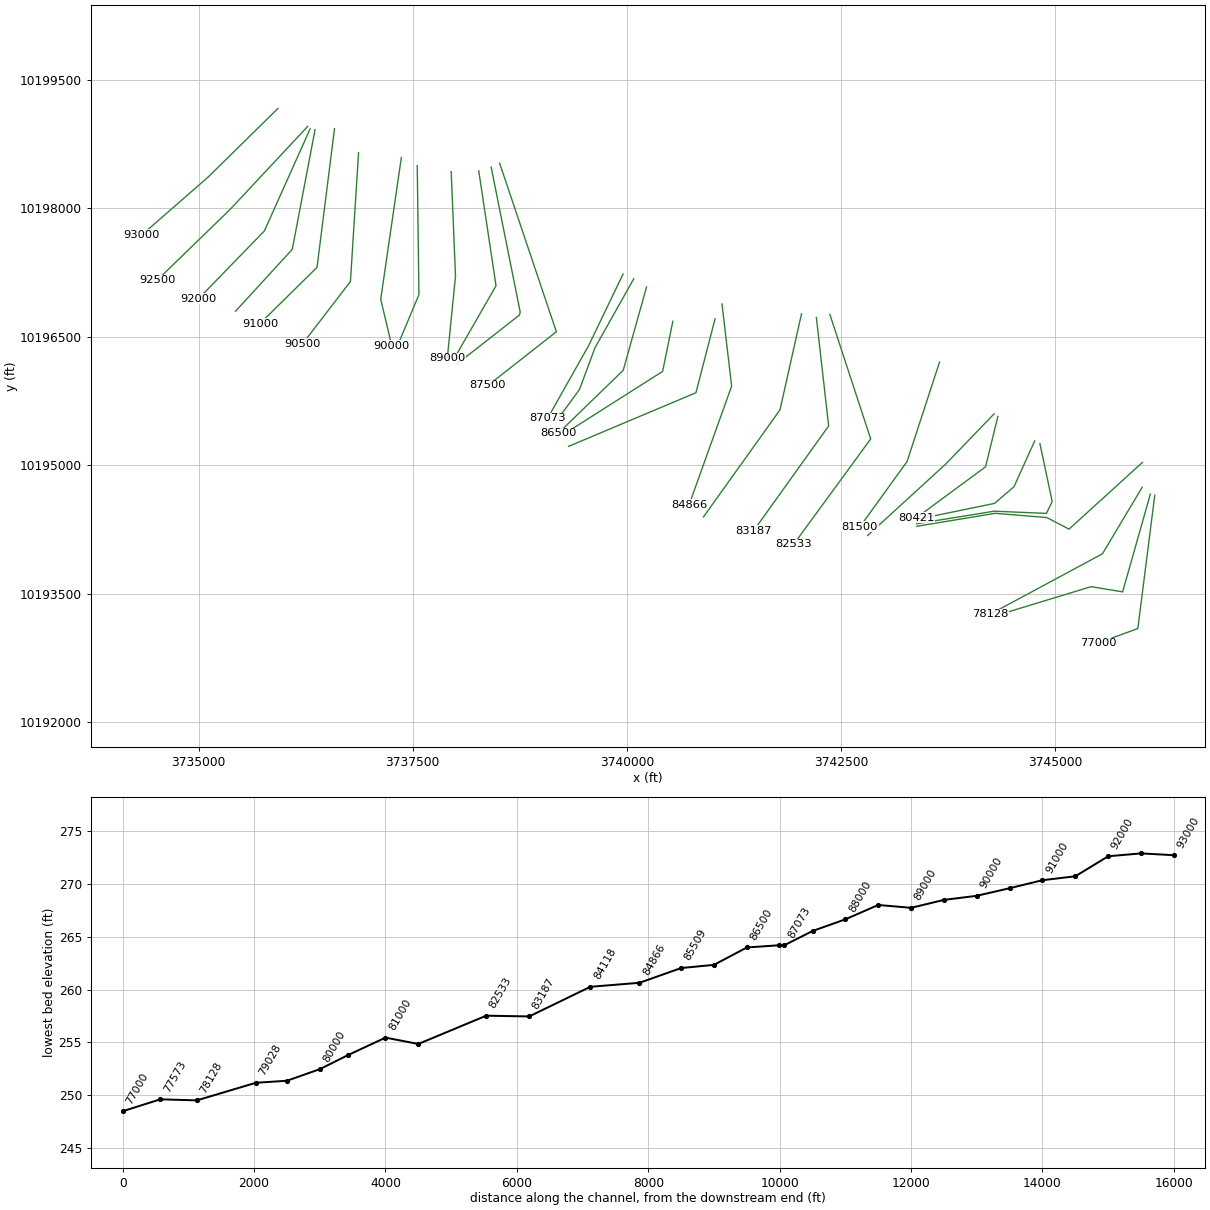
HEC-RAS study CANEY CREEK NORTH.prj: CANEY CREEK NORTH Base Level Engineering

--- CANEY CREEK NORTH.g01 (geometry) --- (continued)

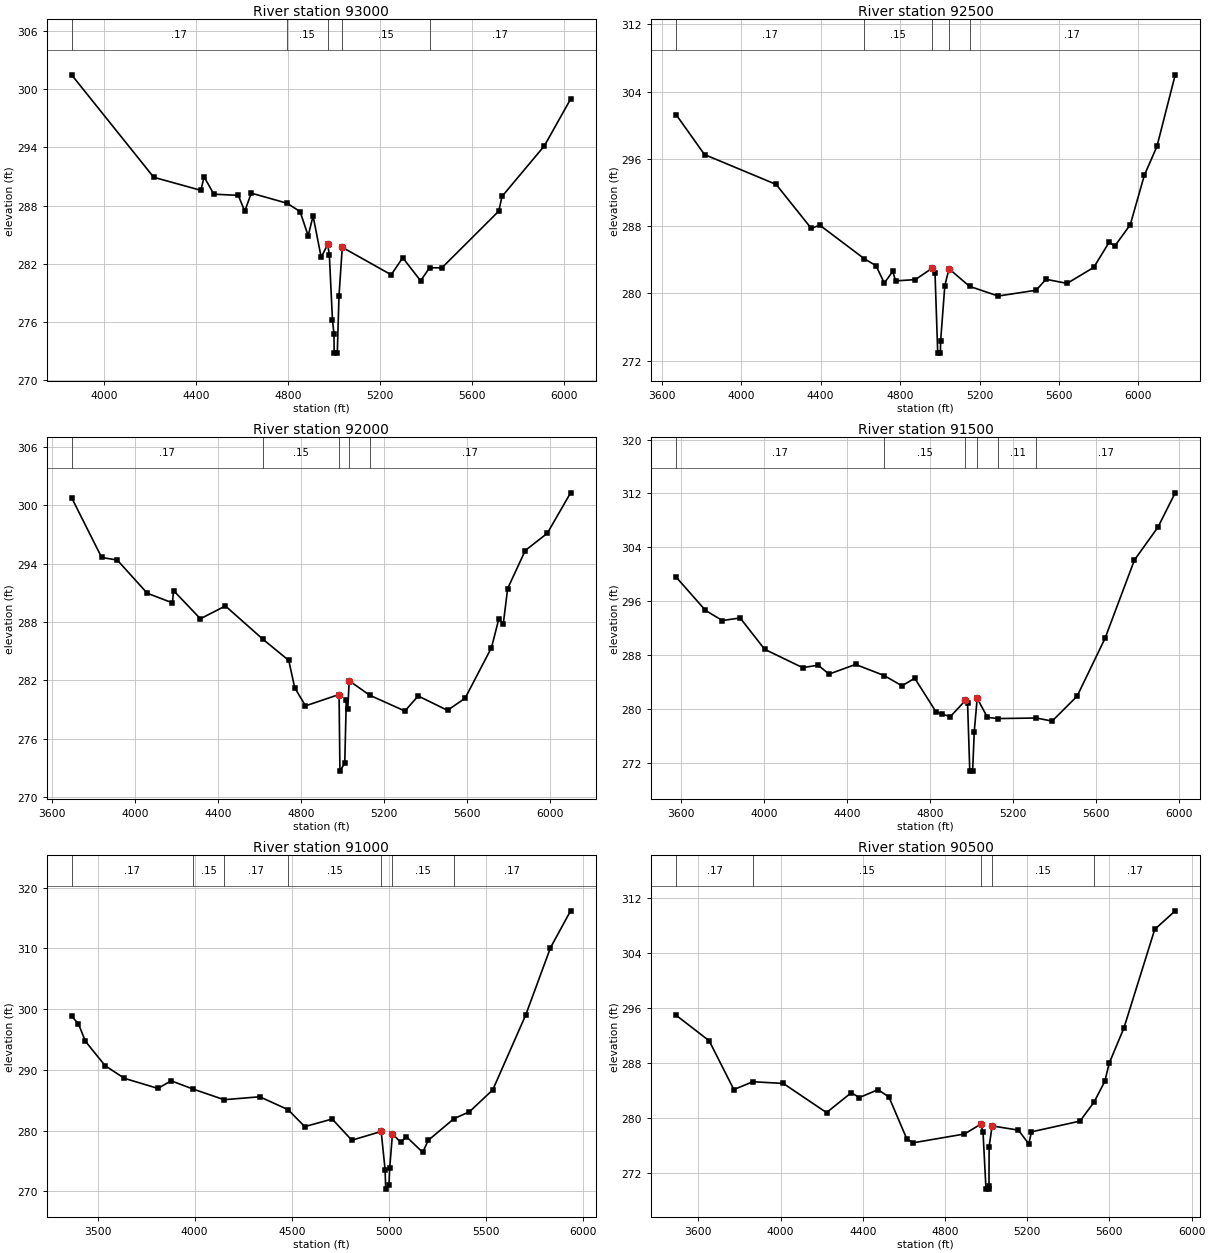
Type RM Length L Ch R = 1 ,93000   ,500,500,500
BEGIN DESCRIPTION:
CANEY CREEK NORTH 183.0
END DESCRIPTION:
XS GIS Cut Line= 3
      3735926.97     10199166.83      3735113.61     10198366.62
      3734338.47     10197689.72
#Sta/Elev= 30
    3859  301.51    4216  290.92    4421  289.57  4435.2  290.96  4477.6  289.17
  4583.8  289.05    4612  287.41  4640.3  289.28  4795.4  288.24  4852.5  287.38
  4887.8  284.87  4909.1  286.92  4944.4  282.64  4972.6  283.97  4979.8  282.92
  4993.5  276.13    5000  274.74  5000.8  272.74  5014.4  272.74  5021.8  278.63
    5036  283.68  5248.7  280.84    5299   282.6  5376.8  280.22  5415.9  281.57
  5468.9  281.55  5716.7  287.42  5730.9  288.94    5915  294.17  6029.1     299
#Mann= 5 ,-1 , 0
    3859     .17       0  4795.4     .15       0  4972.6     .09       0
    5036     .15       0  5415.9     .17       0
Bank Sta=4972.6,5036
XS Rating Curve= 0 ,0
Exp/Cntr=0.3,0.1

Type RM Length L Ch R = 1 ,92500   ,500,500,500
BEGIN DESCRIPTION:
CANEY CREEK NORTH 182.0
END DESCRIPTION:
XS GIS Cut Line= 3
      3736273.55     10198956.39      3735367.91     10197986.75
      3734517.88      10197161.1
#Sta/Elev= 30
  3673.2  301.25  3815.6  296.52  4176.1  292.97    4353  287.74  4395.5  288.13
  4620.1  284.13  4678.8  283.31  4720.8  281.24  4763.3  282.64  4777.5   281.5
  4876.7  281.65  4961.7  283.01  4975.8  282.46  4989.6  272.91  5003.2  272.91
    5004  274.31  5025.3  280.94  5046.4  282.94  5149.6  280.85  5293.9   279.7
    5485  280.39  5534.4  281.69  5640.6   281.2  5774.9   283.1  5852.6   286.1
  5880.9  285.64  5958.8  288.18  6029.5  294.05  6093.1  297.49    6185     306
#Mann= 5 ,-1 , 0
  3673.2     .17       0  4620.1     .15       0  4961.7     .09       0
  5046.4     .15       0  5149.6     .17       0
Bank Sta=4961.7,5046.4
XS Rating Curve= 0 ,0
Exp/Cntr=0.3,0.1

Type RM Length L Ch R = 1 ,92000   ,500,500,500
BEGIN DESCRIPTION:
CANEY CREEK NORTH 181.0
END DESCRIPTION:
XS GIS Cut Line= 3
      3736302.44      10198927.5      3735768.93     10197736.65
      3735002.78     10196947.05
#Sta/Elev= 30
  3695.1   300.8    3840  294.64    3915  294.38  4059.6  290.96    4181  289.97
  4186.5  291.23  4315.8  288.33  4436.3  289.65  4617.8  286.21  4741.7  284.04
  4770.4  281.23  4822.3  279.36  4984.2  280.53  4988.4  272.64  5011.7  273.47
  5018.9  279.92  5025.9     279  5033.1  281.94  5132.7  280.45  5301.6  278.83
  5365.4  280.38  5506.9   278.9  5591.8  280.15  5718.9  285.36  5754.3  288.32
  5775.5  287.76  5796.8  291.44  5881.7  295.36  5987.7  297.13  6100.2   301.3
#Mann= 5 ,-1 , 0
  3695.1     .17       0  4617.8     .15       0  4984.2     .09       0
  5033.1     .15       0  5132.7     .17       0
Bank Sta=4984.2,5033.1
XS Rating Curve= 0 ,0
Exp/Cntr=0.3,0.1

Type RM Length L Ch R = 1 ,91500   ,500,500,500
BEGIN DESCRIPTION:
CANEY CREEK NORTH 180.0
END DESCRIPTION:
XS GIS Cut Line= 3
      3736360.22     10198919.28      3736094.49     10197521.52
      3735432.36     10196799.03
#Sta/Elev= 30
  3577.2  299.55  3717.9  294.62  3799.3  293.11  3885.1  293.49  4002.9  288.84
  4186.1  286.11  4260.8  286.48    4313  285.15  4440.6  286.59  4578.5  284.94
  4664.5  283.41  4725.6  284.54  4827.4  279.59  4857.9  279.19  4897.6  278.85
  4969.9  281.24  4980.1  280.85  4990.8  270.74  5004.5  270.74  5012.3  276.61
  5026.5  281.57  5075.8  278.72    5129  278.55  5311.9  278.63  5387.2  278.17
  5507.5  281.87  5641.9  290.45  5783.7   302.1  5896.5  306.96    5980  312.08
#Mann= 6 ,-1 , 0
  3577.2     .17       0  4578.5     .15       0  4969.9     .09       0
  5026.5     .15       0    5129     .11       0  5311.9     .17       0
Bank Sta=4969.9,5026.5
XS Rating Curve= 0 ,0
Exp/Cntr=0.3,0.1

Type RM Length L Ch R = 1 ,91000   ,500,500,500
BEGIN DESCRIPTION:
CANEY CREEK NORTH 179.0
END DESCRIPTION:
XS GIS Cut Line= 3
      3736587.16     10198931.68      3736383.25     10197311.16
      3735717.54     10196655.04
#Sta/Elev= 30
  3366.7  298.85  3401.9  297.56  3437.9   294.7  3538.7   290.7    3638  288.61
  3810.8  286.95  3879.1   288.2    3991  286.85  4151.4  285.09  4334.9  285.57
  4480.5  283.45  4566.7  280.66  4707.8  281.91  4808.6  278.42  4959.8  279.86
  4979.9  273.59  4983.2  270.37    5000  271.13  5003.9  273.92    5018  279.49
  5060.5  278.06  5088.8  279.03  5173.6  276.42  5201.9   278.4  5334.5  281.97
  5414.1   283.1  5534.2  286.72  5703.9  299.05  5831.2  310.11  5934.7  316.18
#Mann= 7 ,-1 , 0
  3366.7     .17       0    3991     .15       0  4151.4     .17       0
  4480.5     .15       0  4959.8     .09       0    5018     .15       0
  5334.5     .17       0
Bank Sta=4959.8,5018
XS Rating Curve= 0 ,0
Exp/Cntr=0.3,0.1

Type RM Length L Ch R = 1 ,90500   ,500,500,500
BEGIN DESCRIPTION:
CANEY CREEK NORTH 178.0
END DESCRIPTION:
XS GIS Cut Line= 3
      3736867.73     10198651.04      3736773.02     10197146.01
      3736212.76     10196416.15
#Sta/Elev= 30
    3492  294.95  3652.3  291.24  3772.5  284.13  3864.8  285.27    4013  285.02
  4223.4  280.77  4343.6  283.66  4383.7  282.97  4473.9  284.11    4527  283.05
  4614.2  276.92  4644.2  276.36  4894.7  277.65  4974.9   279.1  4984.9   277.9
  4999.4  269.61  5013.4  269.61  5013.9  270.11  5014.6  275.77  5029.1  278.83
  5157.5  278.21  5207.7  276.19  5220.5  277.96  5456.9  279.53  5524.7  282.28
  5577.4  285.31  5598.7  287.95  5670.8  293.13  5820.4  307.48  5920.1  310.19
#Mann= 5 ,-1 , 0
    3492     .17       0  3864.8     .15       0  4974.9     .09       0
  5029.1     .15       0  5524.7     .17       0
Bank Sta=4974.9,5029.1
XS Rating Curve= 0 ,0
Exp/Cntr=0.3,0.1

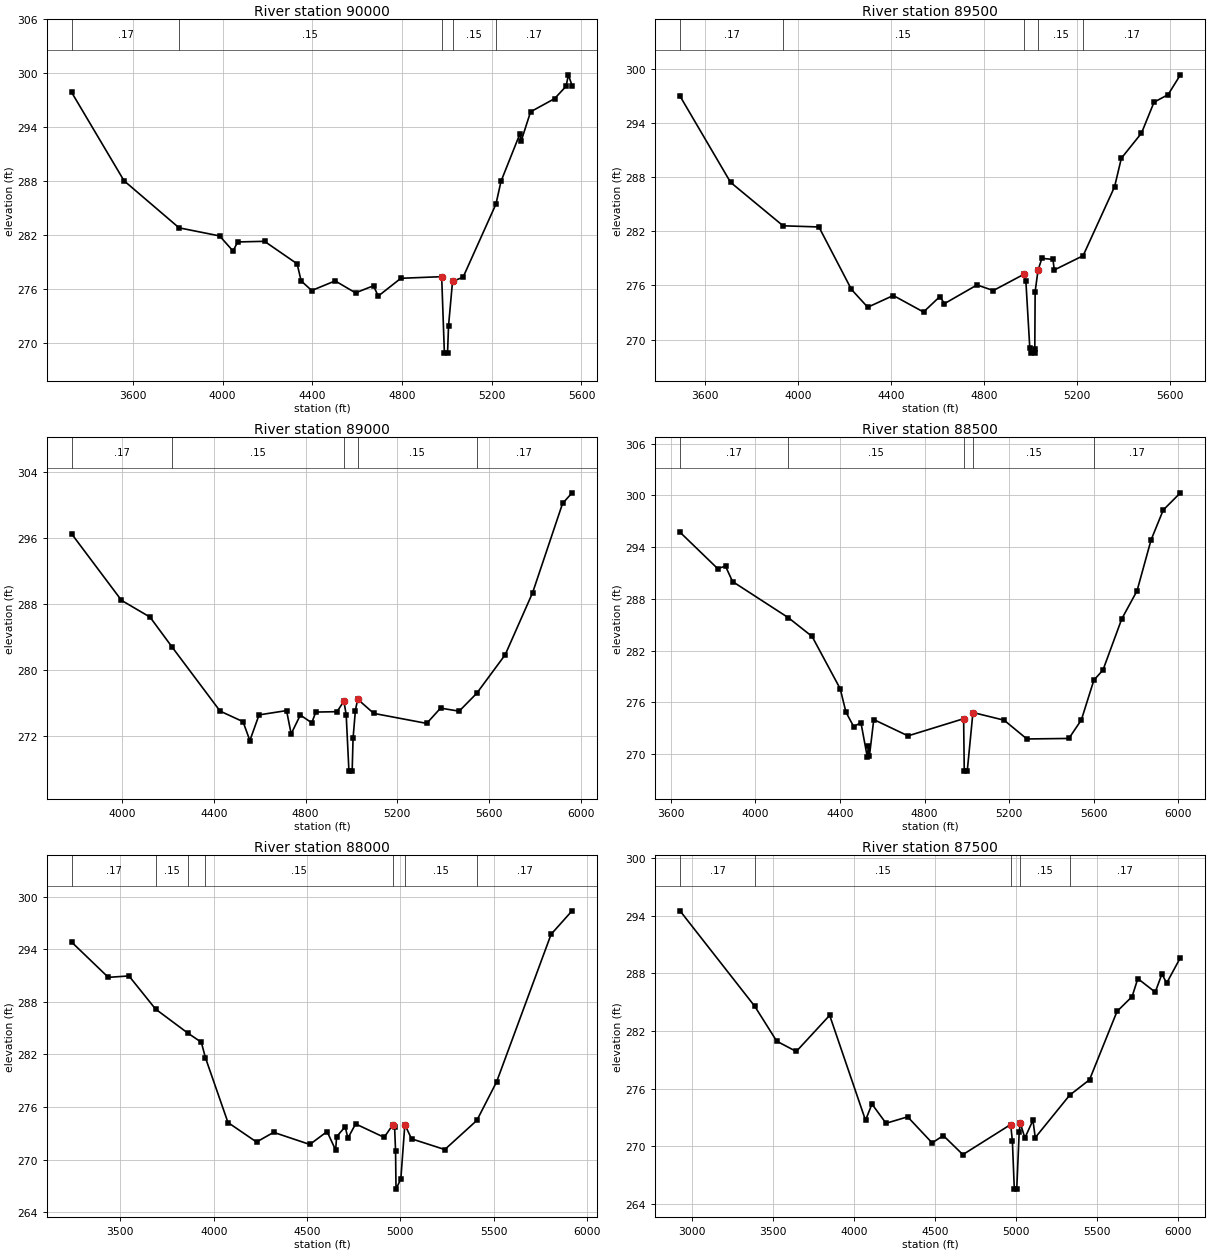
Type RM Length L Ch R = 1 ,90000   ,500,500,500
BEGIN DESCRIPTION:
CANEY CREEK NORTH 177.0
END DESCRIPTION:
XS GIS Cut Line= 3
      3737366.99     10198593.35      3737126.44     10196938.24
      3737255.34     10196395.13
#Sta/Elev= 30
  3327.5  297.87    3561  288.05  3806.2  282.82  3986.9  281.92  4046.9  280.24
  4067.5  281.25  4187.1  281.32  4332.5  278.82  4350.4  276.92  4397.5  275.85
    4502  276.92  4592.9  275.59    4673  276.38    4694  275.23    4795  277.21
  4976.9  277.39    4989  268.89  5003.1  268.89  5007.4   271.9  5025.3  276.86
  5072.6  277.34    5219  285.47  5241.4  287.99  5325.9  293.28    5331  292.44
  5373.2  295.72  5480.1  297.18  5531.5  298.56  5541.8  299.83  5558.2  298.62
#Mann= 5 ,-1 , 0
  3327.5     .17       0  3806.2     .15       0  4976.9     .09       0
  5025.3     .15       0    5219     .17       0
Bank Sta=4976.9,5025.3
XS Rating Curve= 0 ,0
Exp/Cntr=0.3,0.1

Type RM Length L Ch R = 1 ,89500   ,500,500,500
BEGIN DESCRIPTION:
CANEY CREEK NORTH 176.0
END DESCRIPTION:
XS GIS Cut Line= 3
      3737552.66     10198498.43      3737572.37     10196992.16
      3737322.63      10196396.6
#Sta/Elev= 30
  3493.6     297    3711  287.44  3936.9  282.62    4091  282.49    4231  275.56
    4301  273.59    4411  274.89    4541  273.06  4611.1  274.77  4631.1  273.99
  4771.1  276.06  4841.1  275.44  4971.1  277.22  4981.1  276.51    4998   269.1
    5005   268.5  5019.1   268.5  5019.6     269    5021  275.32  5033.7  277.73
  5050.2  279.01  5097.8  278.89  5103.2  277.72  5227.3   279.3  5362.6  286.94
  5391.8  290.11  5478.3  292.89  5532.5  296.33  5592.8  297.16  5645.8  299.36
#Mann= 5 ,-1 , 0
  3493.6     .17       0  3936.9     .15       0  4971.1     .09       0
  5033.7     .15       0  5227.3     .17       0
Bank Sta=4971.1,5033.7
XS Rating Curve= 0 ,0
Exp/Cntr=0.3,0.1

Type RM Length L Ch R = 1 ,89000   ,500,500,500
BEGIN DESCRIPTION:
CANEY CREEK NORTH 175.0
END DESCRIPTION:
XS GIS Cut Line= 3
      3737948.76     10198428.31      3737999.19     10197207.85
      3737903.37     10196249.73
#Sta/Elev= 30
  3778.5  296.47  3995.9  288.43  4120.5   286.4  4216.9  282.77  4426.3  275.02
  4526.4  273.74  4556.4  271.45  4596.4  274.56  4716.5  275.08  4736.6  272.26
  4776.6  274.54  4826.6   273.6  4844.1   274.9  4936.7  274.95  4966.8  276.22
  4976.8  274.59  4988.8  267.75  5002.9  267.75  5006.8  271.72  5016.9  275.07
  5026.9  276.46  5097.3  274.74  5328.4  273.53  5388.7  275.38  5469.9  275.01
  5546.3  277.16  5670.9  281.84  5790.7  289.36  5921.4  300.16  5962.9  301.45
#Mann= 5 ,-1 , 0
  3778.5     .17       0  4216.9     .15       0  4966.8     .09       0
  5026.9     .15       0  5546.3     .17       0
Bank Sta=4966.8,5026.9
XS Rating Curve= 0 ,0
Exp/Cntr=0.3,0.1

Type RM Length L Ch R = 1 ,88500   ,500,500,500
BEGIN DESCRIPTION:
CANEY CREEK NORTH 174.0
END DESCRIPTION:
XS GIS Cut Line= 3
      3738270.58     10198436.57      3738472.03     10197096.02
      3737969.37      10196220.8
#Sta/Elev= 30
  3644.4  295.73  3821.9  291.52  3859.4  291.79  3892.7  290.01  4156.8  285.81
  4268.6  283.64  4401.6  277.57  4428.6  274.86  4465.6  273.17  4499.4  273.66
  4529.6  269.65  4534.6  270.94  4539.8  269.81  4560.1     274  4721.9  272.11
  4984.8   274.1  4987.8  268.02  5001.9  268.02  5028.8  274.82    5176  273.93
  5283.8  271.75  5482.3  271.81  5541.2  273.96  5600.5  278.58  5643.3  279.74
  5732.2  285.68  5804.3  288.93  5870.6  294.83  5928.3  298.31  6009.3   300.3
#Mann= 5 ,-1 , 0
  3644.4     .17       0  4156.8     .15       0  4984.8     .09       0
  5028.8     .15       0  5600.5     .17       0
Bank Sta=4984.8,5028.8
XS Rating Curve= 0 ,0
Exp/Cntr=0.3,0.1

Type RM Length L Ch R = 1 ,88000   ,500,500,500
BEGIN DESCRIPTION:
CANEY CREEK NORTH 173.0
END DESCRIPTION:
XS GIS Cut Line= 4
        3738415.     10198481.93      3738753.82     10196790.44
      3738746.77     10196755.54      3738023.06     10196187.85
#Sta/Elev= 30
  3239.3   294.8  3435.5  290.79  3546.1  290.95  3688.4  287.18  3861.3  284.44
  3933.7   283.4  3955.5  281.65  4076.5  274.25  4229.4  272.03  4321.2  273.13
    4515  271.75  4607.5  273.22  4653.3  271.11  4658.4  272.63  4704.3  273.77
    4719  272.47  4760.3  274.09  4913.2  272.56  4959.1  273.97  4969.1  273.75
  4974.2  271.05  4976.7  266.66  5002.5  267.82    5024  274.01  5059.9  272.39
    5238  271.17  5409.7  274.49  5515.5  278.88  5807.5   295.7  5919.8  298.37
#Mann= 7 ,-1 , 0
  3239.3     .17       0  3688.4     .15       0  3861.3     .17       0
  3955.5     .15       0  4959.1     .09       0    5024     .15       0
  5409.7     .17       0
Bank Sta=4959.1,5024
XS Rating Curve= 0 ,0
Exp/Cntr=0.3,0.1

Type RM Length L Ch R = 1 ,87500   ,427,427,427
BEGIN DESCRIPTION:
CANEY CREEK NORTH 172.0
END DESCRIPTION:
XS GIS Cut Line= 3
      3738514.02     10198527.34      3739175.87     10196559.46
       3738377.9     10195932.03
#Sta/Elev= 30
  2923.8   294.5  3385.6  284.57  3521.3  280.94  3642.1  279.87  3848.3  283.63
  4069.9  272.71  4109.5   274.4  4196.5   272.4  4330.1  273.07  4481.3  270.36
  4550.6  271.12  4671.2  269.14  4966.6  272.27  4977.2  270.54    4989  265.55
    5004  265.55  5019.1  271.45  5025.5  272.44  5054.4  270.88  5104.1  272.71
  5118.5  270.91  5330.9  275.32  5453.8  276.93  5623.7  284.04  5716.8  285.58
    5752  287.45  5859.5  286.04  5901.2  287.93  5930.1  286.98  6015.1  289.63
#Mann= 5 ,-1 , 0
  2923.8     .17       0  3385.6     .15       0  4966.6     .09       0
  5025.5     .15       0  5330.9     .17       0
Bank Sta=4966.6,5025.5
XS Rating Curve= 0 ,0
Exp/Cntr=0.3,0.1

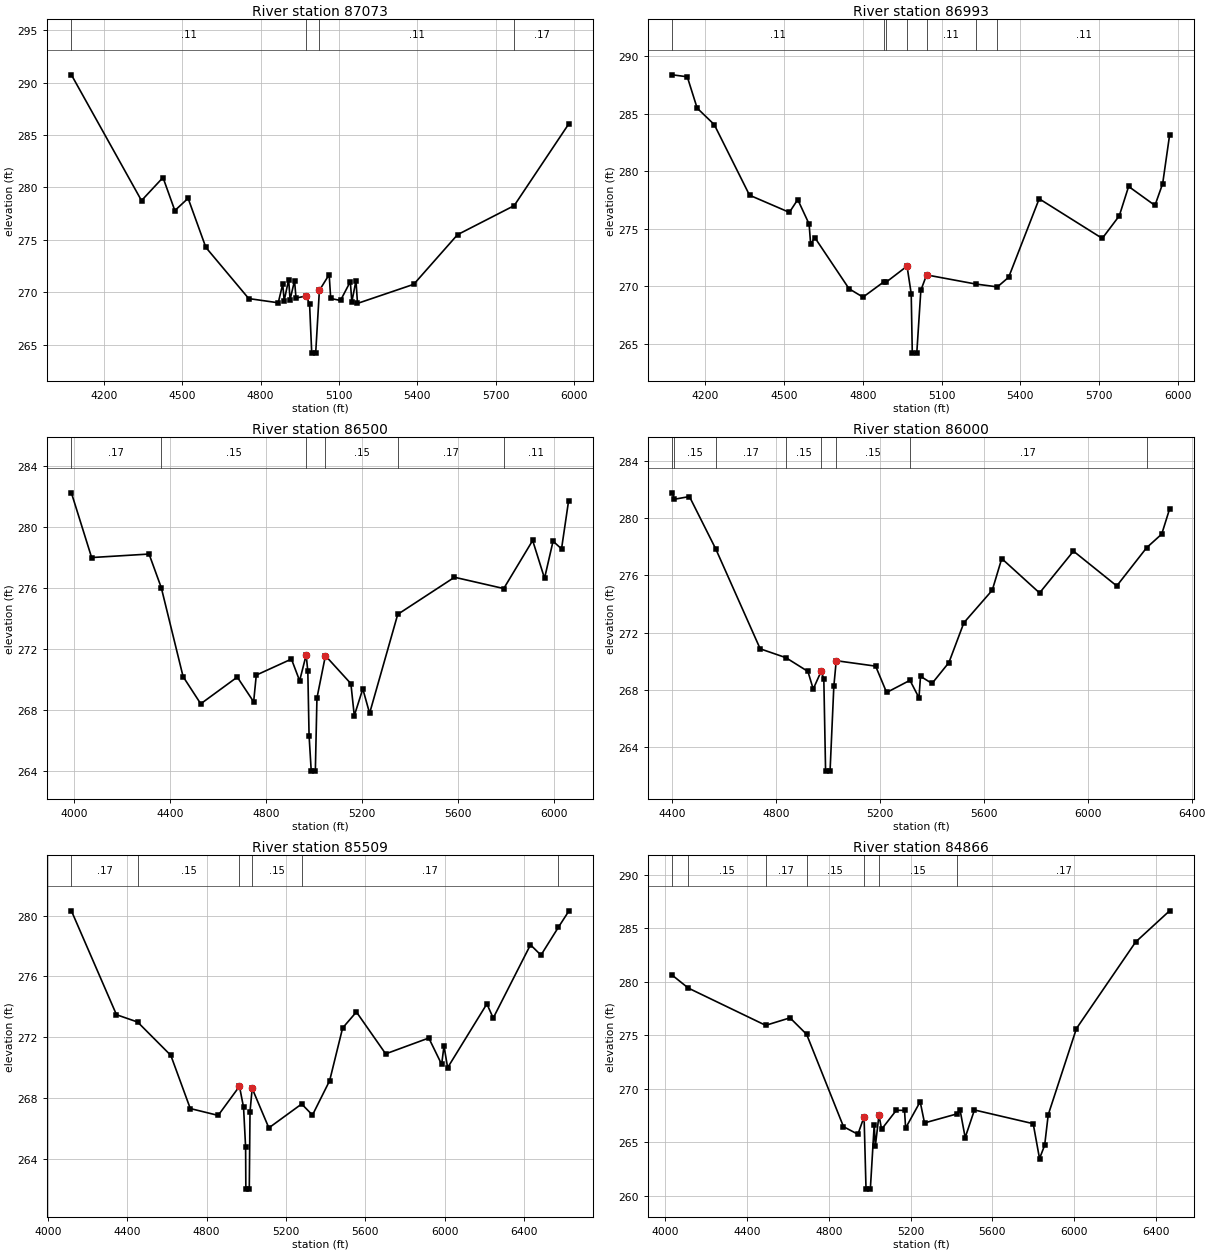
Type RM Length L Ch R = 1 ,87073   ,80,80,80
BEGIN DESCRIPTION:
CANEY CREEK NORTH 171.5
END DESCRIPTION:
XS GIS Cut Line= 3
      3739954.37     10197232.97        3739554.     10196399.77
      3739073.31     10195546.79
#Sta/Elev= 30
  4075.6  290.74    4344  278.75  4426.3  280.95  4471.6   277.8  4522.4  278.97
  4590.3  274.29  4754.5  269.41  4867.5  269.01  4884.6  270.79  4890.2  269.21
  4907.3  271.22  4912.8  269.31  4929.9  271.12  4935.5  269.46  4975.2  269.66
  4987.5  268.85  4995.7  264.21  5010.8  264.21    5025  270.19  5062.5   271.7
  5068.3  269.42  5105.9  269.23  5143.5  271.03  5149.2  269.09  5165.1  271.12
  5170.9  268.95  5386.2  270.77  5553.8   275.5  5770.8  278.27  5979.1  286.04
#Mann= 4 ,-1 , 0
  4075.6     .11       0  4975.2     .06       0    5025     .11       0
  5770.8     .17       0
Bank Sta=4975.2,5025
XS Rating Curve= 0 ,0
Exp/Cntr=0.3,0.1

Type RM Length L Ch R = 1 ,86993   ,493,493,493
BEGIN DESCRIPTION:
CANEY CREEK NORTH 171.0
END DESCRIPTION:
XS GIS Cut Line= 4
      3740079.28     10197178.06      3739626.07     10196370.78
      3739446.27     10195885.75      3739180.05     10195521.06
#Sta/Elev= 30
  4074.2  288.36    4131  288.19  4168.6  285.47  4233.7  284.04  4368.2  277.91
    4520  276.42  4551.9  277.53  4595.3   275.4    4601  273.66    4617  274.23
  4747.4  269.79  4800.6  269.06  4878.9  270.37  4889.9  270.38  4968.4  271.75
  4984.3  269.36  4988.4   264.2  5005.5   264.2    5021  269.65  5042.9  270.99
  5229.7   270.2  5312.8  269.95  5355.7  270.79  5471.9   277.6  5712.3  274.16
  5777.2  276.12  5812.7  278.67  5913.1  277.02  5942.5  278.92  5968.8  283.12
#Mann= 7 ,-1 , 0
  4074.2     .11       0  4878.9     .15       0  4889.9     .11       0
  4968.4     .06       0  5042.9     .11       0  5229.7     .17       0
  5312.8     .11       0
Bank Sta=4968.4,5042.9
XS Rating Curve= 0 ,0
Exp/Cntr=0.3,0.1

Type RM Length L Ch R = 1 ,86500   ,500,500,500
BEGIN DESCRIPTION:
CANEY CREEK NORTH 170.0
END DESCRIPTION:
XS GIS Cut Line= 3
      3740228.66     10197082.15      3739956.23     10196108.97
      3739195.91     10195371.52
#Sta/Elev= 30
  3989.4  282.22  4073.6  277.98  4312.7  278.21  4363.7     276  4454.4  270.18
  4527.8   268.4  4679.9  270.15  4748.1  268.53    4759  270.28  4905.4  271.33
  4939.5  269.91  4966.7   271.6  4973.6  270.53  4978.8  266.32  4987.8  263.99
  5004.9  263.99  5011.6  268.78  5046.9  271.55  5152.9  269.72    5167  267.62
  5202.5  269.38  5230.8  267.78  5347.9  274.26  5584.2  276.69  5789.2  275.95
  5909.6   279.1    5959  276.62  5994.5  279.05  6029.8  278.55  6059.2   281.7
#Mann= 6 ,-1 , 0
  3989.4     .17       0  4363.7     .15       0  4966.7     .09       0
  5046.9     .15       0  5347.9     .17       0  5789.2     .11       0
Bank Sta=4966.7,5046.9
XS Rating Curve= 0 ,0
Exp/Cntr=0.3,0.1

Type RM Length L Ch R = 1 ,86000   ,500,500,500
BEGIN DESCRIPTION:
CANEY CREEK NORTH 169.0
END DESCRIPTION:
XS GIS Cut Line= 3
      3740535.58     10196682.13      3740416.16     10196095.77
      3739306.27     10195390.52
#Sta/Elev= 30
  4401.6  281.77  4408.9  281.32  4467.2  281.51  4569.1  277.83  4739.5  270.88
  4838.6  270.26  4923.2   269.3  4943.6  268.07  4974.2  269.31  4984.4  268.77
  4991.2  262.34  5008.4  262.34  5022.9  268.25  5032.2  270.05  5183.8  269.67
  5226.1  267.83  5315.9  268.68  5350.6  267.46  5356.5  268.96  5400.8  268.46
  5465.8  269.92  5523.4   272.7  5632.6  274.97  5669.1  277.18  5814.7  274.78
  5945.1   277.7  6111.7  275.27  6226.8  277.94  6284.8  278.89    6315  280.64
#Mann= 8 ,-1 , 0
  4401.6     .17       0  4408.9     .15       0  4569.1     .17       0
  4838.6     .15       0  4974.2     .09       0  5032.2     .15       0
  5315.9     .17       0  6226.8     .11       0
Bank Sta=4974.2,5032.2
XS Rating Curve= 0 ,0
Exp/Cntr=0.3,0.1

Type RM Length L Ch R = 1 ,85509   ,634,634,634
BEGIN DESCRIPTION:
CANEY CREEK NORTH 168.0
END DESCRIPTION:
XS GIS Cut Line= 3
      3741028.29     10196711.08       3740804.9     10195846.92
      3739318.31     10195220.39
#Sta/Elev= 30
  4118.2  280.31  4345.4  273.49  4451.8  273.01  4619.3  270.82  4717.3  267.33
  4857.9  266.88  4965.2  268.79  4985.8  267.41  4996.2  264.79  4997.4  262.04
  5014.7  262.04  5018.4  267.13  5029.3  268.65  5113.3  266.06  5278.8  267.63
  5333.1   266.9  5419.7  269.16  5485.1  272.62  5554.6  273.67  5702.1  270.92
  5919.4  271.96  5984.2  270.23    5996  271.44  6014.3  270.01  6212.1   274.2
  6244.1  273.27  6431.9  278.08  6484.7   277.4    6572  279.22    6624  280.27
#Mann= 6 ,-1 , 0
  4118.2     .17       0  4451.8     .15       0  4965.2     .09       0
  5029.3     .15       0  5278.8     .17       0    6572     .11       0
Bank Sta=4965.2,5029.3
XS Rating Curve= 0 ,0
Exp/Cntr=0.3,0.1

Type RM Length L Ch R = 1 ,84866   ,748,748,748
BEGIN DESCRIPTION:
CANEY CREEK NORTH 166.0
END DESCRIPTION:
XS GIS Cut Line= 3
      3741108.77     10196883.07      3741221.49     10195923.77
      3740726.02      10194541.8
#Sta/Elev= 30
  4034.1   280.6    4112  279.41  4490.8  275.93    4610  276.63  4691.3  275.09
  4871.8  266.47  4942.3  265.76  4972.5  267.39  4982.1  260.64  5003.2  260.64
  5022.2  266.67  5027.5  264.62  5045.4  267.55  5058.3  266.23  5130.3     268
  5170.6  267.99  5175.9  266.34  5247.2   268.8  5268.4  266.82  5428.5  267.67
  5442.1  268.06  5467.5  265.45  5512.8  268.03  5800.5  266.75  5831.5  263.49
  5856.6  264.74    5874  267.58  6012.1  275.63    6302  283.71  6468.1  286.62
#Mann= 7 ,-1 , 0
  4034.1     .17       0    4112     .15       0  4490.8     .17       0
  4691.3     .15       0  4972.5     .09       0  5045.4     .15       0
  5428.5     .17       0
Bank Sta=4972.5,5045.4
XS Rating Curve= 0 ,0
Exp/Cntr=0.3,0.1

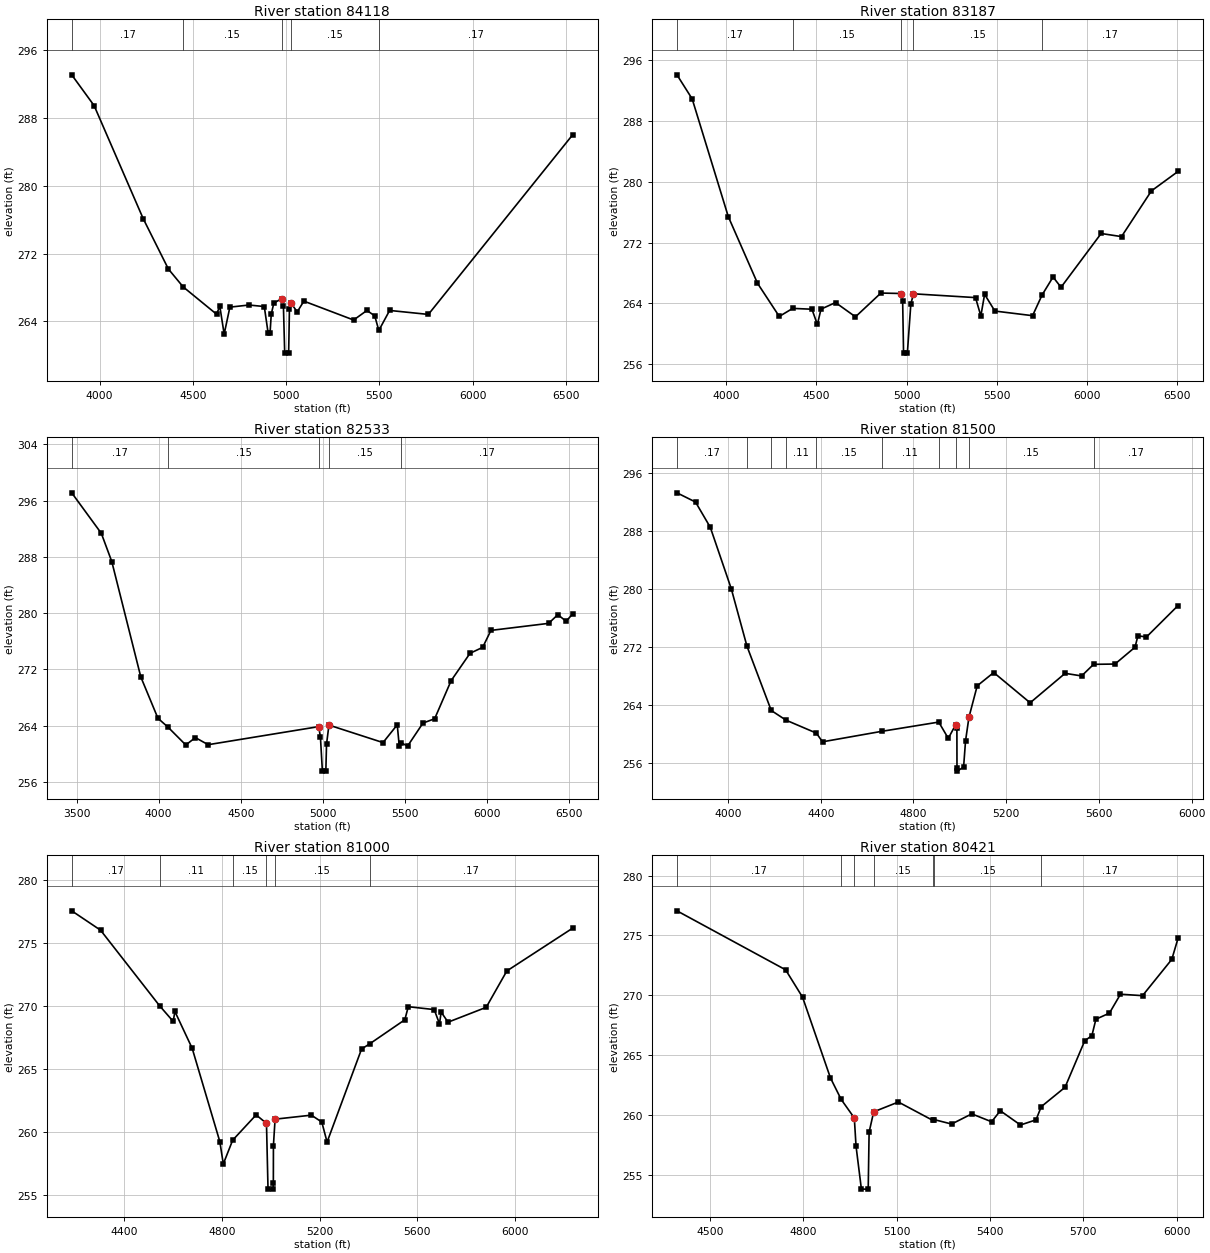
Type RM Length L Ch R = 1 ,84118   ,931,931,931
BEGIN DESCRIPTION:
CANEY CREEK NORTH 165.0
END DESCRIPTION:
XS GIS Cut Line= 3
       3742036.8      10196768.4      3741785.81     10195646.94
      3740892.58     10194396.51
#Sta/Elev= 30
  3850.8  293.12    3971  289.48  4233.7  276.15    4369  270.19  4448.2  268.08
  4626.9  264.86  4644.7  265.79  4667.9   262.5  4698.6  265.69  4801.1  265.94
    4883  265.76  4903.5  262.65  4913.8   262.6  4920.4  264.87  4934.3  266.18
  4975.3  266.67  4985.5  265.87  4992.5  260.26  5013.6  260.26  5017.8  265.46
    5024  266.23  5059.6  265.13  5095.2   266.4  5361.9  264.17  5433.2   265.3
    5475  264.66    5497  262.94  5554.9   265.3  5762.5  264.83  6536.7  286.06
#Mann= 5 ,-1 , 0
  3850.8     .17       0  4448.2     .15       0  4975.3     .09       0
    5024     .15       0    5497     .17       0
Bank Sta=4975.3,5024
XS Rating Curve= 0 ,0
Exp/Cntr=0.3,0.1

Type RM Length L Ch R = 1 ,83187   ,654,654,654
BEGIN DESCRIPTION:
CANEY CREEK NORTH 163.0
END DESCRIPTION:
XS GIS Cut Line= 3
      3742210.41     10196724.92      3742353.52     10195459.18
      3741477.76     10194234.86
#Sta/Elev= 30
  3726.2  294.09  3810.6  290.92  4010.9  275.42  4172.9  266.65  4293.6  262.28
  4368.2  263.34  4474.8  263.23    4505  261.22  4525.1  263.24  4605.6  264.11
  4716.3  262.23  4857.2  265.36  4967.9   265.3    4978  264.26    4983  257.45
  5004.1  257.45  5023.4  263.93  5038.1  265.26  5382.1  264.76  5411.6  262.35
  5432.5  265.19  5489.5  262.99  5698.5  262.38  5751.6  265.12  5812.1  267.47
  5856.4  266.12  6078.8   273.2  6191.8  272.79  6357.7  278.81  6505.3  281.37
#Mann= 5 ,-1 , 0
  3726.2     .17       0  4368.2     .15       0  4967.9     .09       0
  5038.1     .15       0  5751.6     .17       0
Bank Sta=4967.9,5038.1
XS Rating Curve= 0 ,0
Exp/Cntr=0.3,0.1

Type RM Length L Ch R = 1 ,82533   ,1033,1033,1033
BEGIN DESCRIPTION:
CANEY CREEK NORTH 162.0
END DESCRIPTION:
XS GIS Cut Line= 3
      3742367.86     10196761.03      3742844.26     10195307.51
      3741945.63     10194077.38
#Sta/Elev= 30
  3470.4  297.11  3650.7  291.35  3714.4  287.34  3891.3  270.92  3995.7  265.04
  4058.2  263.75  4165.4  261.24  4223.8  262.29  4301.7  261.28  4975.2  263.85
  4985.7   262.4  4997.7  257.52  5018.8  257.52  5022.9  261.34  5037.6  264.07
  5367.1  261.58  5453.8  264.11  5466.2  261.05  5477.8  261.57  5516.4  261.07
  5610.6  264.36  5681.7  264.97  5782.1  270.39  5897.2  274.28  5974.4  275.13
  6024.6  277.54    6376  278.54  6432.4  279.78  6482.6  278.84  6523.4   279.9
#Mann= 5 ,-1 , 0
  3470.4     .17       0  4058.2     .15       0  4975.2     .09       0
  5037.6     .15       0  5477.8     .17       0
Bank Sta=4975.2,5037.6
XS Rating Curve= 0 ,0
Exp/Cntr=0.3,0.1

Type RM Length L Ch R = 1 ,81500   ,500,500,500
BEGIN DESCRIPTION:
CANEY CREEK NORTH 161.0
END DESCRIPTION:
XS GIS Cut Line= 3
      3743647.04     10196204.16      3743268.92     10195043.92
      3742718.12     10194280.59
#Sta/Elev= 30
  3779.7   293.2  3859.8  291.93  3923.6  288.44  4014.1  279.97  4081.8  272.05
  4186.4   263.2  4249.9  261.87  4381.1  260.08  4407.6  258.88  4662.2  260.32
    4909   261.6  4950.1  259.36    4982  261.23  4987.3  260.76  4987.7  255.34
  4988.2  254.84  5016.2  255.39  5024.7  259.03  5039.4  262.28    5075   266.6
  5146.2  268.43  5303.3  264.26  5454.2  268.32  5525.3  267.96    5577  269.56
  5669.4   269.6  5755.7  271.92  5768.3  273.49  5805.1  273.33  5941.3  277.66
#Mann= 10 ,-1 , 0
  3779.7     .17       0  4081.8     .15       0  4186.4     .17       0
  4249.9     .11       0  4381.1     .15       0  4662.2     .11       0
    4909     .15       0    4982     .09       0  5039.4     .15       0
    5577     .17       0
Bank Sta=4982,5039.4
XS Rating Curve= 0 ,0
Exp/Cntr=0.3,0.1

Type RM Length L Ch R = 1 ,81000   ,565,565,565
BEGIN DESCRIPTION:
CANEY CREEK NORTH 160.0
END DESCRIPTION:
XS GIS Cut Line= 3
      3744285.09     10195600.87      3743720.28      10195014.7
      3742808.25     10194179.76
#Sta/Elev= 30
    4186  277.56  4304.1  276.02  4545.7  270.01  4601.3  268.77  4608.2  269.56
    4679  266.63  4792.2  259.21  4806.3  257.44  4844.6  259.33  4940.6  261.34
    4983  260.67  4989.3  255.44  5010.6  255.44  5011.1  255.94  5011.4   258.9
  5018.2     261  5166.8  261.32  5209.4  260.77    5231  259.18  5372.2  266.58
  5404.8  266.98  5549.1   268.9  5563.3  269.94  5669.4  269.71    5691  268.58
  5697.8  269.51  5726.1  268.71  5882.1  269.89  5966.6  272.78  6236.5  276.19
#Mann= 6 ,-1 , 0
    4186     .17       0  4545.7     .11       0  4844.6     .15       0
    4983     .09       0  5018.2     .15       0  5404.8     .17       0
Bank Sta=4983,5018.2
XS Rating Curve= 0 ,0
Exp/Cntr=0.3,0.1

Type RM Length L Ch R = 1 ,80421   ,435,435,435
BEGIN DESCRIPTION:
CANEY CREEK NORTH 159.0
END DESCRIPTION:
XS GIS Cut Line= 3
      3744328.45     10195570.41      3744184.17     10194981.43
      3743375.31     10194385.14
#Sta/Elev= 30
  4393.6  277.06    4743  272.13  4797.5  269.84  4887.1   263.1  4921.6   261.3
  4963.9  259.75  4969.5  257.38  4986.7   253.8  5008.6   253.8  5011.5  258.56
  5026.2  260.26  5105.6  261.08  5215.4  259.56  5220.8  259.61  5276.8  259.24
  5341.6  260.09  5405.4  259.43  5433.4  260.35  5498.2  259.16  5548.3  259.59
    5565  260.69  5641.5  262.31  5704.9   266.2  5727.9  266.63  5740.8     268
  5784.3  268.51  5819.8  270.09  5890.7  269.97  5984.8     273  6004.9  274.76
#Mann= 7 ,-1 , 0
  4393.6     .17       0  4921.6     .15       0  4963.9     .09       0
  5026.2     .15       0  5215.4     .11       0  5220.8     .15       0
    5565     .17       0
Bank Sta=4963.9,5026.2
XS Rating Curve= 0 ,0
Exp/Cntr=0.3,0.1

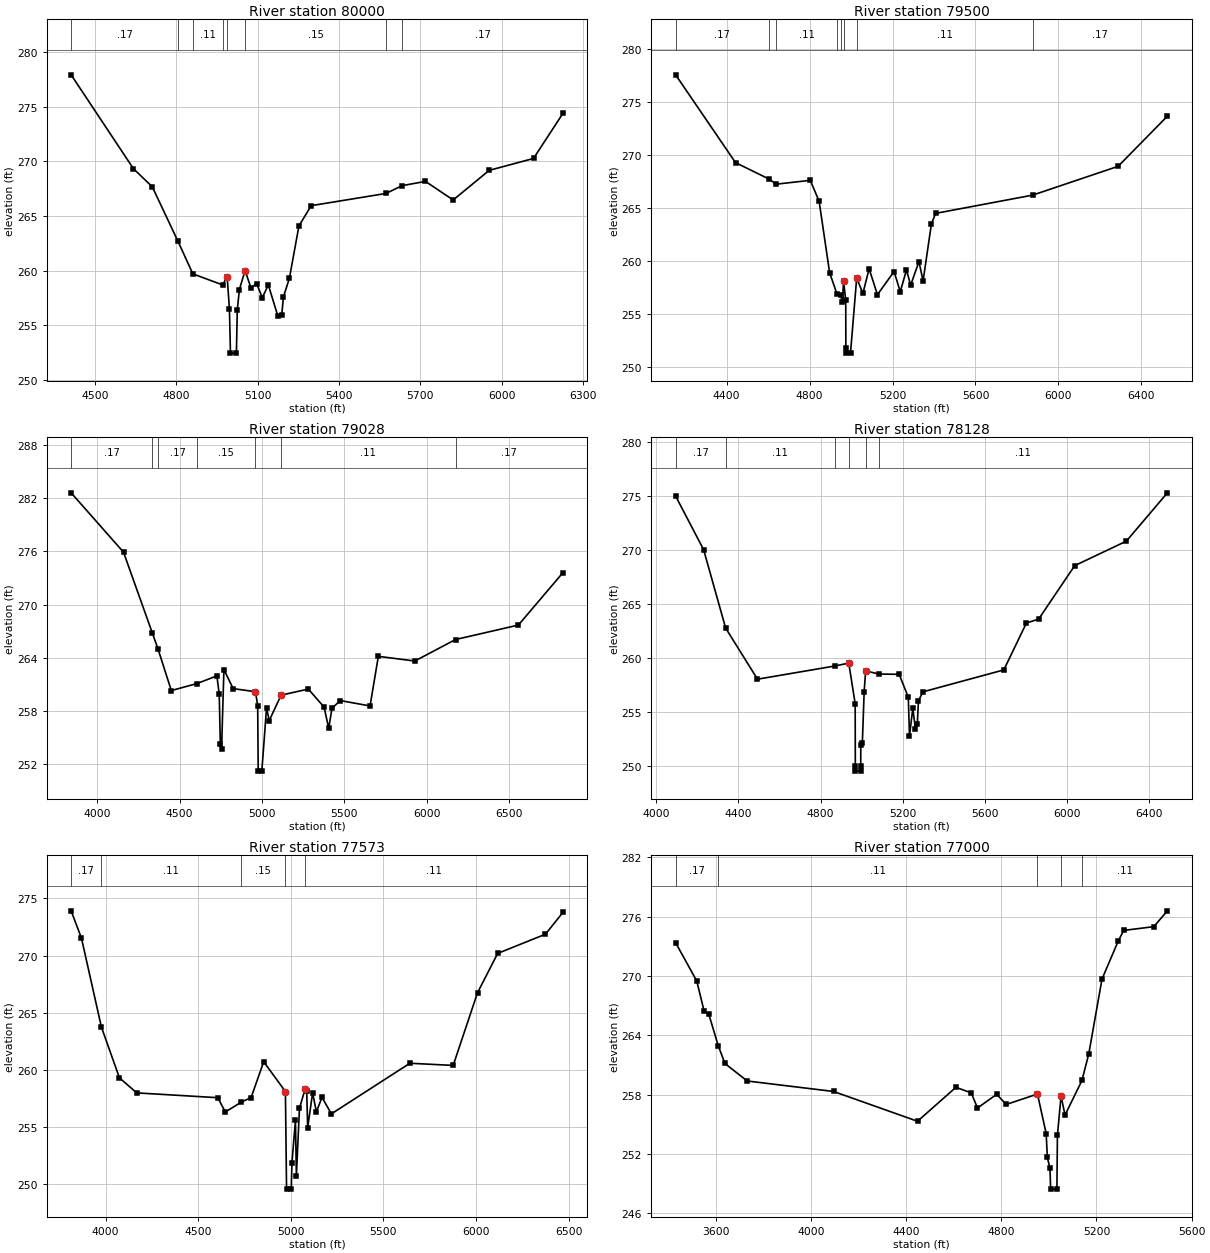
Type RM Length L Ch R = 1 ,80000   ,500,500,500
BEGIN DESCRIPTION:
CANEY CREEK NORTH 158.0
END DESCRIPTION:
XS GIS Cut Line= 4
      3744758.13     10195283.97      3744516.02      10194748.9
      3744289.39     10194554.83      3743381.79     10194367.53
#Sta/Elev= 30
  4412.7  277.91  4642.4  269.32  4711.7  267.67  4806.5  262.68  4861.3   259.7
  4971.1  258.69  4987.8  259.45  4996.1  256.46  4999.9  252.45  5021.8  252.45
  5025.1   256.4  5032.8  258.27  5053.7     260  5075.6  258.41  5096.5  258.81
  5117.3  257.51  5139.3   258.7  5174.4  255.86  5188.7   255.9  5195.2   257.6
  5217.2  259.31  5252.3  264.09  5297.4  265.94  5573.5  267.06    5632  267.77
  5718.6  268.16  5820.7  266.46  5953.4  269.17  6116.8  270.26  6225.1  274.38
#Mann= 8 ,-1 , 0
  4412.7     .17       0  4806.5     .15       0  4861.3     .11       0
  4971.1     .15       0  4987.8     .09       0  5053.7     .15       0
  5573.5     .15       0    5632     .17       0
Bank Sta=4987.8,5053.7
XS Rating Curve= 0 ,0
Exp/Cntr=0.3,0.1

Type RM Length L Ch R = 1 ,79500   ,472,472,472
BEGIN DESCRIPTION:
CANEY CREEK NORTH 157.0
END DESCRIPTION:
XS GIS Cut Line= 5
      3744818.91     10195253.61      3744962.14     10194576.53
      3744894.82     10194437.87      3744285.05     10194463.68
      3743381.61     10194317.56
#Sta/Elev= 30
  4153.8  277.54  4442.6  269.28  4604.2  267.73  4638.5  267.25  4803.2  267.61
  4845.9  265.64  4896.4  258.93  4932.1   256.9    4949  256.83  4958.1  256.18
  4963.7  258.13  4974.2  256.32  4974.8  251.85  4975.3  251.35  4997.2  251.35
    5027  258.41    5057  256.97    5087  259.29  5127.1  256.85  5207.2  259.03
  5237.2  257.13  5267.2  259.18  5287.2  257.74  5327.3  259.96  5347.3  258.14
  5387.3   263.5  5407.3   264.5  5875.8  266.22  6287.8  268.93  6525.5  273.65
#Mann= 8 ,-1 , 0
  4153.8     .17       0  4604.2     .15       0  4638.5     .11       0
  4932.1     .15       0    4949     .11       0  4963.7     .06       0
    5027     .11       0  5875.8     .17       0
Bank Sta=4963.7,5027
XS Rating Curve= 0 ,0
Exp/Cntr=0.3,0.1

Type RM Length L Ch R = 1 ,79028   ,900,900,900
BEGIN DESCRIPTION:
CANEY CREEK NORTH 156.0
END DESCRIPTION:
XS GIS Cut Line= 5
      3746014.33      10195032.9      3745158.64     10194253.86
      3744900.77      10194389.3       3744296.6     10194438.78
      3743381.79     10194287.47
#Sta/Elev= 30
  3842.8  282.63  4160.4  275.92  4335.5  266.76    4370  264.95  4450.2  260.27
  4605.4  261.06  4726.6  261.93  4740.8  259.87  4747.5   254.2    4755  253.67
  4769.2  262.64  4825.3  260.49  4960.4  260.14    4974  258.58  4977.1  251.16
  4999.1  251.16  5027.7   258.3  5044.1  256.88  5115.9  259.75    5281  260.44
  5376.9  258.39  5404.6     256  5424.6  258.27  5474.8  259.14  5655.4  258.53
  5705.6  264.14  5926.6  263.61  6173.7  266.04    6555  267.68  6824.7   273.6
#Mann= 7 ,-1 , 0
  3842.8     .17       0  4335.5     .11       0    4370     .17       0
  4605.4     .15       0  4960.4     .09       0  5115.9     .11       0
  6173.7     .17       0
Bank Sta=4960.4,5115.9
XS Rating Curve= 0 ,0
Exp/Cntr=0.3,0.1

Type RM Length L Ch R = 1 ,78128   ,555,555,555
BEGIN DESCRIPTION:
CANEY CREEK NORTH 154.0
END DESCRIPTION:
XS GIS Cut Line= 3
      3746012.64     10194743.12      3745548.33     10193965.73
      3744238.58     10193260.79
#Sta/Elev= 30
  4094.5  274.95  4230.7  269.99  4337.9  262.73  4492.9     258    4869  259.22
    4937  259.49  4968.2  255.73  4968.9  249.99  4969.4  249.49  4994.8  249.49
  4995.3  249.99  4995.4  251.89  5003.1  252.11  5011.9  256.84    5019  258.77
  5082.7  258.48  5182.2  258.45  5226.7  256.33  5232.4  252.76  5248.6  255.29
  5261.7  253.38  5270.5  253.85  5276.2  256.01  5298.1  256.83  5691.6  258.86
  5801.1  263.19  5861.2  263.57  6036.4  268.51  6287.9  270.78  6487.4  275.25
#Mann= 6 ,-1 , 0
  4094.5     .17       0  4337.9     .11       0    4869     .15       0
    4937     .09       0    5019     .15       0  5082.7     .11       0
Bank Sta=4937,5019
XS Rating Curve= 0 ,0
Exp/Cntr=0.3,0.1

Type RM Length L Ch R = 1 ,77573   ,573,573,573
BEGIN DESCRIPTION:
CANEY CREEK NORTH 153.0
END DESCRIPTION:
XS GIS Cut Line= 4
      3746107.43     10194661.98      3745784.12     10193521.31
      3745416.59     10193582.56      3744367.94     10193262.88
#Sta/Elev= 30
  3814.4  273.91  3870.2  271.52  3977.7  263.76  4075.2  259.31  4168.7     258
  4605.9  257.58  4646.9  256.33  4732.4  257.19  4785.9  257.59  4853.8  260.72
  4971.1  258.12  4977.2  249.59  5002.6  249.59  5006.4  251.91  5025.3   255.6
  5030.3  250.76  5046.9  256.67  5077.3  258.32  5086.1  258.13  5091.2  254.94
  5117.9  258.01  5138.2  256.35  5168.6  257.61  5219.3  256.17  5643.1  260.59
  5876.6   260.4    6008  266.75  6116.9  270.19  6374.9  271.87  6468.9  273.77
#Mann= 5 ,-1 , 0
  3814.4     .17       0  3977.7     .11       0  4732.4     .15       0
  4971.1     .09       0  5077.3     .11       0
Bank Sta=4971.1,5077.3
XS Rating Curve= 0 ,0
Exp/Cntr=0.3,0.1

Type RM Length L Ch R = 1 ,77000   ,500,500,500
BEGIN DESCRIPTION:
CANEY CREEK NORTH 152.0
END DESCRIPTION:
XS GIS Cut Line= 3
      3746159.24     10194649.44      3745961.57     10193093.45
      3745494.24     10192921.38
#Sta/Elev= 30
  3431.5  273.37  3520.6  269.48  3550.8  266.49    3571  266.13  3610.5  262.96
  3638.7  261.16  3732.3  259.39  4095.2  258.33    4448  255.32  4609.3  258.75
  4673.6  258.19    4700  256.66  4780.6  258.04  4820.9  257.02    4952  258.07
  4988.6  254.08  4993.6  251.66  5004.6  250.55  5007.5  248.46  5033.7  248.46
  5035.9   253.9  5051.1  257.86  5067.9  255.95  5138.9  259.44  5167.6  262.13
  5223.2  269.69  5291.7  273.55  5314.5  274.61  5440.9  274.99    5498  276.59
#Mann= 5 ,-1 , 0
  3431.5     .17       0  3610.5     .11       0    4952     .06       0
  5051.1     .11       0  5138.9     .11       0
Bank Sta=4952,5051.1
XS Rating Curve= 0 ,0
Exp/Cntr=0.3,0.1