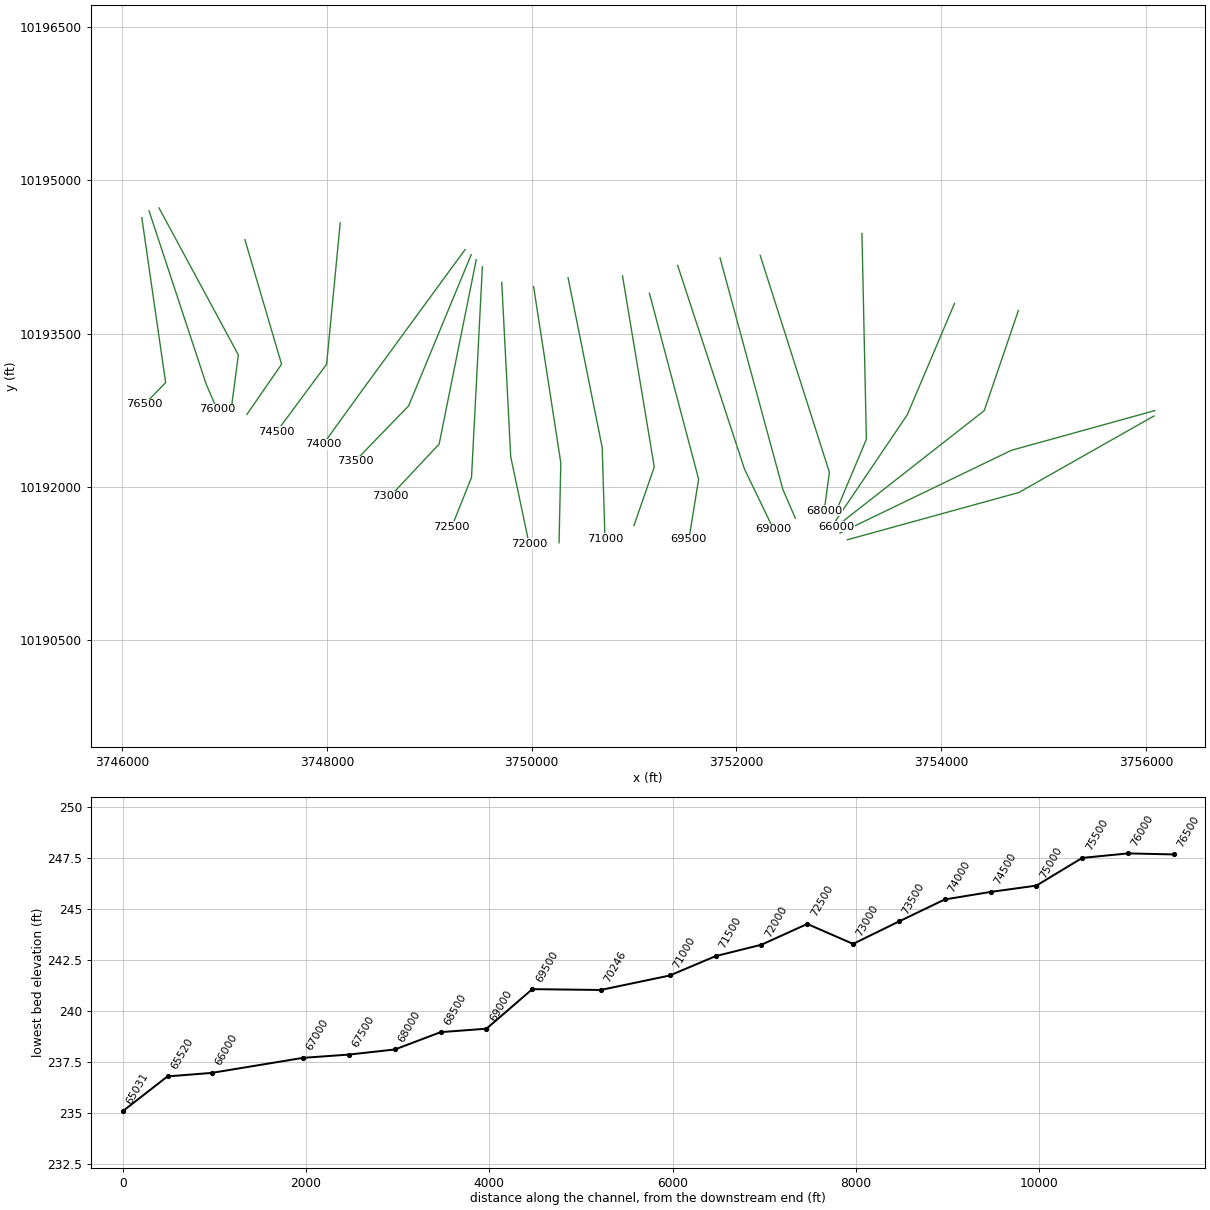
HEC-RAS study CANEY CREEK NORTH.prj: CANEY CREEK NORTH Base Level Engineering

--- CANEY CREEK NORTH.g01 (geometry) --- (continued)

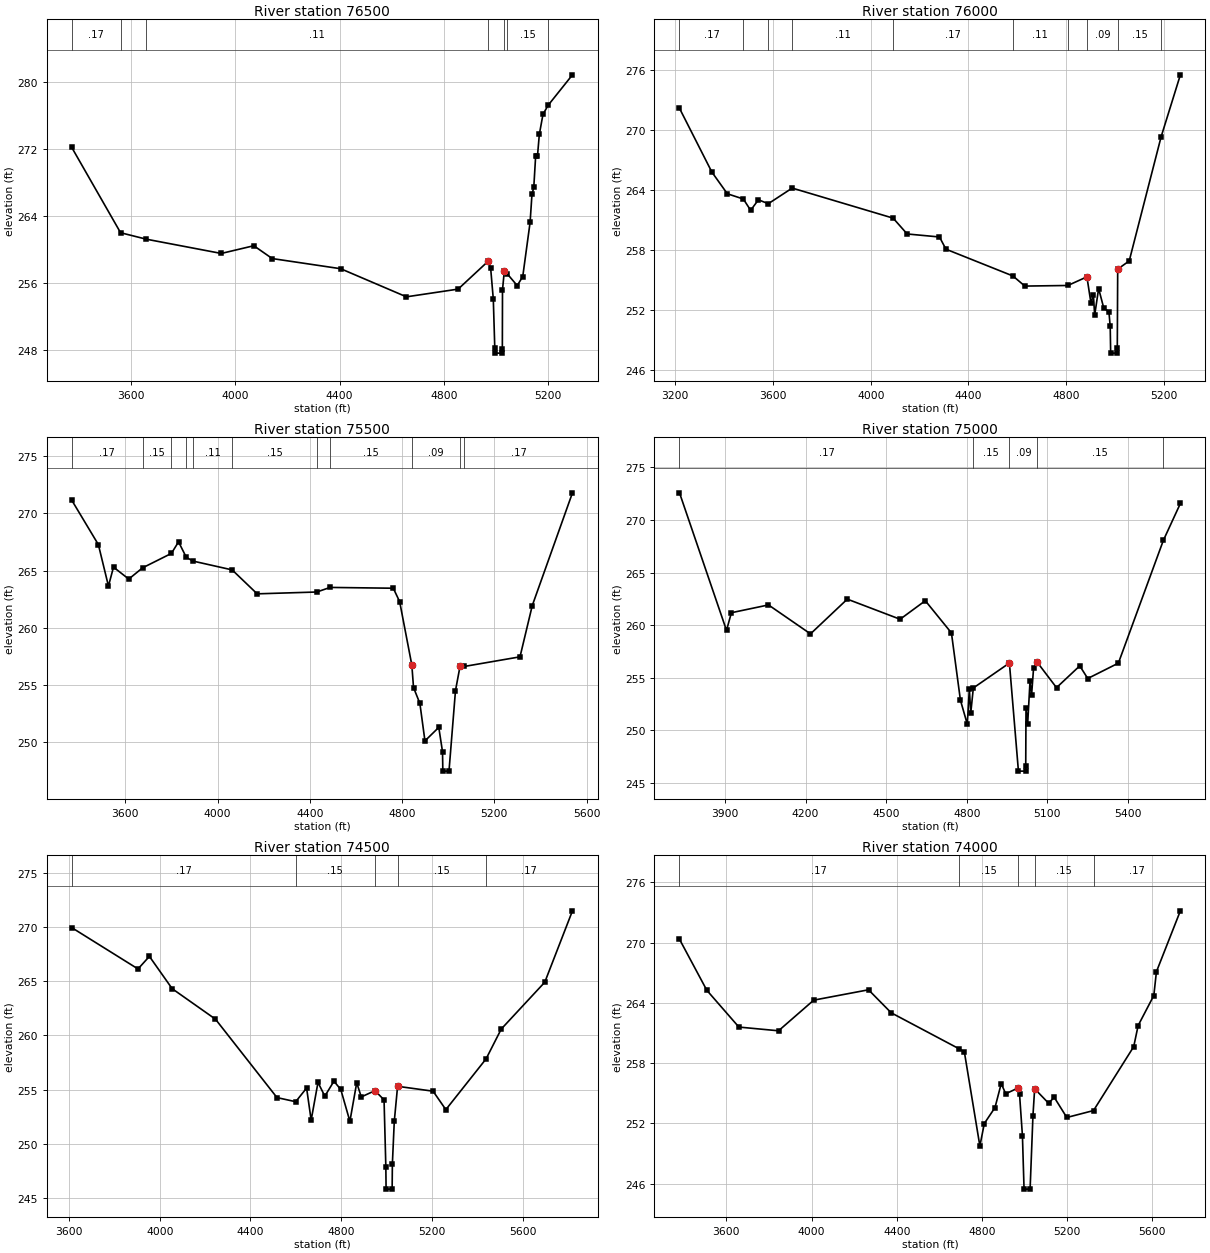
Type RM Length L Ch R = 1 ,76500   ,500,500,500
BEGIN DESCRIPTION:
CANEY CREEK NORTH 151.0
END DESCRIPTION:
XS GIS Cut Line= 3
       3746190.5     10194633.52      3746423.38     10193021.05
      3746217.87     10192811.09
#Sta/Elev= 30
  3370.8  272.22  3558.9  262.02  3657.7  261.25  3945.5  259.55  4070.4  260.47
  4141.2  258.94  4403.9  257.73  4656.4  254.38  4854.9   255.3  4969.7  258.61
  4979.8  257.77  4989.9   254.1  4995.6  248.27  4997.9  247.67  5024.1  247.67
  5024.6  248.17  5025.2   255.2  5032.2  257.46  5043.7  257.11  5081.7  255.72
  5102.9  256.79  5131.2  263.27  5138.3  266.58  5145.3  267.42  5152.5  271.17
  5159.5  271.16  5166.6  273.74  5180.7  276.14  5200.9  277.23  5293.8  280.84
#Mann= 7 ,-1 , 0
  3370.8     .17       0  3558.9     .15       0  3657.7     .11       0
  4969.7     .06       0  5032.2     .11       0  5043.7     .15       0
  5200.9     .11       0
Bank Sta=4969.7,5032.2
XS Rating Curve= 0 ,0
Exp/Cntr=0.3,0.1

Type RM Length L Ch R = 1 ,76000   ,500,500,500
BEGIN DESCRIPTION:
CANEY CREEK NORTH 150.0
END DESCRIPTION:
XS GIS Cut Line= 3
       3746260.9     10194700.34       3746819.1     10193007.18
       3746924.8     10192761.67
#Sta/Elev= 30
  3217.2  272.15  3349.6  265.79  3413.1  263.62  3478.5   263.1  3508.4  261.97
  3540.2  263.02  3580.7  262.63  3678.5  264.19  4091.6  261.19    4149  259.61
  4281.3  259.31  4307.8  258.09  4581.9  255.42  4630.7  254.41  4806.8  254.47
  4884.8  255.33  4901.1  252.75  4911.3  253.53  4916.5   251.5  4932.7  254.16
  4953.8  252.21  4974.8  251.86  4980.1  250.38    4982  247.72  5008.6  247.72
  5009.1  248.22  5010.8   256.1  5057.9  256.92  5188.4   269.3  5267.3  275.49
#Mann= 10 ,-1 , 0
  3217.2     .17       0  3478.5     .11       0  3580.7     .15       0
  3678.5     .11       0  4091.6     .17       0  4581.9     .11       0
  4806.8     .15       0  4884.8     .09       0  5010.8     .15       0
  5188.4     .17       0
Bank Sta=4884.8,5010.8
XS Rating Curve= 0 ,0
Exp/Cntr=0.3,0.1

Type RM Length L Ch R = 1 ,75500   ,500,500,500
BEGIN DESCRIPTION:
CANEY CREEK NORTH 149.0
END DESCRIPTION:
XS GIS Cut Line= 3
      3746358.28     10194729.22      3747133.47     10193292.27
       3747063.7     10192758.21
#Sta/Elev= 30
  3367.3  271.18  3483.4  267.28  3527.1  263.66    3549  265.31  3615.2  264.27
    3675  265.25    3800  266.51    3831  267.52  3864.5  266.17  3893.8  265.84
  4063.4  265.07  4171.8  262.98  4430.3  263.14    4488  263.54    4762  263.47
  4789.6  262.29  4842.3  256.76  4849.6   254.8  4877.2  253.41  4899.1  250.14
  4959.1  251.32  4975.3  249.19  4976.7   247.5  5003.4   247.5  5031.5  254.53
  5051.6  256.69  5069.8  256.64  5311.2  257.48  5364.3  261.95  5538.6   271.8
#Mann= 11 ,-1 , 0
  3367.3     .17       0    3675     .15       0    3800     .11       0
  3864.5     .17       0  3893.8     .11       0  4063.4     .15       0
  4430.3     .17       0    4488     .15       0  4842.3     .09       0
  5051.6     .15       0  5069.8     .17       0
Bank Sta=4842.3,5051.6
XS Rating Curve= 0 ,0
Exp/Cntr=0.3,0.1

Type RM Length L Ch R = 1 ,75000   ,500,500,500
BEGIN DESCRIPTION:
CANEY CREEK NORTH 148.0
END DESCRIPTION:
XS GIS Cut Line= 3
      3747197.61     10194418.95      3747555.84     10193201.14
      3747217.86     10192711.09
#Sta/Elev= 30
  3730.6  272.58  3905.6  259.51  3923.8  261.19  4061.9  261.93  4218.3  259.18
  4355.3  262.48  4551.9  260.57  4645.7  262.33    4743  259.27  4776.4  252.89
    4802   250.6  4809.7  253.95  4814.9  251.65  4824.5  254.04  4958.8  256.41
  4992.4  246.14  5019.1  246.14  5019.6  246.64  5020.6  252.17  5026.7  250.59
  5035.5  254.67  5041.5  253.42  5048.7   255.9  5062.5  256.48  5134.2  254.07
  5220.7  256.14  5250.5  254.94  5364.5   256.4  5531.9  268.06  5595.3  271.57
#Mann= 5 ,-1 , 0
  3730.6     .17       0  4824.5     .15       0  4958.8     .09       0
  5062.5     .15       0  5531.9     .17       0
Bank Sta=4958.8,5062.5
XS Rating Curve= 0 ,0
Exp/Cntr=0.3,0.1

Type RM Length L Ch R = 1 ,74500   ,500,500,500
BEGIN DESCRIPTION:
CANEY CREEK NORTH 147.0
END DESCRIPTION:
XS GIS Cut Line= 3
      3748128.69     10194582.59      3747995.69     10193200.47
      3747507.87     10192541.23
#Sta/Elev= 30
  3611.5  269.95  3904.4  266.13  3954.6  267.29  4055.1  264.31  4245.9   261.5
  4517.2  254.27  4599.7  253.89  4647.8  255.15  4667.9  252.19    4698  255.67
  4728.1   254.4  4768.3  255.78  4798.5  255.02  4838.7  252.08  4868.8  255.64
  4888.9  254.33  4949.2  254.91  4989.3  254.06  4997.2  247.91  4998.3  245.83
    5025  245.83    5026  248.15  5034.4  252.07    5049  255.31  5205.5  254.86
  5261.8  253.16  5439.2  257.84  5506.1  260.59  5698.1  264.91  5820.1  271.49
#Mann= 5 ,-1 , 0
  3611.5     .17       0  4599.7     .15       0  4949.2     .09       0
    5049     .15       0  5439.2     .17       0
Bank Sta=4949.2,5049
XS Rating Curve= 0 ,0
Exp/Cntr=0.3,0.1

Type RM Length L Ch R = 1 ,74000   ,500,500,500
BEGIN DESCRIPTION:
CANEY CREEK NORTH 146.0
END DESCRIPTION:
XS GIS Cut Line= 3
      3749347.56     10194320.95      3748391.78     10193013.06
      3747963.45     10192419.96
#Sta/Elev= 30
  3380.1  270.33  3508.4  265.25  3658.9  261.59    3845  261.22  4010.3  264.27
  4267.5   265.3    4374  263.01  4693.4  259.42  4717.6   259.1  4790.3  249.75
  4811.1  251.99  4861.3  253.58  4890.6  255.97  4911.5  254.95  4967.9  255.51
  4976.4  254.94  4990.1  250.78  4997.7  245.46  5026.1  245.46  5039.5  252.77
  5047.5  255.45  5112.5  254.02  5139.6  254.59  5198.4  252.59  5323.8  253.28
  5512.5  259.64  5533.3  261.74  5606.9  264.73  5619.2   267.1  5731.6  273.16
#Mann= 5 ,-1 , 0
  3380.1     .17       0  4693.4     .15       0  4967.9     .09       0
  5047.5     .15       0  5323.8     .17       0
Bank Sta=4967.9,5047.5
XS Rating Curve= 0 ,0
Exp/Cntr=0.3,0.1

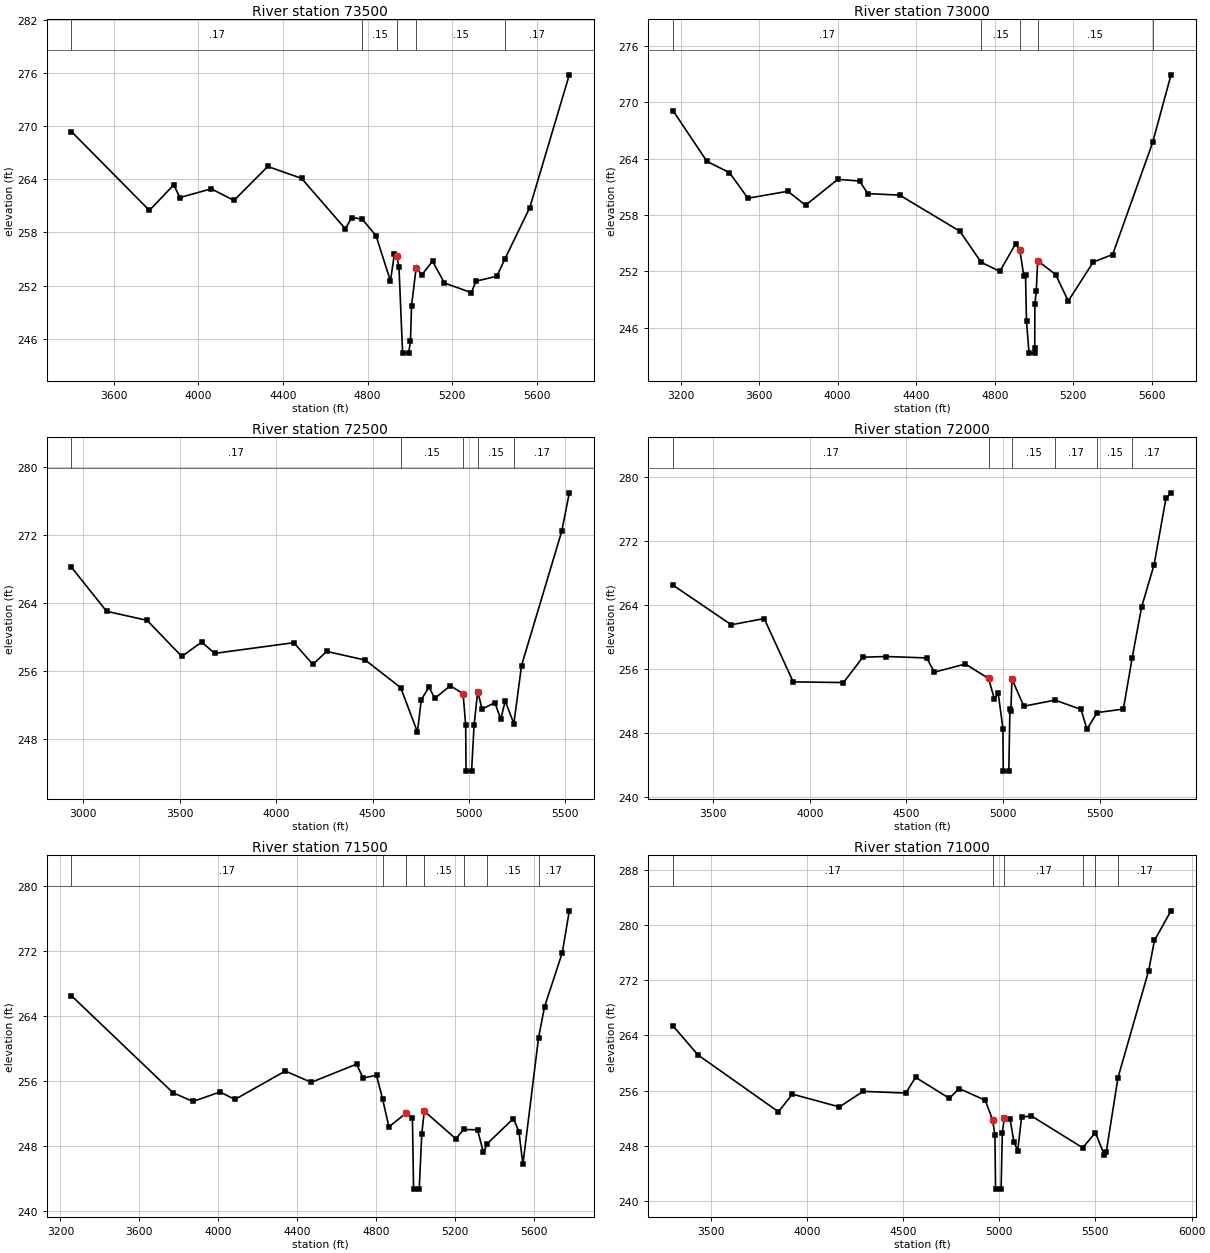
Type RM Length L Ch R = 1 ,73500   ,500,500,500
BEGIN DESCRIPTION:
CANEY CREEK NORTH 145.0
END DESCRIPTION:
XS GIS Cut Line= 3
      3749408.29      10194271.6      3748796.82      10192793.6
      3748272.58     10192252.22
#Sta/Elev= 30
  3400.5  269.38    3769  260.48  3884.1  263.37  3913.4  261.93  4061.2  262.92
  4168.7  261.61  4328.3  265.44    4488   264.1  4695.4   258.4  4724.7  259.68
  4774.7   259.5  4840.4  257.62  4908.3  252.51  4926.7  255.52  4937.8  255.38
  4948.6  254.08  4965.7  244.38  4994.2  244.38  5002.9  245.71  5008.1  249.75
  5029.4  253.94  5057.7  253.24  5107.1  254.76  5163.7  252.29    5291   251.2
  5312.2   252.5  5411.2  253.05  5449.9  255.04  5566.8   260.8  5753.6  275.78
#Mann= 5 ,-1 , 0
  3400.5     .17       0  4774.7     .15       0  4937.8     .09       0
  5029.4     .15       0  5449.9     .17       0
Bank Sta=4937.8,5029.4
XS Rating Curve= 0 ,0
Exp/Cntr=0.3,0.1

Type RM Length L Ch R = 1 ,73000   ,500,500,500
BEGIN DESCRIPTION:
CANEY CREEK NORTH 144.0
END DESCRIPTION:
XS GIS Cut Line= 3
      3749457.39     10194222.18      3749094.97     10192420.26
      3748617.85     10191911.07
#Sta/Elev= 30
    3162   269.1  3334.3  263.71  3448.7  262.52  3542.8  259.79  3746.3  260.53
  3836.3  259.04  4000.6   261.8  4111.8  261.62  4153.1  260.28  4315.8  260.12
  4621.8  256.28  4731.2  252.96  4825.8  251.99  4905.8  254.91  4927.8  254.29
  4948.2  251.46  4956.7  251.64  4961.8  246.67  4974.7  243.28  5003.2  243.28
  5003.7  243.78  5004.4  248.47  5011.7  249.93  5018.6  253.13  5110.4  251.65
  5174.4  248.83  5301.4  252.98  5400.6  253.79  5604.3  265.73  5697.8  272.94
#Mann= 5 ,-1 , 0
    3162     .17       0  4731.2     .15       0  4927.8     .09       0
  5018.6     .15       0  5604.3     .17       0
Bank Sta=4927.8,5018.6
XS Rating Curve= 0 ,0
Exp/Cntr=0.3,0.1

Type RM Length L Ch R = 1 ,72500   ,500,500,500
BEGIN DESCRIPTION:
CANEY CREEK NORTH 143.0
END DESCRIPTION:
XS GIS Cut Line= 3
      3749517.52     10194152.85      3749411.34     10192093.89
      3749217.87     10191611.11
#Sta/Elev= 30
  2938.3  268.23  3120.3  263.05  3330.6  261.98  3510.8  257.74  3613.7  259.43
  3681.1   258.1  4091.6  259.36  4190.3   256.8  4261.8  258.33  4462.1  257.31
  4645.8  254.07  4732.5  248.86  4752.5  252.66  4792.5  254.14  4822.6  252.81
  4902.7   254.3  4969.2  253.36  4982.8  249.66  4984.6  244.26  5013.3  244.26
  5026.4  249.71  5045.2  253.61  5067.7  251.55    5134  252.31  5164.6  250.38
  5187.8   252.5  5232.6  249.85  5272.4  256.67  5481.1  272.47  5520.1  276.97
#Mann= 5 ,-1 , 0
  2938.3     .17       0  4645.8     .15       0  4969.2     .09       0
  5045.2     .15       0  5232.6     .17       0
Bank Sta=4969.2,5045.2
XS Rating Curve= 0 ,0
Exp/Cntr=0.3,0.1

Type RM Length L Ch R = 1 ,72000   ,500,500,500
BEGIN DESCRIPTION:
CANEY CREEK NORTH 142.0
END DESCRIPTION:
XS GIS Cut Line= 3
      3749706.62     10194001.77      3749794.42     10192296.83
      3749973.82     10191445.32
#Sta/Elev= 30
  3292.8  266.51  3593.9  261.56  3764.1  262.34  3914.3  254.41  4174.7  254.33
  4274.8   257.5    4395  257.59  4605.2  257.41  4645.3  255.63  4805.5  256.65
  4925.7  254.84  4955.7  252.27  4975.7     253    5000  248.56  5001.8  243.24
  5030.5  243.24  5036.2  250.97  5041.3   250.8  5046.8  254.76  5108.1  251.37
  5270.4  252.13  5404.4  250.96  5435.1  248.48  5488.2  250.57  5623.6  251.01
  5668.9  257.39  5718.1  263.79  5782.6  269.08  5843.9  277.38  5870.2  278.08
#Mann= 6 ,-1 , 0
  3292.8     .17       0  4925.7     .09       0  5046.8     .15       0
  5270.4     .17       0  5488.2     .15       0  5668.9     .17       0
Bank Sta=4925.7,5046.8
XS Rating Curve= 0 ,0
Exp/Cntr=0.3,0.1

Type RM Length L Ch R = 1 ,71500   ,500,500,500
BEGIN DESCRIPTION:
CANEY CREEK NORTH 141.0
END DESCRIPTION:
XS GIS Cut Line= 3
      3750017.87     10193960.37      3750283.62     10192236.83
      3750266.63     10191455.72
#Sta/Elev= 30
  3256.1  266.51  3771.4  254.55  3872.6  253.48  4009.9  254.65  4085.1  253.73
  4340.9  257.23  4472.3  255.84  4702.3  258.08  4735.1  256.37  4803.5  256.71
    4834  253.81  4866.5  250.35  4955.2  252.08  4985.6  251.44  4991.4  242.68
  5020.1  242.68    5033   249.5  5045.8  252.29  5205.8  248.88  5245.3  250.03
  5315.8  249.99  5345.8   247.2  5365.4  248.29  5498.1  251.38  5525.9  249.76
  5545.9  245.73  5625.4  261.35  5655.9  265.16  5745.9  271.83  5781.3  276.97
#Mann= 7 ,-1 , 0
  3256.1     .17       0    4834     .15       0  4955.2     .09       0
  5045.8     .15       0  5245.3     .17       0  5365.4     .15       0
  5625.4     .17       0
Bank Sta=4955.2,5045.8
XS Rating Curve= 0 ,0
Exp/Cntr=0.3,0.1

Type RM Length L Ch R = 1 ,71000   ,754,754,754
BEGIN DESCRIPTION:
CANEY CREEK NORTH 140.0
END DESCRIPTION:
XS GIS Cut Line= 3
      3750354.28     10194048.28      3750687.87     10192387.24
      3750715.28     10191494.96
#Sta/Elev= 30
  3305.8  265.33  3435.5  261.14  3852.9  252.93  3925.1  255.48  4169.9  253.63
  4292.3  255.88  4514.5  255.64  4565.4  257.91  4741.1  254.88  4792.1  256.28
  4926.8  254.61  4965.5  251.78  4977.7  249.62  4981.1  241.73  5009.8  241.73
  5016.2  249.88  5026.2  251.96  5056.2  251.89  5076.2  248.62  5096.2  247.28
  5116.2  252.15  5166.8  252.34  5433.7  247.72  5499.8   249.9  5546.4  246.66
  5556.4  247.13  5617.1  257.86  5776.5  273.35  5806.6  277.73  5892.7  282.02
#Mann= 6 ,-1 , 0
  3305.8     .17       0  4965.5     .09       0  5026.2     .17       0
  5433.7     .17       0  5499.8     .15       0  5617.1     .17       0
Bank Sta=4965.5,5026.2
XS Rating Curve= 0 ,0
Exp/Cntr=0.3,0.1

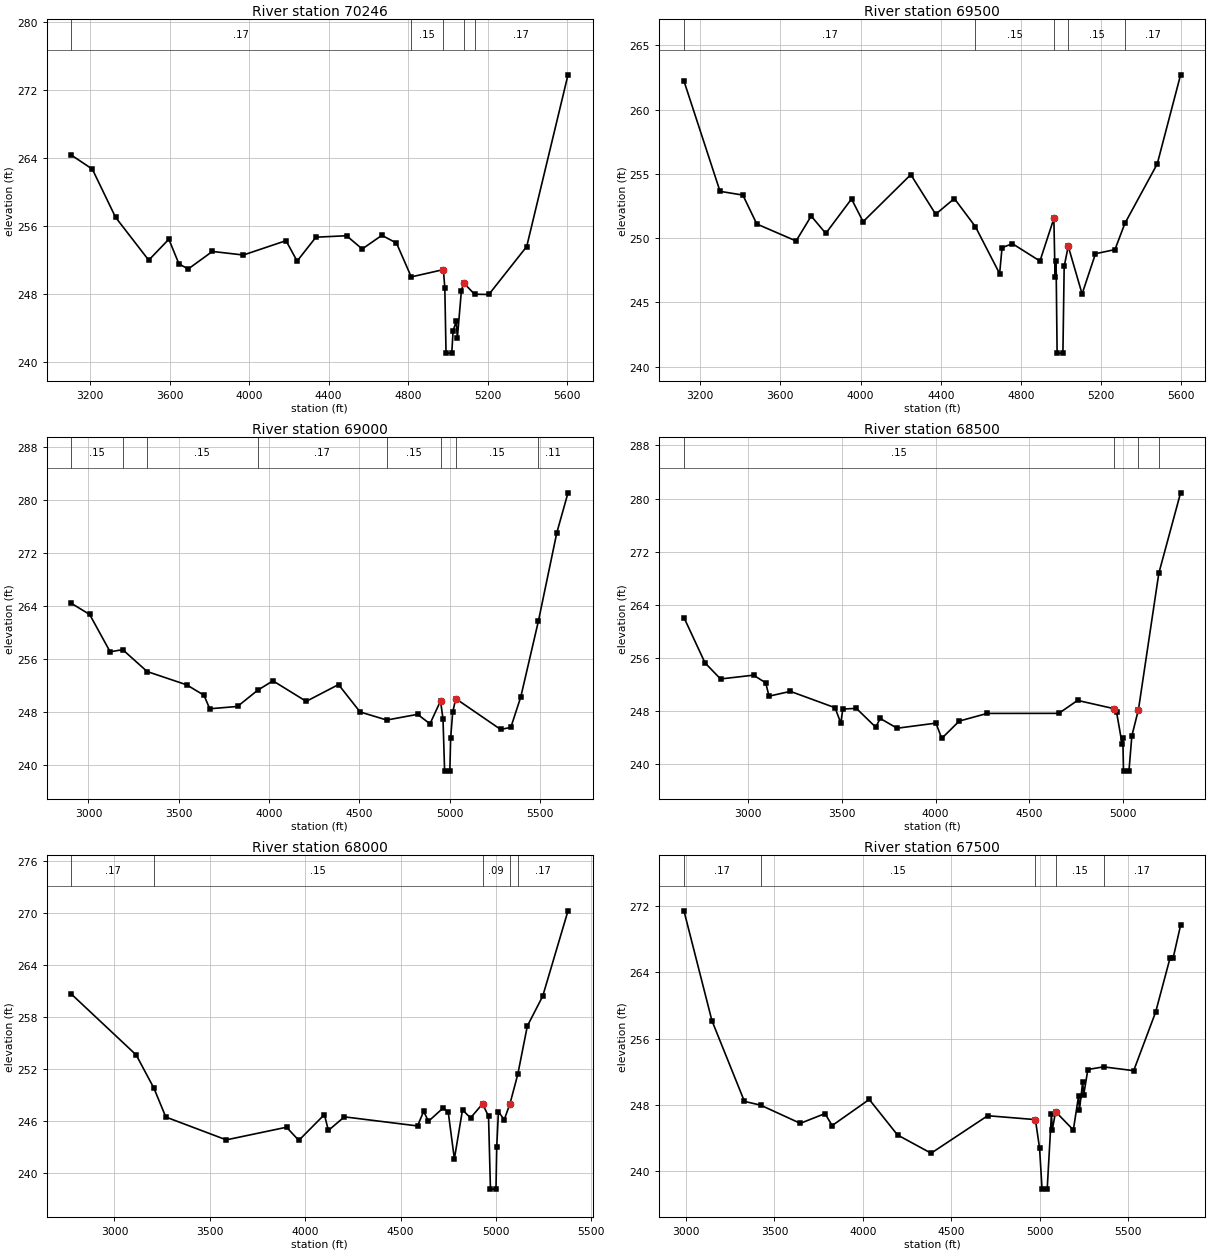
Type RM Length L Ch R = 1 ,70246   ,746,746,746
BEGIN DESCRIPTION:
CANEY CREEK NORTH 138.0
END DESCRIPTION:
XS GIS Cut Line= 3
      3750886.38     10194064.97      3751196.81     10192196.38
      3750998.69     10191624.74
#Sta/Elev= 30
  3105.8  264.35  3211.2   262.7    3328  257.03    3495  251.97  3596.3  254.44
    3647  251.54  3693.5  250.93  3815.4     253  3971.4  252.58    4186  254.27
  4241.8  251.86  4336.3  254.68  4490.6  254.85  4569.5  253.29  4668.3   254.9
  4741.8  253.99  4816.1     250  4977.9  250.86  4985.1   248.7  4991.2  241.02
  5020.1  241.02  5026.8  243.66  5042.6  244.77    5048  242.77  5068.5  248.36
  5079.7  249.31  5134.5  247.96  5206.7  247.93  5397.2  253.58    5605  273.81
#Mann= 5 ,-1 , 0
  3105.8     .17       0  4816.1     .15       0  4977.9     .09       0
  5079.7     .15       0  5134.5     .17       0
Bank Sta=4977.9,5079.7
XS Rating Curve= 0 ,0
Exp/Cntr=0.3,0.1

Type RM Length L Ch R = 1 ,69500   ,500,500,500
BEGIN DESCRIPTION:
CANEY CREEK NORTH 137.0
END DESCRIPTION:
XS GIS Cut Line= 3
      3751149.34     10193895.07      3751630.23      10192076.9
      3751534.71     10191487.89
#Sta/Elev= 30
  3119.3  262.22  3299.3  253.64  3413.1  253.35  3482.7   251.1  3678.7  249.78
    3754  251.72  3826.8  250.37  3955.2  253.05    4013  251.28  4250.9  254.94
    4375  251.86  4468.1  253.08  4572.9   250.9    4694  247.24  4706.1  249.26
  4757.8  249.57  4895.2  248.22  4964.6  251.53  4970.5  246.97  4975.6  248.19
  4980.8  241.06  5009.7  241.06    5016   247.8  5036.3  249.37  5105.4  245.66
  5172.1  248.79  5269.3  249.11  5318.6  251.14  5480.2  255.77  5596.7   262.7
#Mann= 5 ,-1 , 0
  3119.3     .17       0  4572.9     .15       0  4964.6     .09       0
  5036.3     .15       0  5318.6     .17       0
Bank Sta=4964.6,5036.3
XS Rating Curve= 0 ,0
Exp/Cntr=0.3,0.1

Type RM Length L Ch R = 1 ,69000   ,500,500,500
BEGIN DESCRIPTION:
CANEY CREEK NORTH 136.0
END DESCRIPTION:
XS GIS Cut Line= 3
      3751425.06     10194167.39      3752077.67     10192176.84
      3752362.54     10191585.37
#Sta/Elev= 30
  2905.2  264.44  3006.6  262.76  3119.9  257.13  3189.8  257.45  3324.8  254.15
  3544.3  252.14  3639.8  250.57  3671.7  248.53  3825.6  248.88    3937  251.32
  4021.8  252.75  4206.3  249.65  4385.2  252.18  4504.6  248.05  4652.5  246.83
    4823  247.69  4891.9  246.26  4950.3  249.71    4964  246.99  4972.9  239.12
  5001.9  239.12  5006.4  244.11  5017.5  247.97  5034.6  250.06  5283.4  245.41
  5339.8  245.72  5394.9  250.32  5492.4  261.75  5594.7  275.12  5656.5  281.12
#Mann= 8 ,-1 , 0
  2905.2     .15       0  3189.8     .17       0  3324.8     .15       0
    3937     .17       0  4652.5     .15       0  4950.3     .09       0
  5034.6     .15       0  5492.4     .11       0
Bank Sta=4950.3,5034.6
XS Rating Curve= 0 ,0
Exp/Cntr=0.3,0.1

Type RM Length L Ch R = 1 ,68500   ,500,500,500
BEGIN DESCRIPTION:
CANEY CREEK NORTH 135.0
END DESCRIPTION:
XS GIS Cut Line= 3
      3751839.28     10194239.65      3752452.75     10191977.77
      3752574.94     10191694.61
#Sta/Elev= 30
  2656.4  262.08  2768.9  255.25  2851.8  252.83  3027.9   253.4  3092.8  252.25
  3110.8  250.24  3224.8  250.96  3463.1   248.5  3494.2  246.17  3504.6   248.3
  3577.1   248.4  3680.7  245.56  3704.1  246.89  3794.7  245.41  4001.9  246.18
    4033  243.88  4126.6  246.49  4275.5  247.64  4658.2  247.65  4758.3   249.6
  4955.1  248.34  4966.4  247.87  4995.7  243.11    5000  243.91  5003.6  238.95
  5032.7  238.95  5048.1  244.24  5083.5  248.23  5192.2  268.75  5308.4  280.86
#Mann= 4 ,-1 , 0
  2656.4     .15       0  4955.1     .09       0  5083.5     .15       0
  5192.2     .17       0
Bank Sta=4955.1,5083.5
XS Rating Curve= 0 ,0
Exp/Cntr=0.3,0.1

Type RM Length L Ch R = 1 ,68000   ,500,500,500
BEGIN DESCRIPTION:
CANEY CREEK NORTH 134.0
END DESCRIPTION:
XS GIS Cut Line= 3
      3752231.59      10194264.9      3752907.68     10192144.05
      3752856.99     10191769.67
#Sta/Elev= 30
    2774  260.63  3113.9   253.6    3207  249.75  3269.1  246.43  3586.2  243.79
    3902  245.25  3966.4  243.73  4100.5  246.71  4121.5  244.88  4205.4  246.45
  4588.8   245.4    4621  247.08  4646.3  245.94  4722.9  247.47  4749.8     247
    4782  241.59  4824.7  247.26  4866.7  246.32  4929.7  247.95  4961.1  246.52
  4971.2   238.1  5000.3   238.1    5004  242.95  5013.1  247.05  5043.4  246.12
  5073.6  247.97  5114.4  251.35  5164.5  256.94  5245.2  260.39  5377.8  270.25
#Mann= 5 ,-1 , 0
    2774     .17       0    3207     .15       0  4929.7     .09       0
  5073.6     .15       0  5114.4     .17       0
Bank Sta=4929.7,5073.6
XS Rating Curve= 0 ,0
Exp/Cntr=0.3,0.1

Type RM Length L Ch R = 1 ,67500   ,500,500,500
BEGIN DESCRIPTION:
CANEY CREEK NORTH 133.0
END DESCRIPTION:
XS GIS Cut Line= 3
       3753225.5     10194479.32      3753268.91     10192467.49
      3752959.95     10191731.73
#Sta/Elev= 30
  2987.7   271.4    3146  258.16  3329.8  248.43  3421.9  247.97  3646.1  245.78
  3786.1  246.96  3826.1  245.51  4036.2  248.66  4196.2  244.38  4386.3  242.18
  4706.4   246.7  4976.4  246.23    5000   242.8  5014.1  237.85  5043.2  237.85
    5067   246.9  5072.4  245.02  5090.7  247.19  5191.2  244.98  5220.4  249.04
  5225.8  247.41  5244.1   250.8  5249.5  249.17  5273.3  252.27  5361.8  252.59
  5532.6  252.13  5656.8  259.19    5739  265.76  5755.3  265.66    5798  269.66
#Mann= 5 ,-1 , 0
  2987.7     .17       0  3421.9     .15       0  4976.4     .09       0
  5090.7     .15       0  5361.8     .17       0
Bank Sta=4976.4,5090.7
XS Rating Curve= 0 ,0
Exp/Cntr=0.3,0.1

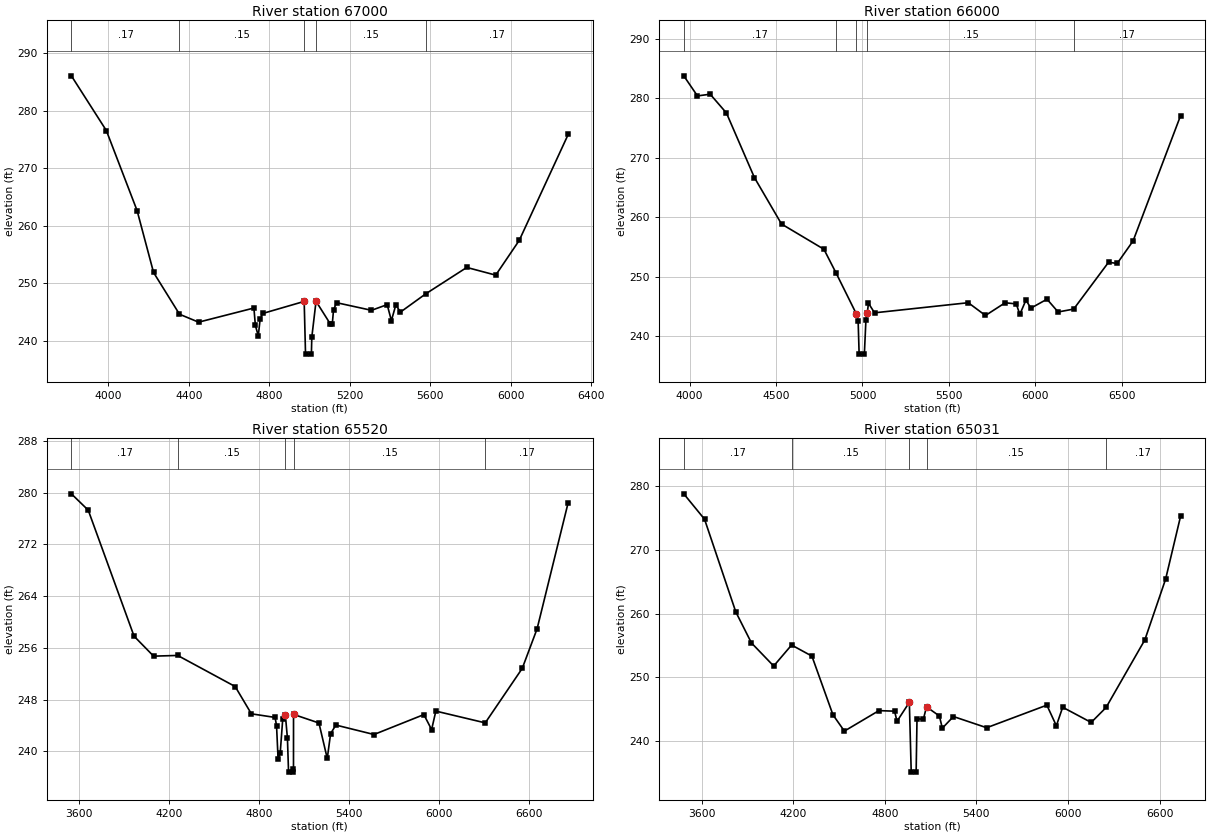
Type RM Length L Ch R = 1 ,67000   ,1000,1000,1000
BEGIN DESCRIPTION:
CANEY CREEK NORTH 132.0
END DESCRIPTION:
XS GIS Cut Line= 3
       3754130.5     10193796.45      3753668.58     10192706.82
       3752948.8     10191641.12
#Sta/Elev= 30
  3816.5   286.1  3990.3  276.58  4143.2  262.65    4225  251.89  4353.9  244.63
  4448.9  243.25  4723.8  245.71  4731.1  242.68  4745.6  240.87  4754.7  243.78
  4767.3  244.76  4973.7  246.86  4980.4  237.69  5009.5  237.69  5011.6  240.64
  5032.6  246.88  5104.5  242.89  5113.5  242.97  5119.5  245.37  5134.5  246.64
  5308.3  245.31  5386.2   246.3  5407.2  243.52  5429.3  246.26  5452.1     245
  5577.2  248.16  5781.9  252.77  5925.8  251.43  6042.6  257.47    6286   275.9
#Mann= 5 ,-1 , 0
  3816.5     .17       0  4353.9     .15       0  4973.7     .09       0
  5032.6     .15       0  5577.2     .17       0
Bank Sta=4973.7,5032.6
XS Rating Curve= 0 ,0
Exp/Cntr=0.3,0.1

Type RM Length L Ch R = 1 ,66000   ,480,480,480
BEGIN DESCRIPTION:
CANEY CREEK NORTH 130.0
END DESCRIPTION:
XS GIS Cut Line= 3
      3754753.71     10193726.02      3754420.19     10192747.39
      3752971.65     10191611.65
#Sta/Elev= 30
  3966.1  283.77  4045.3  280.39  4118.9  280.68  4212.9  277.52  4374.9  266.65
  4531.7  258.84  4777.1  254.59  4848.5  250.53  4965.2  243.69    4975  242.52
  4980.8  236.95    5011  236.95  5020.2  242.77  5028.3  243.91  5034.6  245.52
  5069.9   243.9  5612.3   245.6  5711.7  243.45  5825.6  245.59  5889.8   245.4
  5910.6  243.64  5945.9  246.03  5974.8  244.69  6067.9  246.19  6132.1  244.04
  6222.3  244.53  6424.1  252.41  6473.8   252.2    6566     256  6840.7  277.07
#Mann= 5 ,-1 , 0
  3966.1     .17       0  4848.5     .15       0  4965.2     .09       0
  5028.3     .15       0  6222.3     .17       0
Bank Sta=4965.2,5028.3
XS Rating Curve= 0 ,0
Exp/Cntr=0.3,0.1

Type RM Length L Ch R = 1 ,65520   ,489,489,489
BEGIN DESCRIPTION:
CANEY CREEK NORTH 129.0
END DESCRIPTION:
XS GIS Cut Line= 3
      3756086.15     10192747.48      3754685.71     10192359.46
      3753011.25      10191550.8
#Sta/Elev= 30
  3546.8  279.83  3659.2   277.3  3964.7  257.81    4095  254.72  4255.6  254.83
    4639  250.02    4747   245.8    4905  245.24  4914.8  243.98  4925.1  238.81
  4939.2  239.72  4956.3  245.06  4973.5  245.64  4987.4  242.03  4994.9  236.78
  5027.1  236.78  5027.8  237.28  5028.1  245.71  5197.5  244.38    5253  238.89
  5275.2  242.73  5310.4  244.06  5564.6   242.6  5897.1  245.68  5948.8  243.36
    5977  246.22  6306.4   244.4  6553.2  252.83  6652.3  258.96  6859.5  278.48
#Mann= 5 ,-1 , 0
  3546.8     .17       0  4255.6     .15       0  4973.5     .09       0
  5028.1     .15       0  6306.4     .17       0
Bank Sta=4973.5,5028.1
XS Rating Curve= 0 ,0
Exp/Cntr=0.3,0.1

Type RM Length L Ch R = 1 ,65031   ,531,531,531
BEGIN DESCRIPTION:
CANEY CREEK NORTH 128.0
END DESCRIPTION:
XS GIS Cut Line= 3
      3756078.05     10192694.94      3754758.33     10191946.87
      3753083.37     10191484.88
#Sta/Elev= 30
    3483  278.82    3619  274.83  3823.9  260.25  3926.3  255.38    4072  251.75
  4189.3  255.05  4322.4  253.31  4460.3  244.08  4535.1  241.52  4761.6  244.74
    4864  244.65  4879.9  243.06  4960.7  246.04    4973  235.07  5005.2  235.07
  5010.9  243.47  5052.4  243.37  5073.1  245.33  5157.4   243.9  5176.8  241.98
  5249.5  243.81  5467.3  242.05  5861.5   245.6  5923.7  242.36  5965.2  245.27
  6151.9  242.88  6249.4  245.23  6503.4  255.86  6639.5  265.41  6737.5   275.3
#Mann= 5 ,-1 , 0
    3483     .17       0  4189.3     .15       0  4960.7     .09       0
  5073.1     .15       0  6249.4     .17       0
Bank Sta=4960.7,5073.1
XS Rating Curve= 0 ,0
Exp/Cntr=0.3,0.1