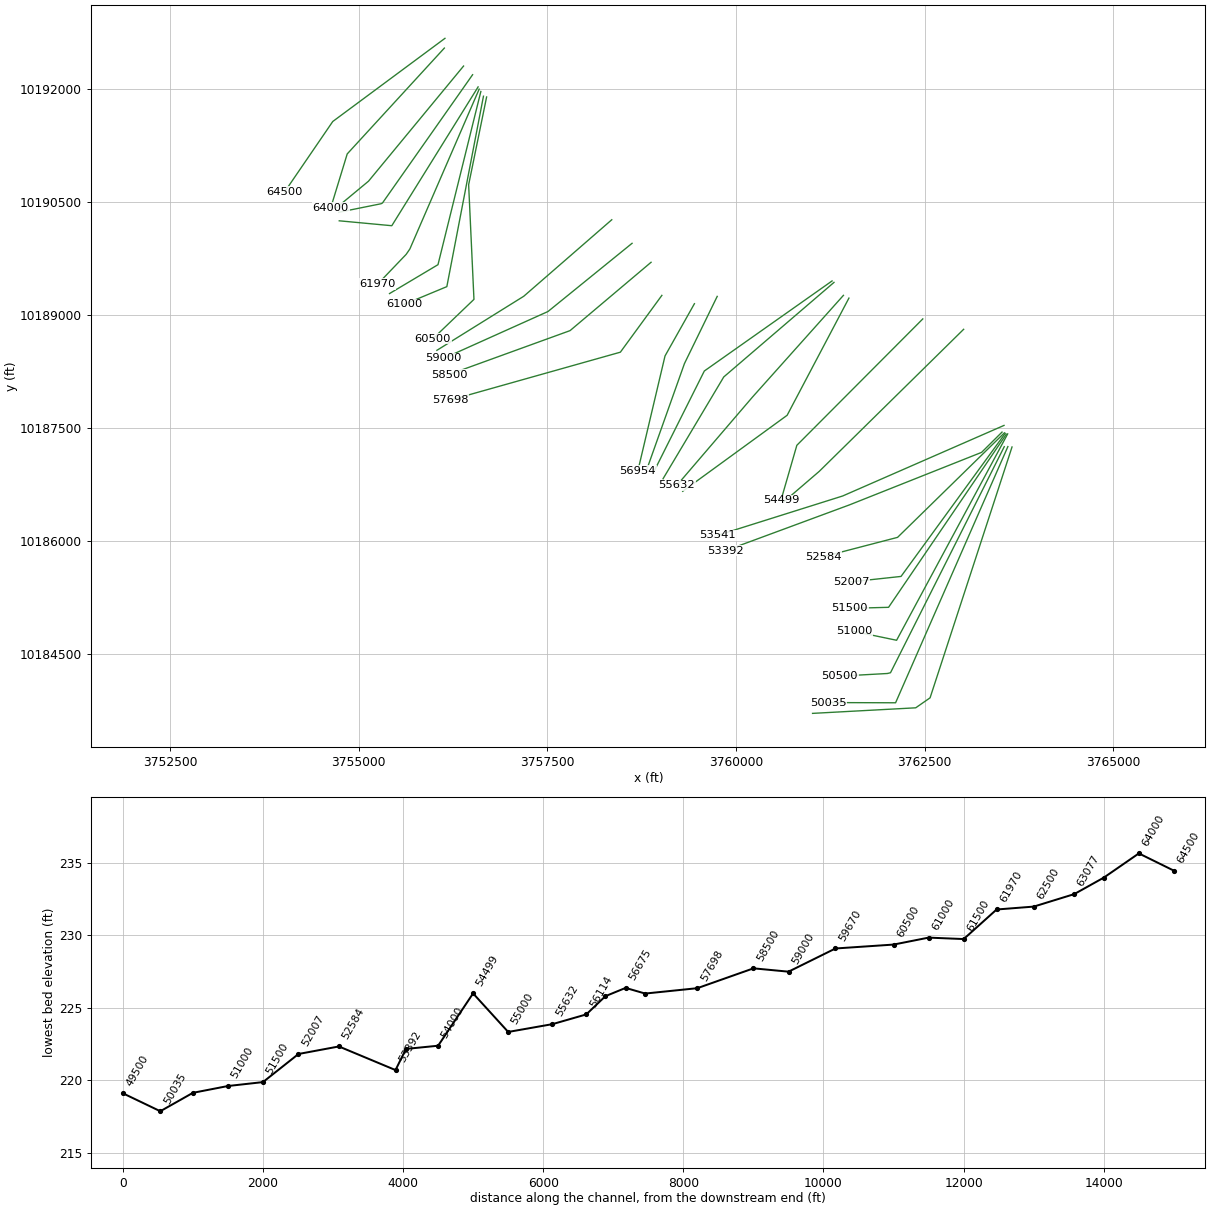
HEC-RAS study CANEY CREEK NORTH.prj: CANEY CREEK NORTH Base Level Engineering

--- CANEY CREEK NORTH.g01 (geometry) --- (continued)

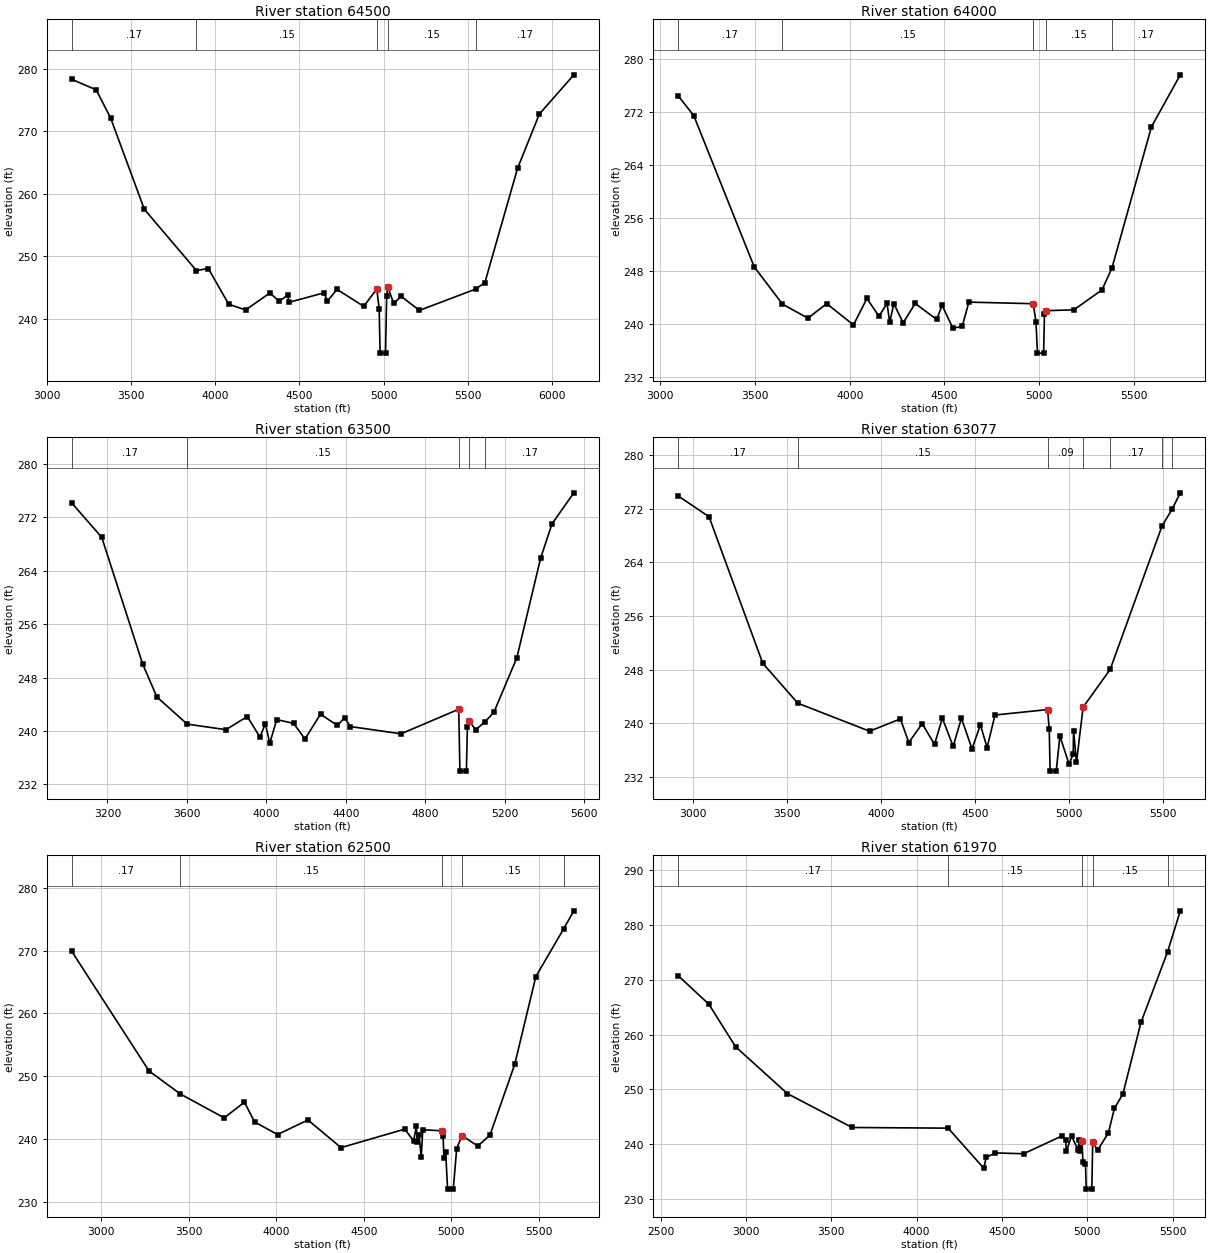
Type RM Length L Ch R = 1 ,64500   ,500,500,500
BEGIN DESCRIPTION:
CANEY CREEK NORTH 127.0
END DESCRIPTION:
XS GIS Cut Line= 3
      3756142.74     10192670.73      3754655.51     10191567.58
       3754018.4     10190635.16
#Sta/Elev= 30
  3148.3   278.3    3294  276.62  3379.5  272.11  3579.8  257.49  3888.9  247.68
  3959.6  248.01  4080.6  242.29  4180.8  241.37  4324.8  244.09  4381.1  242.75
  4431.2  243.78  4437.4  242.59  4646.1  244.11    4667  242.78  4723.3  244.67
  4881.9  241.95  4959.7  244.72  4973.7  241.53  4979.3  234.46  5011.5  234.46
  5018.2  243.61  5024.2  245.03  5060.1  242.45  5104.8  243.54  5212.6   241.3
  5546.7  244.72  5601.3  245.76  5795.1  264.04  5924.4  272.73  6129.3  279.02
#Mann= 5 ,-1 , 0
  3148.3     .17       0  3888.9     .15       0  4959.7     .09       0
  5024.2     .15       0  5546.7     .17       0
Bank Sta=4959.7,5024.2
XS Rating Curve= 0 ,0
Exp/Cntr=0.3,0.1

Type RM Length L Ch R = 1 ,64000   ,500,500,500
BEGIN DESCRIPTION:
CANEY CREEK NORTH 126.0
END DESCRIPTION:
XS GIS Cut Line= 3
      3756134.67     10192541.44      3754847.14     10191137.41
      3754629.75     10190425.99
#Sta/Elev= 30
    3095  274.46  3177.7  271.45  3496.5  248.65  3645.4  243.04  3779.5  240.92
  3878.8  243.11    4020   239.9  4090.9   243.9  4154.4   241.2  4196.9  243.15
  4211.1  240.27  4232.7  243.11    4282  240.21  4345.5  243.14    4459  240.73
  4487.4  242.86  4544.1  239.41  4593.4  239.68  4628.7  243.34  4968.3   243.1
  4982.5  240.37  4990.5  235.65  5022.8  235.65  5027.5  241.58    5038  242.05
  5182.5  242.18  5330.8  245.18  5383.3  248.48  5591.7  269.77  5743.9  277.61
#Mann= 5 ,-1 , 0
    3095     .17       0  3645.4     .15       0  4968.3     .09       0
    5038     .15       0  5383.3     .17       0
Bank Sta=4968.3,5038
XS Rating Curve= 0 ,0
Exp/Cntr=0.3,0.1

Type RM Length L Ch R = 1 ,63500   ,423,423,423
BEGIN DESCRIPTION:
CANEY CREEK NORTH 125.0
END DESCRIPTION:
XS GIS Cut Line= 3
      3756389.17     10192302.98      3755129.25     10190775.69
      3754707.98     10190425.99
#Sta/Elev= 30
  3020.1  274.17  3171.6     269  3377.4  250.03  3449.1  245.09  3601.7  241.02
    3797  240.19  3903.8  242.16  3967.7  239.08    3995  241.08  4017.2  238.16
  4052.3   241.7  4137.4  241.13  4194.3  238.79  4272.5  242.51  4357.8  240.82
  4393.7  241.99  4422.4  240.66  4677.7  239.57  4968.2  243.25  4974.2  233.98
  5006.7  233.98  5011.7  240.56  5018.2  241.55  5053.8  240.18    5102  241.41
  5145.8  242.84  5260.4  250.94  5380.2  265.87  5437.5  271.02  5547.5  275.67
#Mann= 5 ,-1 , 0
  3020.1     .17       0  3601.7     .15       0  4968.2     .09       0
  5018.2     .15       0    5102     .17       0
Bank Sta=4968.2,5018.2
XS Rating Curve= 0 ,0
Exp/Cntr=0.3,0.1

Type RM Length L Ch R = 1 ,63077   ,577,577,577
BEGIN DESCRIPTION:
CANEY CREEK NORTH 124.0
END DESCRIPTION:
XS GIS Cut Line= 4
      3756509.08     10192188.06      3755314.53     10190486.62
      3755295.02     10190476.46      3754736.63     10190363.52
#Sta/Elev= 30
  2921.1  273.94  3085.5  270.83  3371.3  248.94  3557.8  242.98  3939.5   238.8
  4103.3  240.64  4147.8  237.11  4219.2  239.93  4284.6  236.83  4326.4  240.75
  4383.6  236.54  4427.5  240.73  4484.2  236.17  4528.6  239.76  4564.3  236.35
  4606.2  241.22  4885.9  242.03  4894.6  239.13  4899.3  232.84  4931.8  232.84
  4951.3   238.1    5000  233.87    5022  235.37  5024.1  238.89  5039.5  234.14
  5074.8  242.38  5218.8  248.03    5495  269.48  5549.2     272  5591.7   274.4
#Mann= 7 ,-1 , 0
  2921.1     .17       0  3557.8     .15       0  4885.9     .09       0
  5074.8     .15       0  5218.8     .17       0    5495     .15       0
  5549.2     .17       0
Bank Sta=4885.9,5074.8
XS Rating Curve= 0 ,0
Exp/Cntr=0.3,0.1

Type RM Length L Ch R = 1 ,62500   ,530,530,530
BEGIN DESCRIPTION:
CANEY CREEK NORTH 123.0
END DESCRIPTION:
XS GIS Cut Line= 3
      3756582.12     10192026.25      3755438.11     10190185.13
      3754741.75     10190250.26
#Sta/Elev= 30
  2832.4  269.94  3274.1  250.83    3453  247.16  3703.2  243.35  3818.9  245.85
  3876.8   242.7  4007.8  240.69  4181.4  243.01  4370.3   238.6    4734  241.55
  4784.8  239.68  4800.1  241.99    4806  239.48  4815.5  240.66  4828.2   237.1
  4836.8  241.45  4945.9  241.29  4952.5  240.53  4958.3  236.88  4967.8  237.83
  4978.7  231.98  5011.2  231.98  5030.4  238.42  5060.5  240.52  5150.9  238.86
  5220.5  240.59  5361.8  251.88  5482.4  265.89  5640.8  273.48  5699.4  276.38
#Mann= 5 ,-1 , 0
  2832.4     .17       0    3453     .15       0  4945.9     .09       0
  5060.5     .15       0  5640.8     .17       0
Bank Sta=4945.9,5060.5
XS Rating Curve= 0 ,0
Exp/Cntr=0.3,0.1

Type RM Length L Ch R = 1 ,61970   ,470,470,470
BEGIN DESCRIPTION:
CANEY CREEK NORTH 122.0
END DESCRIPTION:
XS GIS Cut Line= 4
      3756596.08     10191996.84       3755677.8     10189877.07
      3755628.28     10189804.83       3755251.6     10189411.52
#Sta/Elev= 30
  2602.3  270.75    2782  265.55  2939.2  257.76  3242.7  249.21  3622.1  243.03
  4184.3  242.91  4393.5  235.58  4406.8  237.57  4461.2  238.39  4626.6  238.24
  4854.2  241.53  4872.2  240.83  4877.7  238.73  4907.5  241.47  4944.4  239.01
  4953.3   240.7  4959.3  238.77  4968.2  240.62  4974.2  236.77  4989.1  236.28
  4993.7  231.78  5026.2  231.78  5031.4   240.4  5059.7  238.88  5123.2  242.03
  5158.4  246.52  5208.1  249.14  5314.1   262.2  5469.8  275.08  5544.6  282.58
#Mann= 5 ,-1 , 0
  2602.3     .17       0  4184.3     .15       0  4968.2     .09       0
  5031.4     .15       0  5469.8     .17       0
Bank Sta=4968.2,5031.4
XS Rating Curve= 0 ,0
Exp/Cntr=0.3,0.1

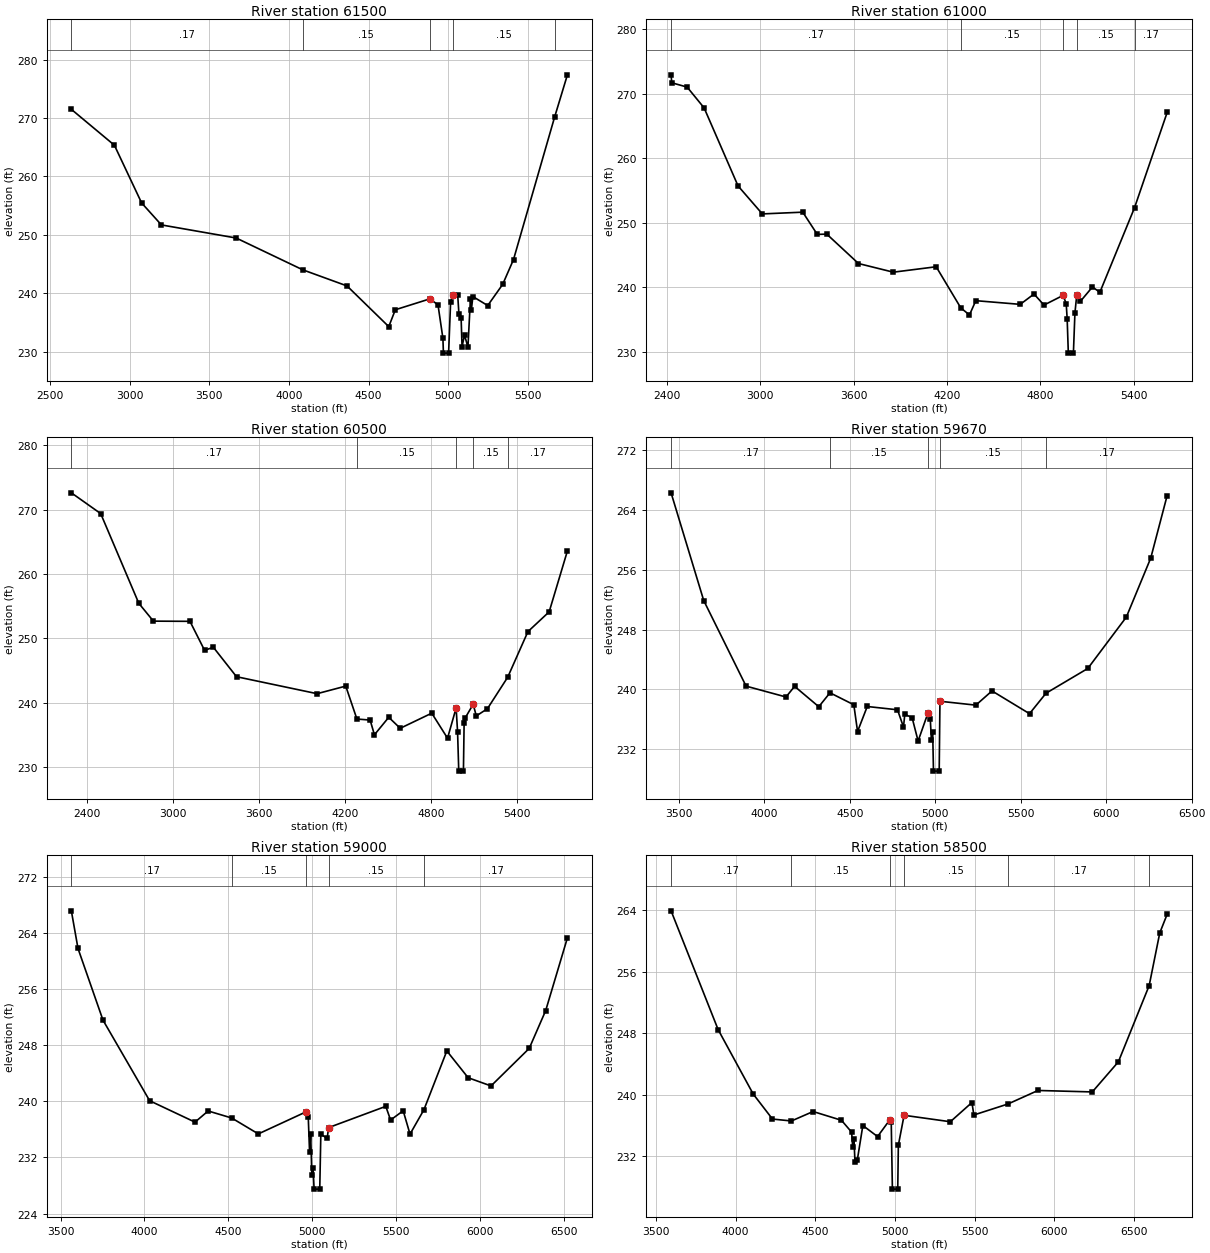
Type RM Length L Ch R = 1 ,61500   ,500,500,500
BEGIN DESCRIPTION:
CANEY CREEK NORTH 121.0
END DESCRIPTION:
XS GIS Cut Line= 3
      3756618.45     10191965.56      3756050.35     10189668.26
      3755408.09     10189285.25
#Sta/Elev= 30
  2633.5   271.5  2903.8  265.35  3074.6  255.47  3198.9   251.7  3668.2  249.46
  4086.4  244.01  4364.2  241.25  4626.3  234.28  4667.5  237.17  4883.8  239.03
  4935.3  238.02  4966.2  232.28  4969.4  229.74  5001.9  229.74  5014.6  238.52
  5027.9  239.78  5059.1  239.69  5066.9  236.38  5080.5  235.74  5086.3  230.85
  5101.9  232.85  5123.3  230.74  5138.9  239.01  5144.7  237.12  5154.3  239.43
  5247.4  237.89  5341.3  241.51  5409.4  245.77  5667.1  270.14  5747.8  277.41
#Mann= 5 ,-1 , 0
  2633.5     .17       0  4086.4     .15       0  4883.8     .09       0
  5027.9     .15       0  5667.1     .17       0
Bank Sta=4883.8,5027.9
XS Rating Curve= 0 ,0
Exp/Cntr=0.3,0.1

Type RM Length L Ch R = 1 ,61000   ,500,500,500
BEGIN DESCRIPTION:
CANEY CREEK NORTH 120.0
END DESCRIPTION:
XS GIS Cut Line= 3
      3756653.17     10191903.07       3756167.7      10189377.1
      3755601.16     10189141.18
#Sta/Elev= 30
  2427.8  272.92  2432.2  271.69    2531  271.02    2640   267.8    2858  255.72
  3013.8  251.39  3273.6  251.66  3366.7  248.22  3427.8  248.26  3631.4  243.71
  3855.2  242.37  4130.4  243.21  4288.6  236.84  4344.2  235.75  4384.9  237.96
  4670.1  237.39  4758.7  238.99  4822.8  237.28    4945  238.77  4965.4  237.52
  4971.6  235.17  4979.1  229.84  5011.7  229.84  5021.5  236.05  5033.2  238.83
  5057.1  237.87    5134  240.08  5181.7  239.26  5404.3  252.35  5613.7  267.09
#Mann= 5 ,-1 , 0
  2427.8     .17       0  4288.6     .15       0    4945     .09       0
  5033.2     .15       0  5404.3     .17       0
Bank Sta=4945,5033.2
XS Rating Curve= 0 ,0
Exp/Cntr=0.3,0.1

Type RM Length L Ch R = 1 ,60500   ,830,830,830
BEGIN DESCRIPTION:
CANEY CREEK NORTH 119.0
END DESCRIPTION:
XS GIS Cut Line= 4
      3756694.84     10191892.67       3756456.7     10190729.03
      3756527.16     10189208.12      3755982.82     10188686.09
#Sta/Elev= 30
  2289.7  272.63  2494.7   269.4  2760.9  255.45  2862.9  252.68  3118.1  252.65
  3220.2  248.14  3281.4  248.62  3443.2  244.04    4006   241.4  4206.2  242.58
    4284  237.46  4376.4   237.3  4406.4  235.01  4506.5  237.73  4586.6  236.02
  4806.8  238.37    4917  234.48    4977  239.18    4987  235.51  4995.4  229.36
    5028  229.36  5032.8  236.81    5040  237.62  5096.3  239.76  5117.7  237.94
  5195.4  239.06  5337.2  243.96  5478.4  251.05  5626.8  254.13  5754.2   263.6
#Mann= 5 ,-1 , 0
  2289.7     .17       0    4284     .15       0    4977     .09       0
  5096.3     .15       0  5337.2     .17       0
Bank Sta=4977,5096.3
XS Rating Curve= 0 ,0
Exp/Cntr=0.3,0.1

Type RM Length L Ch R = 1 ,59670   ,670,670,670
BEGIN DESCRIPTION:
CANEY CREEK NORTH 117.0
END DESCRIPTION:
XS GIS Cut Line= 3
      3758353.78     10190264.19      3757187.53     10189249.61
      3756036.11     10188532.44
#Sta/Elev= 30
  3454.2  266.25  3645.2  251.87    3893  240.44  4126.6  238.99  4176.9  240.41
  4318.4  237.69  4383.9  239.55  4523.4  237.95  4545.3  234.38  4601.9  237.72
  4778.9  237.28    4814  234.98  4821.6  236.67  4864.3  236.24  4899.5  233.11
  4956.4   236.8  4970.7  236.08  4977.3  233.24  4984.9  234.29  4989.4  229.09
  5022.9  229.09  5027.3  238.42  5237.4   237.9  5331.8   239.8  5551.3  236.76
  5647.8  239.49  5892.4   242.8  6117.8  249.66  6260.6  257.54  6356.5  265.88
#Mann= 5 ,-1 , 0
  3454.2     .17       0  4383.9     .15       0  4956.4     .09       0
  5027.3     .15       0  5647.8     .17       0
Bank Sta=4956.4,5027.3
XS Rating Curve= 0 ,0
Exp/Cntr=0.3,0.1

Type RM Length L Ch R = 1 ,59000   ,500,500,500
BEGIN DESCRIPTION:
CANEY CREEK NORTH 116.0
END DESCRIPTION:
XS GIS Cut Line= 3
       3758622.9     10189951.71      3757508.38       10189047.
      3756122.84     10188423.89
#Sta/Elev= 30
  3564.5  267.16  3604.2  261.79  3752.9  251.58  4030.9  240.09    4301  237.04
  4379.3  238.63  4519.6  237.63  4678.2  235.36    4962   238.5  4975.5  237.82
  4983.5  232.73  4989.9  235.38  4997.1  229.49  5004.2  230.44  5010.5  227.49
  5044.1  227.49  5050.5  235.31  5088.3  234.73  5096.8  236.26  5437.4  239.29
    5466  237.34    5541  238.66  5581.7  235.33  5664.6  238.81    5801  247.19
  5927.9  243.37  6064.2   242.2  6291.7  247.55  6389.8  252.94  6519.2  263.31
#Mann= 5 ,-1 , 0
  3564.5     .17       0  4519.6     .15       0    4962     .09       0
  5096.8     .15       0  5664.6     .17       0
Bank Sta=4962,5096.8
XS Rating Curve= 0 ,0
Exp/Cntr=0.3,0.1

Type RM Length L Ch R = 1 ,58500   ,802,802,802
BEGIN DESCRIPTION:
CANEY CREEK NORTH 115.0
END DESCRIPTION:
XS GIS Cut Line= 3
      3758874.62     10189699.95      3757800.94     10188793.58
      3756196.66     10188211.24
#Sta/Elev= 30
  3594.9  263.94  3890.3  248.47    4110   240.1  4230.9  236.84  4349.9  236.59
  4485.8  237.82  4663.8  236.68  4727.6  235.13  4734.2  233.16  4741.9  234.28
  4748.5  231.28  4762.8  231.46  4797.9     236  4890.2  234.56  4968.2  236.77
    4976   236.4  4983.2  227.72  5016.8  227.72  5020.6  233.43  5056.6  237.33
  5346.7  236.49    5482  238.99  5494.4  237.37  5708.1   238.8  5896.4  240.56
  6237.3  240.37  6400.8  244.29    6594  254.21  6660.4  261.06  6706.7  263.49
#Mann= 6 ,-1 , 0
  3594.9     .17       0  4349.9     .15       0  4968.2     .09       0
  5056.6     .15       0  5708.1     .17       0    6594     .11       0
Bank Sta=4968.2,5056.6
XS Rating Curve= 0 ,0
Exp/Cntr=0.3,0.1

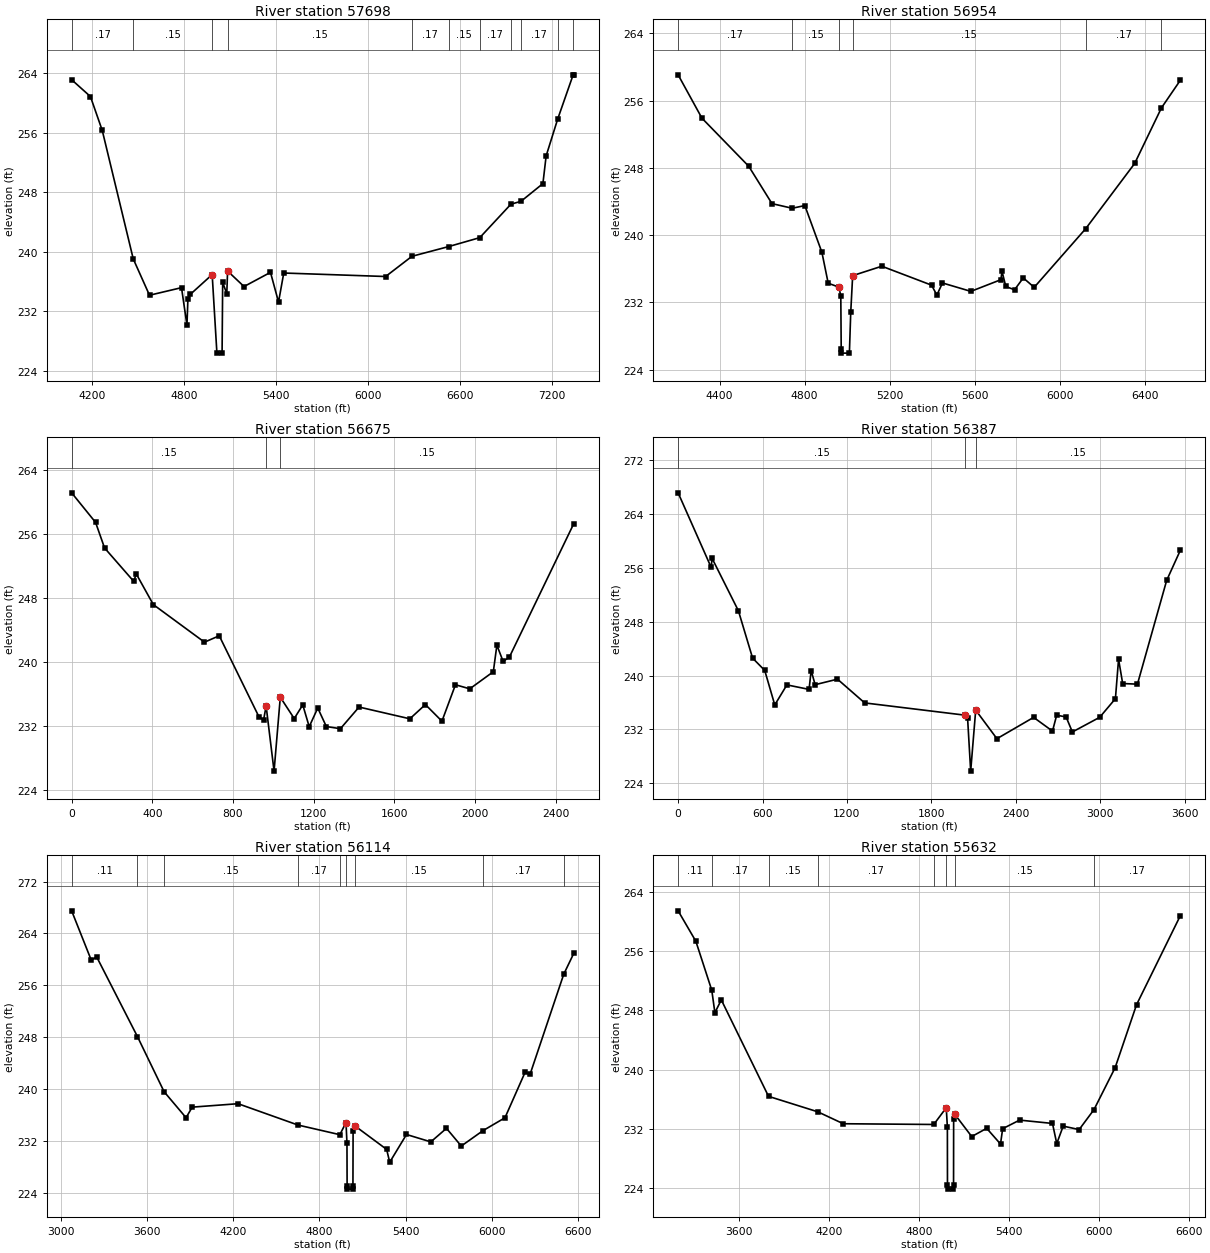
Type RM Length L Ch R = 1 ,57698   ,744,744,744
BEGIN DESCRIPTION:
CANEY CREEK NORTH 114.0
END DESCRIPTION:
XS GIS Cut Line= 3
      3759017.83     10189261.04      3758467.72     10188507.59
      3756214.04      10187872.7
#Sta/Elev= 30
  4067.1  263.14  4189.5  260.88  4266.7  256.31  4468.7  239.03  4574.7  234.14
  4783.4  235.16  4818.9  230.11  4825.1  233.61  4839.8  234.24  4983.3  236.92
  5014.2  226.35  5047.9  226.35  5051.8  235.87  5078.6  234.34  5083.8   237.4
    5191  235.31  5363.5  237.22    5416  233.22    5450  237.13  6114.3  236.66
  6285.9  239.38  6525.4  240.69  6728.2  241.89  6931.1  246.39  6996.9  246.78
  7139.7  249.16  7160.8  252.89  7235.5  257.81  7336.9   263.8  7341.4   263.8
#Mann= 11 ,-1 , 0
  4067.1     .17       0  4468.7     .15       0  4983.3     .09       0
  5083.8     .15       0  6285.9     .17       0  6525.4     .15       0
  6728.2     .17       0  6931.1     .11       0  6996.9     .17       0
  7235.5     .15       0  7336.9     .17       0
Bank Sta=4983.3,5083.8
XS Rating Curve= 0 ,0
Exp/Cntr=0.3,0.1

Type RM Length L Ch R = 1 ,56954   ,279,279,279
BEGIN DESCRIPTION:
CANEY CREEK NORTH 112.0
END DESCRIPTION:
XS GIS Cut Line= 3
      3759449.42     10189150.75      3759059.81     10188457.99
      3758699.45     10186932.07
#Sta/Elev= 30
  4205.2  259.06  4317.2  253.91  4537.5  248.19  4646.8  243.75  4741.9   243.2
  4801.4  243.52  4881.7  237.96  4911.3  234.29  4962.1  233.82  4970.6  232.72
  4972.5  226.48  4973.5  225.98    5011  225.98  5017.4  230.87  5026.4  235.19
  5163.6  236.31  5397.6  234.06  5422.6  232.88  5448.9  234.32  5582.5  233.32
  5723.8  234.71    5729   235.7  5746.9   233.9    5788  233.51  5829.1  234.92
  5880.5   233.8  6122.4  240.76  6353.1  248.52  6479.1  255.13  6567.9  258.41
#Mann= 6 ,-1 , 0
  4205.2     .17       0  4741.9     .15       0  4962.1     .09       0
  5026.4     .15       0  6122.4     .17       0  6479.1     .11       0
Bank Sta=4962.1,5026.4
XS Rating Curve= 0 ,0
Exp/Cntr=0.3,0.1

Type RM Length L Ch R = 1 ,56675   ,288,288,288
XS GIS Cut Line= 3
      3759751.36     10189247.67      3759317.17     10188356.49
      3758815.35     10186944.01
#Sta/Elev= 30
       0   261.2   118.6   257.5   163.1   254.3   307.7  250.12   320.3  251.05
   404.9  247.21   658.4  242.51   731.6  243.31   928.9  233.14   951.4  232.78
     964  234.51  1003.3  226.37  1034.2  235.62  1103.2  232.95  1145.6  234.66
  1177.5  231.93  1219.9  234.27  1262.4  231.95  1332.1  231.68  1424.6  234.39
  1676.3  232.92  1753.4   234.7  1835.4  232.62  1902.4  237.18  1973.4  236.67
  2090.1  238.81  2107.7  242.13  2138.6  240.11  2169.5  240.63  2489.2  257.36
#Mann= 3 , 0 , 0
       0     .15       0     964     .09       0  1034.2     .15       0
Bank Sta=964,1034.2
XS Rating Curve= 0 ,0
Exp/Cntr=0.3,0.1

Type RM Length L Ch R = 1 ,56387   ,274,274,274
XS GIS Cut Line= 3
       3761273.8     10189452.55      3759580.65     10188257.87
      3758909.98     10186918.57
#Sta/Elev= 30
       0  267.17   235.2  256.07   241.3  257.44   428.5  249.64   529.5   242.6
   615.7  240.77   687.1  235.64   773.3  238.62   930.9  237.95   945.7  240.75
   974.1  238.65  1132.9  239.47  1326.2  235.94  2042.8  234.11  2057.6  233.75
  2079.8   225.8  2115.5  234.87  2266.3  230.62  2527.2  233.79  2661.4  231.75
    2691  234.11    2758  233.86  2802.7  231.62  2996.9   233.8  3108.7  236.57
  3131.1  242.44  3160.3  238.82  3265.3  238.73  3473.2  254.16    3570  258.62
#Mann= 3 , 0 , 0
       0     .15       0  2042.8     .09       0  2115.5     .15       0
Bank Sta=2042.8,2115.5
XS Rating Curve= 0 ,0
Exp/Cntr=0.3,0.1

Type RM Length L Ch R = 1 ,56114   ,482,482,482
BEGIN DESCRIPTION:
CANEY CREEK NORTH 110.0
END DESCRIPTION:
XS GIS Cut Line= 3
      3761299.44     10189433.27      3759838.25     10188178.99
      3759033.81     10186829.11
#Sta/Elev= 30
  3074.3  267.48  3211.5  259.83  3247.7  260.41  3532.6  248.07  3718.1  239.57
    3871  235.56  3913.8  237.19  4233.2  237.72  4650.2  234.43    4942  232.94
  4984.9  234.82  4991.5   231.6  4992.5  225.04  4993.5  224.54  5032.1  224.54
  5033.1  225.04  5034.2   233.5  5049.8  234.25  5267.8  230.67  5289.2  228.69
    5406  232.97  5575.4  231.83  5684.4  233.92  5787.6  231.19  5938.4  233.56
  6091.8  235.55  6231.5  242.55  6266.5  242.25  6501.1   257.7  6571.4  260.94
#Mann= 9 ,-1 , 0
  3074.3     .11       0  3532.6     .17       0  3718.1     .15       0
  4650.2     .17       0    4942     .15       0  4984.9     .09       0
  5049.8     .15       0  5938.4     .17       0  6501.1     .11       0
Bank Sta=4984.9,5049.8
XS Rating Curve= 0 ,0
Exp/Cntr=0.3,0.1

Type RM Length L Ch R = 1 ,55632   ,632,632,632
BEGIN DESCRIPTION:
CANEY CREEK NORTH 109.0
END DESCRIPTION:
XS GIS Cut Line= 3
      3761424.39     10189261.34      3760220.83     10187914.29
      3759216.06     10186740.51
#Sta/Elev= 30
  3193.6  261.45    3312  257.34  3418.3  250.72    3439  247.69  3481.7  249.43
    3797   236.4  4125.8  234.31  4295.9   232.7  4899.6   232.6  4983.1  234.86
  4990.6  232.24  4991.2  224.37  4992.2  223.87  5030.8  223.87  5031.8  224.37
  5032.4  233.32  5040.1  233.97  5153.1  230.97    5253  232.08  5345.2  229.96
  5359.5  232.03  5472.6  233.19  5692.1  232.74  5720.6  230.02  5763.5  232.38
  5869.9  231.91  5969.4  234.62  6110.3  240.28    6253  248.77  6545.1  260.79
#Mann= 8 ,-1 , 0
  3193.6     .11       0  3418.3     .17       0    3797     .15       0
  4125.8     .17       0  4899.6     .15       0  4983.1     .09       0
  5040.1     .15       0  5969.4     .17       0
Bank Sta=4983.1,5040.1
XS Rating Curve= 0 ,0
Exp/Cntr=0.3,0.1

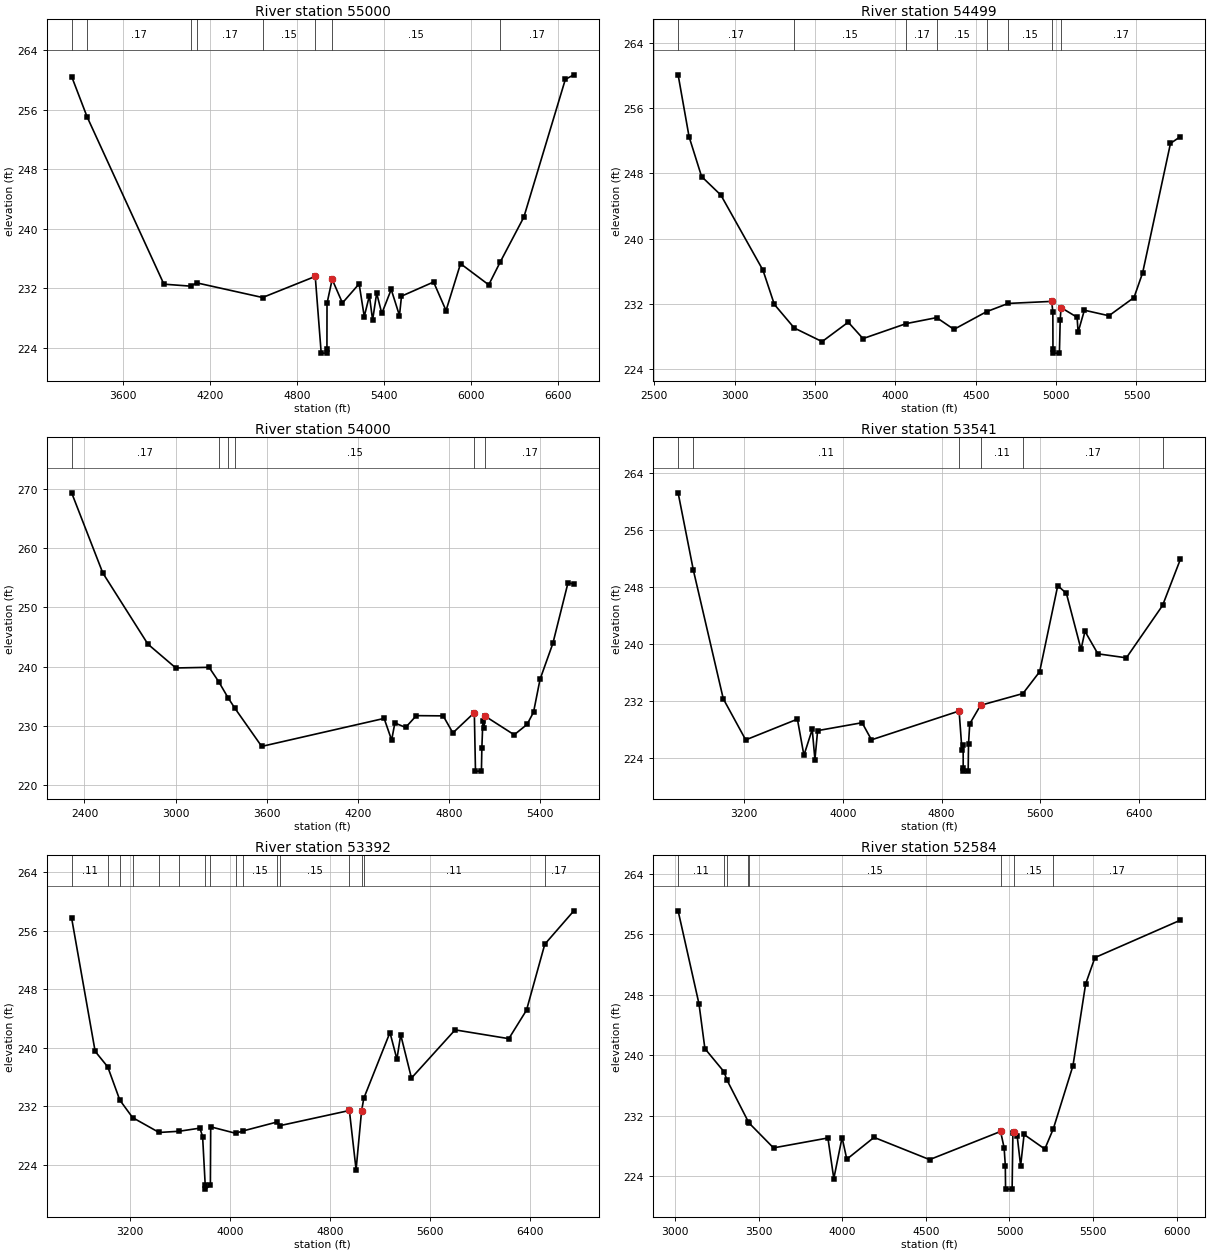
Type RM Length L Ch R = 1 ,55000   ,501,501,501
BEGIN DESCRIPTION:
CANEY CREEK NORTH 108.0
END DESCRIPTION:
XS GIS Cut Line= 3
      3761497.34     10189224.92      3760678.24     10187670.52
      3759294.18     10186662.39
#Sta/Elev= 30
    3243  260.43    3350  255.01  3880.3  232.58    4067  232.31  4105.8  232.76
  4562.1  230.79  4925.8  233.62    4967  223.33  5005.6  223.33  5006.6  223.83
  5007.1     230  5042.7  233.22  5113.7  230.06  5228.9  232.62  5264.4  228.24
  5299.9  231.03  5322.1  227.77  5350.2  231.37  5385.7  228.65  5450.6  231.87
  5507.7  228.37  5521.7  230.97  5743.4  232.87  5829.4  229.04  5929.6  235.33
  6124.3  232.49  6203.7  235.55  6366.9  241.57  6653.6  260.05  6712.3  260.66
#Mann= 8 ,-1 , 0
    3243     .11       0    3350     .17       0    4067     .15       0
  4105.8     .17       0  4562.1     .15       0  4925.8     .09       0
  5042.7     .15       0  6203.7     .17       0
Bank Sta=4925.8,5042.7
XS Rating Curve= 0 ,0
Exp/Cntr=0.3,0.1

Type RM Length L Ch R = 1 ,54499   ,499,499,499
BEGIN DESCRIPTION:
CANEY CREEK NORTH 107.0
END DESCRIPTION:
XS GIS Cut Line= 3
      3762476.46     10188948.83      3760807.02      10187272.5
      3760596.79     10186544.36
#Sta/Elev= 30
  2648.8  260.09  2716.9  252.51  2794.7  247.63  2914.9  245.35  3176.6  236.15
  3247.3  231.96  3371.2  229.07  3544.3   227.4  3706.9  229.78  3798.8  227.77
  4067.9  229.61  4256.9  230.34  4364.5   228.9  4567.5  231.07  4702.1  232.08
  4972.6  232.33  4979.7  231.01  4980.4  226.49  4981.4  225.99  5020.5  225.99
  5025.5  230.11  5030.7  231.57  5130.6  230.38  5136.8  228.54  5175.7  231.25
  5328.4  230.57  5484.5   232.8    5538  235.82  5711.4  251.69  5772.5  252.51
#Mann= 8 ,-1 , 0
  2648.8     .17       0  3371.2     .15       0  4067.9     .17       0
  4256.9     .15       0  4567.5     .17       0  4702.1     .15       0
  4972.6     .09       0  5030.7     .17       0
Bank Sta=4972.6,5030.7
XS Rating Curve= 0 ,0
Exp/Cntr=0.3,0.1

Type RM Length L Ch R = 1 ,54000   ,459,459,459
BEGIN DESCRIPTION:
CANEY CREEK NORTH 106.0
END DESCRIPTION:
XS GIS Cut Line= 3
      3763017.83     10188811.05      3761104.98     10186927.69
      3760632.83     10186521.85
#Sta/Elev= 30
  2315.6  269.32  2520.6  255.81  2817.7   243.8  3001.5  239.78  3220.7  239.89
  3283.7  237.48    3345  234.78  3389.3  233.03  3567.1  226.55  4373.3  231.27
  4422.8  227.61    4444   230.5  4514.8  229.75  4585.5  231.74  4762.2   231.7
  4825.9  228.83  4967.3  232.24  4974.9  222.38    5014  222.38  5016.9  226.28
  5023.5  230.85  5031.2  229.67  5037.8  231.66  5229.8  228.51  5314.3  230.25
  5357.1  232.31  5399.9  237.85  5484.4  243.92  5584.2  254.15  5622.6  253.93
#Mann= 6 ,-1 , 0
  2315.6     .17       0  3283.7     .15       0    3345     .17       0
  3389.3     .15       0  4967.3     .09       0  5037.8     .17       0
Bank Sta=4967.3,5037.8
XS Rating Curve= 0 ,0
Exp/Cntr=0.3,0.1

Type RM Length L Ch R = 1 ,53541   ,149,149,149
BEGIN DESCRIPTION:
CANEY CREEK NORTH 105.0
END DESCRIPTION:
XS GIS Cut Line= 3
      3763553.07      10187536.2      3761414.57     10186600.13
      3759761.02     10186079.39
#Sta/Elev= 30
  2665.6  261.19  2789.1  250.34  3031.5   232.3  3213.1  226.54  3631.9  229.45
  3684.7  224.38    3752  228.01  3773.8  223.78  3795.6  227.84  4155.9  228.95
  4231.9  226.55  4941.8  230.59  4964.7  225.16  4974.6  225.77  4974.9  222.66
  4975.9  222.16  5015.1  222.16  5018.1  226.02    5028   228.8  5115.3  231.39
  5458.6  233.04  5594.2   236.1  5740.8  248.17  5810.8  247.09  5929.6  239.23
  5961.1  241.78  6065.9  238.61  6296.6  238.05  6589.8  245.39  6733.6  251.84
#Mann= 6 ,-1 , 0
  2665.6     .17       0  2789.1     .11       0  4941.8     .06       0
  5115.3     .11       0  5458.6     .17       0  6589.8     .11       0
Bank Sta=4941.8,5115.3
XS Rating Curve= 0 ,0
Exp/Cntr=0.3,0.1

Type RM Length L Ch R = 1 ,53392   ,808,808,808
BEGIN DESCRIPTION:
CANEY CREEK NORTH 104.0
END DESCRIPTION:
XS GIS Cut Line= 4
      3763526.75      10187447.7      3763255.93     10187178.62
      3761503.78     10186481.78      3759865.23     10185875.84
#Sta/Elev= 30
  2732.6   257.7  2920.4  239.52  3021.3  237.39  3117.6  232.86  3219.8  230.47
  3431.4  228.44  3590.2   228.6    3758  229.03  3779.5  227.86  3800.4   221.2
  3801.4   220.7  3841.6   221.2  3844.1  229.21  4042.5  228.33  4103.1  228.65
    4373  229.86  4397.6  229.37  4952.6  231.44  5006.3  223.36  5049.8  231.32
  5067.8   233.1  5277.1  242.09  5332.6  238.45    5363  241.78  5448.9  235.87
  5797.8  242.45  6227.2  241.25  6368.6  245.14  6514.8  254.15    6747  258.71
#Mann= 16 ,-1 , 0
  2732.6     .11       0  3021.3     .15       0  3117.6     .11       0
  3219.8     .15       0  3431.4     .11       0  3590.2     .15       0
  3800.4     .12       0  3841.6     .15       0  4042.5     .11       0
  4103.1     .15       0    4373     .11       0  4397.6     .15       0
  4952.6     .09       0  5049.8     .17       0  5067.8     .11       0
  6514.8     .17       0
Bank Sta=4952.6,5049.8
XS Rating Curve= 0 ,0
Exp/Cntr=0.3,0.1

Type RM Length L Ch R = 1 ,52584   ,577,577,577
BEGIN DESCRIPTION:
CANEY CREEK NORTH 103.0
END DESCRIPTION:
XS GIS Cut Line= 3
      3763558.02     10187437.31      3762142.25     10186051.26
        3761154.     10185793.56
#Sta/Elev= 30
  3018.7  259.11  3143.5  246.81  3178.8   240.9  3293.1  237.84  3310.5  236.76
  3438.7  231.22  3443.6  231.05    3589  227.78  3914.3  229.09  3949.6  223.72
    3999  229.15  4027.3  226.28  4190.1  229.17  4522.4  226.23  4946.7  229.95
  4967.9   227.8    4975  225.44  4976.5  222.33  5015.7  222.33  5020.3   229.7
  5025.5  229.82  5045.9  229.37  5066.6   225.4  5087.2  229.55  5211.2  227.63
  5262.3  230.32  5379.5  238.64  5455.3  249.45  5510.9  252.93  6021.3  257.87
#Mann= 8 ,-1 , 0
  3018.7     .11       0  3293.1     .17       0  3310.5     .15       0
  3438.7     .17       0  3443.6     .15       0  4946.7     .09       0
  5025.5     .15       0  5262.3     .17       0
Bank Sta=4946.7,5025.5
XS Rating Curve= 0 ,0
Exp/Cntr=0.3,0.1

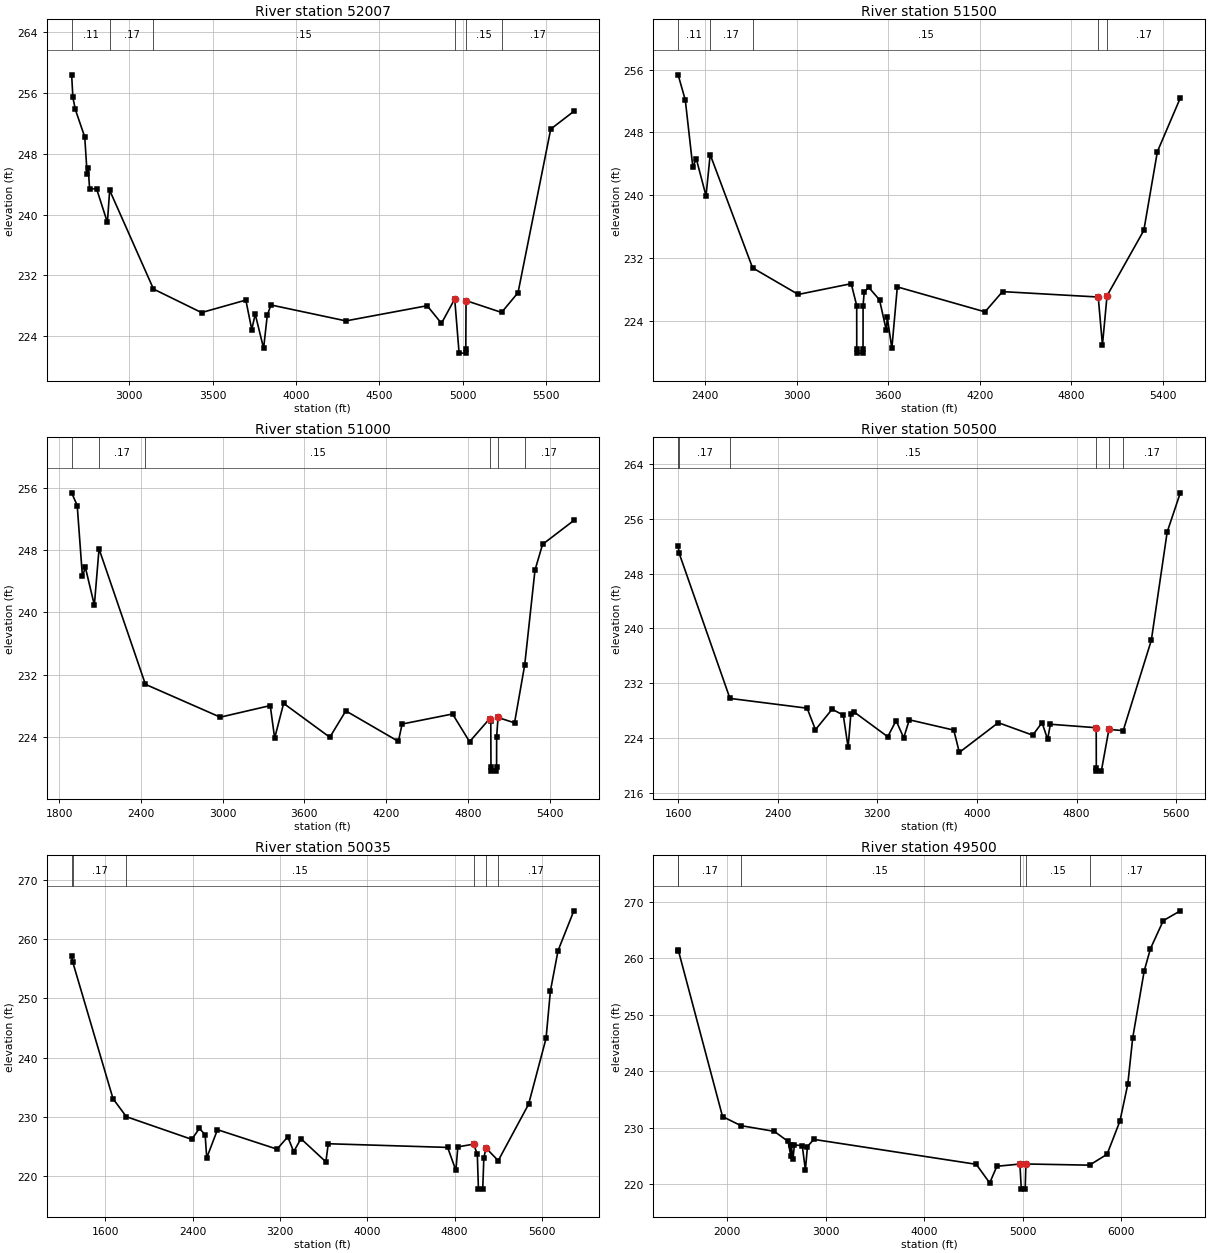
Type RM Length L Ch R = 1 ,52007   ,507,507,507
BEGIN DESCRIPTION:
CANEY CREEK NORTH 102.0
END DESCRIPTION:
XS GIS Cut Line= 3
      3763568.41     10187430.33      3762187.96     10185532.98
      3761524.84     10185461.17
#Sta/Elev= 30
  2653.6  258.33    2661  255.36  2675.6  253.79  2732.1  250.18  2746.7  245.27
  2752.9  246.05  2761.4  243.36  2803.2  243.38  2868.1  238.96  2881.7  243.18
  3144.7  230.22    3433  227.13  3698.8  228.77  3734.3  224.91  3755.2  226.92
  3805.4  222.44  3827.5  226.78  3849.5  228.13  4299.2  226.04  4786.8  228.03
  4872.6  225.72  4952.2  228.91  4978.5  221.81  5017.7  221.81  5018.7  222.31
  5020.2   228.7  5233.4  227.15    5332  229.74  5528.4  251.21    5667  253.54
#Mann= 6 ,-1 , 0
  2653.6     .11       0  2881.7     .17       0  3144.7     .15       0
  4952.2     .09       0  5020.2     .15       0  5233.4     .17       0
Bank Sta=4952.2,5020.2
XS Rating Curve= 0 ,0
Exp/Cntr=0.3,0.1

Type RM Length L Ch R = 1 ,51500   ,500,500,500
BEGIN DESCRIPTION:
CANEY CREEK NORTH 101.0
END DESCRIPTION:
XS GIS Cut Line= 3
      3763584.04     10187419.91      3762022.72     10185123.27
       3761507.6     10185109.64
#Sta/Elev= 30
  2222.9  255.34  2269.9  252.13  2319.1  243.63  2342.4   244.6  2405.9  239.91
  2433.1  245.18    2711  230.74  3010.6  227.35  3357.7  228.72  3393.7  225.93
    3394  220.37    3395  219.87  3434.2  219.87  3435.2  220.37  3435.6  225.94
  3442.8  227.62  3471.6  228.28  3543.4  226.65  3587.9  222.77  3594.3  224.44
  3624.1  220.47  3660.1  228.31  4234.9  225.13  4349.7  227.71  4977.2  227.02
  5004.9  220.91  5034.9  227.18  5276.1  235.51    5365  245.55  5515.3  252.39
#Mann= 5 ,-1 , 0
  2222.9     .11       0  2433.1     .17       0    2711     .15       0
  4977.2     .09       0  5034.9     .17       0
Bank Sta=4977.2,5034.9
XS Rating Curve= 0 ,0
Exp/Cntr=0.3,0.1

Type RM Length L Ch R = 1 ,51000   ,500,500,500
BEGIN DESCRIPTION:
CANEY CREEK NORTH 100.0
END DESCRIPTION:
XS GIS Cut Line= 3
      3763601.41      10187423.4      3762129.19     10184686.21
      3761563.13     10184804.09
#Sta/Elev= 30
    1892  255.35  1932.8  253.72  1970.9  244.64  1992.8  245.76  2058.6  240.93
    2093  248.15  2433.4  230.75  2982.9  226.53  3349.7  228.02  3382.1  223.84
  3447.9   228.3  3787.1  223.95  3904.4  227.34  4290.2  223.42  4317.8  225.65
  4687.9  226.94  4812.8  223.38  4960.4  226.34  4968.6  225.98  4969.9   220.1
  4970.9   219.6  5010.1   219.6  5011.1   220.1  5011.6  224.01  5021.8  226.49
  5142.9   225.8  5217.6  233.25  5293.1  245.43  5348.7  248.73  5578.2   251.8
#Mann= 6 ,-1 , 0
    1892     .11       0    2093     .17       0  2433.4     .15       0
  4960.4     .09       0  5021.8     .15       0  5217.6     .17       0
Bank Sta=4960.4,5021.8
XS Rating Curve= 0 ,0
Exp/Cntr=0.3,0.1

Type RM Length L Ch R = 1 ,50500   ,465,465,465
BEGIN DESCRIPTION:
CANEY CREEK NORTH 99.0
END DESCRIPTION:
XS GIS Cut Line= 4
       3763556.5     10187254.57      3762048.34     10184255.36
      3762007.08      10184245.4      3761375.65     10184210.34
#Sta/Elev= 30
  1600.5  252.06  1609.4  250.98  2016.6  229.77  2636.2  228.34  2703.1  225.19
  2837.1  228.19  2926.4  227.32  2965.4  222.61  2987.7  227.56  3010.1  227.83
  3283.5  224.16  3350.5  226.52  3411.9     224  3456.5  226.64  3813.7  225.13
  3858.3  221.87  4170.8  226.22  4447.5  224.39  4522.4  226.22  4567.1  223.79
  4589.4  225.99  4957.2  225.48    4958  219.63    4959  219.13  4998.3  219.13
  5059.3  225.23    5174  225.06  5399.8  238.28    5527  254.12  5632.4  259.85
#Mann= 6 ,-1 , 0
  1600.5     .11       0  1609.4     .17       0  2016.6     .15       0
  4957.2     .09       0  5059.3     .15       0    5174     .17       0
Bank Sta=4957.2,5059.3
XS Rating Curve= 0 ,0
Exp/Cntr=0.3,0.1

Type RM Length L Ch R = 1 ,50035   ,535,535,535
BEGIN DESCRIPTION:
CANEY CREEK NORTH 98.0
END DESCRIPTION:
XS GIS Cut Line= 3
       3763604.2     10187255.18      3762115.69     10183856.98
      3761223.11     10183859.64
#Sta/Elev= 30
  1289.8  257.11  1298.8   256.2    1669   233.1  1791.1  230.07  2390.6  226.25
  2460.8   228.1    2513  227.02  2527.9  223.13  2626.2  227.88  3172.1   224.6
  3270.3  226.67  3324.9  224.18  3391.3  226.36  3619.7  222.46  3641.5  225.51
  4735.7  224.89  4811.3  221.01  4829.2  224.98  4973.4  225.44  5007.6  223.76
  5017.9  217.86  5057.2  217.86  5067.6  223.17  5087.6  224.78  5199.3  222.66
  5477.6  232.17  5637.6  243.27  5677.6  251.27  5747.6  258.06  5892.3  264.77
#Mann= 6 ,-1 , 0
  1289.8     .11       0  1298.8     .17       0  1791.1     .15       0
  4973.4     .09       0  5087.6     .15       0  5199.3     .17       0
Bank Sta=4973.4,5087.6
XS Rating Curve= 0 ,0
Exp/Cntr=0.3,0.1

Type RM Length L Ch R = 1 ,49500   ,500,500,500
BEGIN DESCRIPTION:
CANEY CREEK NORTH 97.0
END DESCRIPTION:
XS GIS Cut Line= 4
      3763659.11     10187250.02      3762572.92     10183922.62
      3762382.58      10183790.2      3761015.14     10183716.41
#Sta/Elev= 30
  1499.8  261.42  1502.6   261.4    1951  231.97  2136.6  230.36    2477  229.34
  2617.3  227.55  2643.9  225.04  2649.2  226.94  2666.3  224.39  2681.1  226.94
    2761   226.8  2792.6  222.49  2813.9  226.65  2877.7  227.92  4528.3   223.5
    4665   220.2  4737.9  223.15  4971.7  223.55  4986.1   219.1  5025.4   219.1
  5032.8  223.56  5678.9  223.35  5857.5  225.28  5987.7  231.15  6067.8   237.7
  6117.9  245.94  6234.7   257.8  6298.2  261.74  6428.3   266.7  6601.3  268.44
#Mann= 6 ,-1 , 0
  1499.8     .11       0  1502.6     .17       0  2136.6     .15       0
  4971.7     .09       0  5032.8     .15       0  5678.9     .17       0
Bank Sta=4971.7,5032.8
XS Rating Curve= 0 ,0
Exp/Cntr=0.3,0.1