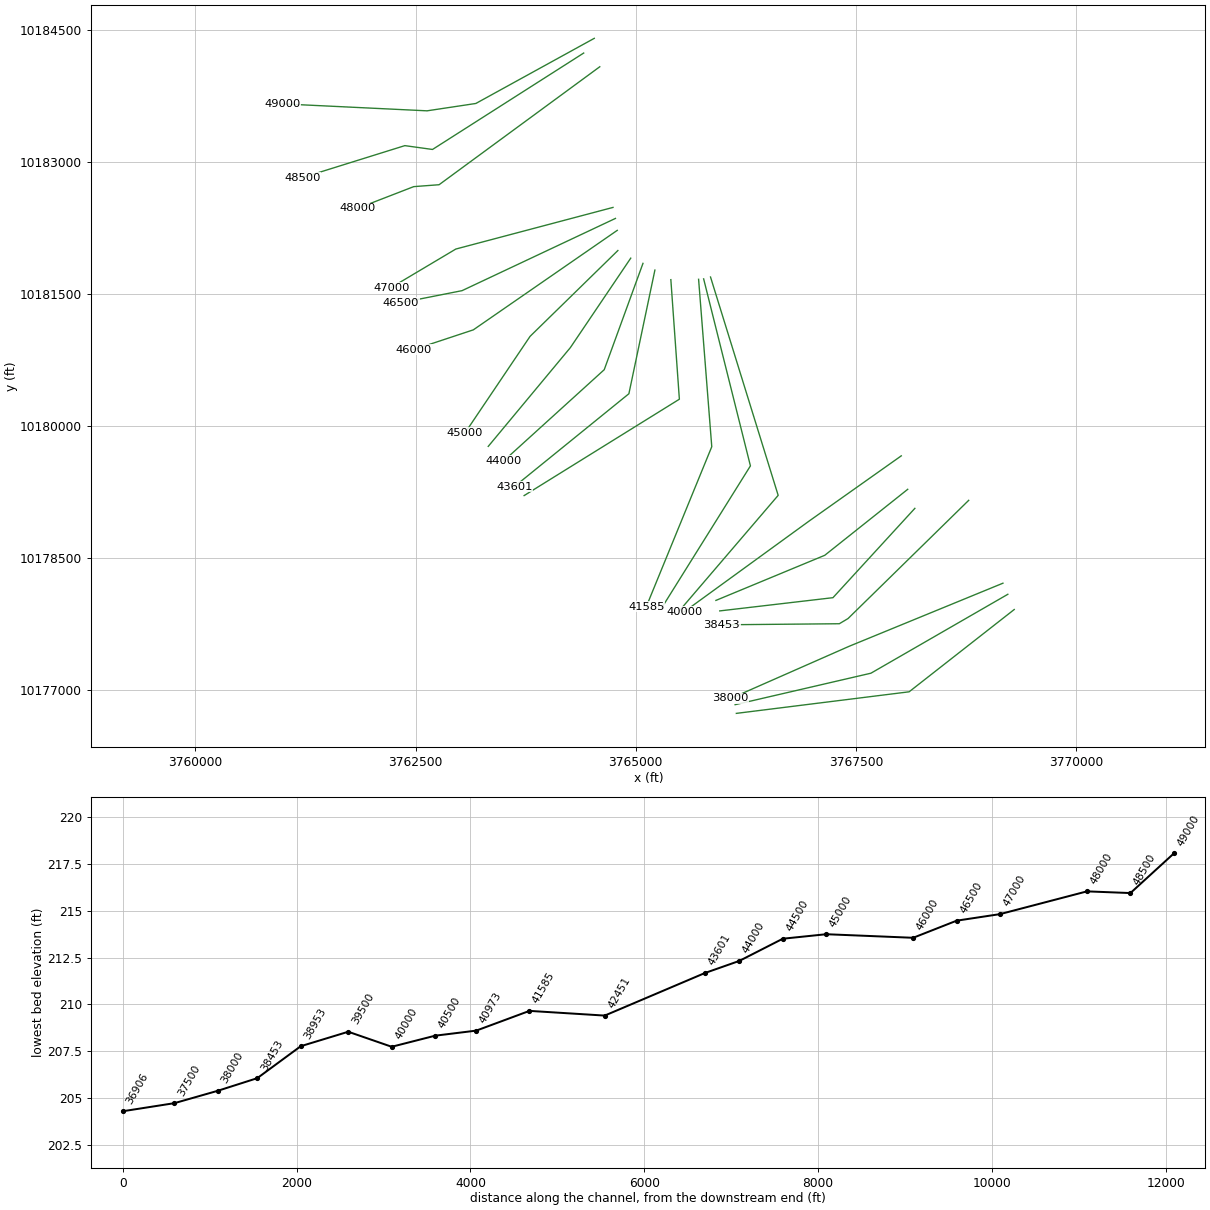
HEC-RAS study CANEY CREEK NORTH.prj: CANEY CREEK NORTH Base Level Engineering

--- CANEY CREEK NORTH.g01 (geometry) --- (continued)

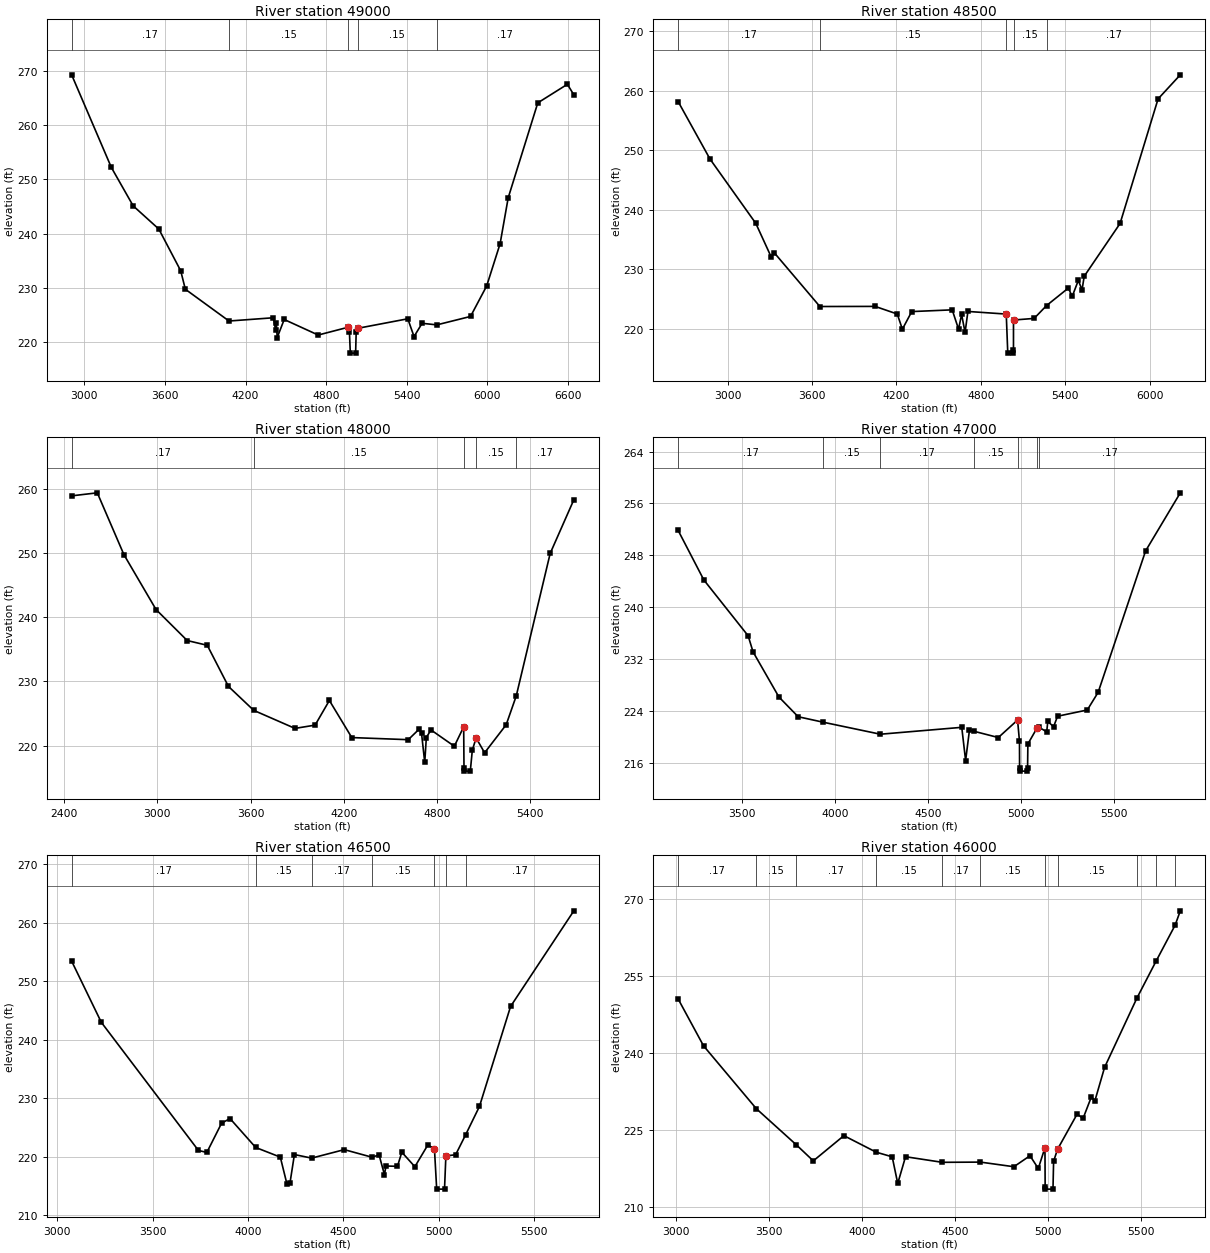
Type RM Length L Ch R = 1 ,49000   ,500,500,500
BEGIN DESCRIPTION:
CANEY CREEK NORTH 96.0
END DESCRIPTION:
XS GIS Cut Line= 4
      3764529.12     10184399.99      3763184.82     10183660.13
      3762630.73     10183576.57      3760989.83     10183655.56
#Sta/Elev= 30
  2905.2  269.26  3200.7  252.21  3363.2  245.14  3553.9  240.88  3716.8   233.2
  3751.3   229.8  4076.3  223.95  4407.1  224.55  4423.2  222.26  4428.9  223.51
  4435.1  220.91  4487.1  224.23  4740.1  221.37  4962.5   222.8  4972.6  221.92
  4979.2  218.04  5018.6  218.04  5022.9   221.9  5032.9   222.6    5407  224.36
  5453.4  221.09  5513.5  223.53    5623  223.24  5873.9  224.79    5994   230.4
  6094.1  238.19  6154.2  246.62  6374.5   264.1  6594.7  267.52  6642.8  265.58
#Mann= 5 ,-1 , 0
  2905.2     .17       0  4076.3     .15       0  4962.5     .09       0
  5032.9     .15       0    5623     .17       0
Bank Sta=4962.5,5032.9
XS Rating Curve= 0 ,0
Exp/Cntr=0.3,0.1

Type RM Length L Ch R = 1 ,48500   ,500,500,500
BEGIN DESCRIPTION:
CANEY CREEK NORTH 95.0
END DESCRIPTION:
XS GIS Cut Line= 4
       3764409.1       10184233.      3762692.88     10183137.71
      3762378.72     10183181.23      3761215.45     10182817.87
#Sta/Elev= 30
  2646.9  258.19  2873.8  248.53  3199.4  237.73  3308.6   232.1  3329.7  232.82
  3655.2  223.76  4048.1  223.78  4205.5   222.5  4241.9  219.95  4308.7  222.91
  4596.4   223.2  4641.4  219.96  4663.2  222.42  4687.9  219.41  4708.1  222.93
  4980.7  222.49  4991.6  215.93  5031.1  215.93  5032.1  216.43  5032.3  221.49
    5179  221.76  5267.4  223.92  5422.5  226.86  5449.7  225.45  5493.3  228.14
  5519.9  226.56  5535.2  228.84  5790.3  237.71  6060.7  258.64  6218.7  262.68
#Mann= 5 ,-1 , 0
  2646.9     .17       0  3655.2     .15       0  4980.7     .09       0
  5032.3     .15       0  5267.4     .17       0
Bank Sta=4980.7,5032.3
XS Rating Curve= 0 ,0
Exp/Cntr=0.3,0.1

Type RM Length L Ch R = 1 ,48000   ,1000,1000,1000
BEGIN DESCRIPTION:
CANEY CREEK NORTH 94.0
END DESCRIPTION:
XS GIS Cut Line= 4
      3764591.44     10184077.13      3762767.51     10182737.22
      3762479.64     10182715.49      3761844.85     10182469.46
#Sta/Elev= 30
  2448.1  258.92  2613.2  259.39  2784.5  249.76  2991.4   241.2    3192  236.37
  3321.1  235.63  3457.4  229.22  3620.2  225.49  3885.7  222.68  4015.3  223.19
  4107.1  227.03  4251.4  221.25  4614.9  220.92  4686.1  222.59  4700.5  221.89
    4721  217.37  4731.3  221.26  4761.1  222.44  4911.5   219.9  4971.7  222.92
  4973.7  216.52  4974.7  216.02  5014.3  216.02  5027.4  219.31  5051.9  221.18
  5106.4  218.88  5245.3  223.25  5310.1  227.74  5528.5  249.95  5680.8  258.31
#Mann= 5 ,-1 , 0
  2448.1     .17       0  3620.2     .15       0  4971.7     .09       0
  5051.9     .15       0  5310.1     .17       0
Bank Sta=4971.7,5051.9
XS Rating Curve= 0 ,0
Exp/Cntr=0.3,0.1

Type RM Length L Ch R = 1 ,47000   ,500,500,500
BEGIN DESCRIPTION:
CANEY CREEK NORTH 92.0
END DESCRIPTION:
XS GIS Cut Line= 3
      3764741.57      10182479.4      3762957.94     10182006.74
      3762224.15     10181569.65
#Sta/Elev= 30
  3154.8  251.86  3293.1  244.23  3531.1  235.64  3557.6  233.16  3696.6  226.22
  3800.1  223.18  3935.8  222.33    4242  220.49  4679.4  221.55  4700.1  216.44
  4720.8  221.12  4745.4  220.94  4875.9  219.98  4979.4  222.67  4989.7  219.37
  4990.2  215.31  4991.2  214.81  5032.2  214.81  5033.2  215.31  5034.8  218.99
  5083.4  221.42  5096.1  221.54    5136  220.85  5141.8  222.45    5173  221.65
  5194.4  223.26  5354.1  224.22  5412.5  226.94  5667.5   248.7  5854.1  257.64
#Mann= 7 ,-1 , 0
  3154.8     .17       0  3935.8     .15       0    4242     .17       0
  4745.4     .15       0  4979.4     .09       0  5083.4     .15       0
  5096.1     .17       0
Bank Sta=4979.4,5083.4
XS Rating Curve= 0 ,0
Exp/Cntr=0.3,0.1

Type RM Length L Ch R = 1 ,46500   ,500,500,500
BEGIN DESCRIPTION:
CANEY CREEK NORTH 91.0
END DESCRIPTION:
XS GIS Cut Line= 3
      3764769.28     10182354.38      3763028.22     10181533.91
      3762332.32     10181396.16
#Sta/Elev= 30
  3075.3  253.42  3230.8  242.97  3740.2  221.07  3784.4  220.73  3861.8  225.73
    3906  226.52  4040.6  221.58  4169.8  219.93  4204.5  215.34  4220.9  215.59
  4243.7  220.37  4333.9  219.76  4505.4  221.21    4651  219.91  4687.7  220.32
    4716  216.93    4724  218.41  4784.3  218.36  4807.1  220.77  4875.5  218.29
  4943.8  222.02  4978.3  221.32    4990  214.46  5031.1  214.46  5038.2  220.13
  5089.4  220.34  5142.2  223.77  5214.4   228.6  5377.6  245.68  5709.4  262.02
#Mann= 7 ,-1 , 0
  3075.3     .17       0  4040.6     .15       0  4333.9     .17       0
    4651     .15       0  4978.3     .09       0  5038.2     .15       0
  5142.2     .17       0
Bank Sta=4978.3,5038.2
XS Rating Curve= 0 ,0
Exp/Cntr=0.3,0.1

Type RM Length L Ch R = 1 ,46000   ,1000,1000,1000
BEGIN DESCRIPTION:
CANEY CREEK NORTH 90.0
END DESCRIPTION:
XS GIS Cut Line= 3
      3764790.15     10182218.98      3763156.28     10181088.74
        3762482.      10180865.1
#Sta/Elev= 30
  3013.3  250.58  3149.8  241.45  3433.1  229.22  3647.7  222.19  3739.3  219.05
  3903.7  223.96  4077.2  220.74  4163.1  219.84  4192.8  214.65  4234.7  219.86
  4431.7  218.77  4637.1  218.81  4816.6  217.91  4903.1  220.05  4947.7  217.57
  4983.5  221.62  4984.5  214.05  4985.5  213.55  5026.6  213.55  5029.9  218.97
    5051   221.3  5156.4  228.17    5188   227.3  5233.1  231.54  5251.2  230.69
  5303.9  237.27  5477.2  250.73  5579.9  257.91  5682.6  264.94  5710.4  267.73
#Mann= 11 ,-1 , 0
  3013.3     .17       0  3433.1     .15       0  3647.7     .17       0
  4077.2     .15       0  4431.7     .17       0  4637.1     .15       0
  4983.5     .09       0    5051     .15       0  5477.2     .17       0
  5579.9     .11       0  5682.6     .17       0
Bank Sta=4983.5,5051
XS Rating Curve= 0 ,0
Exp/Cntr=0.3,0.1

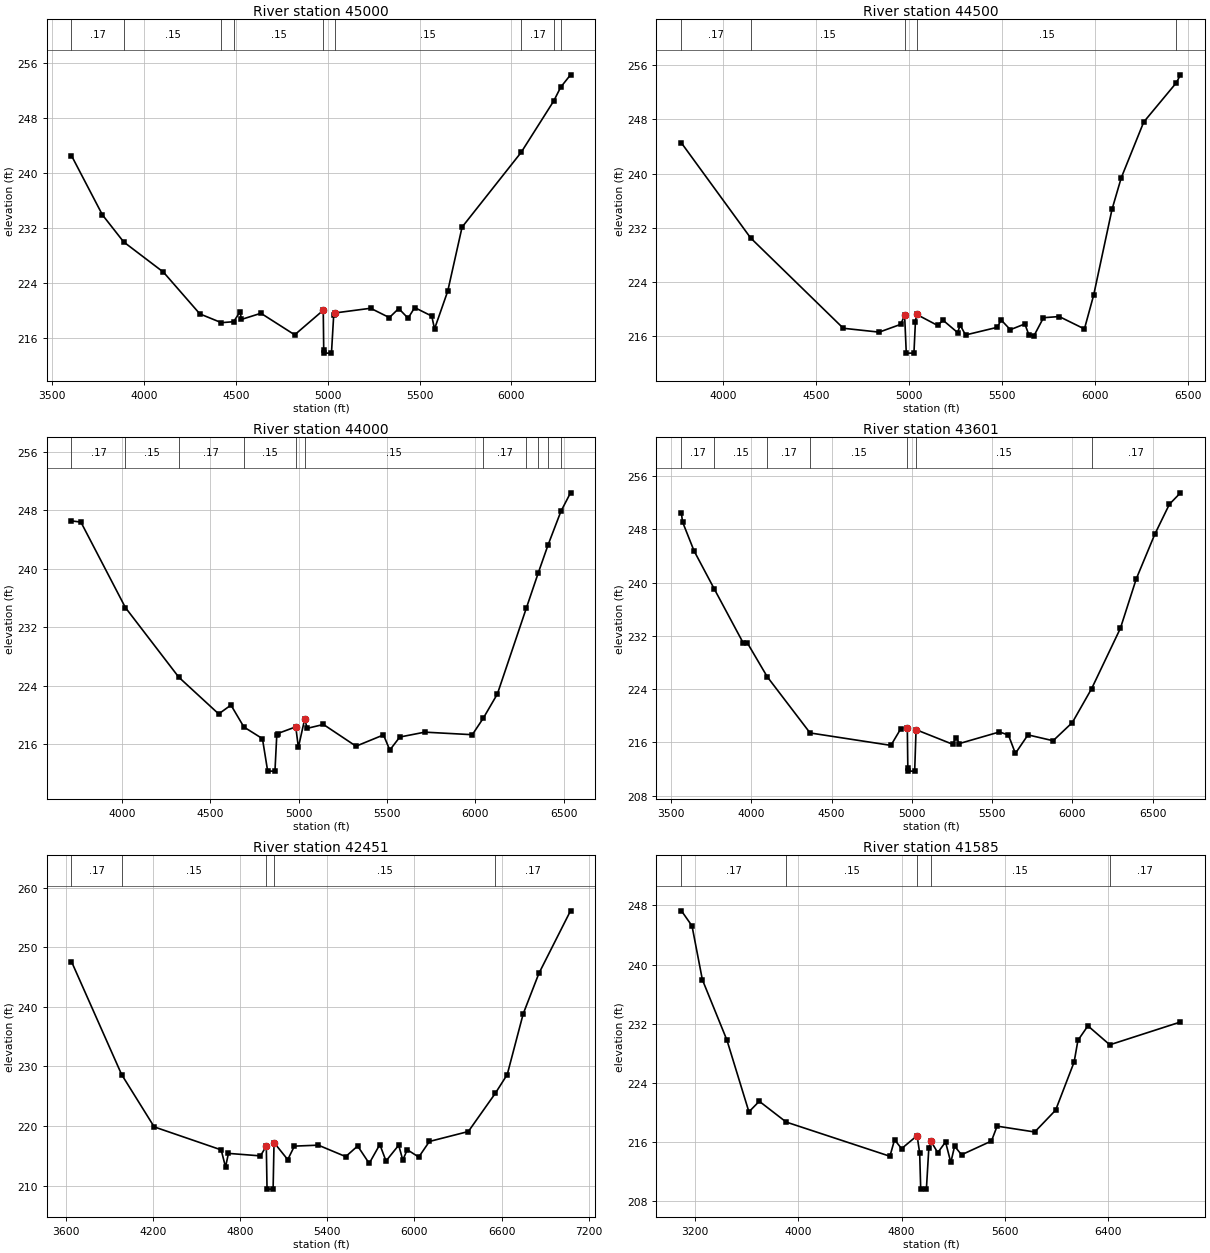
Type RM Length L Ch R = 1 ,45000   ,500,500,500
BEGIN DESCRIPTION:
CANEY CREEK NORTH 88.0
END DESCRIPTION:
XS GIS Cut Line= 3
       3764797.1     10181989.82      3763800.21     10181014.71
      3763061.93      10179918.3
#Sta/Elev= 30
  3605.5  242.53  3773.7   233.9  3889.5  229.95  4106.2  225.54  4304.1  219.46
  4421.3  218.18  4487.9  218.32  4523.4  219.77  4530.4  218.65  4636.6  219.55
  4820.4  216.41  4975.9  219.99  4978.4  214.24  4979.4  213.74  5020.6  213.74
  5032.8  219.32  5040.5   219.6  5233.7  220.28  5335.7  218.92  5386.6  220.24
  5437.6  218.83  5473.6  220.38  5566.6  219.14  5581.6  217.27  5653.5  222.78
  5731.5  232.11  6053.2  243.01  6230.9  250.52  6268.4  252.51  6321.8  254.31
#Mann= 9 ,-1 , 0
  3605.5     .17       0  3889.5     .15       0  4421.3     .17       0
  4487.9     .15       0  4975.9     .09       0  5040.5     .15       0
  6053.2     .17       0  6230.9     .11       0  6268.4     .15       0
Bank Sta=4975.9,5040.5
XS Rating Curve= 0 ,0
Exp/Cntr=0.3,0.1

Type RM Length L Ch R = 1 ,44500   ,500,500,500
BEGIN DESCRIPTION:
CANEY CREEK NORTH 87.0
END DESCRIPTION:
XS GIS Cut Line= 3
      3764942.92       10181903.      3764257.87     10180887.21
      3763325.69      10179765.1
#Sta/Elev= 30
  3774.8  244.53  4147.1   230.5  4645.4  217.17  4838.5   216.6  4954.2  217.75
  4975.2  219.09  4984.1   213.5  5025.3   213.5  5033.3  218.14  5039.8  219.22
  5153.1  217.58  5181.7  218.36  5259.9  216.54  5274.2  217.63  5302.8  216.18
  5473.4  217.31  5494.2   218.4  5543.7  216.96  5621.8  217.81    5644  216.16
  5671.3  216.08  5722.1  218.73  5806.7   218.9  5942.2  217.07  5991.6  222.03
  6090.6  234.72  6140.1  239.37  6261.2  247.62  6436.4  253.41  6458.8  254.59
#Mann= 5 ,-1 , 0
  3774.8     .17       0  4147.1     .15       0  4975.2     .09       0
  5039.8     .15       0  6436.4     .11       0
Bank Sta=4975.2,5039.8
XS Rating Curve= 0 ,0
Exp/Cntr=0.3,0.1

Type RM Length L Ch R = 1 ,44000   ,399,399,399
BEGIN DESCRIPTION:
CANEY CREEK NORTH 86.0
END DESCRIPTION:
XS GIS Cut Line= 3
      3765081.81     10181843.96       3764642.1     10180636.11
      3763502.38     10179601.31
#Sta/Elev= 30
  3714.6  246.53  3767.8  246.37  4019.8  234.68    4322  225.16  4547.8  220.14
  4617.3  221.35  4690.6  218.35  4795.5  216.76  4825.1  212.32  4866.3  212.32
  4876.6  217.24  4881.9  217.46  4984.1  218.37  4998.9  215.56  5034.7  219.45
  5048.8  218.17  5140.8   218.7  5325.2  215.73  5480.7  217.27  5516.5   215.2
    5573  216.98  5714.5  217.65  5983.4   217.3  6045.9  219.57  6125.4  222.87
  6289.6  234.63  6355.8  239.35  6411.6   243.2  6484.7  247.82  6539.4  250.37
#Mann= 11 ,-1 , 0
  3714.6     .17       0  4019.8     .15       0    4322     .17       0
  4690.6     .15       0  4984.1     .09       0  5034.7     .15       0
  6045.9     .17       0  6289.6     .11       0  6355.8     .15       0
  6411.6     .11       0  6484.7     .15       0
Bank Sta=4984.1,5034.7
XS Rating Curve= 0 ,0
Exp/Cntr=0.3,0.1

Type RM Length L Ch R = 1 ,43601   ,1150,1150,1150
BEGIN DESCRIPTION:
CANEY CREEK NORTH 85.0
END DESCRIPTION:
XS GIS Cut Line= 3
      3765217.23     10181767.58      3764922.03     10180363.07
      3763623.44     10179309.22
#Sta/Elev= 30
  3564.8  250.44  3571.5  249.15    3643   244.8  3767.9  239.12  3949.5  230.94
  3975.1  230.95  4099.6  225.84  4365.8  217.41  4869.2  215.54  4930.5  218.03
  4971.4   218.2  4974.6  212.17  4975.6  211.67  5017.3  211.67  5025.8   217.9
  5252.8  215.72  5275.1  216.69    5296  215.82  5545.3  217.56  5601.3  217.09
  5644.4  214.33  5722.7  217.12  5879.3  216.24  5999.2  218.98    6119  224.06
  6298.1  233.13  6397.2  240.58  6512.2  247.26  6603.4  251.79  6672.4  253.51
#Mann= 7 ,-1 , 0
  3564.8     .17       0  3767.9     .15       0  4099.6     .17       0
  4365.8     .15       0  4971.4     .09       0  5025.8     .15       0
    6119     .17       0
Bank Sta=4971.4,5025.8
XS Rating Curve= 0 ,0
Exp/Cntr=0.3,0.1

Type RM Length L Ch R = 1 ,42451   ,866,866,866
BEGIN DESCRIPTION:
CANEY CREEK NORTH 84.0
END DESCRIPTION:
XS GIS Cut Line= 3
      3765398.27     10181659.05      3765495.03     10180300.89
       3763732.8     10179206.13
#Sta/Elev= 30
  3638.4  247.61  3983.5  228.65  4207.8  219.86    4669     216  4699.1  213.12
  4719.1  215.41  4939.7  214.99  4979.8  216.64  4984.9  209.41  5026.7  209.41
    5033  217.23  5127.4  214.36  5173.3  216.63  5338.1  216.79  5526.6  214.87
  5608.9  216.65  5688.4  213.73  5761.6   216.9  5804.1  214.13  5891.4  216.78
  5919.8  214.28  5950.3  216.03  6029.6  214.79  6102.8  217.41  6370.9  219.08
  6556.1  225.47  6638.9  228.65  6748.7  238.83  6856.7  245.62  7074.6  256.13
#Mann= 5 ,-1 , 0
  3638.4     .17       0  3983.5     .15       0  4979.8     .09       0
    5033     .15       0  6556.1     .17       0
Bank Sta=4979.8,5033
XS Rating Curve= 0 ,0
Exp/Cntr=0.3,0.1

Type RM Length L Ch R = 1 ,41585   ,612,612,612
BEGIN DESCRIPTION:
CANEY CREEK NORTH 82.0
END DESCRIPTION:
XS GIS Cut Line= 3
       3765713.2     10181662.79      3765862.77     10179761.37
      3765119.85     10177945.03
#Sta/Elev= 30
  3092.7  247.26  3174.7  245.22  3254.9  237.96  3445.5  229.79    3616   220.1
  3696.3  221.53  3905.1  218.72  4709.4   214.1  4745.3  216.33  4799.7  215.13
    4920  216.88  4940.1  214.54  4948.2  209.66  4992.2  209.66  5011.1  215.23
  5026.8  216.15  5080.2  214.59  5140.8  216.03  5181.6  213.26    5211  215.47
  5264.5   214.3  5496.8  216.16  5540.5  218.17  5832.2  217.38  5994.3  220.33
  6137.9  226.84  6167.3  229.76  6244.7  231.72  6414.4  229.16  6962.4  232.24
#Mann= 5 ,-1 , 0
  3092.7     .17       0  3905.1     .15       0    4920     .09       0
  5026.8     .15       0  6414.4     .17       0
Bank Sta=4920,5026.8
XS Rating Curve= 0 ,0
Exp/Cntr=0.3,0.1

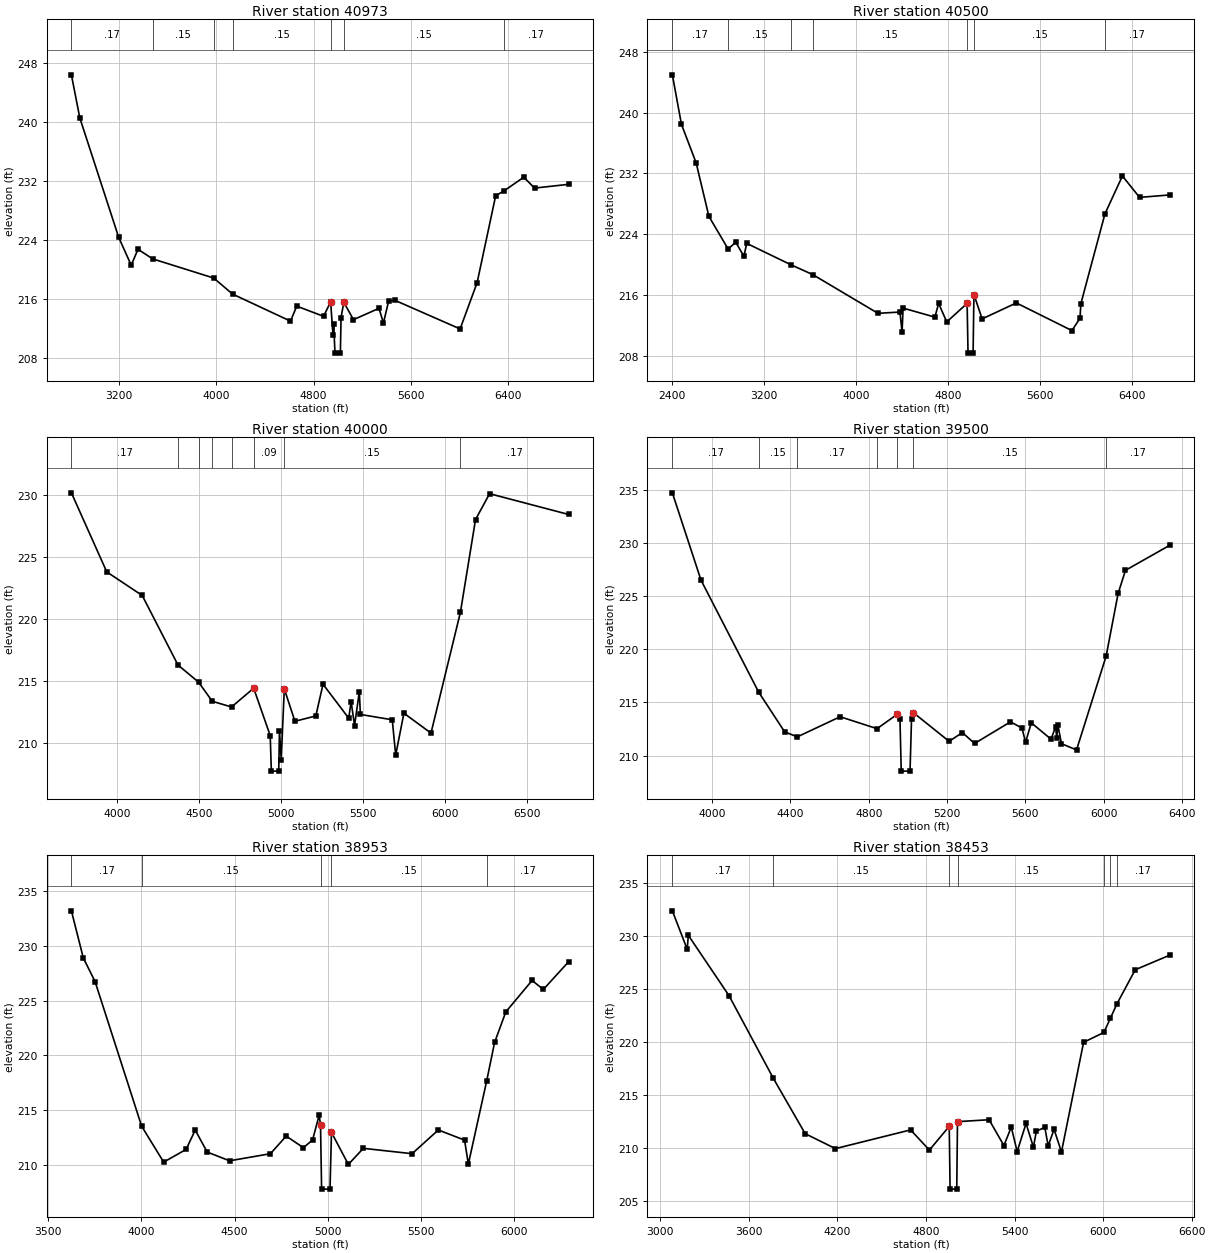
Type RM Length L Ch R = 1 ,40973   ,473,473,473
BEGIN DESCRIPTION:
CANEY CREEK NORTH 81.0
END DESCRIPTION:
XS GIS Cut Line= 3
      3765770.49     10181668.01      3766301.55     10179543.48
      3765297.27     10177934.83
#Sta/Elev= 30
  2810.1  246.45  2879.1   240.6  3198.6  224.36  3301.7  220.56  3357.2  222.73
  3478.9  221.42  3979.8  218.82  4134.6  216.64  4610.8  212.96  4662.3     215
  4882.8  213.61  4940.6  215.59  4960.1  211.08  4965.3  212.56  4976.7  208.61
  5020.7  208.61  5026.4  213.45  5049.1  215.53  5128.2  213.16  5338.1   214.7
  5374.7  212.71  5417.2  215.67  5469.1  215.79  6004.9   211.9  6144.9  218.21
  6297.1  230.01  6366.6  230.68  6528.3  232.53  6616.8  231.05  6896.4  231.56
#Mann= 7 ,-1 , 0
  2810.1     .17       0  3478.9     .15       0  3979.8     .17       0
  4134.6     .15       0  4940.6     .09       0  5049.1     .15       0
  6366.6     .17       0
Bank Sta=4940.6,5049.1
XS Rating Curve= 0 ,0
Exp/Cntr=0.3,0.1

Type RM Length L Ch R = 1 ,40500   ,500,500,500
BEGIN DESCRIPTION:
CANEY CREEK NORTH 80.0
END DESCRIPTION:
XS GIS Cut Line= 3
      3765848.63      10181688.8      3766616.47     10179208.74
      3765494.46     10177897.19
#Sta/Elev= 30
  2403.8  244.99  2482.8  238.47  2610.8  233.38  2721.5  226.35  2888.8  222.05
    2955  222.95  3025.5  221.09  3050.5  222.79  3438.4  219.95  3624.8  218.68
  4191.5  213.58  4382.2  213.75  4400.9  211.08  4409.5  214.27  4686.1  213.08
  4718.7  214.88  4789.2  212.45  4966.2  214.89  4974.2  208.34  5018.2  208.34
  5025.4  216.06  5096.7  212.85  5394.2  214.95  5877.2  211.31  5947.5  212.93
  5955.2  214.86  6164.7  226.69  6316.3  231.67  6465.6  228.85    6726  229.17
#Mann= 7 ,-1 , 0
  2403.8     .17       0  2888.8     .15       0  3438.4     .17       0
  3624.8     .15       0  4966.2     .09       0  5025.4     .15       0
  6164.7     .17       0
Bank Sta=4966.2,5025.4
XS Rating Curve= 0 ,0
Exp/Cntr=0.3,0.1

Type RM Length L Ch R = 1 ,40000   ,500,500,500
BEGIN DESCRIPTION:
CANEY CREEK NORTH 79.0
END DESCRIPTION:
XS GIS Cut Line= 3
      3768013.68     10179657.53      3766967.97     10178917.11
      3765548.61     10177885.41
#Sta/Elev= 30
  3718.7  230.14  3934.6  223.78  4151.2  221.88  4369.4  216.29  4495.8   214.9
  4578.7  213.37  4696.5  212.91  4831.7  214.42  4932.7  210.61  4939.7  207.75
  4984.7  207.75  4989.3  211.01    5000  208.68  5018.7  214.37  5083.7  211.76
  5211.2  212.19  5255.2  214.74  5412.1  212.01  5426.8  213.34  5447.7  211.42
    5477  214.14  5483.2  212.31    5678  211.88  5698.9  209.04  5749.1  212.41
  5914.5  210.81  6094.2  220.53  6186.5  227.99  6272.3  230.07  6754.7   228.4
#Mann= 8 ,-1 , 0
  3718.7     .17       0  4369.4     .15       0  4495.8     .17       0
  4578.7     .11       0  4696.5     .15       0  4831.7     .09       0
  5018.7     .15       0  6094.2     .17       0
Bank Sta=4831.7,5018.7
XS Rating Curve= 0 ,0
Exp/Cntr=0.3,0.1

Type RM Length L Ch R = 1 ,39500   ,547,547,547
BEGIN DESCRIPTION:
CANEY CREEK NORTH 78.0
END DESCRIPTION:
XS GIS Cut Line= 3
      3768086.91     10179277.47       3767145.3     10178527.95
      3765909.84     10178015.56
#Sta/Elev= 30
  3796.5   234.7  3942.8   226.5  4237.4  215.98  4370.4  212.24  4435.1  211.77
  4653.9  213.66  4842.7  212.54  4945.6  213.89  4959.8  213.46  4966.2  208.55
  5011.2  208.55  5018.9  213.48  5027.7  214.05    5211  211.35  5278.7  212.17
  5341.2  211.15  5524.6  213.18  5583.2   212.6  5601.7  211.26    5631  213.09
  5731.9  211.55  5755.1  212.71  5761.2  211.67  5766.6  212.91  5785.1  211.13
  5862.1  210.54  6013.5  219.36  6074.8  225.25  6112.3  227.42  6337.5  229.76
#Mann= 7 ,-1 , 0
  3796.5     .17       0  4237.4     .15       0  4435.1     .17       0
  4842.7     .15       0  4945.6     .09       0  5027.7     .15       0
  6013.5     .17       0
Bank Sta=4945.6,5027.7
XS Rating Curve= 0 ,0
Exp/Cntr=0.3,0.1

Type RM Length L Ch R = 1 ,38953   ,500,500,500
BEGIN DESCRIPTION:
CANEY CREEK NORTH 77.0
END DESCRIPTION:
XS GIS Cut Line= 3
      3768167.85     10179061.07      3767238.42     10178046.54
      3765953.18     10177896.24
#Sta/Elev= 30
  3624.1  233.23  3687.9  228.93  3751.4  226.75  4001.4  213.53  4119.6  210.25
  4239.8  211.41  4289.1  213.18  4353.3  211.17  4473.5  210.37    4693  211.02
  4777.5  212.63    4870  211.57  4919.3  212.28  4954.5  214.54  4961.9  213.65
  4967.7  207.78  5012.8  207.78  5020.7  212.97  5111.3  210.04  5191.9  211.51
  5453.6  211.02  5594.6  213.19  5735.5  212.26  5755.7  210.07  5853.9  217.65
  5896.6  221.19    5957  223.99    6098  226.86  6158.4  226.04    6294  228.57
#Mann= 5 ,-1 , 0
  3624.1     .17       0  4001.4     .15       0  4961.9     .09       0
  5020.7     .15       0  5853.9     .17       0
Bank Sta=4961.9,5020.7
XS Rating Curve= 0 ,0
Exp/Cntr=0.3,0.1

Type RM Length L Ch R = 1 ,38453   ,453,453,453
BEGIN DESCRIPTION:
CANEY CREEK NORTH 76.0
END DESCRIPTION:
XS GIS Cut Line= 4
      3768779.28     10179152.41      3767409.43     10177809.37
      3767310.53     10177750.55      3765975.55     10177738.39
#Sta/Elev= 30
  3081.6  232.39  3182.5  228.74  3189.6  230.08  3465.4  224.37  3765.5  216.56
  3981.6  211.32  4186.7  209.91  4695.8  211.68  4823.1  209.77  4957.5  212.02
  4963.3  206.08  5008.4  206.08  5013.5  212.46  5227.7  212.64  5327.8   210.2
  5377.8  211.94  5417.8  209.63  5477.8  212.29  5527.8  210.05  5547.8  211.56
    5605  211.92  5627.8  210.17  5667.8  211.73  5717.8  209.59  5867.8  219.96
  6005.2  220.89  6049.6  222.24  6093.1  223.58  6217.8  226.82  6450.1  228.19
#Mann= 7 ,-1 , 0
  3081.6     .17       0  3765.5     .15       0  4957.5     .09       0
  5013.5     .15       0  6005.2     .17       0  6049.6     .15       0
  6093.1     .17       0
Bank Sta=4957.5,5013.5
XS Rating Curve= 0 ,0
Exp/Cntr=0.3,0.1

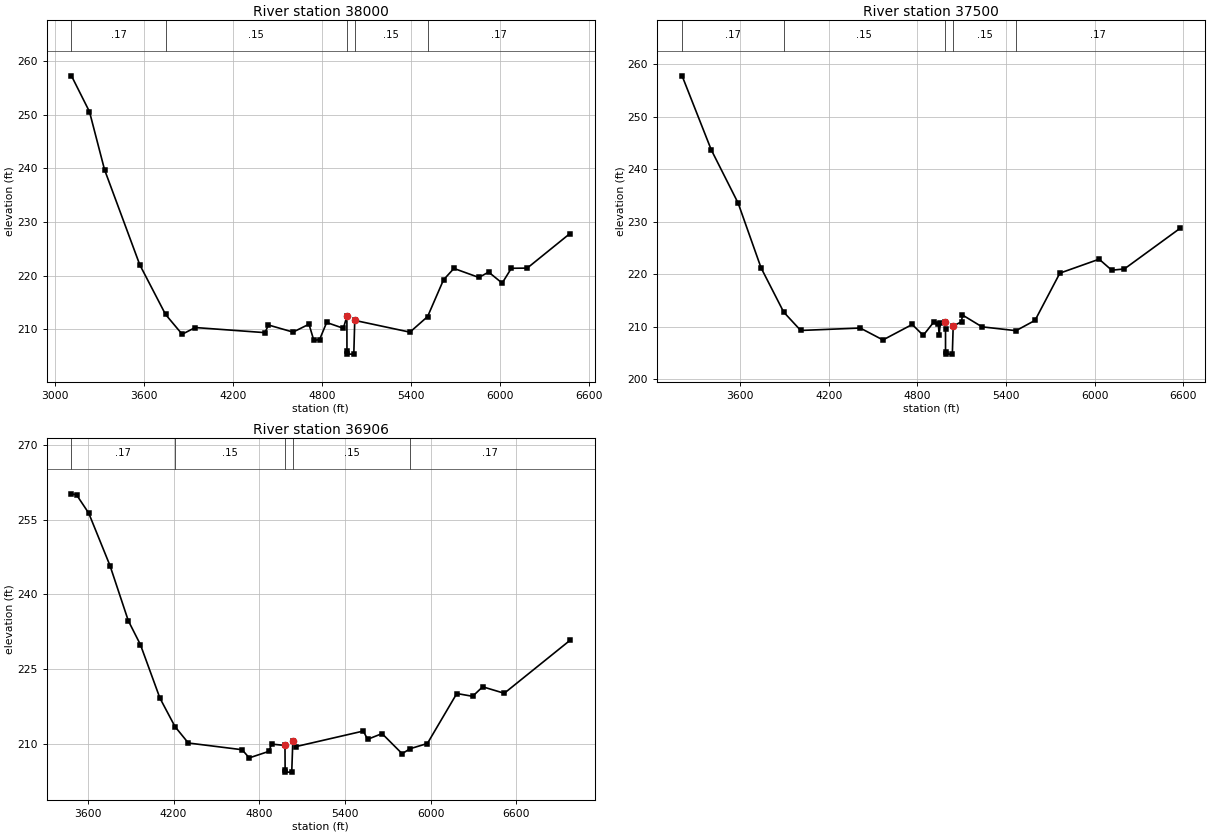
Type RM Length L Ch R = 1 ,38000   ,500,500,500
BEGIN DESCRIPTION:
CANEY CREEK NORTH 75.0
END DESCRIPTION:
XS GIS Cut Line= 3
      3769167.84     10178211.07       3767421.1     10177493.99
      3766077.14     10176901.44
#Sta/Elev= 30
  3111.8  257.21  3233.2  250.53  3334.5  239.75  3571.9  222.04  3745.2  212.81
  3857.3  209.11  3945.4  210.36  4414.8  209.41  4438.8  210.83  4604.3  209.51
  4711.6  210.98  4744.1  207.98  4782.9  208.11  4830.6   211.3    4943  210.22
  4966.9  212.43  4967.4  205.91  4968.4  205.41  5013.5  205.41  5019.8  211.69
  5391.5   209.5  5510.6   212.4  5617.8  219.24  5687.8  221.36    5856  219.68
  5921.6  220.68  6012.8  218.63  6074.6  221.39  6181.5  221.42  6468.8  227.84
#Mann= 5 ,-1 , 0
  3111.8     .17       0  3745.2     .15       0  4966.9     .09       0
  5019.8     .15       0  5510.6     .17       0
Bank Sta=4966.9,5019.8
XS Rating Curve= 0 ,0
Exp/Cntr=0.3,0.1

Type RM Length L Ch R = 1 ,37500   ,594,594,594
BEGIN DESCRIPTION:
CANEY CREEK NORTH 74.5
END DESCRIPTION:
XS GIS Cut Line= 3
      3769223.26     10178085.05      3767669.48     10177188.68
       3766127.9     10176831.12
#Sta/Elev= 30
  3206.2  257.78  3403.6  243.69    3586  233.52  3741.1   221.2  3894.5  212.76
  4009.7  209.26  4413.1  209.72    4567  207.45  4765.1   210.4  4839.8  208.33
  4910.2  210.83  4941.8  210.54  4947.6  208.47  4955.7   210.7  4984.9  210.94
  4990.7  209.54  4990.8  205.25  4991.8  204.75  5036.9  204.75  5042.7  210.11
  5099.6  210.92  5104.8  212.22  5237.9  209.95  5468.4  209.22  5597.1  211.18
  5765.2  220.18  6031.4  222.84  6116.7  220.74  6202.1  220.98  6582.5  228.78
#Mann= 5 ,-1 , 0
  3206.2     .17       0  3894.5     .15       0  4984.9     .09       0
  5042.7     .15       0  5468.4     .17       0
Bank Sta=4984.9,5042.7
XS Rating Curve= 0 ,0
Exp/Cntr=0.3,0.1

Type RM Length L Ch R = 1 ,36906   ,592,592,592
BEGIN DESCRIPTION:
CANEY CREEK NORTH 74.0
END DESCRIPTION:
XS GIS Cut Line= 3
      3769296.05     10177912.12       3768102.9     10176977.37
      3766141.65     10176732.36
#Sta/Elev= 30
  3484.3  260.22  3520.1  260.01  3605.1  256.35  3754.3   245.8  3882.7  234.72
  3967.7  229.91  4104.2  219.18  4209.8  213.46  4303.1  210.17  4680.1  208.82
  4729.9  207.18  4866.4  208.48  4887.2  209.95  4980.3  209.68  4981.4  204.82
  4982.4  204.32  5027.7  204.32  5035.3  210.57  5055.5  209.44  5529.1  212.57
  5559.4  210.91  5660.5  212.06  5801.2  208.02  5856.6  209.02  5978.1  210.07
  6184.2  220.11    6295  219.55  6365.6  221.46  6516.8  220.16  6976.5  230.77
#Mann= 5 ,-1 , 0
  3484.3     .17       0  4209.8     .15       0  4980.3     .09       0
  5035.3     .15       0  5856.6     .17       0
Bank Sta=4980.3,5035.3
XS Rating Curve= 0 ,0
Exp/Cntr=0.3,0.1