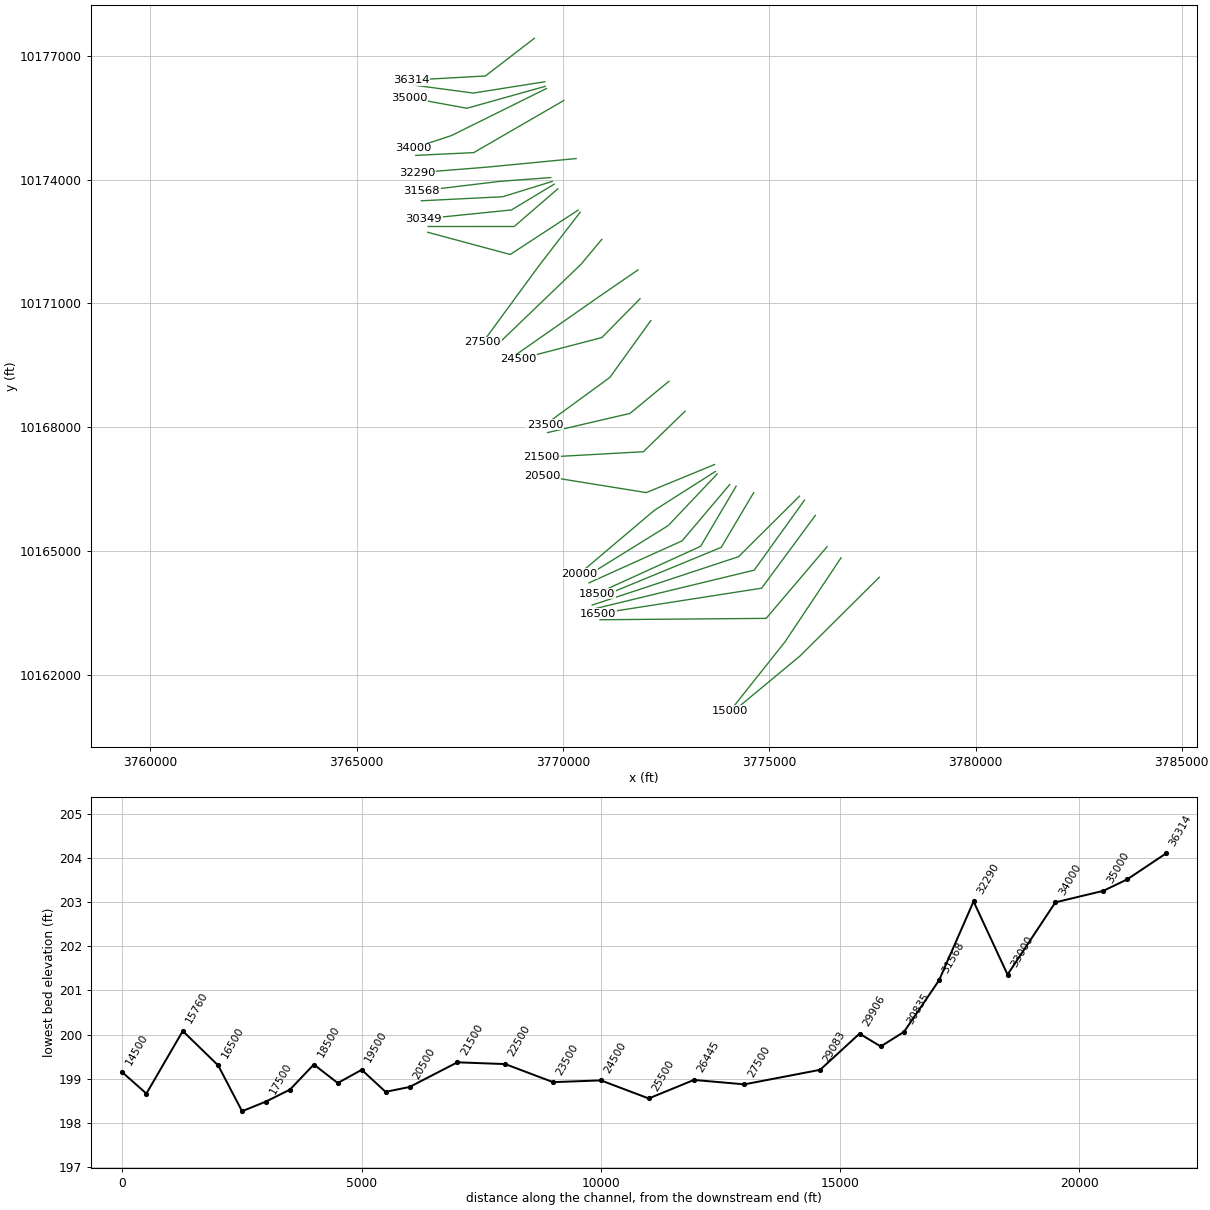
HEC-RAS study CANEY CREEK NORTH.prj: CANEY CREEK NORTH Base Level Engineering

--- CANEY CREEK NORTH.g01 (geometry) --- (continued)

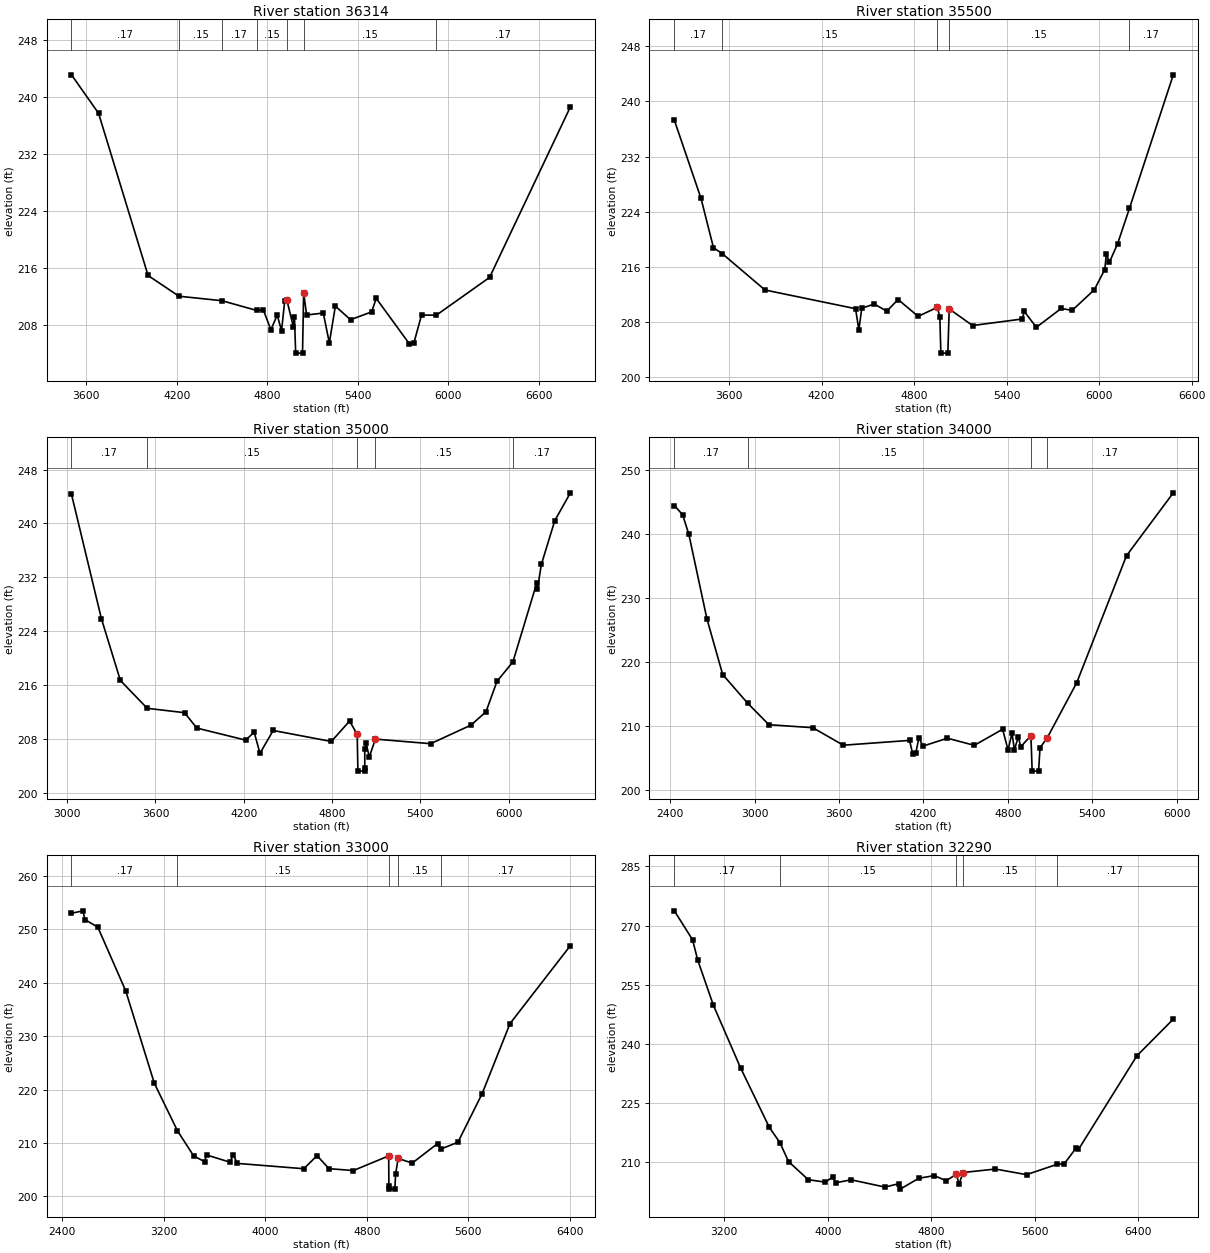
Type RM Length L Ch R = 1 ,36314   ,814,814,814
BEGIN DESCRIPTION:
CANEY CREEK NORTH 71.0
END DESCRIPTION:
XS GIS Cut Line= 3
      3769305.37     10177425.17      3768118.77      10176512.5
      3766313.13     10176412.55
#Sta/Elev= 30
    3503  243.18  3682.4  237.78  4010.4  215.01  4214.7   212.1  4499.3  211.47
  4730.6   210.1  4774.1  210.17  4824.2  207.39  4865.8  209.45  4894.8  207.26
  4915.6  211.43  4930.1  211.55  4973.7  207.72    4980  209.22  4988.3  204.11
  5033.6  204.11    5041  212.54    5061  209.46  5171.2  209.74  5211.2  205.56
  5251.3  210.71  5351.5   208.8  5491.7   209.9  5521.7   211.8    5742   205.4
  5772.1  205.59  5822.2  209.46  5919.6  209.43  6272.9  214.74  6808.4  238.69
#Mann= 7 ,-1 , 0
    3503     .17       0  4214.7     .15       0  4499.3     .17       0
  4730.6     .15       0  4930.1     .09       0    5041     .15       0
  5919.6     .17       0
Bank Sta=4930.1,5041
XS Rating Curve= 0 ,0
Exp/Cntr=0.3,0.1

Type RM Length L Ch R = 1 ,35500   ,500,500,500
BEGIN DESCRIPTION:
CANEY CREEK NORTH 70.0
END DESCRIPTION:
XS GIS Cut Line= 3
      3769558.35     10176372.31      3767825.38     10176098.29
      3766357.48      10176294.1
#Sta/Elev= 30
  3245.5  237.28  3418.3  225.95  3499.1   218.8  3556.6  217.93  3833.2  212.67
  4420.4  209.96  4441.8  206.89  4460.9  210.03  4541.9  210.64  4622.9   209.6
  4696.4  211.29  4826.3  208.85    4951  210.16  4967.1  208.73  4973.6  203.52
  5018.9  203.52  5027.8  209.93  5179.1  207.52  5501.9  208.47  5514.9  209.56
    5593  207.26  5754.1     210  5824.8  209.71  5968.7   212.7  6036.6  215.64
  6046.9  217.85  6066.9  216.71    6120  219.39  6196.4  224.49  6480.9  243.86
#Mann= 5 ,-1 , 0
  3245.5     .17       0  3556.6     .15       0    4951     .09       0
  5027.8     .15       0  6196.4     .17       0
Bank Sta=4951,5027.8
XS Rating Curve= 0 ,0
Exp/Cntr=0.3,0.1

Type RM Length L Ch R = 1 ,35000   ,1000,1000,1000
BEGIN DESCRIPTION:
CANEY CREEK NORTH 69.0
END DESCRIPTION:
XS GIS Cut Line= 3
      3769567.82     10176261.06      3767670.32     10175729.68
      3766273.59     10175986.82
#Sta/Elev= 30
  3029.5  244.33  3232.7  225.89  3361.8  216.71  3544.2  212.58  3797.9  211.93
    3881  209.65  4213.3  207.86  4271.1  209.04  4310.4   205.9  4400.2  209.29
  4795.5  207.66  4919.5  210.69  4971.3  208.71  4975.9  203.26  5021.5  203.26
  5022.5  203.76  5022.8  206.53  5031.6  207.41  5053.3  205.35  5094.8  208.01
  5470.2  207.33  5744.8  210.09  5846.5  212.07  5920.9  216.57  6029.6  219.48
  6191.1  231.14  6196.2   230.3  6222.7  233.93  6314.2  240.44  6420.2  244.55
#Mann= 5 ,-1 , 0
  3029.5     .17       0  3544.2     .15       0  4971.3     .09       0
  5094.8     .15       0  6029.6     .17       0
Bank Sta=4971.3,5094.8
XS Rating Curve= 0 ,0
Exp/Cntr=0.3,0.1

Type RM Length L Ch R = 1 ,34000   ,1000,1000,1000
BEGIN DESCRIPTION:
CANEY CREEK NORTH 67.0
END DESCRIPTION:
XS GIS Cut Line= 3
      3769600.33      10176208.8      3767295.26     10175068.05
      3766367.86     10174761.33
#Sta/Elev= 30
  2428.1  244.41  2486.7  242.98  2531.3   239.9  2659.6  226.75  2771.8  218.06
  2949.3  213.59  3100.3  210.24  3412.7  209.77  3629.7  207.04  4100.8  207.79
  4123.2  205.72  4145.6  205.88  4168.1  208.21  4196.1   206.9  4369.9  208.13
    4562  207.02  4762.8  209.53  4801.7  206.29  4829.7  208.95  4846.6  206.33
  4874.6  208.36  4891.4  206.79  4964.3  208.53  4972.9     203  5018.6     203
  5028.9  206.63  5081.5  208.24  5289.9  216.78  5644.1  236.59  5976.8  246.39
#Mann= 4 ,-1 , 0
  2428.1     .17       0  2949.3     .15       0  4964.3     .09       0
  5081.5     .17       0
Bank Sta=4964.3,5081.5
XS Rating Curve= 0 ,0
Exp/Cntr=0.3,0.1

Type RM Length L Ch R = 1 ,33000   ,710,710,710
BEGIN DESCRIPTION:
CANEY CREEK NORTH 65.0
END DESCRIPTION:
XS GIS Cut Line= 3
        3770023.      10175919.9      3767836.05     10174654.81
      3766432.24     10174588.02
#Sta/Elev= 30
  2473.5  253.01  2563.6  253.47  2579.3  251.84  2681.2   250.4  2900.8  238.49
  3126.4  221.18  3308.5  212.29  3436.1  207.59  3522.3   206.5  3538.1  207.76
  3720.4  206.42  3750.2  207.76  3779.2  206.18  4304.8  205.18  4408.7  207.63
  4502.6  205.19  4694.8  204.84  4973.3  207.58  4974.9  201.86  4975.9  201.36
  5021.6  201.36  5028.2  204.28  5048.3  207.11  5158.4  206.23  5358.6  209.89
  5387.1  208.89  5518.8  210.14    5709   219.2  5929.2  232.35  6405.4  246.96
#Mann= 5 ,-1 , 0
  2473.5     .17       0  3308.5     .15       0  4973.3     .09       0
  5048.3     .15       0  5387.1     .17       0
Bank Sta=4973.3,5048.3
XS Rating Curve= 0 ,0
Exp/Cntr=0.3,0.1

Type RM Length L Ch R = 1 ,32290   ,722,722,722
BEGIN DESCRIPTION:
CANEY CREEK NORTH 63.0
END DESCRIPTION:
XS GIS Cut Line= 3
      3770317.84     10174511.07      3768141.72     10174301.34
      3766477.33     10174168.35
#Sta/Elev= 30
  2813.8  273.73  2954.4  266.37  2994.6  261.19  3115.2  249.75  3326.2  233.78
  3547.2  218.75  3629.4  214.83  3696.3  210.02  3848.6  205.42  3979.2   204.8
  4039.4  206.11  4059.5  204.62  4180.1  205.39  4441.3  203.54  4551.8  204.43
  4559.1  203.02  4702.5  205.77  4823.1  206.46  4913.5  205.16  4993.8  206.79
  5013.9  204.22    5044  207.24  5294.8  208.12  5535.6   206.7  5771.1  209.32
  5826.5  209.44  5916.8  213.38  5936.8  213.09  6388.3  236.89  6669.7  246.21
#Mann= 5 ,-1 , 0
  2813.8     .17       0  3629.4     .15       0  4993.8     .09       0
    5044     .15       0  5771.1     .17       0
Bank Sta=4993.8,5044
XS Rating Curve= 0 ,0
Exp/Cntr=0.3,0.1

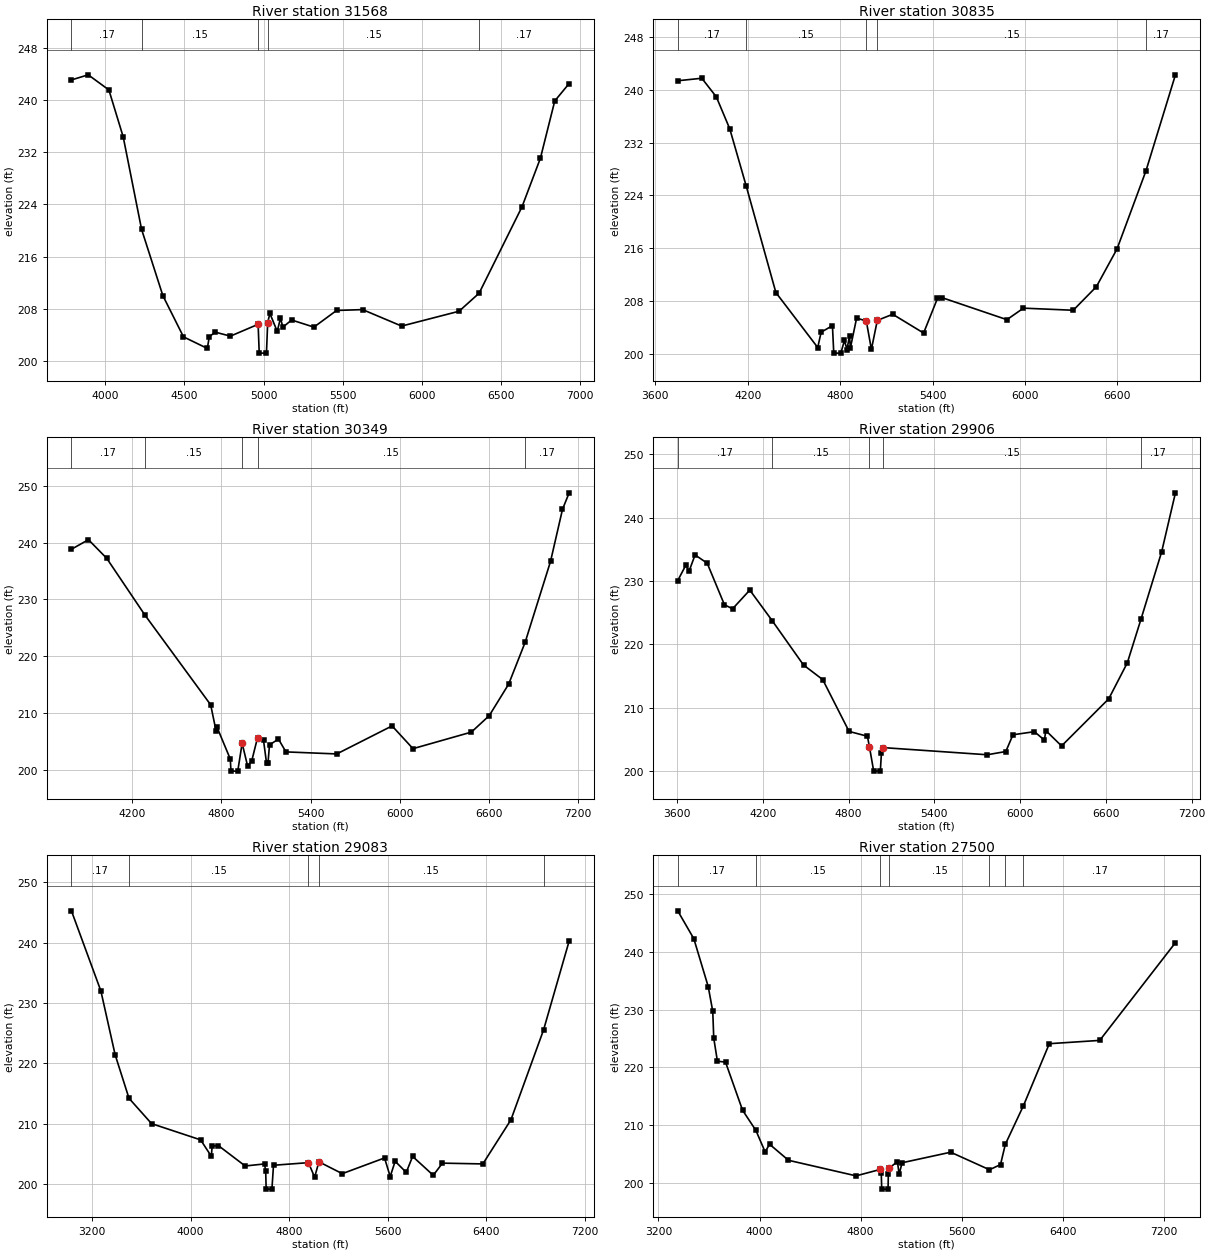
Type RM Length L Ch R = 1 ,31568   ,733,733,733
BEGIN DESCRIPTION:
CANEY CREEK NORTH 62.0
END DESCRIPTION:
XS GIS Cut Line= 3
      3769703.69     10174049.75      3768493.46     10173960.72
      3766577.65     10173730.45
#Sta/Elev= 30
  3786.5  243.04  3892.6  243.82    4023  241.51  4113.7   234.3  4229.4  220.18
  4363.9  210.03  4494.2  203.72  4644.7  201.95  4657.1  203.75  4694.8  204.44
  4790.4  203.83  4965.5  205.64  4972.4  201.23  5018.1  201.23  5025.8  205.91
  5039.9   207.3  5086.2  204.55  5106.4  206.57  5122.1   205.2  5176.9   206.3
  5317.9  205.21  5460.9  207.76  5625.3  207.89  5871.8  205.37  6234.4  207.64
    6361   210.4  6631.7  223.61  6748.1  231.06  6838.7  239.82  6929.6  242.49
#Mann= 5 ,-1 , 0
  3786.5     .17       0  4229.4     .15       0  4965.5     .09       0
  5025.8     .15       0    6361     .17       0
Bank Sta=4965.5,5025.8
XS Rating Curve= 0 ,0
Exp/Cntr=0.3,0.1

Type RM Length L Ch R = 1 ,30835   ,486,486,486
BEGIN DESCRIPTION:
CANEY CREEK NORTH 61.0
END DESCRIPTION:
XS GIS Cut Line= 3
      3769737.22     10173955.49      3768539.29     10173585.37
      3766565.53     10173487.18
#Sta/Elev= 30
  3746.2  241.42  3902.5   241.8  3996.7  238.98  4084.3   234.1  4190.3  225.47
  4383.3  209.26  4654.9  200.91    4677  203.24  4750.3  204.23  4758.9  200.06
  4804.6  200.06  4828.5  201.99  4844.5   200.6  4861.2   202.7  4866.4   200.8
  4907.3  205.39  4970.1  204.93  5003.2  200.63  5041.5  205.03  5141.6  205.96
  5341.9  203.11    5432  208.38    5462  208.48  5882.5  205.14  5989.9  206.89
  6313.1  206.57  6463.2  210.15  6597.2  215.88  6785.1  227.75  6976.2  242.32
#Mann= 5 ,-1 , 0
  3746.2     .17       0  4190.3     .15       0  4970.1     .09       0
  5041.5     .15       0  6785.1     .17       0
Bank Sta=4970.1,5041.5
XS Rating Curve= 0 ,0
Exp/Cntr=0.3,0.1

Type RM Length L Ch R = 1 ,30349   ,443,443,443
BEGIN DESCRIPTION:
CANEY CREEK NORTH 60.0
END DESCRIPTION:
XS GIS Cut Line= 3
      3769785.86     10173888.59      3768751.03     10173265.19
      3766623.26     10173049.28
#Sta/Elev= 30
  3791.9  238.84  3906.3  240.53  4029.1  237.25  4285.3  227.27  4728.2  211.42
  4765.1  206.74  4770.9  207.47  4860.2  201.86  4864.6  199.73  4910.3  199.73
  4939.8  204.64  4976.7  200.61  5004.1  201.51  5043.4  205.64  5083.6  205.16
  5103.7  201.18  5113.8  201.21  5123.8  204.37  5184.1  205.37  5234.4  203.12
  5576.1  202.76    5948   207.7  6088.7  203.69  6481.4  206.61  6601.4  209.51
    6732  215.07  6842.8  222.44  7013.5   236.7  7093.9  245.87  7138.7  248.79
#Mann= 5 ,-1 , 0
  3791.9     .17       0  4285.3     .15       0  4939.8     .09       0
  5043.4     .15       0  6842.8     .17       0
Bank Sta=4939.8,5043.4
XS Rating Curve= 0 ,0
Exp/Cntr=0.3,0.1

Type RM Length L Ch R = 1 ,29906   ,823,823,823
BEGIN DESCRIPTION:
CANEY CREEK NORTH 59.0
END DESCRIPTION:
XS GIS Cut Line= 3
      3769874.03     10173776.07      3768817.44     10172864.15
      3766731.24     10172863.79
#Sta/Elev= 30
  3604.3  230.05  3662.1  232.53    3683   231.5  3725.7   234.1  3810.6   232.8
  3930.9  226.26  3987.9   225.6  4108.6  228.56  4265.8  223.72  4484.3  216.75
  4618.7  214.45    4803  206.28  4931.3  205.52  4945.6  203.85  4975.3  200.02
  5021.8  200.02  5029.6  202.95  5039.6  203.73  5769.6   202.6  5899.6  203.11
  5949.6  205.75  6099.6  206.24  6169.6  204.91  6179.6  206.41  6289.6  203.99
  6619.6  211.42  6749.6  217.09  6845.9  224.02  6989.6  234.57  7086.2  243.89
#Mann= 5 ,-1 , 0
  3604.3     .17       0  4265.8     .15       0  4945.6     .09       0
  5039.6     .15       0  6845.9     .17       0
Bank Sta=4945.6,5039.6
XS Rating Curve= 0 ,0
Exp/Cntr=0.3,0.1

Type RM Length L Ch R = 1 ,29083   ,1583,1583,1583
BEGIN DESCRIPTION:
CANEY CREEK NORTH 56.0
END DESCRIPTION:
XS GIS Cut Line= 3
      3770367.85     10173261.07      3768721.53     10172185.17
      3766721.75      10172723.6
#Sta/Elev= 30
  3033.3  245.25  3272.2  231.99  3387.7  221.45  3500.3  214.23  3683.3  210.04
  4081.5  207.35  4168.2  204.63    4175  206.36  4226.3  206.39  4442.9  203.03
  4600.2  203.37  4609.3  202.13  4613.1   199.2  4659.8   199.2  4672.6  203.15
  4956.2  203.58  5006.2  201.17    5041  203.72  5230.4  201.76  5573.4  204.36
  5619.4  201.28  5659.4  203.81  5749.5  201.97  5801.2  204.61  5968.6  201.49
  6043.3   203.5  6370.8  203.37  6598.7  210.67  6863.5  225.55    7071  240.25
#Mann= 5 ,-1 , 0
  3033.3     .17       0  3500.3     .15       0  4956.2     .09       0
    5041     .15       0  6863.5     .17       0
Bank Sta=4956.2,5041
XS Rating Curve= 0 ,0
Exp/Cntr=0.3,0.1

Type RM Length L Ch R = 1 ,27500   ,1055,1055,1055
BEGIN DESCRIPTION:
CANEY CREEK NORTH 55.0
END DESCRIPTION:
XS GIS Cut Line= 3
      3770417.83     10173211.04      3769412.39     10171905.54
      3768056.07      10170055.7
#Sta/Elev= 30
  3352.2  247.11  3479.9  242.27    3594  233.96  3629.8  229.68  3637.6  225.04
  3666.6  221.04  3730.8  220.89  3865.9  212.54  3971.6  209.04  4044.4  205.32
  4079.7  206.65  4229.2  203.87  4764.7  201.17  4955.8  202.28    4964  201.72
  4967.9  198.87    5018  198.87  5020.1  201.51  5028.6  202.55  5092.3  203.63
  5105.8  201.44  5128.9  203.44  5513.9  205.27  5821.3  202.23  5908.5  203.12
  5946.7  206.64  6090.1  213.33  6295.1  224.08  6694.3  224.65  7293.8  241.59
#Mann= 7 ,-1 , 0
  3352.2     .17       0  3971.6     .15       0  4955.8     .09       0
  5028.6     .15       0  5821.3     .17       0  5946.7     .15       0
  6090.1     .17       0
Bank Sta=4955.8,5028.6
XS Rating Curve= 0 ,0
Exp/Cntr=0.3,0.1

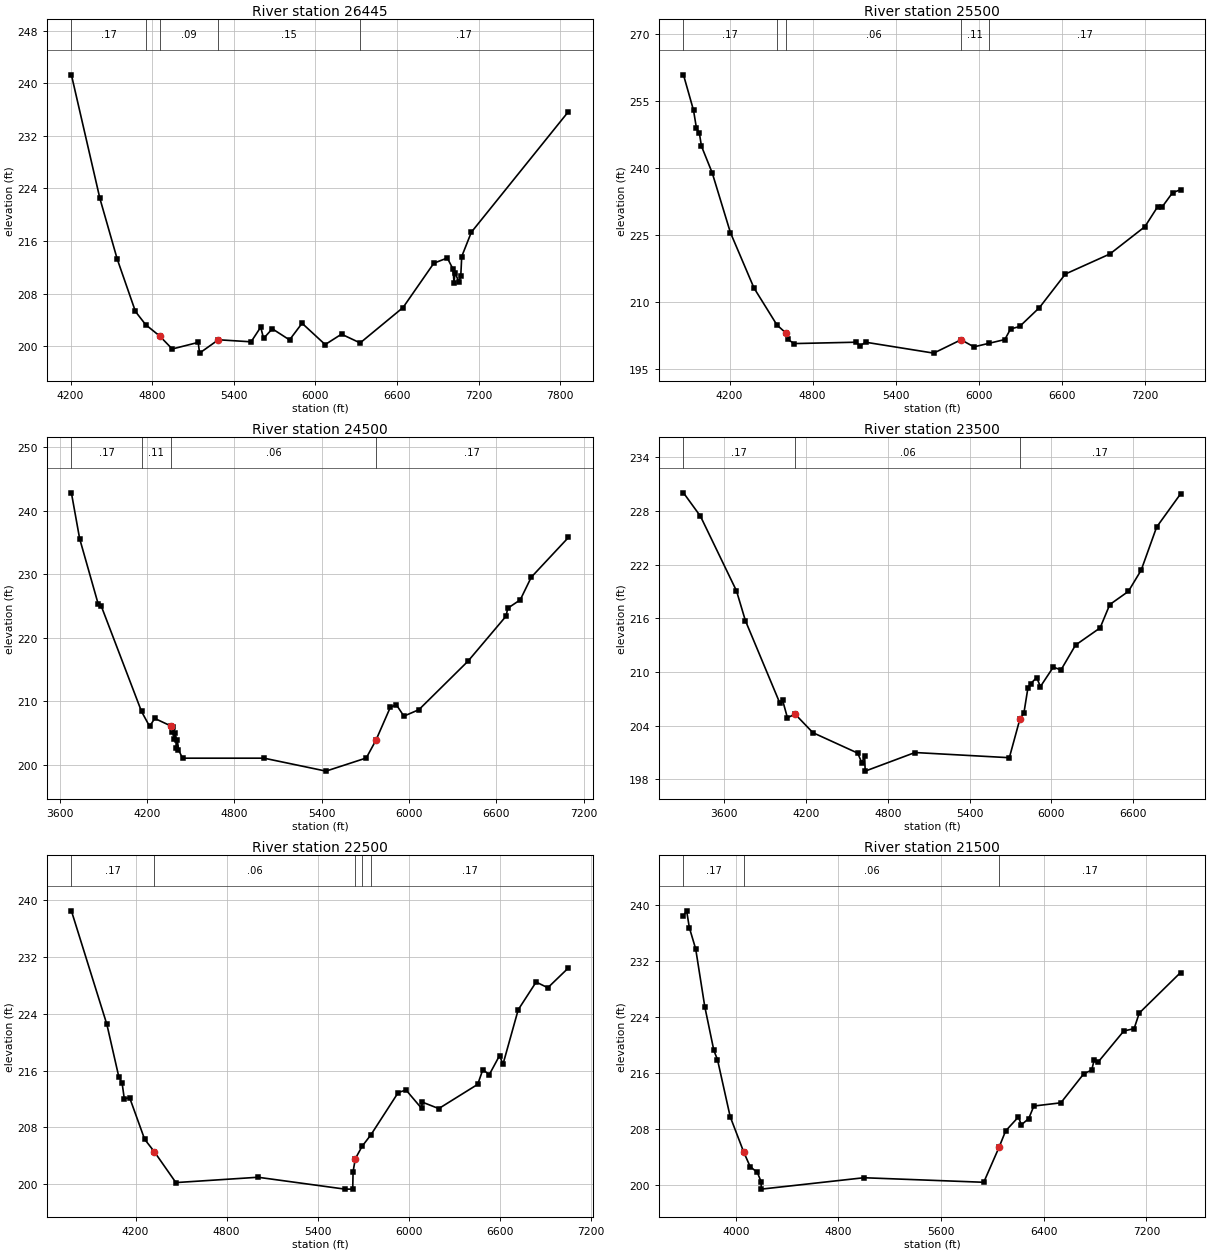
Type RM Length L Ch R = 1 ,26445   ,945,945,945
BEGIN DESCRIPTION:
CANEY CREEK NORTH 53.0
END DESCRIPTION:
XS GIS Cut Line= 3
      3770941.18     10172551.81      3770432.17     10171942.95
      3768367.84     10169961.06
#Sta/Elev= 30
  4206.4  241.27  4415.7   222.5  4543.3  213.27  4677.3   205.3  4752.6  203.29
  4855.6  201.57    4948   199.6  5138.8   200.6  5148.9  198.97  5287.2     201
  5527.8  200.69  5598.5  202.92  5619.6   201.2  5683.5  202.67  5810.5  200.98
  5902.6  203.51  6072.5  200.27  6192.6  201.85  6329.7  200.52  6645.1   205.9
  6871.6  212.64  6970.6  213.43  7013.1  211.73    7020  209.62  7027.2  211.22
  7055.5  209.78  7069.7  210.69  7076.6  213.65  7147.4  217.35  7861.7  235.69
#Mann= 5 ,-1 , 0
  4206.4     .17       0  4752.6     .15       0  4855.6     .09       0
  5287.2     .15       0  6329.7     .17       0
Bank Sta=4855.6,5287.2
XS Rating Curve= 0 ,0
Exp/Cntr=0.3,0.1

Type RM Length L Ch R = 1 ,25500   ,1000,1000,1000
BEGIN DESCRIPTION:
CANEY CREEK NORTH 51.0
END DESCRIPTION:
XS GIS Cut Line= 3
      3771817.82     10171811.05      3770883.82     10171169.53
      3768867.89      10169761.1
#Sta/Elev= 30
  3866.9  260.94  3939.7  252.97  3960.9  248.94  3981.9  247.83  3996.8  244.96
  4074.6  238.96  4205.9  225.59  4376.4  213.16  4542.9  204.84  4606.9  203.07
  4621.3  201.63    4666  200.69  5117.1     201  5140.5  200.12  5182.4     201
  5675.3  198.55  5873.2  201.55  5965.6  199.95  6074.4  200.75  6188.9  201.59
  6230.8  203.96  6296.2  204.52  6439.2  208.75  6626.7  216.28  6948.6  220.78
  7201.5   226.9    7294  231.39  7323.6  231.22  7401.2  234.51  7459.2  235.19
#Mann= 5 ,-1 , 0
  3866.9     .17       0  4542.9     .11       0  4606.9     .06       0
  5873.2     .11       0  6074.4     .17       0
Bank Sta=4606.9,5873.2
XS Rating Curve= 0 ,0
Exp/Cntr=0.3,0.1

Type RM Length L Ch R = 1 ,24500   ,1000,1000,1000
BEGIN DESCRIPTION:
CANEY CREEK NORTH 49.0
END DESCRIPTION:
XS GIS Cut Line= 3
      3771867.85     10171111.07      3770942.03     10170171.45
      3768913.37     10169642.05
#Sta/Elev= 30
  3680.9   242.8  3737.4   235.6  3864.7  225.31    3886  224.97  4162.7  208.36
  4218.3  206.01  4253.7  207.26  4366.8  206.05  4373.9  205.11    4381  205.92
    4388  204.03  4395.1  205.03  4402.2  202.56  4409.3  203.86  4416.3  202.34
  4444.6     201  5004.7     201  5430.2  198.96  5707.1  201.03    5774  203.85
  5872.5  209.02  5913.8  209.42  5965.5  207.62  6068.8  208.64  6406.1  216.28
  6668.2  223.39  6678.6  224.61  6765.1  225.94  6840.9  229.51  7096.6  235.78
#Mann= 4 ,-1 , 0
  3680.9     .17       0  4162.7     .11       0  4366.8     .06       0
    5774     .17       0
Bank Sta=4366.8,5774
XS Rating Curve= 0 ,0
Exp/Cntr=0.3,0.1

Type RM Length L Ch R = 1 ,23500   ,1000,1000,1000
BEGIN DESCRIPTION:
CANEY CREEK NORTH 47.0
END DESCRIPTION:
XS GIS Cut Line= 3
      3772128.64     10170582.99      3771137.77     10169206.18
      3769566.18     10168058.74
#Sta/Elev= 30
  3303.7  230.03  3428.3  227.41  3692.2  219.07  3757.2  215.75  4008.3  206.58
  4029.7  206.86  4065.3  204.89  4121.8  205.29  4251.9  203.22  4580.8  200.93
  4610.3  199.85  4631.2   200.6  4635.1  198.92    5000     201  5691.3  200.42
  5768.5  204.73  5797.9   205.4  5827.2  208.19  5848.1   208.7  5891.4  209.38
  5919.1  208.37  6013.4  210.55  6069.7  210.23  6176.3  213.01  6356.3  214.93
  6427.3  217.54  6563.3  219.01  6657.5  221.39  6770.5   226.2  6945.9  229.91
#Mann= 3 , 0 , 0
  3303.7     .17       0  4121.8     .06       0  5768.5     .17       0
Bank Sta=4121.8,5768.5
XS Rating Curve= 0 ,0
Exp/Cntr=0.3,0.1

Type RM Length L Ch R = 1 ,22500   ,1000,1000,1000
BEGIN DESCRIPTION:
CANEY CREEK NORTH 45.0
END DESCRIPTION:
XS GIS Cut Line= 3
      3772567.81     10169111.04      3771624.39     10168332.63
      3769625.23     10167867.76
#Sta/Elev= 30
  3776.9  238.48  4010.7   222.5  4088.9  215.17  4111.1  214.25  4125.4  212.05
  4160.6   212.2  4259.6  206.34  4323.4  204.59  4465.4  200.25  5006.7     201
  5579.5  199.33  5630.8  199.33    5633  201.77  5647.7   203.6  5692.4  205.35
  5751.2  206.99  5930.7  212.92  5982.1  213.27  6084.1   210.7  6089.2  211.57
  6197.7  210.66  6454.3  214.07  6488.1  216.14  6530.7  215.44  6598.1  218.11
  6621.1  216.91  6721.3  224.57  6839.3  228.46  6916.3  227.66  7052.5  230.46
#Mann= 5 ,-1 , 0
  3776.9     .17       0  4323.4     .06       0  5647.7     .11       0
  5692.4     .15       0  5751.2     .17       0
Bank Sta=4323.4,5647.7
XS Rating Curve= 0 ,0
Exp/Cntr=0.3,0.1

Type RM Length L Ch R = 1 ,21500   ,1000,1000,1000
BEGIN DESCRIPTION:
CANEY CREEK NORTH 43.0
END DESCRIPTION:
XS GIS Cut Line= 3
      3772958.51      10168385.1      3771949.11     10167403.92
      3769486.31     10167267.05
#Sta/Elev= 30
  3592.3  238.49  3616.9  239.19    3638  236.79  3687.6  233.73  3758.3  225.49
  3829.1  219.21  3857.4   217.9  3956.2  209.75  4062.4  204.65  4111.8   202.6
  4168.4  201.75  4196.7  200.45  4199.3  199.37  4998.5     201  5932.7  200.35
  6052.9   205.4    6103  207.69  6203.1   209.7  6225.4  208.56  6283.2  209.47
  6323.3  211.26  6533.6  211.72  6713.9  215.91    6774  216.39    6794   217.9
  6824.1  217.55  7024.4     222  7104.5  222.33  7144.6  224.56  7466.6  230.36
#Mann= 3 , 0 , 0
  3592.3     .17       0  4062.4     .06       0  6052.9     .17       0
Bank Sta=4062.4,6052.9
XS Rating Curve= 0 ,0
Exp/Cntr=0.3,0.1

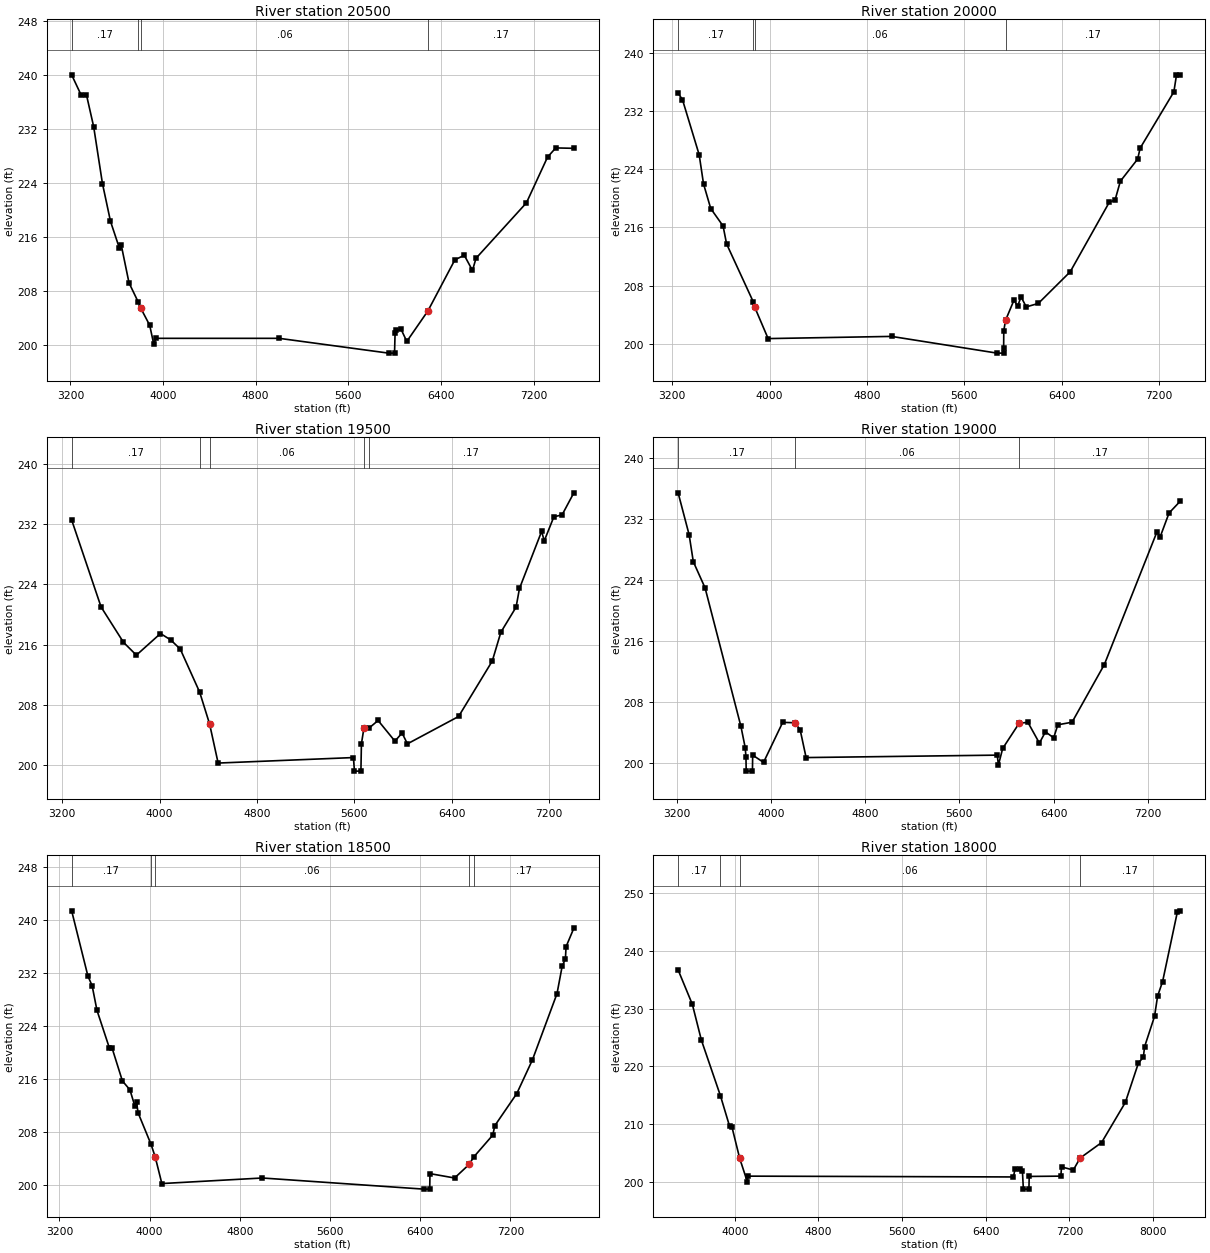
Type RM Length L Ch R = 1 ,20500   ,500,500,500
BEGIN DESCRIPTION:
CANEY CREEK NORTH 41.0
END DESCRIPTION:
XS GIS Cut Line= 3
      3773673.78     10167093.44      3772019.11     10166412.78
      3769503.62     10166819.14
#Sta/Elev= 30
  3210.8  240.01  3292.9  237.01  3338.4  237.07    3401  232.33  3476.7  223.92
  3546.3  218.32  3623.6  214.33  3638.9  214.83  3706.3  209.21  3785.9  206.37
  3807.5  205.47  3884.8  202.94  3920.1  200.11  3938.1     201  5003.2     201
    5948  198.81  5999.5  198.81  6004.1  201.73  6014.2   202.2  6054.8  202.38
  6105.4  200.54  6287.7  205.06  6520.6  212.62  6601.8   213.3  6672.7  211.05
  6703.1  212.85  7138.6  221.06    7321  227.83  7391.9  229.19  7548.1  229.13
#Mann= 4 ,-1 , 0
  3210.8     .17       0  3785.9     .11       0  3807.5     .06       0
  6287.7     .17       0
Bank Sta=3807.5,6287.7
XS Rating Curve= 0 ,0
Exp/Cntr=0.3,0.1

Type RM Length L Ch R = 1 ,20000   ,500,500,500
BEGIN DESCRIPTION:
CANEY CREEK NORTH 40.0
END DESCRIPTION:
XS GIS Cut Line= 3
      3773693.92     10166924.66      3772216.41     10165984.81
      3770403.93     10164450.66
#Sta/Elev= 30
  3248.9  234.45  3284.6  233.57    3422  225.98  3457.6  221.98  3516.8  218.59
  3618.2  216.19  3647.2  213.72  3866.5  205.75    3879  204.99  3988.3   200.7
  5002.3     201  5869.3   198.7  5922.1   198.7  5923.3   199.4  5924.3  201.76
  5938.5   203.2  6008.8  206.01  6037.4  205.12    6066  206.45  6108.8  205.06
  6207.7  205.53  6470.2  209.89    6790  219.42  6839.4  219.81  6882.3  222.35
    7024  225.39  7044.8   226.9  7321.7  234.64  7343.3  236.96  7374.6  236.98
#Mann= 4 ,-1 , 0
  3248.9     .17       0  3866.5     .11       0    3879     .06       0
  5938.5     .17       0
Bank Sta=3879,5938.5
XS Rating Curve= 0 ,0
Exp/Cntr=0.3,0.1

Type RM Length L Ch R = 1 ,19500   ,500,500,500
BEGIN DESCRIPTION:
CANEY CREEK NORTH 39.0
END DESCRIPTION:
XS GIS Cut Line= 3
      3773737.26     10166863.85      3772551.75     10165613.94
      3770508.16     10164346.54
#Sta/Elev= 30
  3277.3  232.53  3519.3  220.98  3703.3  216.29  3809.3  214.59  4007.5  217.46
  4092.4   216.6  4170.1  215.39  4329.4  209.68  4410.8  205.47  4481.2  200.27
  5592.9     201  5601.8   199.2  5654.7   199.2  5658.8  202.82  5680.1  204.98
  5717.7  204.86  5795.9  205.92  5934.2  203.18    5993  204.26  6036.9  202.82
  6457.4  206.45  6734.3  213.81  6804.9  217.63  6929.9  220.96  6957.9  223.44
  7140.1  231.02  7161.4  229.75  7240.5  232.95  7307.9   233.2  7404.7  236.13
#Mann= 5 ,-1 , 0
  3277.3     .17       0  4329.4     .11       0  4410.8     .06       0
  5680.1     .11       0  5717.7     .17       0
Bank Sta=4410.8,5680.1
XS Rating Curve= 0 ,0
Exp/Cntr=0.3,0.1

Type RM Length L Ch R = 1 ,19000   ,500,500,500
BEGIN DESCRIPTION:
CANEY CREEK NORTH 38.0
END DESCRIPTION:
XS GIS Cut Line= 3
        3774043.     10166608.24       3772887.1     10165243.07
      3770629.65     10164224.99
#Sta/Elev= 30
  3211.2  235.43    3305  229.91  3340.2  226.39  3440.2  222.95  3744.7  204.77
  3780.8     202  3787.3   200.8  3789.4   198.9  3842.4   198.9  3844.5     201
  3936.7  200.05  4099.3   205.3  4205.9  205.25  4248.7  204.25  4298.2  200.68
  5921.6     201  5931.6   199.7  5967.8  201.88  6106.6  205.16  6181.5  205.32
  6279.5  202.58  6331.3  204.06  6400.7  203.27  6436.2  204.98  6556.9  205.32
  6831.2  212.89  7277.3  230.27  7305.9  229.67  7380.8  232.78  7476.4  234.34
#Mann= 3 , 0 , 0
  3211.2     .17       0  4205.9     .06       0  6106.6     .17       0
Bank Sta=4205.9,6106.6
XS Rating Curve= 0 ,0
Exp/Cntr=0.3,0.1

Type RM Length L Ch R = 1 ,18500   ,500,500,500
BEGIN DESCRIPTION:
CANEY CREEK NORTH 37.0
END DESCRIPTION:
XS GIS Cut Line= 3
      3774197.36     10166568.73      3773337.45     10165111.77
       3770823.4     10163965.84
#Sta/Elev= 30
  3308.2  241.32  3452.7  231.46  3489.8  230.02  3532.7  226.31  3642.2  220.66
  3665.4  220.69  3758.3  215.65  3825.4   214.3  3868.3  211.88  3883.9  212.41
  3897.7  210.83  4012.8  206.06  4049.7  204.16  4108.3  200.16    5000     201
  6431.5  199.32  6484.5  199.32  6486.6  201.66    6705     201  6834.9  203.06
  6874.4  204.16  7044.1  207.48  7061.6  208.89    7257  213.75  7395.3  218.82
  7613.7  228.83  7659.1  232.94  7688.3  234.08  7693.8   235.9  7762.9   238.7
#Mann= 5 ,-1 , 0
  3308.2     .17       0  4012.8     .11       0  4049.7     .06       0
  6834.9     .11       0  6874.4     .17       0
Bank Sta=4049.7,6834.9
XS Rating Curve= 0 ,0
Exp/Cntr=0.3,0.1

Type RM Length L Ch R = 1 ,18000   ,500,500,500
BEGIN DESCRIPTION:
CANEY CREEK NORTH 36.0
END DESCRIPTION:
XS GIS Cut Line= 3
      3774622.72     10166412.51      3773836.78     10165085.83
       3770821.7     10163843.49
#Sta/Elev= 30
    3458  236.73  3594.2  230.76  3680.5  224.57    3862  214.97  3950.9  209.61
  3972.4  209.55  4046.5  204.11  4120.6  199.98  4126.4     201  6664.5  200.86
    6680  202.17  6727.9  202.18    6751  201.83  6760.1  198.75  6813.1  198.75
  6815.9  200.95  7118.7     201  7124.8   202.6  7237.7  202.06  7302.6  204.13
  7508.1  206.82  7735.2  213.77    7860  220.58  7907.9  221.63  7919.1  223.41
  8014.5  228.68  8043.8   232.2  8091.7  234.72    8233  246.79    8261  246.97
#Mann= 4 ,-1 , 0
    3458     .17       0    3862     .15       0  4046.5     .06       0
  7302.6     .17       0
Bank Sta=4046.5,7302.6
XS Rating Curve= 0 ,0
Exp/Cntr=0.3,0.1

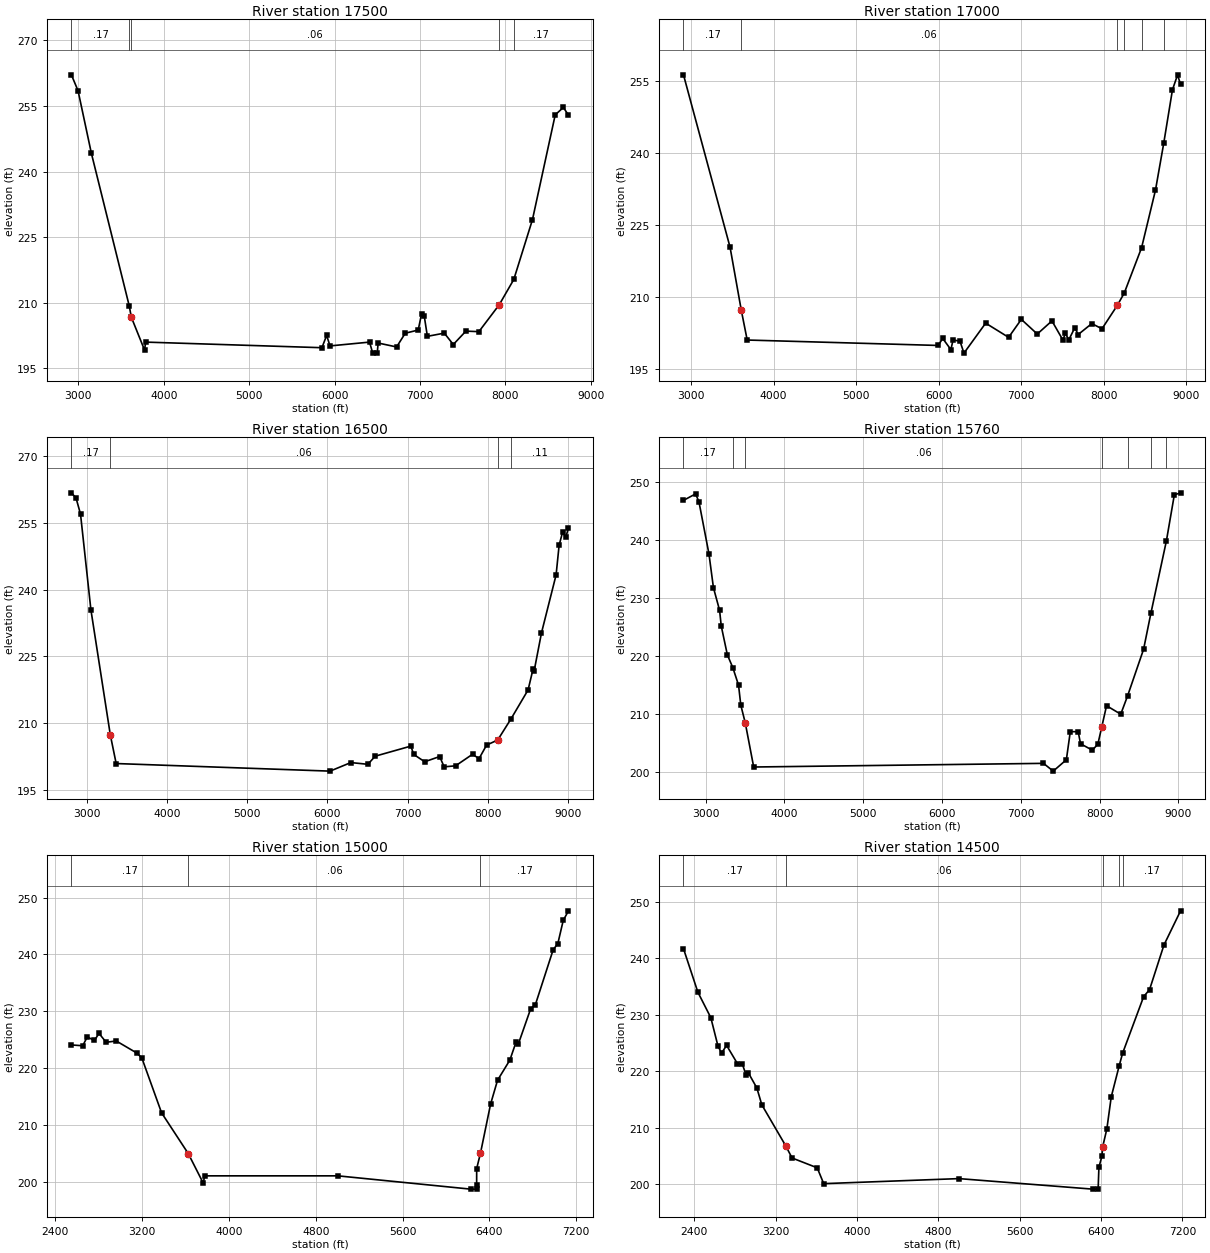
Type RM Length L Ch R = 1 ,17500   ,500,500,500
BEGIN DESCRIPTION:
CANEY CREEK NORTH 35.0
END DESCRIPTION:
XS GIS Cut Line= 3
      3775732.67     10166326.73      3774256.38     10164859.64
      3770707.78     10163686.79
#Sta/Elev= 30
  2918.7   262.1  2996.8  258.45  3152.4  244.18  3597.2  209.17  3619.1  206.75
  3774.6   199.2  3788.8     201  5851.5  199.72  5906.5  202.52  5946.3  200.13
    6409     201  6445.9  198.48  6498.9  198.48  6509.4  200.79  6725.7  199.89
  6826.7  203.03  6978.5  203.76  7017.1  207.38  7048.9  206.99  7085.9  202.32
  7283.9  203.05  7389.2  200.45  7536.7  203.51  7688.7  203.39  7926.4  209.52
  8097.7  215.33    8316     229  8582.5  252.96  8677.7  254.64  8737.4  252.89
#Mann= 5 ,-1 , 0
  2918.7     .17       0  3597.2     .15       0  3619.1     .06       0
  7926.4     .11       0  8097.7     .17       0
Bank Sta=3619.1,7926.4
XS Rating Curve= 0 ,0
Exp/Cntr=0.3,0.1

Type RM Length L Ch R = 1 ,17000   ,500,500,500
BEGIN DESCRIPTION:
CANEY CREEK NORTH 34.0
END DESCRIPTION:
XS GIS Cut Line= 3
      3775855.33     10166230.18      3774634.67     10164532.69
      3770812.35     10163608.77
#Sta/Elev= 30
  2909.2  256.28  3473.6  220.33  3609.9  207.16  3681.1  200.99  5994.7  199.86
  6050.5  201.32    6149     199    6176     201  6259.7  200.75  6307.7  198.26
  6570.8  204.51  6848.6  201.55  7002.9   205.3    7196  202.24  7373.7  204.98
    7507  200.98    7536   202.4  7577.9  201.03    7651  203.56  7692.2  202.14
  7856.8  204.42  7980.2  203.33  8165.4   208.2  8250.3  210.79    8460  220.23
  8628.4  232.24    8728  241.97  8834.2  253.16  8895.9  256.26  8932.4  254.27
#Mann= 6 ,-1 , 0
  2909.2     .17       0  3609.9     .06       0  8165.4     .17       0
  8250.3     .11       0    8460     .17       0    8728     .11       0
Bank Sta=3609.9,8165.4
XS Rating Curve= 0 ,0
Exp/Cntr=0.3,0.1

Type RM Length L Ch R = 1 ,16500   ,740,740,740
BEGIN DESCRIPTION:
CANEY CREEK NORTH 33.0
END DESCRIPTION:
XS GIS Cut Line= 3
      3776117.86     10165861.08       3774815.5     10164095.94
      3770855.35     10163478.46
#Sta/Elev= 30
  2806.4  261.69  2863.9  260.55  2920.2  256.93  3049.7  235.48  3291.9  207.43
    3365     201  6033.7   199.3  6292.7  201.22  6505.6  200.83  6596.7  202.65
    7042  204.91  7076.8  203.05  7214.1   201.4    7401  202.57    7457  200.26
  7599.6  200.49  7811.2  203.08  7892.2   202.1  7986.6  205.14    8125  206.27
    8293  211.07  8504.4  217.51  8567.2  222.26  8580.4  221.82  8671.5   230.3
  8853.7  243.29  8891.4  249.94  8934.6  252.86  8975.1  251.77    9008  253.81
#Mann= 4 ,-1 , 0
  2806.4     .17       0  3291.9     .06       0    8125     .17       0
    8293     .11       0
Bank Sta=3291.9,8125
XS Rating Curve= 0 ,0
Exp/Cntr=0.3,0.1

Type RM Length L Ch R = 1 ,15760   ,760,760,760
BEGIN DESCRIPTION:
CANEY CREEK NORTH 31.0
END DESCRIPTION:
XS GIS Cut Line= 3
      3776402.24     10165101.74      3774925.69     10163364.18
      3770898.73     10163330.89
#Sta/Elev= 30
  2719.8  246.77  2872.4  247.88  2915.3  246.57  3042.7  237.55  3099.8  231.71
  3177.8  227.81  3198.6  225.12  3276.6  220.12  3345.9  217.92  3418.3  214.91
  3446.8  211.47    3504  208.37  3610.5  200.79  7287.9  201.42  7411.3  200.08
  7577.9  202.04  7627.9  206.89  7727.9  206.88  7757.9   204.8  7907.9  203.69
  7977.9  204.74  8027.9  207.74  8087.9  211.36    8268   209.9  8354.3  213.03
    8558   221.1  8650.2  227.28  8847.6   239.8    8948  247.72  9027.1  248.07
#Mann= 7 ,-1 , 0
  2719.8     .17       0  3345.9     .11       0    3504     .06       0
  8027.9     .11       0  8354.3     .17       0  8650.2     .11       0
  8847.6     .17       0
Bank Sta=3504,8027.9
XS Rating Curve= 0 ,0
Exp/Cntr=0.3,0.1

Type RM Length L Ch R = 1 ,15000   ,500,500,500
BEGIN DESCRIPTION:
CANEY CREEK NORTH 30.0
END DESCRIPTION:
XS GIS Cut Line= 3
      3776740.78     10164832.65      3775379.95      10162792.7
      3774055.12     10161125.48
#Sta/Elev= 30
  2547.8  224.06    2652  223.92  2694.1  225.47  2760.2  224.85  2802.2   226.1
  2868.3  224.53  2961.5  224.76  3156.7  222.57  3198.8  221.68  3379.1   212.1
  3625.4  204.91  3763.6   199.7  3775.8     201  5004.2     201  6227.3  198.66
  6281.9  198.66  6283.2  199.46  6283.5  202.28  6318.7  205.01  6411.6  213.64
  6475.7  217.84  6589.5   221.4  6647.2  224.62    6668  224.25  6781.7  230.47
    6825  231.18  6988.4  240.83  7031.6  241.92  7081.3     246  7129.5  247.69
#Mann= 3 , 0 , 0
  2547.8     .17       0  3625.4     .06       0  6318.7     .17       0
Bank Sta=3625.4,6318.7
XS Rating Curve= 0 ,0
Exp/Cntr=0.3,0.1

Type RM Length L Ch R = 1 ,14500   ,500,500,500
BEGIN DESCRIPTION:
CANEY CREEK NORTH 29.0
END DESCRIPTION:
XS GIS Cut Line= 3
      3777667.84     10164361.06       3775747.5     10162453.71
      3774067.85     10161061.07
#Sta/Elev= 30
  2293.4  241.67  2434.8  233.98  2562.1  229.47  2632.8  224.42  2668.2  223.23
  2717.6  224.56  2823.7  221.34  2873.2   221.2  2908.6  219.36  2929.8  219.76
  3014.6  217.04  3064.1  214.04  3297.5  206.84  3361.1  204.65  3608.6  202.91
  3672.3  200.11    5003     201  6316.6  199.14  6371.2  199.14    6379  203.02
  6407.7  204.92  6415.5  206.59  6457.2  209.81  6500.1  215.46  6578.4  220.96
  6611.5  223.16  6819.2  233.21  6876.5  234.41  7018.5  242.32  7181.9  248.37
#Mann= 5 ,-1 , 0
  2293.4     .17       0  3297.5     .06       0  6415.5     .17       0
  6578.4     .11       0  6611.5     .17       0
Bank Sta=3297.5,6415.5
XS Rating Curve= 0 ,0
Exp/Cntr=0.3,0.1