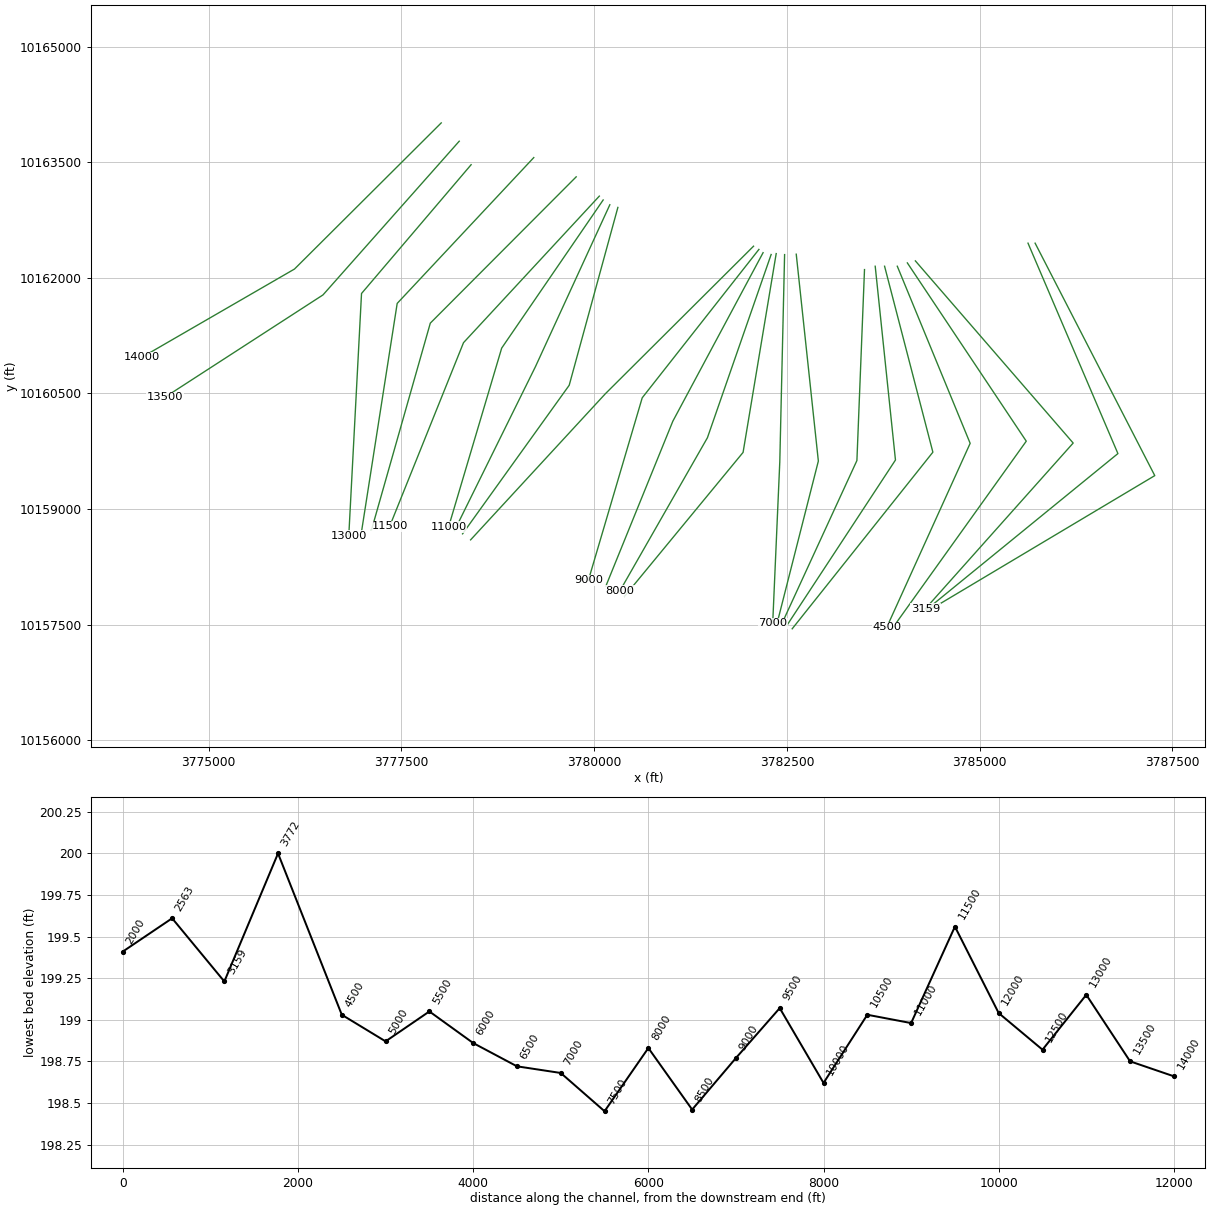
HEC-RAS study CANEY CREEK NORTH.prj: CANEY CREEK NORTH Base Level Engineering

--- CANEY CREEK NORTH.g01 (geometry) --- (continued)

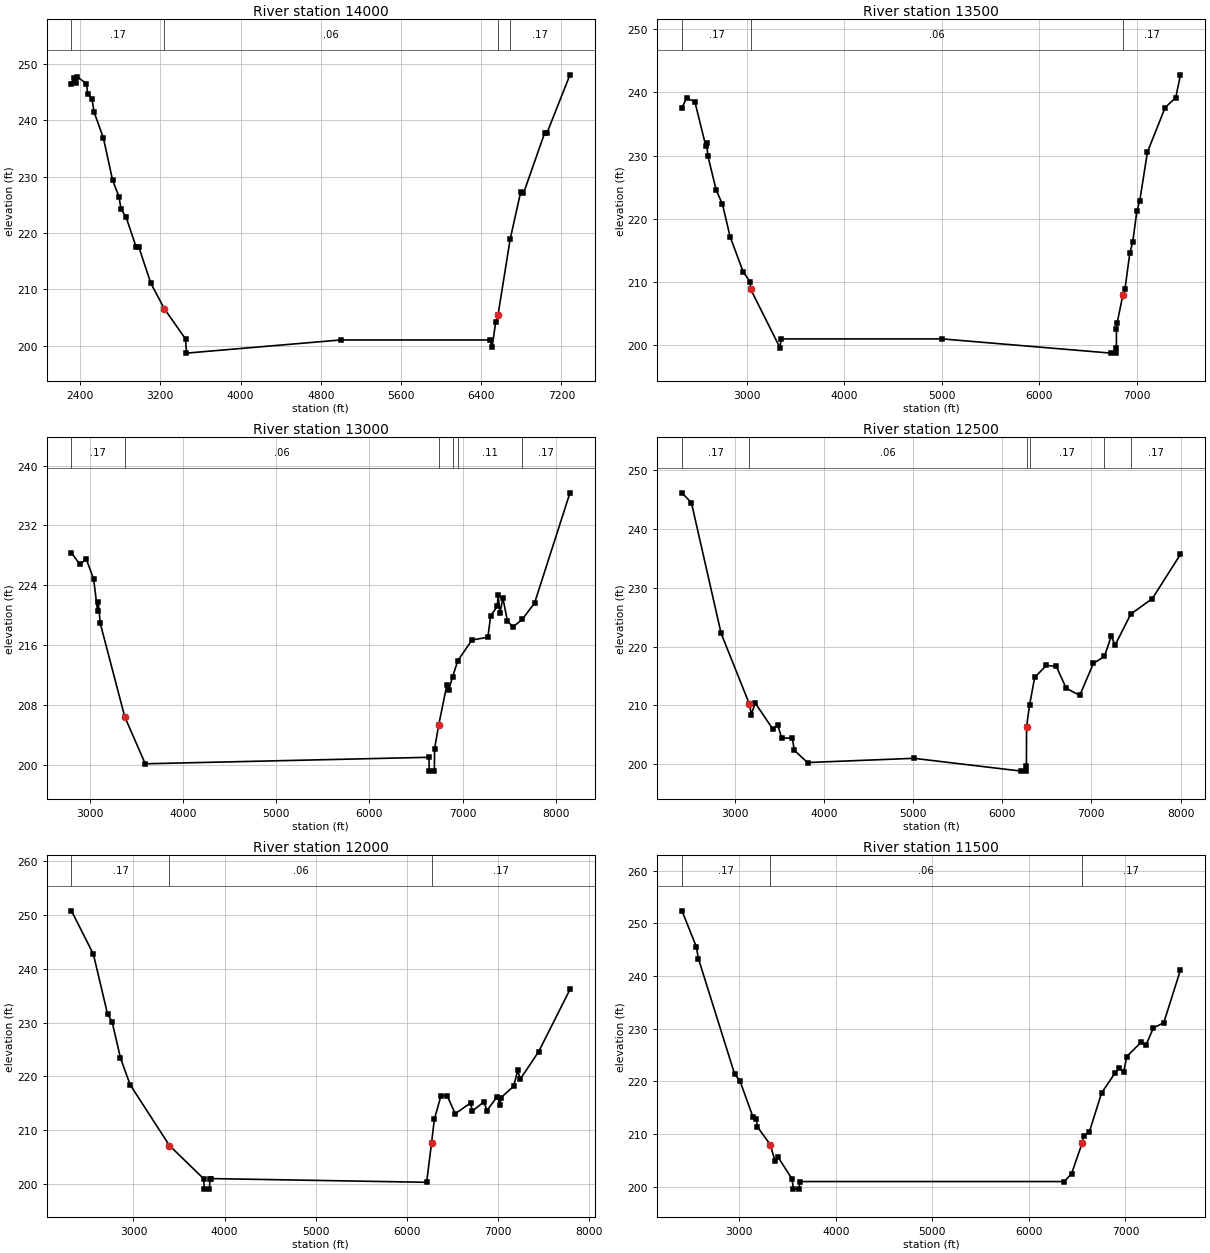
Type RM Length L Ch R = 1 ,14000   ,500,500,500
BEGIN DESCRIPTION:
CANEY CREEK NORTH 28.0
END DESCRIPTION:
XS GIS Cut Line= 3
      3778017.85     10164011.07      3776115.05     10162114.73
      3774136.57     10160969.76
#Sta/Elev= 30
  2313.6  246.48  2341.9  247.55  2363.1  246.68  2370.2  247.76  2462.1  246.55
  2476.2  244.78  2518.7   243.8  2539.9  241.43  2631.8  236.91  2723.7   229.4
  2787.4  226.44  2808.6  224.22  2858.1  222.85  2957.1  217.57  2985.4   217.5
  3105.5  211.06  3239.9  206.55    3452  201.16  3460.1  198.66  4999.1     201
  6487.2     201  6509.6  199.73    6545  204.19  6568.1  205.43  6688.9  218.87
  6793.8  227.24  6822.3  227.05  7034.9  237.84  7056.4  237.76  7285.9   248.1
#Mann= 4 ,-1 , 0
  2313.6     .17       0  3239.9     .06       0  6568.1     .11       0
  6688.9     .17       0
Bank Sta=3239.9,6568.1
XS Rating Curve= 0 ,0
Exp/Cntr=0.3,0.1

Type RM Length L Ch R = 1 ,13500   ,500,500,500
BEGIN DESCRIPTION:
CANEY CREEK NORTH 27.0
END DESCRIPTION:
XS GIS Cut Line= 3
      3778251.15     10163773.56      3776484.57     10161778.88
      3774432.31     10160449.32
#Sta/Elev= 30
  2335.5  237.58  2381.9  239.08  2467.2  238.56  2580.1  231.49  2587.6  232.07
  2601.9  229.89  2686.3  224.54  2750.7  222.29  2828.5  217.19  2963.2  211.59
  3033.4  210.06    3041  208.82  3338.7  199.64    3353     201  5003.6     201
  6732.2  198.75  6786.8  198.75  6788.2  199.55  6789.2  202.51  6795.3  203.47
  6854.9  207.97  6876.9  208.97  6926.3  214.63  6955.4  216.29  6997.8  221.18
  7027.9  222.88  7106.4  230.56  7287.8  237.61  7396.5  239.19  7445.3  242.79
#Mann= 3 , 0 , 0
  2335.5     .17       0    3041     .06       0  6854.9     .17       0
Bank Sta=3041,6854.9
XS Rating Curve= 0 ,0
Exp/Cntr=0.3,0.1

Type RM Length L Ch R = 1 ,13000   ,500,500,500
BEGIN DESCRIPTION:
CANEY CREEK NORTH 26.0
END DESCRIPTION:
XS GIS Cut Line= 3
      3778405.43     10163468.56      3776984.16     10161797.28
      3776818.89     10158652.12
#Sta/Elev= 30
  2806.1  228.34  2894.7   226.8  2965.7  227.46  3043.6  224.83  3086.5  220.51
    3093  221.79    3115  218.89  3377.5   206.4  3597.2  200.13  6638.5     201
  6641.2  199.15  6695.8  199.15  6698.5  202.16  6741.8  205.27  6828.7   210.6
  6848.8  209.93  6890.8  211.76  6947.5  213.92  7099.1  216.68  7269.3  217.04
  7299.4   219.9  7369.5  221.18  7379.5  222.67  7399.5  220.26  7429.6  222.32
  7479.6  219.19  7539.7  218.43  7637.9  219.43    7770  221.62  8149.5  236.35
#Mann= 6 ,-1 , 0
  2806.1     .17       0  3377.5     .06       0  6741.8     .11       0
  6890.8     .17       0  6947.5     .11       0  7637.9     .17       0
Bank Sta=3377.5,6741.8
XS Rating Curve= 0 ,0
Exp/Cntr=0.3,0.1

Type RM Length L Ch R = 1 ,12500   ,500,500,500
BEGIN DESCRIPTION:
CANEY CREEK NORTH 25.0
END DESCRIPTION:
XS GIS Cut Line= 3
      3779217.88      10163561.1      3777446.69     10161668.65
      3776983.97     10158705.16
#Sta/Elev= 30
    2408  246.15  2514.3  244.44  2846.5  222.27  3164.9  210.19  3186.4  208.45
  3228.9  210.42  3426.8  205.97  3483.4  206.61  3525.9  204.46  3646.1  204.42
  3667.6  202.36  3816.1  200.28  5007.7     201  6214.9  198.82    6270  198.82
  6271.4  199.72  6272.8  206.37  6306.3  210.05  6363.9  214.75  6495.5  216.81
  6606.8  216.62  6718.1   212.9    6870   211.7  7021.8  217.13    7147  218.34
    7224  221.83  7264.7  220.21    7442  225.53  7683.6  228.16  7999.4   235.7
#Mann= 6 ,-1 , 0
    2408     .17       0  3164.9     .06       0  6272.8     .11       0
  6306.3     .17       0    7147     .11       0    7442     .17       0
Bank Sta=3164.9,6272.8
XS Rating Curve= 0 ,0
Exp/Cntr=0.3,0.1

Type RM Length L Ch R = 1 ,12000   ,500,500,500
BEGIN DESCRIPTION:
CANEY CREEK NORTH 24.0
END DESCRIPTION:
XS GIS Cut Line= 3
      3779767.87     10163311.09      3777876.15     10161412.59
      3777114.01     10158730.16
#Sta/Elev= 30
  2319.9  250.76  2560.3   242.7  2715.9  231.56  2765.4  230.15  2857.3  223.42
  2963.4  218.45  3394.7  207.14  3769.5  200.98    3777  199.04  3832.6  199.04
  3840.2  200.99  3854.4     201  6216.1  200.31  6269.9   207.6  6301.1  212.05
  6373.8  216.41  6440.2  216.43  6529.8  213.05  6698.2  215.06  6716.9  213.54
  6844.2  215.25  6878.1  213.65  6990.1  216.23    7024  214.64  7029.2     216
    7170  218.15  7215.9  221.12  7242.9  219.47  7444.6  224.58  7788.6  236.14
#Mann= 3 , 0 , 0
  2319.9     .17       0  3394.7     .06       0  6269.9     .17       0
Bank Sta=3394.7,6269.9
XS Rating Curve= 0 ,0
Exp/Cntr=0.3,0.1

Type RM Length L Ch R = 1 ,11500   ,500,500,500
BEGIN DESCRIPTION:
CANEY CREEK NORTH 23.0
END DESCRIPTION:
XS GIS Cut Line= 3
      3780067.82     10163061.04      3778306.75     10161159.04
       3777348.9     10158774.86
#Sta/Elev= 30
  2407.9  252.38  2556.7  245.55  2577.7  243.32    2953  221.41  3009.1  220.05
  3143.8  213.21  3179.2  212.88    3186  211.44    3321  208.03  3370.3  204.99
  3398.6  205.74  3547.2   201.5  3561.9  199.56  3617.6  199.56  3632.2     201
  6366.5     201  6441.9  202.51  6549.7  208.22  6566.1  209.61  6625.2  210.39
  6751.6  217.78  6888.7  221.52    6937  222.53  6980.8  221.74  7013.1  224.72
    7164  227.48  7211.3  226.88  7289.2  230.16  7396.8  231.16  7569.4  241.18
#Mann= 3 , 0 , 0
  2407.9     .17       0    3321     .06       0  6549.7     .17       0
Bank Sta=3321,6549.7
XS Rating Curve= 0 ,0
Exp/Cntr=0.3,0.1

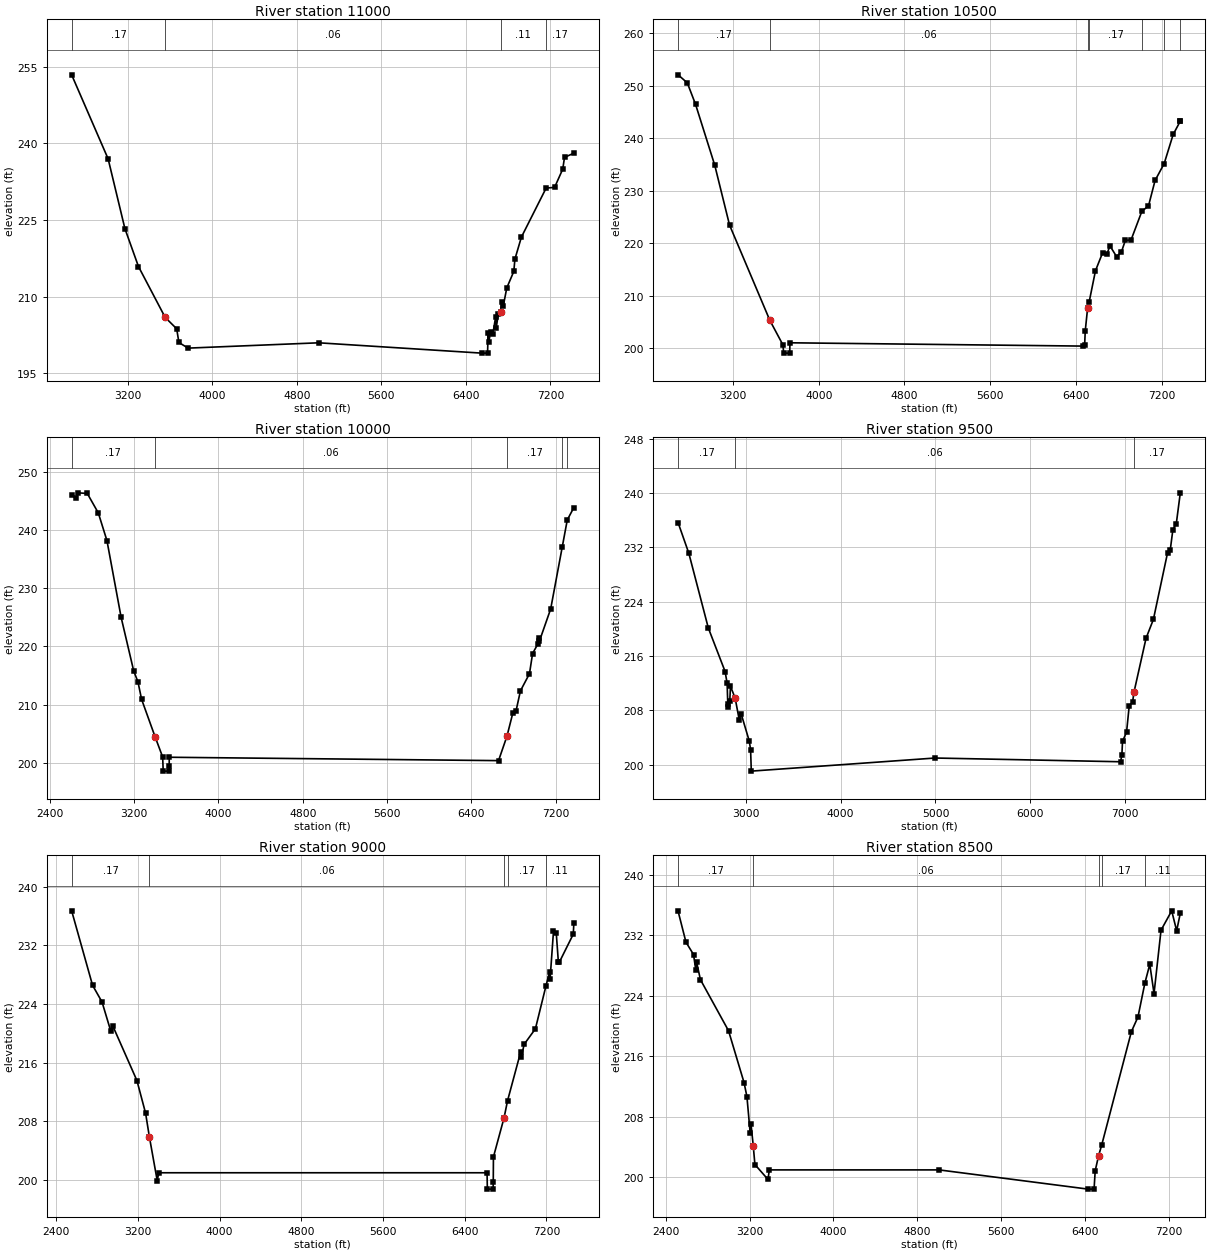
Type RM Length L Ch R = 1 ,11000   ,500,500,500
BEGIN DESCRIPTION:
CANEY CREEK NORTH 22.0
END DESCRIPTION:
XS GIS Cut Line= 3
      3780117.85     10163011.08      3778801.76     10161088.62
      3778112.75     10158766.48
#Sta/Elev= 30
  2670.2  253.43  3015.5  236.98  3173.9  223.36  3302.5  215.92  3554.9  205.98
    3664  203.74  3685.1  201.06  3771.8  199.96  5007.9     201  6550.1  198.98
  6605.8  198.98  6611.1  202.89  6616.4  201.12  6635.1  203.11    6656  202.75
  6682.8  206.13    6688  203.98  6708.1  206.69    6729   207.1  6739.4  208.99
  6754.5  208.21  6787.7  211.74  6854.1  214.97  6864.6  217.37  6925.8  221.67
  7159.9  231.27  7240.1  231.41  7317.3  234.99    7334  237.28  7422.2   238.1
#Mann= 4 ,-1 , 0
  2670.2     .17       0  3554.9     .06       0    6729     .11       0
  7159.9     .17       0
Bank Sta=3554.9,6729
XS Rating Curve= 0 ,0
Exp/Cntr=0.3,0.1

Type RM Length L Ch R = 1 ,10500   ,500,500,500
BEGIN DESCRIPTION:
CANEY CREEK NORTH 21.0
END DESCRIPTION:
XS GIS Cut Line= 3
      3780204.28      10162948.9      3779240.07     10160848.66
      3778190.43     10158721.54
#Sta/Elev= 30
    2689  252.04  2774.6  250.51  2851.7  246.41  3030.6  234.82  3168.5  223.43
  3544.9  205.25  3665.9  200.62  3673.9  199.03  3729.6  199.03  3731.9     201
  6463.1  200.37    6480  200.64  6485.6  203.27    6508  207.69  6522.8  208.86
    6581  214.73  6648.3  218.19  6687.6  217.88  6715.7  219.47  6777.4  217.42
  6822.3  218.27  6859.6  220.52  6912.2  220.56  7014.6   226.1  7074.9  227.03
  7136.7  231.92  7221.5  235.13  7305.6  240.69  7370.1  243.15    7372  243.15
#Mann= 7 ,-1 , 0
    2689     .17       0  3544.9     .06       0    6508     .11       0
  6522.8     .17       0  7014.6     .11       0  7221.5     .17       0
  7370.1     .11       0
Bank Sta=3544.9,6508
XS Rating Curve= 0 ,0
Exp/Cntr=0.3,0.1

Type RM Length L Ch R = 1 ,10000   ,500,500,500
BEGIN DESCRIPTION:
CANEY CREEK NORTH 20.0
END DESCRIPTION:
XS GIS Cut Line= 3
      3780308.46     10162914.19      3779677.26     10160606.04
      3778294.57      10158678.1
#Sta/Elev= 30
  2607.1  245.98  2651.8  245.38  2666.8  246.35  2755.5  246.24  2860.1   242.9
  2942.1  238.15  3076.9  224.97  3196.5  215.76  3236.2  213.94  3270.7  210.94
  3398.2  204.54  3470.8  201.04  3475.8  198.62  3531.5  198.62  3532.9  199.52
    3533     201    6658  200.42  6737.8  204.61  6794.3  208.64  6823.8  208.94
  6865.6  212.38  6951.5  215.33    6981  218.79  7031.4  220.44  7037.5  221.44
  7046.1  220.93  7152.9  226.45  7261.8     237  7310.3  241.71  7372.5  243.82
#Mann= 5 ,-1 , 0
  2607.1     .17       0  3398.2     .06       0  6737.8     .17       0
  7261.8     .11       0  7310.3     .17       0
Bank Sta=3398.2,6737.8
XS Rating Curve= 0 ,0
Exp/Cntr=0.3,0.1

Type RM Length L Ch R = 1 ,9500    ,500,500,500
BEGIN DESCRIPTION:
CANEY CREEK NORTH 19.0
END DESCRIPTION:
XS GIS Cut Line= 3
      3782067.86     10162411.08      3780146.79      10160496.8
      3778398.71     10158599.95
#Sta/Elev= 30
    2288  235.65  2401.1  231.14  2606.2  220.15    2783  213.74  2804.2  212.02
  2811.3  208.97  2818.3  208.58  2832.5  209.44  2839.5  211.57    2889  209.82
  2931.5  206.65  2952.7  207.48  3037.5  203.51  3051.7  202.22  3059.1  199.07
  4995.7     201  6949.6  200.45  6963.8  201.43  6970.6  203.46  7013.1  204.81
  7041.5  208.72  7076.6  209.21  7090.8  210.66  7218.4  218.63  7296.1  221.42
  7444.7  231.19    7473  231.58  7501.4  234.64  7537.1   235.5  7579.5  240.05
#Mann= 3 , 0 , 0
    2288     .17       0    2889     .06       0  7090.8     .17       0
Bank Sta=2889,7090.8
XS Rating Curve= 0 ,0
Exp/Cntr=0.3,0.1

Type RM Length L Ch R = 1 ,9000    ,500,500,500
BEGIN DESCRIPTION:
CANEY CREEK NORTH 18.0
END DESCRIPTION:
XS GIS Cut Line= 3
      3782137.46     10162369.27      3780624.26      10160443.7
      3779926.22     10158075.84
#Sta/Elev= 30
    2551  236.69  2755.6  226.55  2848.7  224.26  2933.7  220.32  2955.7  220.95
  3190.3  213.56  3275.3   209.1  3311.8  205.92  3389.2  199.91  3403.6     201
  6618.7     201  6621.8  198.77  6678.1  198.77  6679.6  199.77  6681.2  203.15
  6785.5   208.5  6819.3  210.81  6948.6  217.49  6953.8  216.73  6981.9   218.5
  7092.3  220.62  7195.6  226.46  7230.8  228.36    7236  227.41  7269.3   233.9
  7296.3  233.69  7317.2  229.69  7327.6  229.72  7463.1  233.51  7468.6  234.97
#Mann= 5 ,-1 , 0
    2551     .17       0  3311.8     .06       0  6785.5     .11       0
  6819.3     .17       0  7195.6     .11       0
Bank Sta=3311.8,6785.5
XS Rating Curve= 0 ,0
Exp/Cntr=0.3,0.1

Type RM Length L Ch R = 1 ,8500    ,500,500,500
BEGIN DESCRIPTION:
CANEY CREEK NORTH 17.0
END DESCRIPTION:
XS GIS Cut Line= 3
      3782191.51     10162326.98      3781020.97     10160139.36
      3780152.37     10157998.78
#Sta/Elev= 30
  2518.9  235.16  2593.7  231.08  2665.9  229.45  2687.8  227.38  2695.7  228.42
  2731.7  226.13  2999.9  219.38  3147.8  212.54  3175.4  210.68  3206.1  205.92
  3213.7  207.12  3235.6   204.2  3251.5  201.71  3376.2  199.74  3389.2     201
  5008.9     201    6431  198.46  6487.3  198.46  6498.2  200.89  6530.6  202.88
  6560.1  204.28  6843.6  219.27  6906.4  221.21  6972.1  225.68    7019  228.16
  7059.4  224.29  7126.1  232.66  7227.9  235.22  7275.3  232.59  7310.1  234.91
#Mann= 5 ,-1 , 0
  2518.9     .17       0  3235.6     .06       0  6530.6     .11       0
  6560.1     .17       0  6972.1     .11       0
Bank Sta=3235.6,6530.6
XS Rating Curve= 0 ,0
Exp/Cntr=0.3,0.1

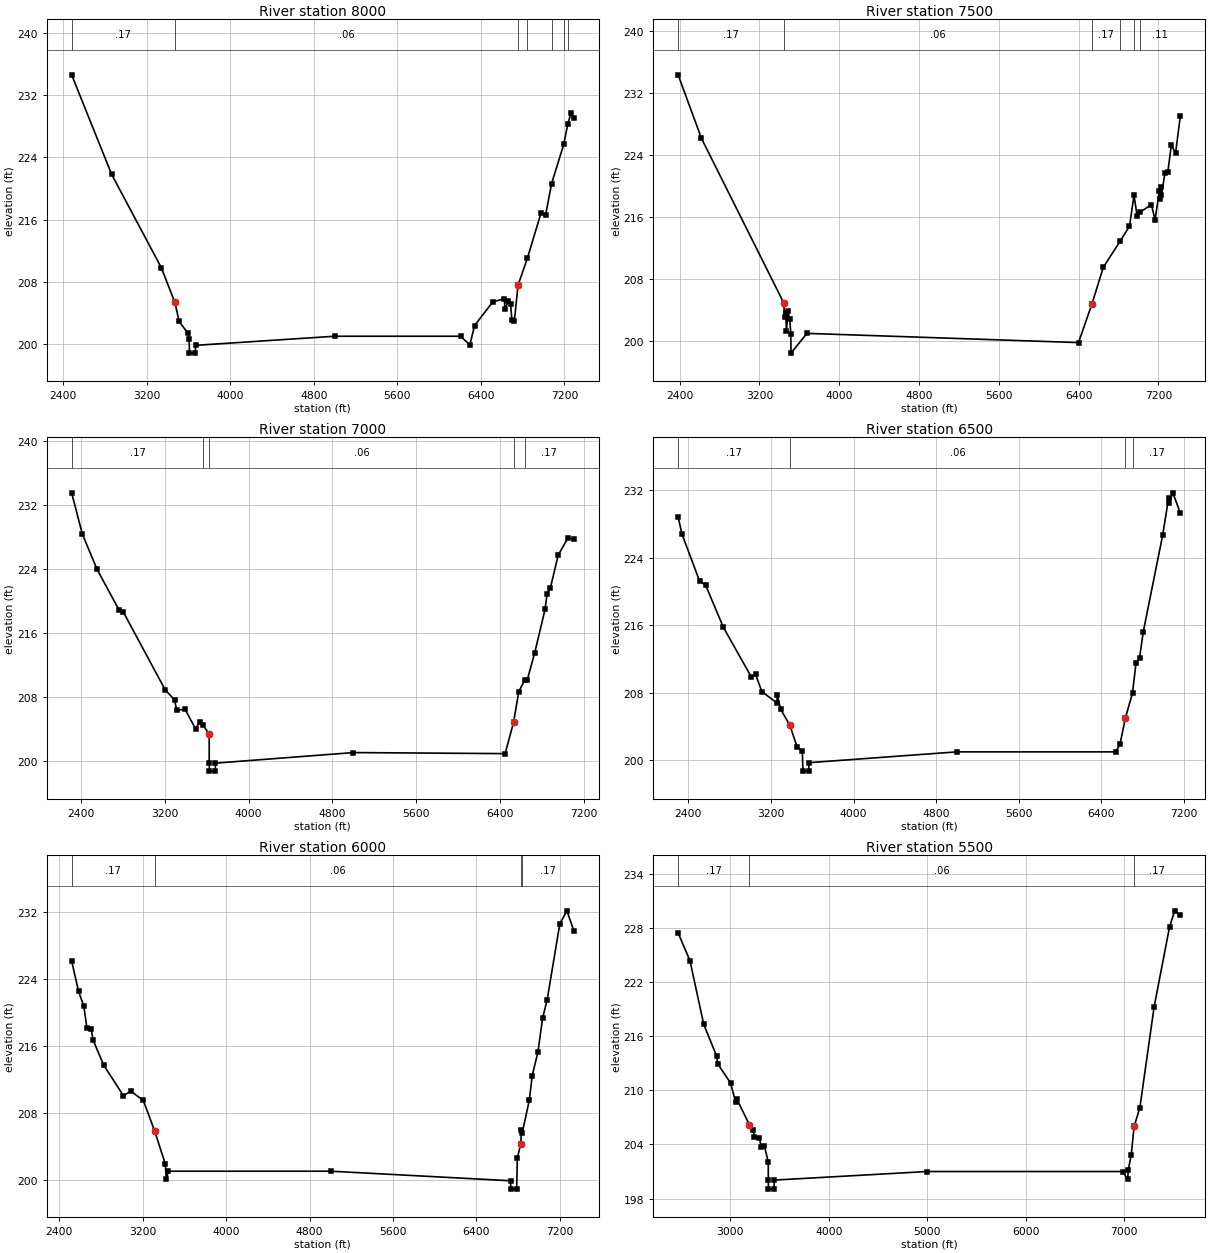
Type RM Length L Ch R = 1 ,8000    ,500,500,500
BEGIN DESCRIPTION:
CANEY CREEK NORTH 16.0
END DESCRIPTION:
XS GIS Cut Line= 3
      3782295.96      10162303.1      3781469.64     10159925.08
      3780334.15     10157936.76
#Sta/Elev= 30
  2482.5   234.6  2865.8  221.79    3341  209.81  3470.7  205.34  3511.5   202.9
  3596.2  201.37  3606.8  200.62  3610.4  198.83  3666.7  198.83  3668.2  199.83
  4999.5     201  6205.7     201  6294.4  199.88  6339.6  202.38  6513.2  205.41
  6624.7  205.83  6630.5  204.48  6662.2   205.5  6683.8  205.11  6697.4  203.07
  6720.5  202.96    6755  207.54  6845.4  211.05  6974.6   216.8  7019.9  216.63
  7076.9  220.62  7192.6  225.65  7231.9  228.28  7261.7  229.65  7289.7  229.01
#Mann= 7 ,-1 , 0
  2482.5     .17       0  3470.7     .06       0    6755     .17       0
  6845.4     .11       0  7076.9    .125       0  7192.6     .11       0
  7231.9    .125       0
Bank Sta=3470.7,6755
XS Rating Curve= 0 ,0
Exp/Cntr=0.3,0.1

Type RM Length L Ch R = 1 ,7500    ,500,500,500
BEGIN DESCRIPTION:
CANEY CREEK NORTH 15.0
END DESCRIPTION:
XS GIS Cut Line= 3
      3782361.63     10162315.14      3781932.12     10159735.04
      3780394.95     10157867.38
#Sta/Elev= 30
  2384.4  234.37  2618.6  226.16  3442.8  204.94    3453  203.05  3463.1  203.66
  3470.7  201.25  3483.4  203.87  3503.7  202.86  3513.8  200.95  3516.1  198.45
    3676     201  6398.4  199.81  6533.4  204.81  6647.3  209.54  6818.3  212.95
  6909.2  214.82  6954.6  218.81  6987.4  216.09  7015.2  216.64  7129.4  217.62
    7166  215.64  7207.6  219.34  7215.5   218.3    7222  219.88  7229.8  218.83
    7265  221.71  7293.7  221.85  7328.9  225.27  7371.9   224.3  7418.9  229.03
#Mann= 6 ,-1 , 0
  2384.4     .17       0  3442.8     .06       0  6533.4     .17       0
  6818.3     .11       0  6954.6    .125       0  7015.2     .11       0
Bank Sta=3442.8,6533.4
XS Rating Curve= 0 ,0
Exp/Cntr=0.3,0.1

Type RM Length L Ch R = 1 ,7000    ,500,500,500
BEGIN DESCRIPTION:
CANEY CREEK NORTH 14.0
END DESCRIPTION:
XS GIS Cut Line= 3
      3782470.54     10162302.08      3782408.39      10159615.9
      3782316.35     10157516.72
#Sta/Elev= 30
  2313.1  233.48  2414.1  228.36  2554.2  223.94  2764.2  218.85  2804.2  218.61
  3204.4  208.86  3294.4  207.58  3314.4  206.31  3394.4  206.41  3494.4  203.97
  3534.4  204.85  3566.5  204.39  3624.5  203.35  3624.8  199.68  3626.2  198.68
  3682.7  198.68  3684.2  199.68  4999.9     201  6446.2  200.87  6526.3  204.78
  6576.3  208.63  6633.7  210.08  6656.4  210.06    6728  213.47  6826.6   218.9
  6846.6  220.89  6876.6  221.53  6952.3   225.7  7046.8  227.87  7101.2  227.66
#Mann= 5 ,-1 , 0
  2313.1     .17       0  3566.5     .11       0  3624.5     .06       0
  6526.3     .11       0  6633.7     .17       0
Bank Sta=3624.5,6526.3
XS Rating Curve= 0 ,0
Exp/Cntr=0.3,0.1

Type RM Length L Ch R = 1 ,6500    ,500,500,500
BEGIN DESCRIPTION:
CANEY CREEK NORTH 13.0
END DESCRIPTION:
XS GIS Cut Line= 3
      3782621.58     10162307.27      3782908.35     10159622.64
      3782375.21     10157525.34
#Sta/Elev= 30
  2300.1  228.84  2336.5  226.83  2507.5  221.24  2567.8  220.71  2738.8  215.74
  3010.3  209.85  3050.5  210.17  3110.9  208.15  3255.1  206.81  3261.7   207.7
  3291.9  206.08  3382.4  204.14  3452.8  201.59  3503.1  201.08  3508.9  198.72
  3565.4  198.72  3566.9  199.72  4998.3     201    6539     201  6580.3  201.93
  6631.9  205.01    6701  207.97  6735.1  211.56  6769.4  212.13  6805.2  215.22
    6993  226.65  7050.8  231.07  7055.9  230.45  7091.7  231.68    7164  229.29
#Mann= 4 ,-1 , 0
  2300.1     .17       0  3382.4     .06       0  6631.9     .11       0
    6701     .17       0
Bank Sta=3382.4,6631.9
XS Rating Curve= 0 ,0
Exp/Cntr=0.3,0.1

Type RM Length L Ch R = 1 ,6000    ,500,500,500
BEGIN DESCRIPTION:
CANEY CREEK NORTH 12.0
END DESCRIPTION:
XS GIS Cut Line= 3
      3783506.75     10162107.53       3783408.3     10159629.38
      3782433.68     10157508.94
#Sta/Elev= 30
  2519.9  226.11  2586.4  222.47  2636.4  220.72  2666.5  218.08  2706.5  217.98
  2726.5  216.64  2826.6  213.68  3016.7  210.01  3086.8  210.57  3206.9  209.45
    3317  205.75  3417.1  201.89  3427.1  200.02  3447.1     201  5008.3     201
  6727.5  199.86    6729  198.86  6785.6  198.86  6792.1  202.56  6825.1   204.3
  6831.7  205.89  6839.6  205.61  6906.2  209.45  6935.1  212.43  6990.2  215.28
  7034.2  219.29  7078.2  221.49  7199.3  230.56  7267.3   232.1  7333.7  229.72
#Mann= 4 ,-1 , 0
  2519.9     .17       0    3317     .06       0  6825.1     .11       0
  6839.6     .17       0
Bank Sta=3317,6825.1
XS Rating Curve= 0 ,0
Exp/Cntr=0.3,0.1

Type RM Length L Ch R = 1 ,5500    ,500,500,500
BEGIN DESCRIPTION:
CANEY CREEK NORTH 11.0
END DESCRIPTION:
XS GIS Cut Line= 3
      3783645.63     10162150.94      3783908.26     10159636.12
      3782500.18     10157489.41
#Sta/Elev= 30
  2471.5  227.42    2592  224.34  2730.7  217.33  2863.5  213.75  2873.5  212.92
  3004.3  210.79  3054.5   208.7  3064.6  209.08  3195.3  206.17  3235.5  205.63
  3245.6  204.83  3295.8  204.68  3316.1  203.68  3346.1  203.85  3386.3  202.06
  3386.7  200.05  3388.2  199.05  3444.8  199.05  3446.2  200.05    5000     201
  6982.1     201  7033.4  200.15  7039.4  201.18  7069.6  202.87  7098.9     206
    7157  208.07  7301.7  219.25  7458.3  228.09  7509.6  229.87  7567.3  229.37
#Mann= 3 ,-1 , 0
  2471.5     .17       0  3195.3     .06       0  7098.9     .17       0
Bank Sta=3195.3,7098.9
XS Rating Curve= 0 ,0
Exp/Cntr=0.3,0.1

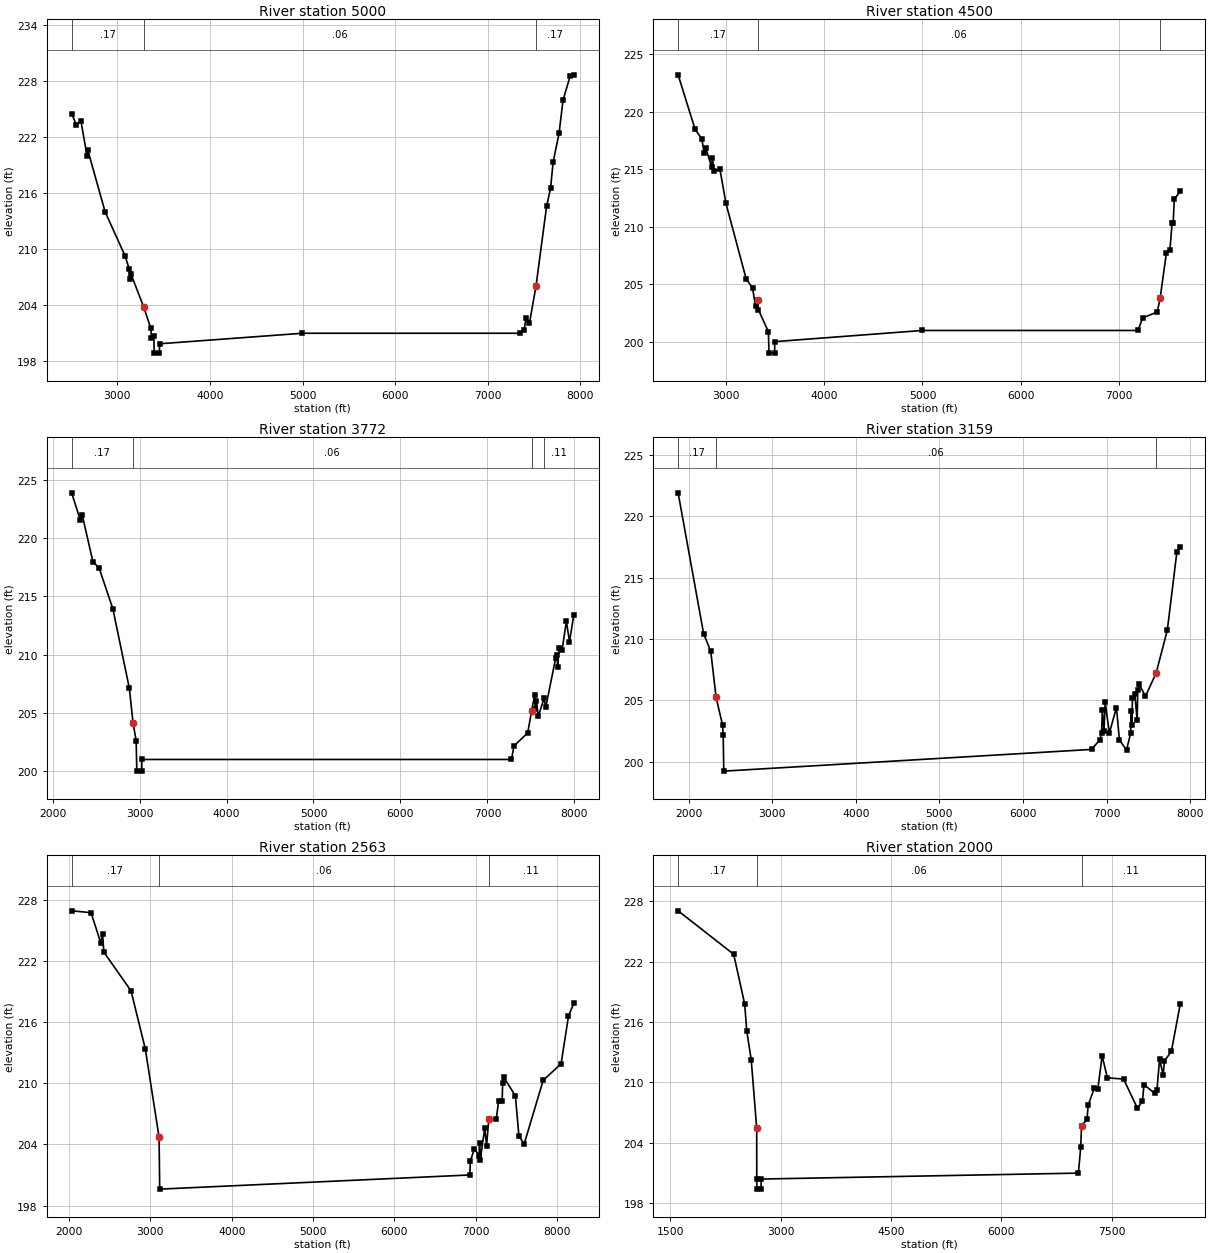
Type RM Length L Ch R = 1 ,5000    ,500,500,500
BEGIN DESCRIPTION:
CANEY CREEK NORTH 10.0
END DESCRIPTION:
XS GIS Cut Line= 3
      3783767.16     10162150.93      3784393.44     10159737.88
      3782569.24     10157446.04
#Sta/Elev= 30
    2507  224.55  2558.5  223.33  2607.1  223.77  2672.2  220.05  2682.5  220.59
  2868.4  214.01  3083.6   209.3  3129.3  207.86  3137.1  206.77  3147.4  207.35
  3286.4  203.78  3362.4  201.51  3367.6  200.52  3395.3  200.67    3398  198.87
  3454.7  198.87  3456.1  199.87  4998.8     201  7349.7     201  7392.9  201.39
  7413.7  202.67  7449.9  202.07  7521.1  206.08  7634.8  214.59    7678  216.54
  7705.5  219.35  7769.4  222.42  7812.6  225.99    7891  228.62  7929.2   228.7
#Mann= 3 , 0 , 0
    2507     .17       0  3286.4     .06       0  7521.1     .17       0
Bank Sta=3286.4,7521.1
XS Rating Curve= 0 ,0
Exp/Cntr=0.3,0.1

Type RM Length L Ch R = 1 ,4500    ,728,728,728
BEGIN DESCRIPTION:
CANEY CREEK NORTH 9.0
END DESCRIPTION:
XS GIS Cut Line= 3
      3783932.08     10162150.94      3784876.93     10159852.79
      3783795.33     10157464.71
#Sta/Elev= 30
  2515.2  223.23  2688.1  218.48  2756.1  217.67  2780.1  216.42  2796.2  216.87
  2857.4  215.18  2862.8  216.02  2881.3  214.84  2940.1  215.03  3001.6  212.05
    3207  205.49  3271.9   204.7  3302.6  203.11    3326  203.63  3331.9   202.8
  3433.2  200.89  3439.4  199.03  3496.4  199.03  3497.9  200.03  4998.2     201
  7191.7     201  7237.8  202.09  7387.4  202.61    7417  203.84  7479.8  207.73
  7515.8  207.97  7537.8  210.33  7548.8  210.31  7560.1   212.4  7621.6  213.12
#Mann= 3 , 0 , 0
  2515.2     .17       0    3326     .06       0    7417     .11       0
Bank Sta=3326,7417
XS Rating Curve= 0 ,0
Exp/Cntr=0.3,0.1

Type RM Length L Ch R = 1 ,3772    ,613,613,613
BEGIN DESCRIPTION:
CANEY CREEK NORTH 3.0
END DESCRIPTION:
XS GIS Cut Line= 3
      3784062.33     10162194.28      3785604.43     10159880.72
      3783863.48     10157445.78
#Sta/Elev= 30
  2219.6  223.88  2319.6  221.53  2342.2  221.94  2463.8  217.98  2535.9  217.42
  2693.7  213.92    2883  207.11  2925.1  204.16  2961.2   202.6  2968.7     200
  3025.7     200  3027.2     201  7276.1     201  7305.6  202.17  7462.9  203.28
  7507.1  205.13  7542.7  206.53  7548.9  205.29  7563.6  206.03  7584.5  204.69
  7650.5  206.25  7670.5  205.49    7786  209.75  7800.7  209.94  7806.9   208.9
  7821.6  210.53  7857.3  210.36  7907.6  212.85  7943.3  211.12  7993.3   213.4
#Mann= 4 ,-1 , 0
  2219.6     .17       0  2925.1     .06       0  7507.1    .125       0
  7650.5     .11       0
Bank Sta=2925.1,7507.1
XS Rating Curve= 0 ,0
Exp/Cntr=0.3,0.1

Type RM Length L Ch R = 1 ,3159    ,596,596,596
BEGIN DESCRIPTION:
CANEY CREEK NORTH 2.0
END DESCRIPTION:
XS GIS Cut Line= 3
      3784166.46     10162220.37       3786212.8     10159856.58
      3784295.26     10157704.94
#Sta/Elev= 30
  1873.5  221.91  2178.5  210.44    2264  208.99  2327.6  205.25  2405.5  202.97
  2413.1  202.16  2419.7  199.23  6820.5     201    6920  201.79  6940.9  202.37
  6948.4  204.23  6969.3   202.5  6983.5  204.84  7032.9  202.33  7118.1  204.41
  7153.2  201.79  7238.5  200.93  7287.9  202.33  7295.4  204.12  7302.1  202.95
  7309.6  205.21    7338  205.52  7365.6  203.36  7373.1  205.88  7387.3  206.35
  7465.1  205.33  7592.6  207.22  7726.8  210.72  7840.5  217.06  7882.1  217.52
#Mann= 3 ,-1 , 0
  1873.5     .17       0  2327.6     .06       0  7592.6     .11       0
Bank Sta=2327.6,7592.6
XS Rating Curve= 0 ,0
Exp/Cntr=0.3,0.1

Type RM Length L Ch R = 1 ,2563    ,563,563,563
BEGIN DESCRIPTION:
CANEY CREEK NORTH 1.0
END DESCRIPTION:
XS GIS Cut Line= 3
      3785627.08     10162450.38      3786792.97     10159719.77
      3784306.51      10157690.7
#Sta/Elev= 30
  2030.9  226.93  2269.4  226.75    2389  223.79  2410.7   224.7  2427.3  222.87
  2761.4  219.08  2937.5  213.36  3106.6  204.69  3114.2  199.61  6929.4     201
  6935.8  202.33  6985.4  203.58  7042.8  202.91  7049.3  204.11  7057.2  202.44
  7113.2   205.6  7135.5  203.88  7162.7  206.45  7255.4   206.5  7284.1  208.29
  7327.2  208.26  7333.6  210.02    7348  210.58  7490.1  208.77  7533.2  204.87
  7597.1  204.01  7831.9  210.29  8052.3  211.91  8143.5  216.59  8209.3  217.88
#Mann= 3 ,-1 , 0
  2030.9     .17       0  3106.6     .06       0  7162.7     .11       0
Bank Sta=3106.6,7162.7
XS Rating Curve= 0 ,0
Exp/Cntr=0.3,0.1

Type RM Length L Ch R = 1 ,2000    ,500,500,500
BEGIN DESCRIPTION:
CANEY CREEK NORTH 4.0
END DESCRIPTION:
XS GIS Cut Line= 3
      3785719.23     10162450.41        3787271.     10159433.61
       3784326.1     10157675.48
#Sta/Elev= 30
  1607.5  227.03  2362.3  222.72  2511.9  217.78  2540.1  215.09  2600.6  212.26
  2675.1  205.46  2675.8  200.41  2677.3  199.41  2734.3  199.41  2735.8  200.41
  7045.6     201  7076.8  203.56  7088.4   205.7  7162.4  206.33  7177.9  207.72
  7263.5  209.48  7309.7  209.37  7367.9  212.63  7438.7  210.46  7659.1  210.33
  7847.3  207.44  7915.3  208.13  7936.9  209.79  8080.8  208.91    8112   209.2
  8148.2  212.31  8197.6  210.71  8213.2  212.11  8308.5  213.08  8429.8  217.81
#Mann= 3 , 0 , 0
  1607.5     .17       0  2675.1     .06       0  7088.4     .11       0
Bank Sta=2675.1,7088.4
XS Rating Curve= 0 ,0
Exp/Cntr=0.3,0.1