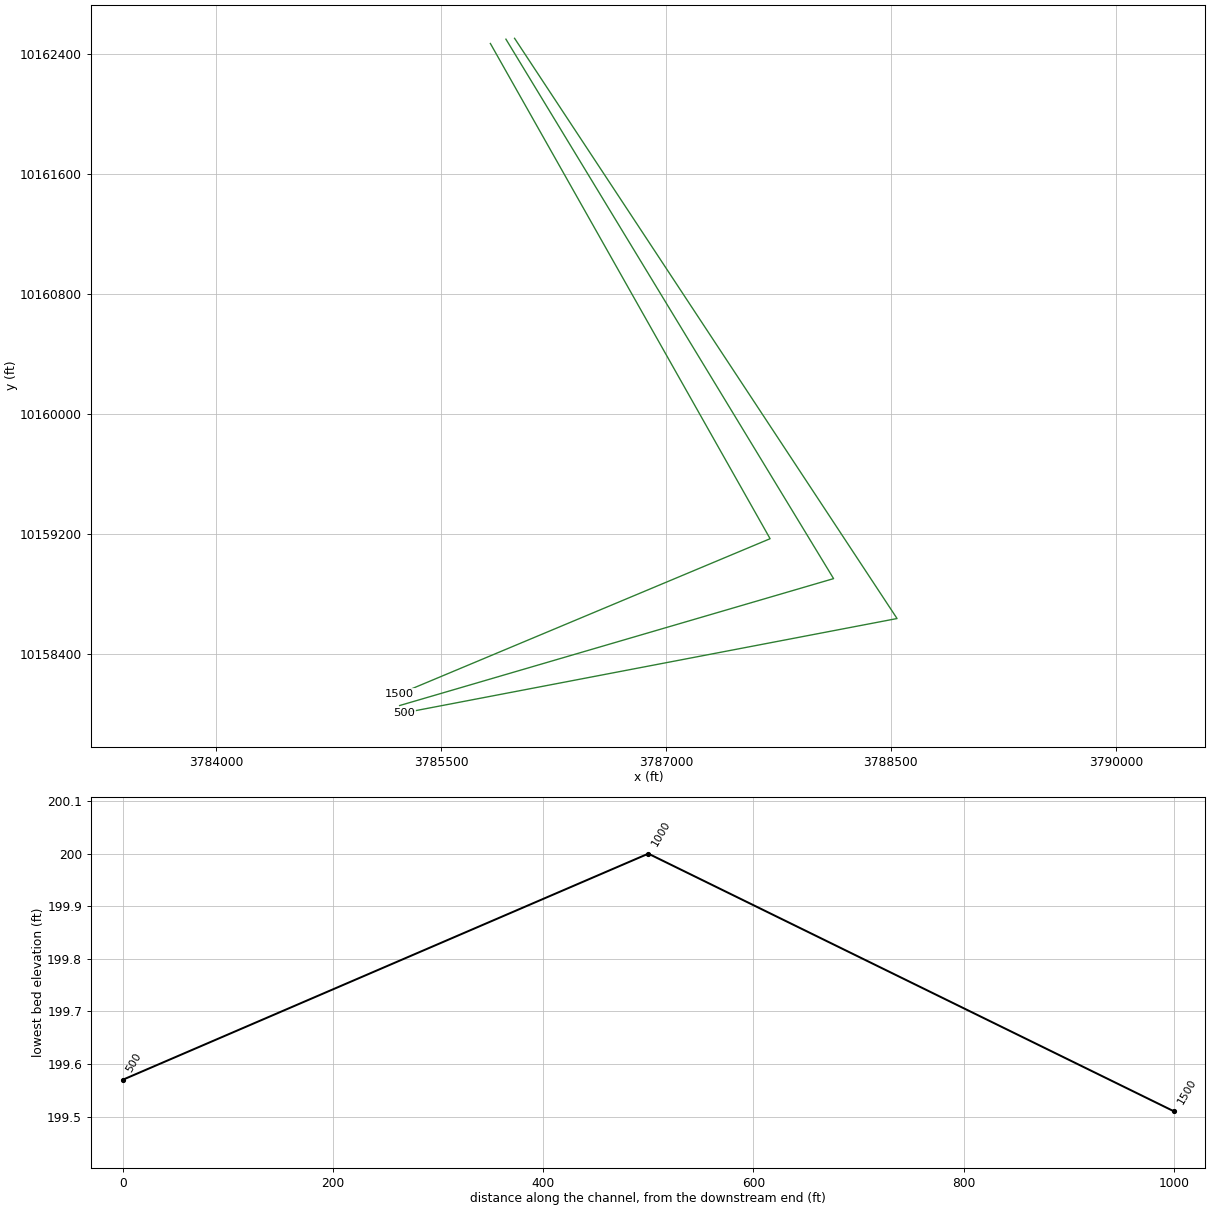
HEC-RAS study CANEY CREEK NORTH.prj: CANEY CREEK NORTH Base Level Engineering

--- CANEY CREEK NORTH.g01 (geometry) --- (continued)

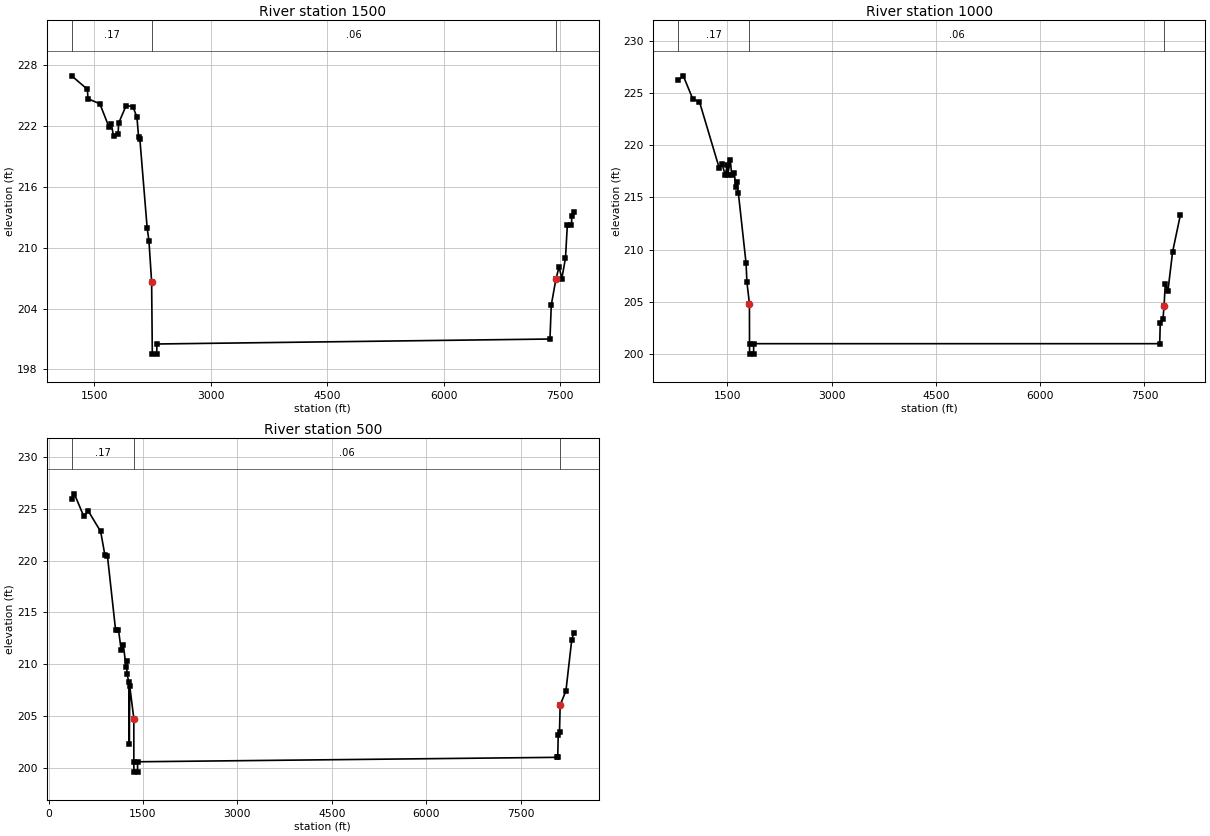
Type RM Length L Ch R = 1 ,1500    ,500,500,500
BEGIN DESCRIPTION:
CANEY CREEK NORTH 3.5
END DESCRIPTION:
XS GIS Cut Line= 3
      3785828.65     10162467.75      3787694.39     10159167.64
      3785224.17     10158134.15
#Sta/Elev= 30
    1209  226.96    1412  225.63  1419.2   224.7  1572.8   224.2  1689.1  221.92
  1720.9  222.19  1748.3     221  1807.5  221.18    1814  222.28    1910  224.02
  1997.8  223.93  2050.1  222.87  2071.7   220.9  2087.6  220.73  2181.6  211.95
  2204.6  210.69  2239.1  206.64  2248.1  199.51  2305.2  199.51  2306.7  200.51
  7370.2     201  7387.1  204.35  7446.1  206.88  7487.7  208.14  7522.3  206.95
  7569.9  208.96  7593.7  212.23  7646.7   212.2  7652.1  213.14  7677.7  213.56
#Mann= 3 , 0 , 0
    1209     .17       0  2239.1     .06       0  7446.1     .11       0
Bank Sta=2239.1,7446.1
XS Rating Curve= 0 ,0
Exp/Cntr=0.3,0.1

Type RM Length L Ch R = 1 ,1000    ,500,500,500
BEGIN DESCRIPTION:
CANEY CREEK NORTH 2.5
END DESCRIPTION:
XS GIS Cut Line= 3
      3785932.37      10162496.5      3788117.78     10158901.66
      3785223.52     10158055.92
#Sta/Elev= 30
     793  226.19   867.3  226.63  1004.9   224.4  1099.9  224.15  1384.5   217.8
  1427.3  218.15    1470  217.13  1500.9  218.09  1506.8  217.16  1543.6  218.53
  1564.9  217.11  1601.7   217.3    1623  215.97  1638.5  216.44  1659.9  215.39
  1770.3  208.68  1782.4  206.89  1818.8  204.81  1819.7     201  1821.2     200
  1878.3     200  1879.8     201  7719.1     201  7726.9  202.99  7765.6  203.32
  7781.6  204.59    7799  206.75  7837.7  206.07  7904.6  209.79  8015.3  213.29
#Mann= 3 , 0 , 0
     793     .17       0  1818.8     .06       0  7781.6     .11       0
Bank Sta=1818.8,7781.6
XS Rating Curve= 0 ,0
Exp/Cntr=0.3,0.1

Type RM Length L Ch R = 1 ,500     ,0,0,0
BEGIN DESCRIPTION:
CANEY CREEK NORTH 1.5
END DESCRIPTION:
XS GIS Cut Line= 3
      3785989.97     10162502.28      3788541.17     10158635.69
      3785254.26     10158007.49
#Sta/Elev= 30
   367.6  225.97   410.1  226.46   560.7  224.28   632.8  224.79   828.5  222.82
   894.8  220.57   936.9  220.42  1066.4  213.26  1111.6  213.34  1153.7   211.4
  1189.8  211.84  1231.9  209.71    1241  210.32    1247  209.02  1277.2  208.26
  1283.1  202.31  1291.5  207.85  1355.4  204.73  1355.5  200.57    1357  199.57
  1414.1  199.57  1415.6  200.57  8085.4     201  8090.4  201.04  8098.4  203.16
  8118.8  203.49  8128.9  206.05  8220.6  207.42  8312.2  212.31  8346.4  213.05
#Mann= 3 , 0 , 0
   367.6     .17       0  1355.4     .06       0  8128.9     .11       0
Bank Sta=1355.4,8128.9
XS Rating Curve= 0 ,0
Exp/Cntr=0.3,0.1

Chan Stop Cuts=-1
Use User Specified Reach Order=0
Composite Channel Slope=5