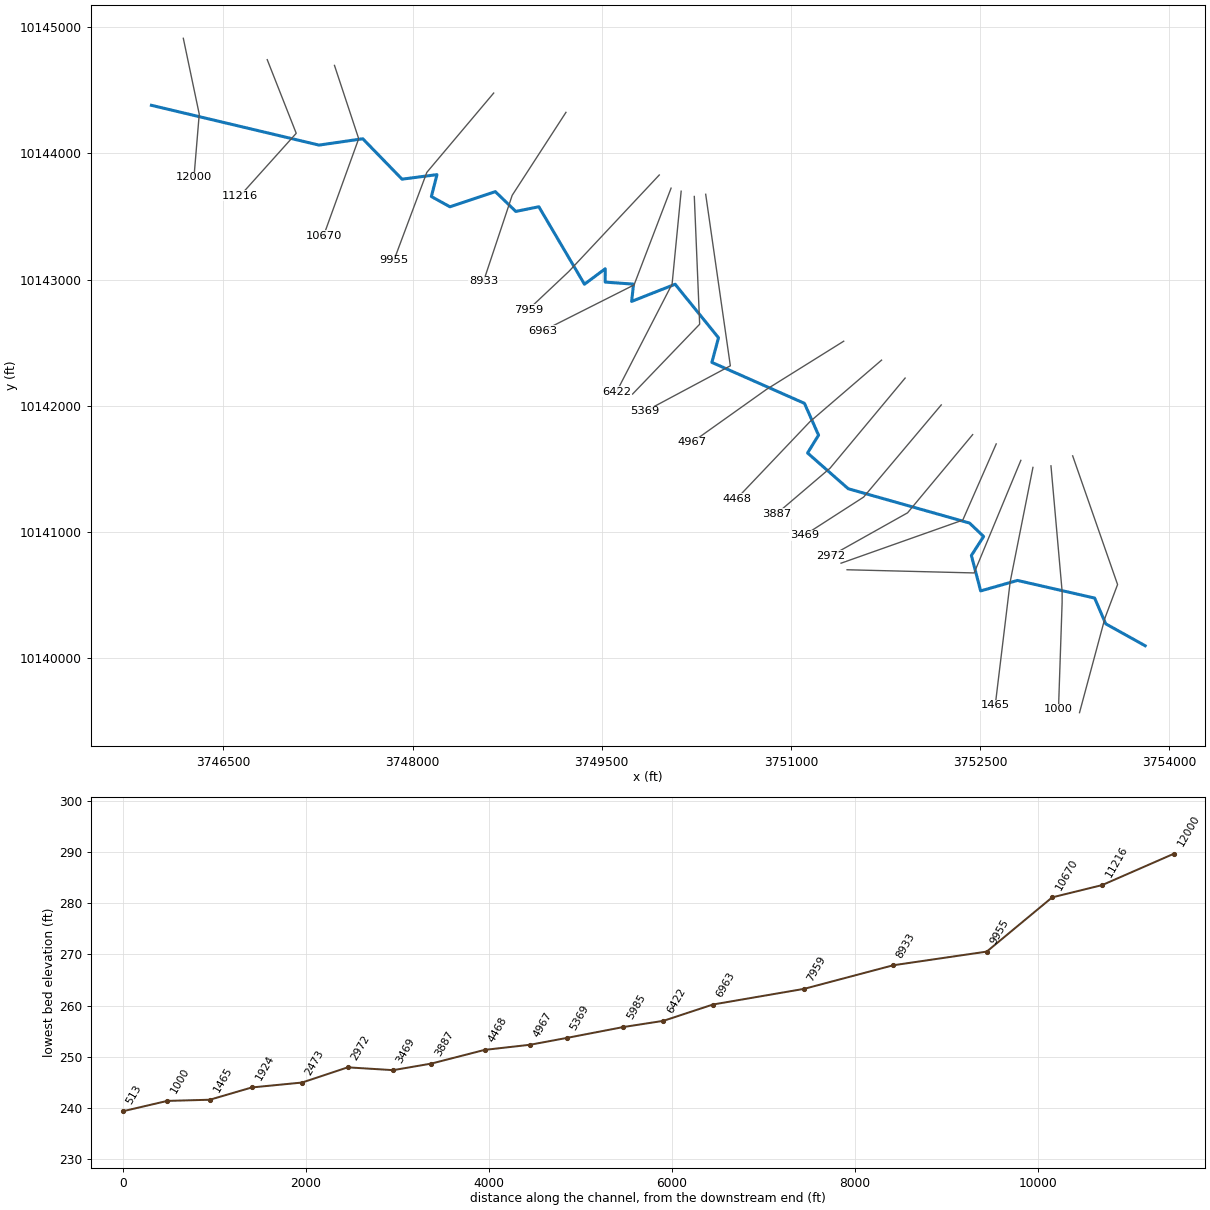
--- CARWILE CREEK.prj (project) ---

Proj Title=CARWILE CREEK Base Level Engineering
Current Plan=p01
Default Exp/Contr=0.3,0.1
English Units
Geom File=g01
Flow File=f01
Flow File=f02
Plan File=p01
Y Axis Title=Elevation
X Axis Title(PF)=Main Channel Distance
X Axis Title(XS)=Station
BEGIN DESCRIPTION:
CARWILE CREEK
END DESCRIPTION:
DSS File=dss
DSS Export Rating Curves= 0
DSS Export Rating Curve Sorted= 0
DSS Export Volume Flow Curves= 0
DXF OffsetX= 0
DXF OffsetY= 0
DXF ScaleX= 1
DXF ScaleY= 10

--- CARWILE CREEK.p01 (plan) ---

Plan Title=Multiple Run
Program Version=4.10
Short Identifier=Multiple Run
Geom File=g01
Flow File=f01
Subcritical Flow
K Sum by GR= 0
Std Step Tol= 0.01
Critical Tol= 0.01
Num of Std Step Trials= 20
Max Error Tol= 0.3
Flow Tol Ratio= 0.001
Split Flow NTrial= 30
Split Flow Tol= 0.02
Split Flow Ratio= 0.02
Log Output Level= 0
Friction Slope Method= 1
Unsteady Friction Slope Method= 2
Unsteady Bridges Friction Slope Method= 1
Parabolic Critical Depth
Global Vel Dist= 1 , 1 , 1
Global Log Level= 0
CheckData=True
Encroach Param=-1 ,0,0, 0
BEGIN DESCRIPTION:
Multiple Run
END DESCRIPTION:
Computation Interval=1HOUR
Output Interval=1HOUR
Run HTab= 0
Run UNet= 0
Run PostProcess= 0
Run WQNet= 0
UNET Theta= 1
UNET Theta Warmup= 1
UNET ZTol= 0.02
UNET ZSATol= 0.05
UNET MxIter= 20
UNET MaxInSteps= 0
UNET DtIC= 0
UNET DtMin= 0
UNET MaxCRTS= 20
UNET WFStab= 2
UNET SFStab= 1
UNET WFX= 1
UNET SFX= 1
UNET DSS MLevel= 4
UNET DZMax Abort= 100
UNET Convert EG Bridges= 0
UNET Use Existing IB Tables=-1
UNET Froude Reduction=False
UNET Froude Limit= 1
UNET Froude Power= 10
UNET Time Slicing=0,0, 5
UNET Junction Losses=0
Instantaneous Interval=1HOUR
DSS File=dss
Write IC File= 0
Write IC File at Sim End=0
Echo Input=False
Echo Parameters=False
Echo Output=False
Write Detailed= 0
WQ AD Non Conservative
WQ ULTIMATE=-1
WQ Max Comp Step=1HOUR
WQ Output Interval=15MIN
WQ Output Selected Increments= 0
WQ Output face flow=0
WQ Output face velocity=0
WQ Output face area=0
WQ Output face dispersion=0
WQ Output cell volume=0
WQ Output cell surface area=0
WQ Output cell continuity=0
WQ Output cumulative cell continuity=0
WQ Output face conc=0
WQ Output face dconc_dx=0
WQ Output face courant=0
WQ Output face peclet=0
WQ Output face adv mass=0
WQ Output face disp mass=0
WQ Output cell mass=0
WQ Output cell source sink temp=0
WQ Output cell source sink nsm=0
WQ Output MaxMinRange=-1
WQ Daily Max Min Mean=-1
WQ Daily Range=0
WQ Daily Time=0
WQ Create Restart=0
WQ Fixed Restart=0
WQ System Summary=0
WQ Use Fixed Temperature=0
Sorting and Armoring Iterations= 10
XS Update Threshold= 0.02
Hydraulics Update Threshold= 0.02
Energy Slope Method= 1
Volume Change Method= 0
XS Weighting Method= 0
Number of US Weighted Cross Sections= 1
Number of DS Weighted Cross Sections= 1
Upstream XS Weight=0.25
Main XS Weight=0.5
Downstream XS Weight=0.25
Number of DS XS's Weighted with US Boundary= 1
Upstream Boundary Weight= 1
Weight of XSs Associated with US Boundary= 0
Number of US XS's Weighted with DS Boundary= 1
Downstream Boundary Weight= 0.5
Weight of XSs Associated with DS Boundary= 0.5
Sediment Output Level= 4
Mass or Volume Output= 0
Output Increment Type= 1
Profile and TS Output Increment= 10
XS Output Flag= 0
XS Output Increment= 10
Disregard all LS=0
Disregard all Conn=0
Disregard all Breaches=0
Disregard all Pumps=0

--- CARWILE CREEK.f01 (steady flow) ---

Flow Title=Multiple
Program Version=4.10
Number of Profiles= 7
Profile Names=10-year,25-year,50-year,1pct_min,100-year,1pct_plu,500-year
River Rch & RM=CARWILE CREEK,Reach-1         ,12000
     269     347     453     196     593    1791    1042
River Rch & RM=CARWILE CREEK,Reach-1         ,11216
     719     985    1342     602    1817    5487    3445
River Rch & RM=CARWILE CREEK,Reach-1         ,7959
     660     890    1201     532    1606    4850    2970
River Rch & RM=CARWILE CREEK,Reach-1         ,4967
    1089    1516    2086     943    2847    8598    5483
River Rch & RM=CARWILE CREEK,Reach-1         ,1465
    1592    2245    3117    1418    4281   12928    8363
River Rch & RM=CARWILE CREEK,Reach-1         ,1000
    1592    2245    3117    1418    4281   12928    8363
River Rch & RM=CARWILE CREEK,Reach-1         ,513
    1592    2245    3117    1418    4281   12928    8363
Boundary for River Rch & Prof#=CARWILE CREEK,Reach-1         , 1
Up Type= 0
Dn Type= 3
Dn Slope=0.006
Boundary for River Rch & Prof#=CARWILE CREEK,Reach-1         , 2
Up Type= 0
Dn Type= 3
Dn Slope=0.006
Boundary for River Rch & Prof#=CARWILE CREEK,Reach-1         , 3
Up Type= 0
Dn Type= 3
Dn Slope=0.006
Boundary for River Rch & Prof#=CARWILE CREEK,Reach-1         , 4
Up Type= 0
Dn Type= 3
Dn Slope=0.006
Boundary for River Rch & Prof#=CARWILE CREEK,Reach-1         , 5
Up Type= 0
Dn Type= 3
Dn Slope=0.006
Boundary for River Rch & Prof#=CARWILE CREEK,Reach-1         , 6
Up Type= 0
Dn Type= 3
Dn Slope=0.006
Boundary for River Rch & Prof#=CARWILE CREEK,Reach-1         , 7
Up Type= 0
Dn Type= 3
Dn Slope=0.006
DSS Import GetInterval= 0
DSS Import GetPeak= 0
DSS Import FillOption= 0

--- CARWILE CREEK.f02 (steady flow) ---

Flow Title=Orig_BLE_Flow
Program Version=4.10
Number of Profiles= 7
Profile Names=10-year,25-year,50-year,1pct_min,100-year,1pct_plu,500-year
River Rch & RM=CARWILE CREEK,Reach-1         ,12000
     269     340     394     151     456    1376     606
River Rch & RM=CARWILE CREEK,Reach-1         ,11216
     719     966    1167     463    1398    4223    2003
River Rch & RM=CARWILE CREEK,Reach-1         ,7959
     660     873    1044     409    1235    3729    1727
River Rch & RM=CARWILE CREEK,Reach-1         ,4967
    1089    1486    1814     725    2190    6613    3188
River Rch & RM=CARWILE CREEK,Reach-1         ,1465
    1592    2201    2710    1090    3293    9943    4862
River Rch & RM=CARWILE CREEK,Reach-1         ,1000
    1592    2201    2710    1090    3293    9943    4862
River Rch & RM=CARWILE CREEK,Reach-1         ,513
    1592    2201    2710    1090    3293    9943    4862
Boundary for River Rch & Prof#=CARWILE CREEK,Reach-1         , 1
Up Type= 0
Dn Type= 3
Dn Slope=0.01
Boundary for River Rch & Prof#=CARWILE CREEK,Reach-1         , 2
Up Type= 0
Dn Type= 3
Dn Slope=0.01
Boundary for River Rch & Prof#=CARWILE CREEK,Reach-1         , 3
Up Type= 0
Dn Type= 3
Dn Slope=0.01
Boundary for River Rch & Prof#=CARWILE CREEK,Reach-1         , 4
Up Type= 0
Dn Type= 3
Dn Slope=0.01
Boundary for River Rch & Prof#=CARWILE CREEK,Reach-1         , 5
Up Type= 0
Dn Type= 3
Dn Slope=0.01
Boundary for River Rch & Prof#=CARWILE CREEK,Reach-1         , 6
Up Type= 0
Dn Type= 3
Dn Slope=0.01
Boundary for River Rch & Prof#=CARWILE CREEK,Reach-1         , 7
Up Type= 0
Dn Type= 3
Dn Slope=0.01
DSS Import GetInterval= 0
DSS Import GetPeak= 0
DSS Import FillOption= 0

--- CARWILE CREEK.g01 (geometry) ---

Geom Title=Existing Conditions
Program Version=4.10

River Reach=CARWILE CREEK   ,Reach-1
Reach XY= 30
      3745930.47     10144380.68      3747258.97      10144065.3
      3747605.73     10144115.55      3747917.11     10143795.23
      3748193.96     10143831.21      3748149.45     10143657.52
      3748296.83     10143576.34      3748656.28     10143696.49
      3748818.56     10143539.58      3749001.54     10143576.56
      3749362.86      10142962.7       3749527.6     10143085.15
      3749527.11     10142979.48       3749752.1     10142963.39
      3749736.85     10142826.52      3750081.62     10142962.48
      3750425.46      10142538.4      3750372.86     10142343.19
       3751106.8     10142018.51      3751218.53     10141766.41
      3751131.27     10141625.23      3751453.81     10141341.77
      3752415.21     10141069.95      3752526.78     10140963.66
      3752429.79     10140812.78       3752503.4     10140531.93
      3752794.95     10140615.03      3753406.75     10140475.25
      3753494.58     10140271.34      3753807.31     10140097.47

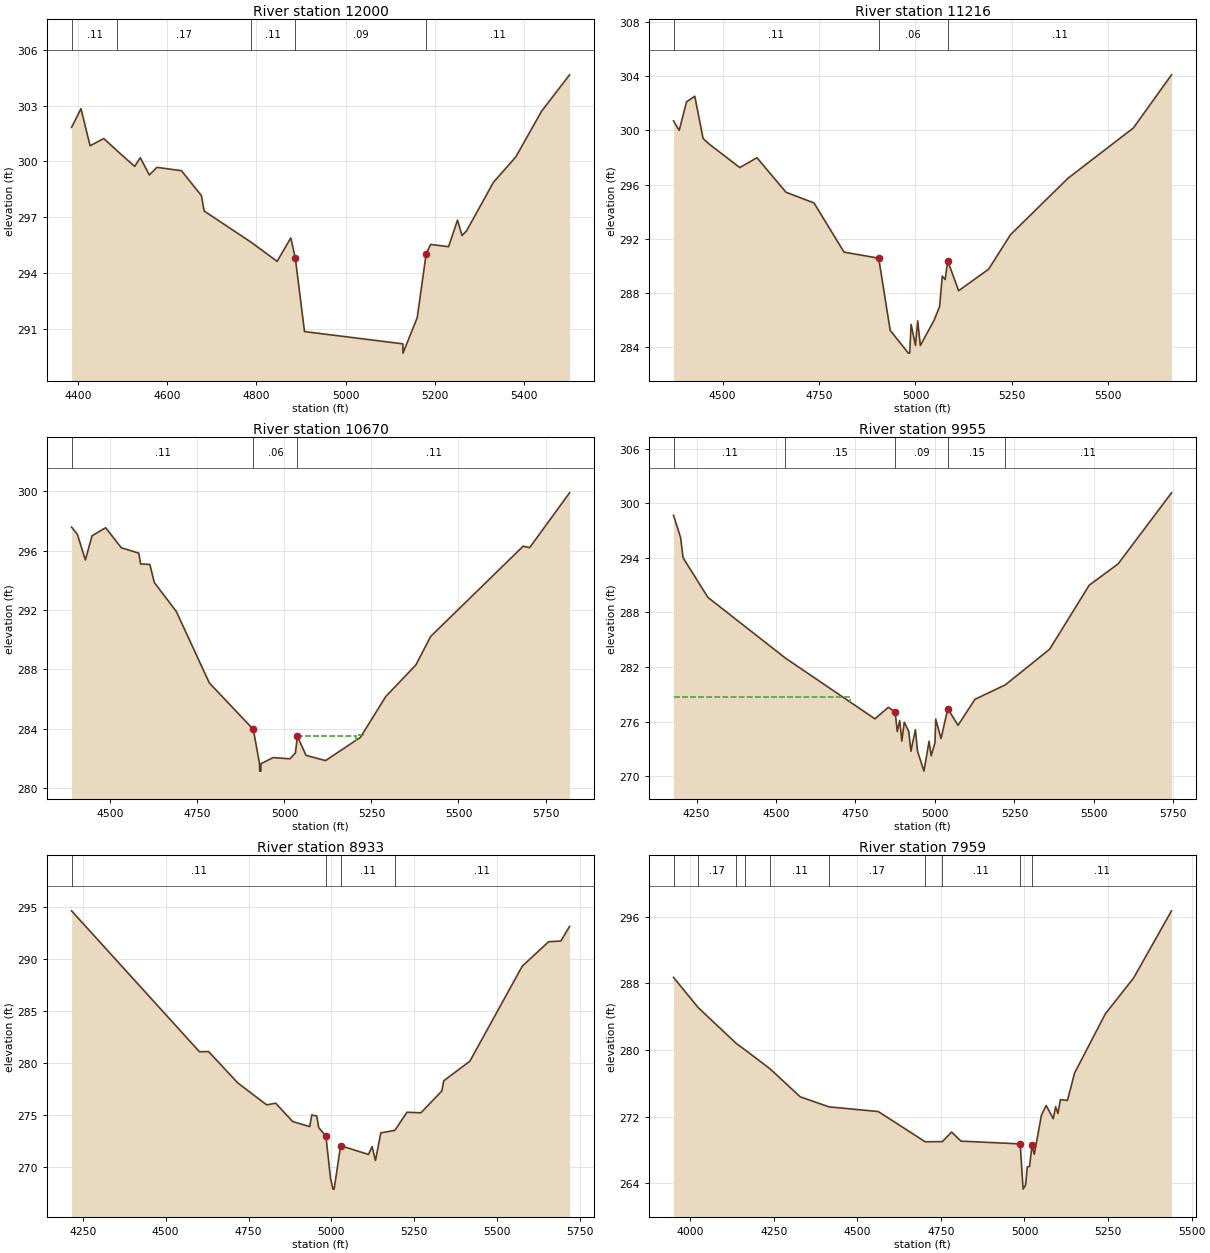
Type RM Length L Ch R = 1 ,12000   ,784,784,784
BEGIN DESCRIPTION:
CARWILE CREEK 24.0
END DESCRIPTION:
XS GIS Cut Line= 3
      3746183.26      10144911.7      3746309.52     10144310.72
      3746267.85     10143811.05
#Sta/Elev= 30
  4385.9  301.83    4407  302.84  4427.4  300.84  4458.1  301.23  4488.5  300.56
  4527.2  299.73  4539.8   300.2  4560.2  299.27    4577  299.68    4632   299.5
  4676.8  298.16  4682.9  297.33  4787.4  295.66  4846.4  294.62    4877  295.88
  4887.2  294.78  4907.7  290.84  5128.1  290.18  5128.3  289.68  5160.2  291.59
  5180.3  295.04  5190.3  295.53  5230.4  295.41  5250.5  296.84  5260.5  296.01
  5270.6  296.26  5330.8  298.87    5381  300.24  5438.7   302.7  5501.4  304.66
#Mann= 5 ,-1 , 0
  4385.9     .11       0  4488.5     .17       0  4787.4     .11       0
  4887.2     .09       0  5180.3     .11       0
Bank Sta=4887.2,5180.3
XS Rating Curve= 0 ,0
Exp/Cntr=0.3,0.1

Type RM Length L Ch R = 1 ,11216   ,546,546,546
BEGIN DESCRIPTION:
CARWILE CREEK 18.0
END DESCRIPTION:
XS GIS Cut Line= 3
      3746848.45     10144742.32      3747078.27     10144158.75
       3746634.6       10143665.
#Sta/Elev= 30
  4372.8   300.7  4387.5     300  4406.4   302.1  4427.9  302.52  4449.4   299.4
  4466.1  298.97  4544.6  297.25  4589.1  297.98  4664.3  295.43  4736.9  294.64
  4814.8  291.01  4904.7  290.56  4934.5  285.23  4981.6  283.55  4985.1  283.55
  4988.7  285.67    5000  284.12  5005.9  285.93  5012.6  284.11  5048.5  285.99
  5062.7  287.01  5069.4  289.24  5076.9  288.98  5083.6  290.36    5112  288.16
  5189.7  289.75  5246.5   292.3  5395.3  296.46    5565  300.18  5663.8   304.1
#Mann= 3 ,-1 , 0
  4372.8     .11       0  4904.7     .06       0  5083.6     .11       0
#XS Ineff= 2 , 0
       0                  5083.6       0  290.36
Permanent Ineff=
       F       F
Bank Sta=4904.7,5083.6
XS Rating Curve= 0 ,0
Exp/Cntr=0.3,0.1

Type RM Length L Ch R = 1 ,10670   ,715,715,715
BEGIN DESCRIPTION:
CARWILE CREEK 17.0
END DESCRIPTION:
XS GIS Cut Line= 3
      3747381.44     10144696.87      3747573.36     10144116.16
      3747294.74      10143345.9
#Sta/Elev= 30
  4388.4  297.58    4405   297.1  4428.1  295.37  4447.2     297  4486.3  297.54
  4531.4  296.19  4581.5  295.83  4586.7   295.1  4613.2  295.07  4626.2  293.85
  4689.4   291.9  4784.2  287.09  4910.6  283.96  4928.5  281.65  4928.8  281.15
  4932.3  281.15  4932.5  281.65  4967.5  282.06    5016  281.98  5031.4  282.37
  5037.3  283.49  5062.1  282.21  5118.1  281.86  5218.1  283.42  5291.3  286.18
  5377.6   288.3  5420.1  290.22    5686   296.3  5704.5   296.2  5819.1  299.89
#Mann= 3 , 0 , 0
  4388.4     .11       0  4910.6     .06       0  5037.3     .11       0
#XS Ineff= 2 ,-1
  5037.3  5204.7  283.49  5204.7  5235.4  283.59
Permanent Ineff=
       T       F
Bank Sta=4910.6,5037.3
XS Rating Curve= 0 ,0
Exp/Cntr=0.3,0.1

Type RM Length L Ch R = 1 ,9955    ,1022,1022,1022
BEGIN DESCRIPTION:
CARWILE CREEK 15.0
END DESCRIPTION:
XS GIS Cut Line= 3
      3748643.36     10144477.66      3748113.37     10143848.94
      3747852.67     10143152.11
#Sta/Elev= 30
  4177.7  298.69    4200  296.23  4207.7  294.02  4285.8  289.66  4529.7  282.98
  4811.1   276.3  4853.3  277.57  4874.8  277.05  4881.4   274.9  4889.1  276.12
  4895.7  273.85  4903.4  275.93  4917.7   274.9  4924.3  272.74  4938.5  275.11
  4945.1  272.74  4965.4  270.55  4981.4  273.84    4988  272.24    5000  273.67
  5002.3  276.27  5019.1  274.14  5040.4  277.41  5072.5  275.59  5125.8  278.45
  5221.3  280.04  5360.7  283.96  5485.1     291  5575.9  293.34    5744  301.16
#Mann= 5 ,-1 , 0
  4177.7     .11       0  4529.7     .15       0  4874.8     .09       0
  5040.4     .15       0  5221.3     .11       0
#XS Ineff= 2 , 0
       0  4733.1  278.66               0
Permanent Ineff=
       F       F
Bank Sta=4874.8,5040.4
XS Rating Curve= 0 ,0
Exp/Cntr=0.3,0.1

Type RM Length L Ch R = 1 ,8933    ,974,974,974
BEGIN DESCRIPTION:
CARWILE CREEK 13.0
END DESCRIPTION:
XS GIS Cut Line= 3
      3749216.25     10144324.85      3748790.03     10143667.18
      3748562.95     10142985.82
#Sta/Elev= 30
  4216.3   294.6  4602.1  281.07  4629.5  281.09  4717.2  278.09  4804.7  275.97
  4831.9  276.13  4883.3  274.37  4934.7  273.88  4940.7     275  4955.8   274.9
  4961.8  273.78  4983.4  272.97  4997.4   268.9  5004.7  267.88  5008.2  267.88
  5027.7  272.05  5111.8  271.21  5122.6  271.97  5132.9  270.63    5149  273.28
  5191.2  273.52  5227.8  275.26    5270  275.21  5333.2  277.31  5338.7  278.28
  5417.5  280.16  5575.6  289.29    5655  291.63  5691.9   291.7  5718.2   293.1
#Mann= 4 ,-1 , 0
  4216.3     .11       0  4983.4     .06       0  5027.7     .11       0
  5191.2     .11       0
#XS Ineff= 2 , 0
       0  4955.8   274.9               0
Permanent Ineff=
       F       F
Bank Sta=4983.4,5027.7
XS Rating Curve= 0 ,0
Exp/Cntr=0.3,0.1

Type RM Length L Ch R = 1 ,7959    ,996,996,996
BEGIN DESCRIPTION:
CARWILE CREEK 11.0
END DESCRIPTION:
XS GIS Cut Line= 3
      3749955.82     10143828.31      3749238.04     10143062.64
      3748917.89      10142761.1
#Sta/Elev= 30
  3950.5  288.73  4024.4  285.09  4138.3  280.78  4164.2  280.02  4239.3  277.73
  4329.3  274.37  4415.5  273.16  4562.8   272.6  4702.8  268.97  4754.3  268.98
  4782.1  270.13  4810.3  269.04  4987.3  268.71  4995.9  263.27  5003.6  263.77
  5008.4  265.94  5015.2  265.99  5022.5  268.52  5029.4  267.46  5050.8  272.16
    5065  273.33    5086  271.74  5093.3  273.18  5100.2  272.37  5107.5  274.02
  5128.5  273.94    5150  277.24  5241.8  284.34  5326.8  288.68  5439.8  296.73
#Mann= 10 ,-1 , 0
  3950.5     .11       0  4024.4     .17       0  4138.3     .11       0
  4164.2     .17       0  4239.3     .11       0  4415.5     .17       0
  4702.8     .15       0  4754.3     .11       0  4987.3     .07       0
  5022.5     .11       0
Bank Sta=4987.3,5022.5
XS Rating Curve= 0 ,0
Exp/Cntr=0.3,0.1

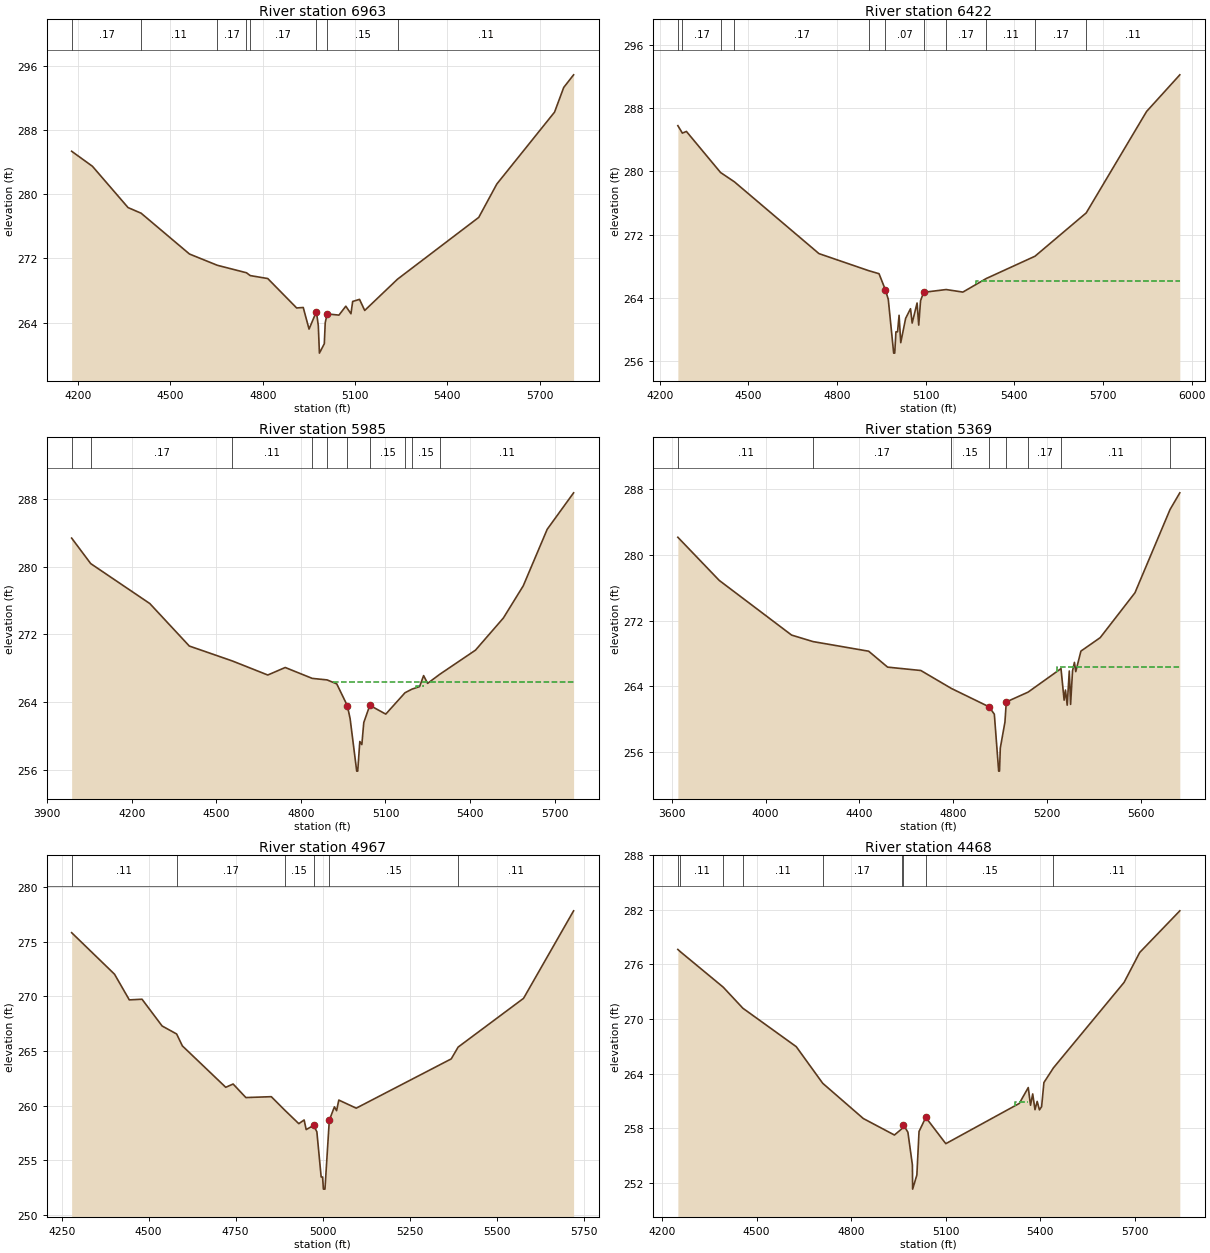
Type RM Length L Ch R = 1 ,6963    ,541,541,541
BEGIN DESCRIPTION:
CARWILE CREEK 9.0
END DESCRIPTION:
XS GIS Cut Line= 3
       3750049.6      10143724.2      3749756.16     10142957.11
      3749032.58     10142592.39
#Sta/Elev= 30
  4178.7  285.33  4246.3  283.46  4362.1  278.32  4404.6  277.62  4561.8  272.54
  4652.3  271.14    4747  270.21  4759.1  269.86  4816.2  269.49  4910.1  265.83
  4931.5  265.89  4950.4   263.2  4974.3  265.38  4980.5  263.63  4984.1  260.21
    5000  261.38    5003     264  5009.3  265.09  5047.6  264.94  5069.9  266.05
  5086.6  265.11  5092.2  266.64  5114.5   266.9  5131.3  265.52  5238.2  269.42
    5502   277.1  5560.7  281.25  5748.4   290.2  5778.2  293.27  5810.3  294.84
#Mann= 8 ,-1 , 0
  4178.7     .17       0  4404.6     .11       0  4652.3     .17       0
    4747     .11       0  4759.1     .17       0  4974.3     .09       0
  5009.3     .15       0  5238.2     .11       0
#XS Ineff= 2 , 0
       0                  5114.5       0   266.9
Permanent Ineff=
       F       F
Bank Sta=4974.3,5009.3
XS Rating Curve= 0 ,0
Exp/Cntr=0.3,0.1

Type RM Length L Ch R = 1 ,6422    ,437,437,437
BEGIN DESCRIPTION:
CARWILE CREEK 8.0
END DESCRIPTION:
XS GIS Cut Line= 3
      3750129.45      10143699.9      3750057.59      10142964.5
      3749617.83     10142111.03
#Sta/Elev= 30
  4261.1  285.75  4276.4  284.81  4290.1  285.02  4405.7  279.83  4452.4  278.66
  4738.7  269.59  4906.6  267.44    4942  267.05  4963.3  265.04  4973.3  263.82
  4991.6  257.02  4995.2  257.02  4999.2  259.71  5004.7  259.71  5009.9   261.8
  5015.5  258.34  5032.1  261.41  5048.6  262.63  5054.2  260.82  5070.8  263.35
  5076.4  260.56  5082.6  263.64    5093   264.7    5169  265.05  5225.9  264.73
  5304.8  266.44    5470  269.26  5643.3  274.73  5847.6  287.54  5960.1  292.17
#Mann= 11 ,-1 , 0
  4261.1     .11       0  4276.4     .17       0  4405.7     .11       0
  4452.4     .17       0  4906.6     .11       0  4963.3     .07       0
    5093     .15       0    5169     .17       0  5304.8     .11       0
    5470     .17       0  5643.3     .11       0
#XS Ineff= 2 , 0
       0                  5270.3       0  266.15
Permanent Ineff=
       F       F
Bank Sta=4963.3,5093
XS Rating Curve= 0 ,0
Exp/Cntr=0.3,0.1

Type RM Length L Ch R = 1 ,5985    ,616,616,616
BEGIN DESCRIPTION:
CARWILE CREEK 12.0
END DESCRIPTION:
XS GIS Cut Line= 3
      3750233.61     10143658.19        3750276.      10142645.6
      3749744.31     10142092.21
#Sta/Elev= 30
  3986.6   283.4  4054.3  280.38    4264  275.65  4404.1  270.62  4556.3  268.86
  4682.5  267.19  4744.4  268.08  4840.2  266.79    4893  266.61  4927.2  266.14
  4964.6  263.57  4974.6  262.03    4998  255.81  5001.6  255.81    5009  259.32
  5016.2  258.95  5023.1  261.56  5044.5   263.6  5101.1  262.56  5169.4  265.09
  5194.3  265.52  5221.2  265.82  5235.4  267.12  5249.5   266.2  5292.9  267.28
  5419.3  270.13  5518.4  273.94  5588.9  277.75  5673.8  284.44  5767.5  288.76
#Mann= 10 ,-1 , 0
  3986.6     .11       0  4054.3     .17       0  4556.3     .11       0
  4840.2     .17       0    4893     .15       0  4964.6     .09       0
  5044.5     .15       0  5169.4     .17       0  5194.3     .15       0
  5292.9     .11       0
#XS Ineff= 3 ,-1
  4914.5  4894.5  266.41  5207.1  5235.4  265.83  5235.4  5298.9  267.12
Permanent Ineff=
       F       F       F
Bank Sta=4964.6,5044.5
XS Rating Curve= 0 ,0
Exp/Cntr=0.3,0.1

Type RM Length L Ch R = 1 ,5369    ,402,402,402
BEGIN DESCRIPTION:
CARWILE CREEK 11.5
END DESCRIPTION:
XS GIS Cut Line= 3
      3750323.89     10143675.51      3750519.27     10142315.97
      3749844.71     10141955.79
#Sta/Elev= 30
  3626.5  282.16  3802.7  276.91  4111.1  270.25  4202.3  269.46  4439.2  268.29
    4520  266.35  4661.5  265.94    4792  263.75  4952.1  261.52  4974.6  260.62
  4993.1  253.69  4996.7  253.69    5000   256.5  5019.8  259.66  5025.5  262.11
  5118.5  263.31  5258.6  266.17  5271.9  262.33  5277.6  263.56    5285  261.72
  5293.9  265.88  5299.5  261.81  5307.7  265.89  5315.8  266.93  5321.5   265.8
  5343.4   268.3  5425.6  269.94  5573.6   275.4  5723.1  285.54  5764.7  287.57
#Mann= 8 ,-1 , 0
  3626.5     .11       0  4202.3     .17       0    4792     .15       0
  4952.1     .09       0  5025.5     .15       0  5118.5     .17       0
  5258.6     .11       0  5723.1     .17       0
#XS Ineff= 2 , 0
       0                  5239.7       0  266.41
Permanent Ineff=
       F       F
Bank Sta=4952.1,5025.5
XS Rating Curve= 0 ,0
Exp/Cntr=0.3,0.1

Type RM Length L Ch R = 1 ,4967    ,499,499,499
BEGIN DESCRIPTION:
CARWILE CREEK 7.0
END DESCRIPTION:
XS GIS Cut Line= 3
      3751417.86     10142511.08      3750805.84     10142129.17
      3750217.84     10141711.06
#Sta/Elev= 30
  4278.6  275.82  4401.9  272.02  4444.4  269.67  4480.9  269.73  4538.7  267.28
  4580.4  266.55  4596.9  265.46  4721.6  261.67  4742.8  261.97  4779.4  260.73
  4852.5  260.81  4890.5   259.6  4931.6  258.34  4946.9  258.68  4952.8   257.8
  4974.1  258.18  4983.5   257.6  4995.9  253.46    5000  253.46  5002.3  252.35
  5006.8  252.35  5019.3  258.66    5034  259.88  5040.2  259.53  5046.6   260.5
  5096.7  259.76  5369.8  264.27  5389.6  265.35  5577.6  269.81  5721.5  277.82
#Mann= 6 ,-1 , 0
  4278.6     .11       0  4580.4     .17       0  4890.5     .15       0
  4974.1     .09       0  5019.3     .15       0  5389.6     .11       0
Bank Sta=4974.1,5019.3
XS Rating Curve= 0 ,0
Exp/Cntr=0.3,0.1

Type RM Length L Ch R = 1 ,4468    ,581,581,581
BEGIN DESCRIPTION:
CARWILE CREEK 6.0
END DESCRIPTION:
XS GIS Cut Line= 3
      3751717.83     10142361.06      3751148.93     10141872.03
      3750567.83     10141261.04
#Sta/Elev= 30
  4249.8  277.65  4258.1  277.39  4393.8  273.51  4456.1   271.2  4625.6  266.98
  4709.6  262.96  4838.5  259.09  4937.3  257.28    4960  257.94  4965.8  258.41
  4980.1  257.58  4994.3     254  4995.1  251.34  5008.5  252.89  5015.4  257.67
  5036.8  259.21  5100.4  256.33  5333.7  260.75  5362.1  262.49  5369.3  260.55
  5376.2  261.79  5383.5  260.06  5390.4  260.97  5397.6  260.04  5404.5  260.39
  5411.8  263.04  5442.2  264.66  5666.2  274.03  5715.9  277.32  5843.2  281.89
#Mann= 9 ,-1 , 0
  4249.8     .17       0  4258.1     .11       0  4393.8     .17       0
  4456.1     .11       0  4709.6     .17       0    4960     .15       0
  4965.8     .09       0  5036.8     .15       0  5442.2     .11       0
#XS Ineff= 2 ,-1
  5319.6  5362.1  260.85  5362.1  5411.8  262.49
Permanent Ineff=
       F       F
Bank Sta=4965.8,5036.8
XS Rating Curve= 0 ,0
Exp/Cntr=0.3,0.1

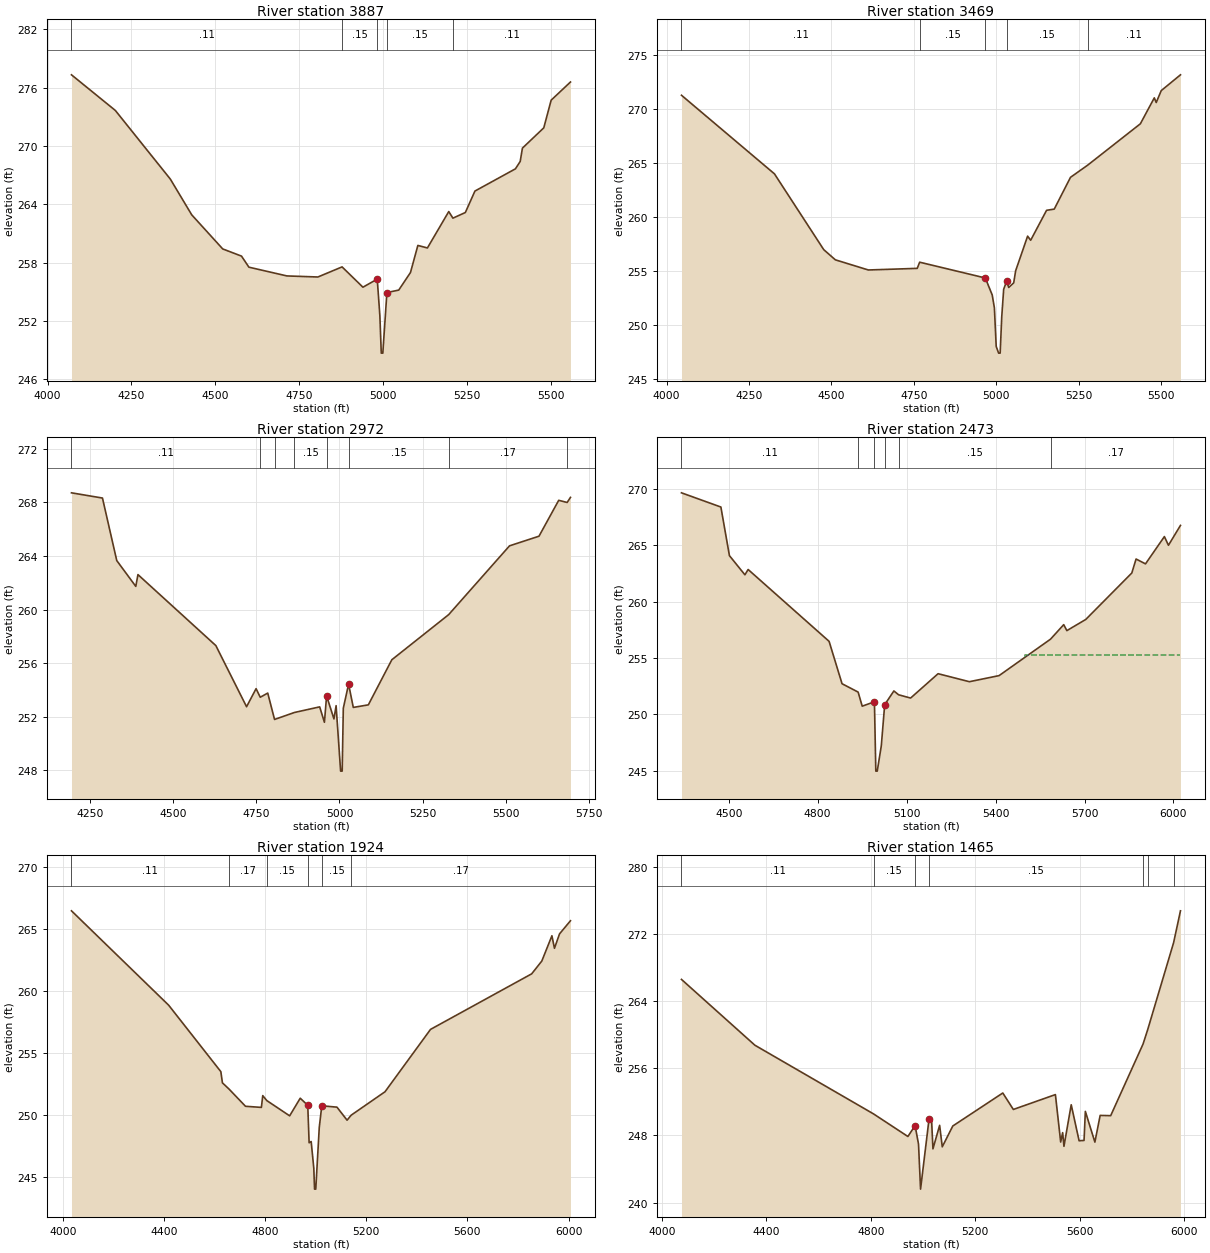
Type RM Length L Ch R = 1 ,3887    ,418,418,418
BEGIN DESCRIPTION:
CARWILE CREEK 5.0
END DESCRIPTION:
XS GIS Cut Line= 3
       3751904.6     10142218.85       3751310.2     10141505.16
      3750884.61     10141142.43
#Sta/Elev= 30
  4071.2  277.33    4202  273.66    4366  266.59  4429.8  262.91  4522.2   259.4
  4578.2  258.66  4600.3  257.52  4713.6  256.62    4806  256.51  4878.1  257.55
  4940.3  255.46    4983  256.29  4990.8  252.53    4995  248.67  4999.6  248.67
  5011.8  254.91    5047  255.16  5082.1  256.97  5104.1  259.76  5132.6   259.5
  5196.3  263.25  5208.6  262.57  5245.7  263.15  5274.3  265.36  5395.1  267.65
  5409.3  268.41  5415.9  269.78  5479.6  271.87  5501.6  274.72  5559.2  276.59
#Mann= 5 ,-1 , 0
  4071.2     .11       0  4878.1     .15       0    4983     .09       0
  5011.8     .15       0  5208.6     .11       0
Bank Sta=4983,5011.8
XS Rating Curve= 0 ,0
Exp/Cntr=0.3,0.1

Type RM Length L Ch R = 1 ,3469    ,497,497,497
BEGIN DESCRIPTION:
CARWILE CREEK 4.0
END DESCRIPTION:
XS GIS Cut Line= 3
      3752191.01     10142006.12      3751575.76      10141275.7
      3751105.95     10140973.16
#Sta/Elev= 30
    4045  271.23  4327.1  263.96  4476.6  256.95  4511.8  256.01  4611.9  255.07
  4760.2  255.22  4767.6  255.79  4966.8  254.33  4987.7  252.76  4994.3  251.57
  4999.8     248  5007.1  247.38  5011.8  247.38  5016.6  250.74  5022.5  253.29
  5031.8  254.06  5037.7  253.45  5052.9  253.88  5058.8     255  5095.1   258.2
  5104.4  257.82  5152.6  260.59  5175.9   260.7  5225.2  263.64  5277.5  264.77
  5437.1  268.59  5479.4  270.99  5485.3  270.56  5500.5  271.66  5558.8  273.12
#Mann= 5 ,-1 , 0
    4045     .11       0  4767.6     .15       0  4966.8     .09       0
  5031.8     .15       0  5277.5     .11       0
Bank Sta=4966.8,5031.8
XS Rating Curve= 0 ,0
Exp/Cntr=0.3,0.1

Type RM Length L Ch R = 1 ,2972    ,499,499,499
BEGIN DESCRIPTION:
CARWILE CREEK 3.0
END DESCRIPTION:
XS GIS Cut Line= 3
      3752440.01     10141770.73      3751924.14     10141151.05
      3751317.86     10140811.08
#Sta/Elev= 30
  4193.7  268.72  4286.9  268.33  4329.9  263.66  4387.2  261.73  4393.7  262.61
    4628  257.31  4720.5  252.74  4749.1  254.09  4761.7  253.45  4784.2  253.76
  4804.7  251.79  4864.4  252.31  4940.5  252.73  4954.8  251.58  4961.3  253.55
  4983.4  251.83  4989.9  252.82  5003.5  247.93  5008.2  247.93  5011.6  252.63
  5027.5  254.43  5041.6  252.69  5086.9  252.88  5157.6  256.25  5328.6  259.62
  5511.7  264.76  5600.4  265.48  5659.7  268.16  5685.1     268  5695.1  268.38
#Mann= 8 ,-1 , 0
  4193.7     .11       0  4761.7     .15       0  4804.7     .11       0
  4864.4     .15       0  4961.3     .09       0  5027.5     .15       0
  5328.6     .17       0  5685.1     .11       0
Bank Sta=4961.3,5027.5
XS Rating Curve= 0 ,0
Exp/Cntr=0.3,0.1

Type RM Length L Ch R = 1 ,2473    ,549,549,549
BEGIN DESCRIPTION:
CARWILE CREEK 2.0
END DESCRIPTION:
XS GIS Cut Line= 3
      3752626.63     10141696.92      3752361.61     10141093.23
      3751396.74      10140751.8
#Sta/Elev= 30
  4340.7  269.64  4473.6  268.38  4502.4  264.07  4554.6  262.37  4565.5  262.84
  4838.5  256.47  4882.2  252.71  4936.4  251.97  4950.2  250.72  4991.4  251.11
  4996.1  244.96  5000.9  244.96  5014.6  247.21    5026  250.85    5057  252.07
  5072.9  251.73  5113.4  251.44  5206.1   253.6  5311.6  252.89  5411.8  253.43
  5585.2  256.66  5629.8  257.95  5640.4  257.42  5704.1  258.41  5859.4  262.53
  5873.8  263.77  5905.6  263.34  5969.3  265.76    5983  264.99  6023.5  266.75
#Mann= 6 ,-1 , 0
  4340.7     .11       0  4936.4     .17       0  4991.4     .09       0
    5026     .17       0  5072.9     .15       0  5585.2     .17       0
#XS Ineff= 2 , 0
       0                  5499.2       0  255.27
Permanent Ineff=
       F       F
Bank Sta=4991.4,5026
XS Rating Curve= 0 ,0
Exp/Cntr=0.3,0.1

Type RM Length L Ch R = 1 ,1924    ,459,459,459
BEGIN DESCRIPTION:
CARWILE CREEK 1.0
END DESCRIPTION:
XS GIS Cut Line= 3
      3752821.96     10141566.74      3752451.81     10140674.48
      3751444.52     10140699.73
#Sta/Elev= 30
    4034  266.44  4418.4  258.83  4624.8  253.47    4631  252.57  4657.5  252.06
  4722.2  250.68  4785.1  250.59  4790.5  251.54  4806.5  251.14  4896.9  249.91
  4938.7  251.33  4968.5  250.76  4973.9  247.74    4982  247.84  4992.4  245.69
  4995.4     244  5000.2     244    5014  248.97    5024  250.72    5084  250.61
    5124  249.56  5140.1  249.96    5274  251.85  5454.1  256.88  5854.2  261.36
  5894.2  262.39  5934.2  264.43  5944.3  263.42  5964.3  264.58  6007.6  265.64
#Mann= 6 ,-1 , 0
    4034     .11       0  4657.5     .17       0  4806.5     .15       0
  4968.5     .09       0    5024     .15       0  5140.1     .17       0
Bank Sta=4968.5,5024
XS Rating Curve= 0 ,0
Exp/Cntr=0.3,0.1

Type RM Length L Ch R = 1 ,1465    ,465,465,465
BEGIN DESCRIPTION:
CARWILE CREEK 3.5
END DESCRIPTION:
XS GIS Cut Line= 3
      3752917.85     10141511.06      3752737.35     10140604.25
      3752618.96     10139625.88
#Sta/Elev= 30
  4075.4  266.58  4356.5  258.74  4810.6  250.56  4942.1  247.87  4969.7  249.17
  4982.8  246.95  4990.6   241.6  5023.3  250.01  5032.9  249.77    5038   246.4
  5063.6   249.2  5073.7  246.64    5114  249.12  5305.4  253.05  5345.7  251.09
  5506.8  252.86    5527  247.21  5534.5  248.33  5539.5   246.7  5567.3  251.65
  5597.5  247.36  5616.4   247.4  5621.4  250.86  5657.9   247.2  5678.1  250.38
  5718.4  250.35  5842.4  258.89  5859.7  260.56  5959.2  270.95  5985.5  274.75
#Mann= 7 ,-1 , 0
  4075.4     .11       0  4810.6     .15       0  4969.7     .09       0
  5023.3     .15       0  5842.4     .17       0  5859.7     .15       0
  5959.2     .11       0
Bank Sta=4969.7,5023.3
XS Rating Curve= 0 ,0
Exp/Cntr=0.3,0.1

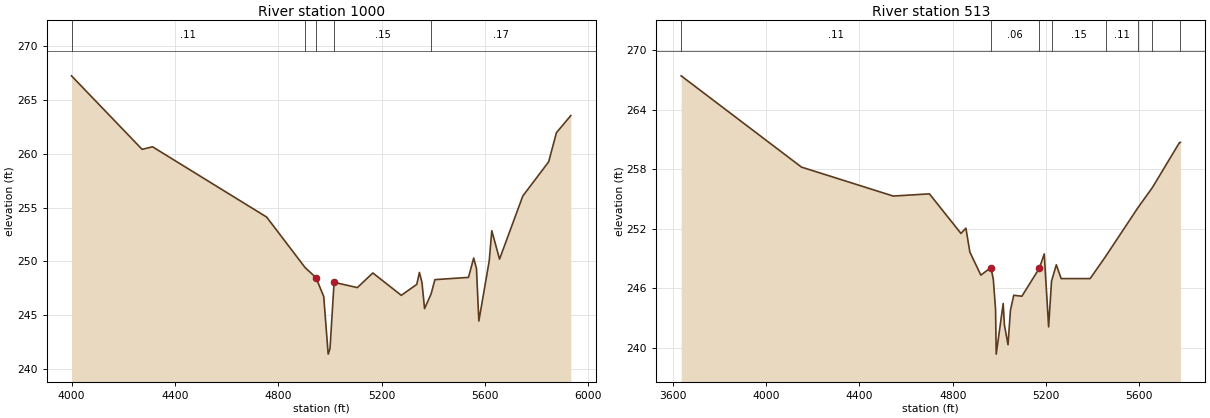
Type RM Length L Ch R = 1 ,1000    ,487,487,487
BEGIN DESCRIPTION:
CARWILE CREEK 2.5
END DESCRIPTION:
XS GIS Cut Line= 4
      3753060.67     10141523.31      3753149.21     10140526.94
      3753149.03     10140439.23      3753120.27     10139595.53
#Sta/Elev= 30
  3999.7  267.26    4273  260.42  4313.2  260.66  4754.9  254.12  4903.8  249.42
  4945.7  248.49  4975.8  246.73    4993  241.37    5000  241.87  5015.9  248.05
  5105.9  247.56  5165.9  248.92    5276  246.84    5336  247.86    5346  248.97
    5356  248.04    5366   245.6  5391.5  246.98    5406   248.3  5536.1  248.51
  5556.1  250.31  5566.9  249.34  5576.1  244.45  5616.2  250.04  5626.2  252.85
  5656.2  250.21  5746.2  256.08  5846.3  259.26  5876.3  261.97  5931.9  263.56
#Mann= 5 ,-1 , 0
  3999.7     .11       0  4903.8     .15       0  4945.7     .09       0
  5015.9     .15       0  5391.5     .17       0
Bank Sta=4945.7,5015.9
XS Rating Curve= 0 ,0
Exp/Cntr=0.3,0.1

Type RM Length L Ch R = 1 ,513     ,0,0,0
BEGIN DESCRIPTION:
CARWILE CREEK 1.5
END DESCRIPTION:
XS GIS Cut Line= 4
      3753232.71     10141602.47       3753588.6     10140582.54
      3753488.48     10140316.71      3753286.93     10139567.24
#Sta/Elev= 30
  3635.7  267.42  4151.5  258.21  4544.7  255.29    4700  255.51  4835.1  251.52
  4856.4  252.05  4873.3  249.64  4920.5  247.31  4963.9  248.08    4974  246.85
  4983.5  243.84  4986.3  239.34  5016.2  244.45  5021.5  242.27  5036.9  240.29
  5047.3  243.77  5061.5  245.28  5096.3  245.18    5171     248  5192.2  249.45
    5211  242.09  5223.4   246.7    5244  248.36  5264.7  246.96    5389  246.96
  5454.8  249.18  5592.8  254.08  5656.1  256.16  5772.3   260.7  5776.1   260.7
#Mann= 8 ,-1 , 0
  3635.7     .11       0  4963.9     .06       0    5171     .17       0
  5223.4     .15       0  5454.8     .11       0  5592.8     .15       0
  5656.1     .17       0  5772.3     .11       0
Bank Sta=4963.9,5171
XS Rating Curve= 0 ,0
Exp/Cntr=0.3,0.1

Chan Stop Cuts=-1
Use User Specified Reach Order=0
Composite Channel Slope=5