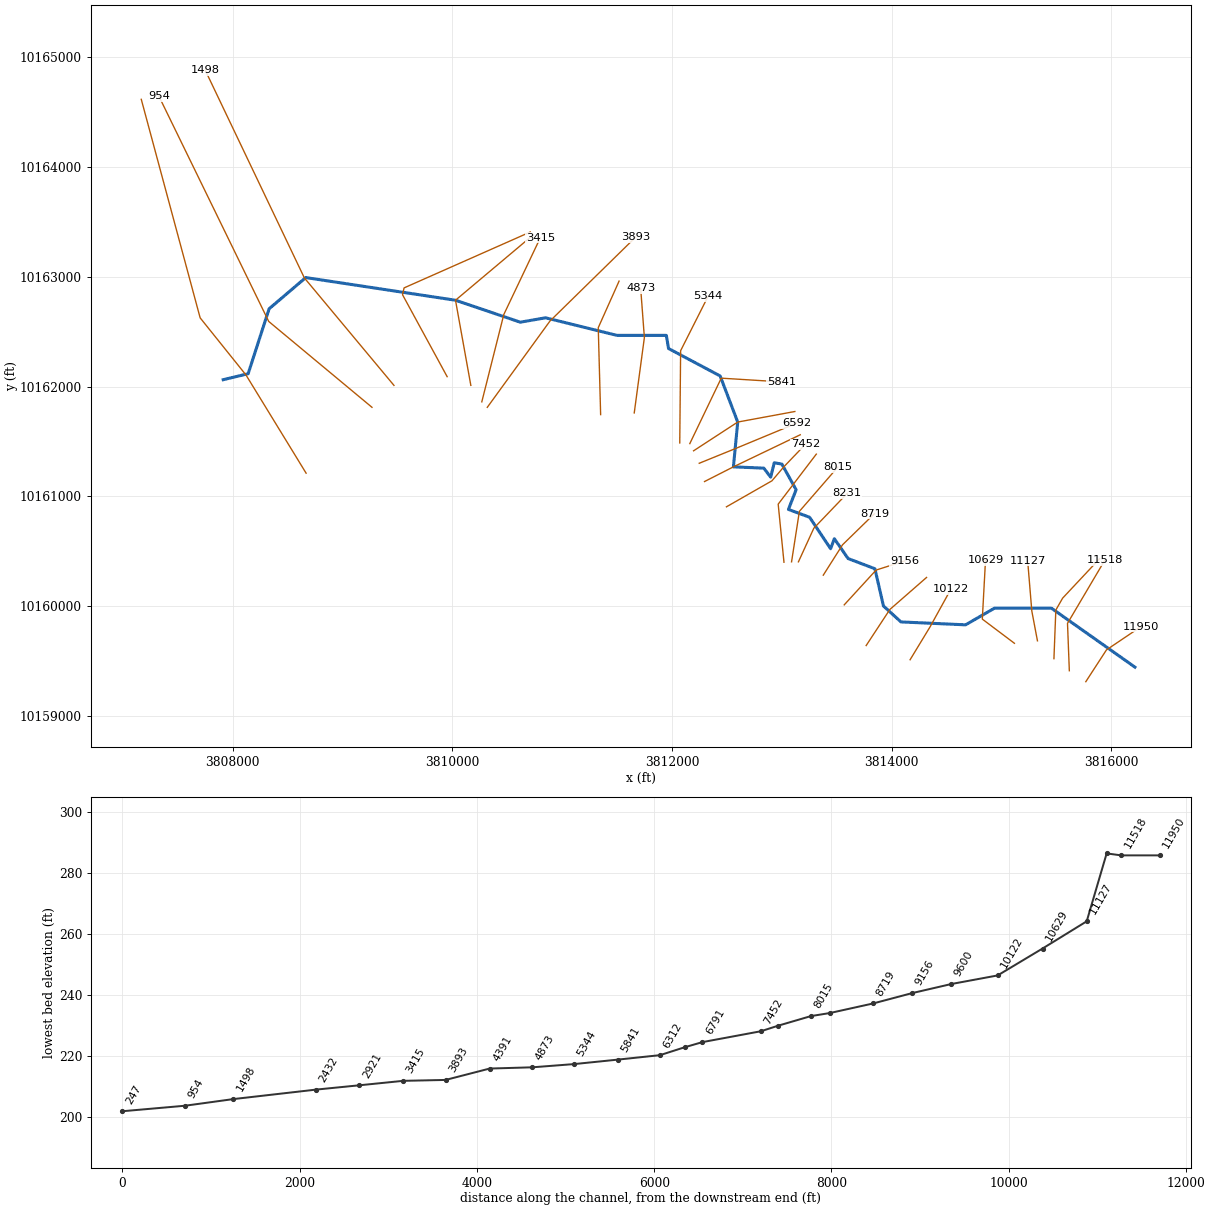
--- CHAMBERS CREEK.prj (project) ---

Proj Title=CHAMBERS CREEK Base Level Engineering
Current Plan=p01
Default Exp/Contr=0.3,0.1
English Units
Geom File=g01
Flow File=f01
Flow File=f02
Plan File=p01
Y Axis Title=Elevation
X Axis Title(PF)=Main Channel Distance
X Axis Title(XS)=Station
BEGIN DESCRIPTION:
CHAMBERS CREEK
END DESCRIPTION:
DSS Export Rating Curves= 0
DSS Export Rating Curve Sorted= 0
DSS Export Volume Flow Curves= 0
DXF OffsetX= 0
DXF OffsetY= 0
DXF ScaleX= 1
DXF ScaleY= 10

--- CHAMBERS CREEK.p01 (plan) ---

Plan Title=Multiple Run
Short Identifier=Multiple
Geom File=g01
Flow File=f01
Subcritical Flow
K Sum by GR= 0
Std Step Tol= 0.01
Critical Tol= 0.01
Num of Std Step Trials= 20
Max Error Tol= 0.3
Flow Tol Ratio= 0.001
Split Flow NTrial= 30
Split Flow Tol= 0.02
Split Flow Ratio= 0.02
Log Output Level= 0
Friction Slope Method= 1
Unsteady Friction Slope Method= 2
Unsteady Bridges Friction Slope Method= 1
Parabolic Critical Depth
Global Vel Dist=  1 , 1 , 1
Global Log Level= 0
CheckData=True
Encroach Param= -1, 0, 0, 0
BEGIN DESCRIPTION:
Multiple Run
END DESCRIPTION:

--- CHAMBERS CREEK.f01 (steady flow) ---

Flow Title=Multiple
Program Version=4.10
Number of Profiles= 7
Profile Names=10-year,25-year,50-year,1pct_min,100-year,1pct_plu,500-year
River Rch & RM=CHAMBERS CREEK,Reach-1         ,11950
     294     384     506     222     670    2023    1202
River Rch & RM=CHAMBERS CREEK,Reach-1         ,11518
     900    1246    1711     773    2334    7049    4489
River Rch & RM=CHAMBERS CREEK,Reach-1         ,5344
    1030    1426    1957     883    2666    8051    5114
River Rch & RM=CHAMBERS CREEK,Reach-1         ,1498
    2922    4178    5851    2679    8090   24431   16008
River Rch & RM=CHAMBERS CREEK,Reach-1         ,954
    2922    4178    5851    2679    8090   24431   16008
River Rch & RM=CHAMBERS CREEK,Reach-1         ,247
    2922    4178    5851    2679    8090   24431   16008
Boundary for River Rch & Prof#=CHAMBERS CREEK,Reach-1         , 1
Up Type= 0
Dn Type= 3
Dn Slope=0.006
Boundary for River Rch & Prof#=CHAMBERS CREEK,Reach-1         , 2
Up Type= 0
Dn Type= 3
Dn Slope=0.006
Boundary for River Rch & Prof#=CHAMBERS CREEK,Reach-1         , 3
Up Type= 0
Dn Type= 3
Dn Slope=0.006
Boundary for River Rch & Prof#=CHAMBERS CREEK,Reach-1         , 4
Up Type= 0
Dn Type= 3
Dn Slope=0.006
Boundary for River Rch & Prof#=CHAMBERS CREEK,Reach-1         , 5
Up Type= 0
Dn Type= 3
Dn Slope=0.006
Boundary for River Rch & Prof#=CHAMBERS CREEK,Reach-1         , 6
Up Type= 0
Dn Type= 3
Dn Slope=0.006
Boundary for River Rch & Prof#=CHAMBERS CREEK,Reach-1         , 7
Up Type= 0
Dn Type= 3
Dn Slope=0.006
DSS Import GetInterval= 0
DSS Import GetPeak= 0
DSS Import FillOption= 0

--- CHAMBERS CREEK.f02 (steady flow) ---

Flow Title=Orig_BLE_Flow
Program Version=4.10
Number of Profiles= 7
Profile Names=10-year,25-year,50-year,1pct_min,100-year,1pct_plu,500-year
River Rch & RM=CHAMBERS CREEK,Reach-1         ,11950
     294     376     440     171     515    1555     699
River Rch & RM=CHAMBERS CREEK,Reach-1         ,11518
     900    1222    1488     595    1795    5422    2610
River Rch & RM=CHAMBERS CREEK,Reach-1         ,5344
    1030    1398    1702     679    2051    6193    2973
River Rch & RM=CHAMBERS CREEK,Reach-1         ,1498
    2922    4096    5088    2061    6223   18793    9307
River Rch & RM=CHAMBERS CREEK,Reach-1         ,954
    2922    4096    5088    2061    6223   18793    9307
Boundary for River Rch & Prof#=CHAMBERS CREEK,Reach-1         , 1
Up Type= 0
Dn Type= 3
Dn Slope=0.005
Boundary for River Rch & Prof#=CHAMBERS CREEK,Reach-1         , 2
Up Type= 0
Dn Type= 3
Dn Slope=0.005
Boundary for River Rch & Prof#=CHAMBERS CREEK,Reach-1         , 3
Up Type= 0
Dn Type= 3
Dn Slope=0.005
Boundary for River Rch & Prof#=CHAMBERS CREEK,Reach-1         , 4
Up Type= 0
Dn Type= 3
Dn Slope=0.005
Boundary for River Rch & Prof#=CHAMBERS CREEK,Reach-1         , 5
Up Type= 0
Dn Type= 3
Dn Slope=0.005
Boundary for River Rch & Prof#=CHAMBERS CREEK,Reach-1         , 6
Up Type= 0
Dn Type= 3
Dn Slope=0.005
Boundary for River Rch & Prof#=CHAMBERS CREEK,Reach-1         , 7
Up Type= 0
Dn Type= 3
Dn Slope=0.005
DSS Import GetInterval= 0
DSS Import GetPeak= 0
DSS Import FillOption= 0

--- CHAMBERS CREEK.g01 (geometry) ---

Geom Title=Existing Conditions
Program Version=4.10

River Reach=CHAMBERS CREEK  ,Reach-1
Reach XY= 30
      3816215.37     10159443.53       3815455.3     10159980.41
      3814936.97     10159981.33      3814673.08     10159829.29
       3814084.8     10159855.59       3813925.3      10160000.9
      3813847.44     10160340.22      3813603.17     10160433.19
      3813477.91     10160614.18      3813444.31     10160522.52
      3813252.38     10160809.49       3813060.2     10160880.85
      3813129.73     10161060.28      3813000.56     10161293.35
      3812931.03     10161306.37      3812898.22     10161174.86
      3812835.72     10161256.89       3812558.9     10161268.61
      3812598.23     10161676.84      3812438.23     10162096.84
      3811968.23     10162346.84      3811948.23     10162466.84
      3811498.23     10162466.84      3810848.23     10162626.84
      3810618.23     10162586.84      3810028.23     10162786.84
       3808664.7     10162993.31      3808331.07     10162708.89
      3808140.14     10162117.39      3807913.09      10162062.7

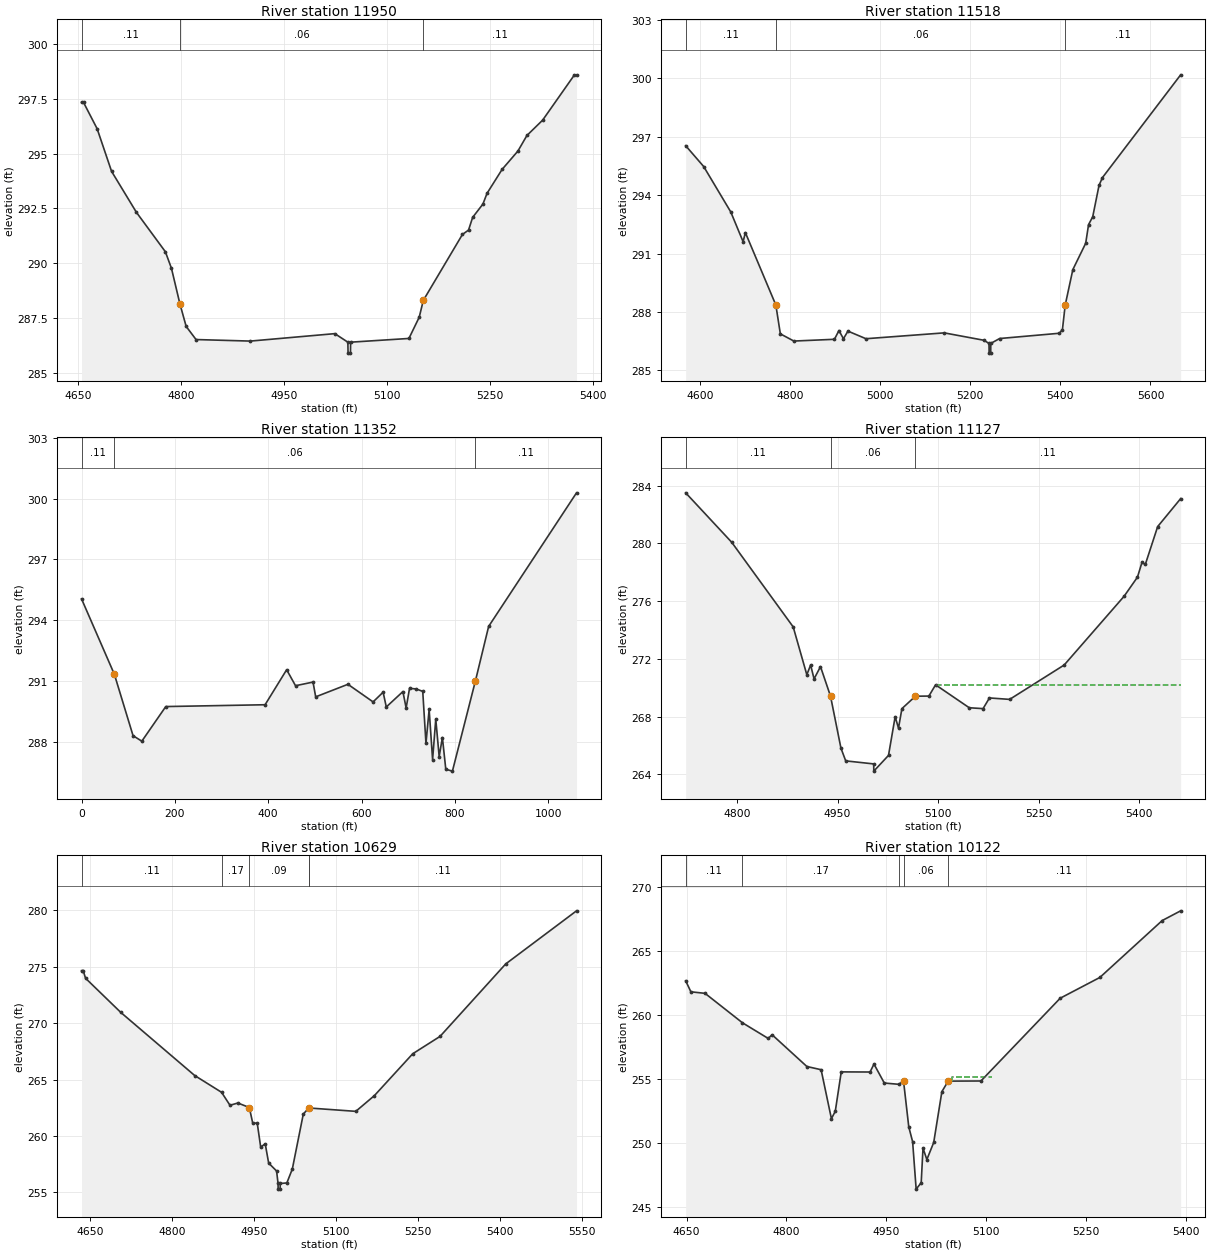
Type RM Length L Ch R = 1 ,11950   ,432,432,432
BEGIN DESCRIPTION:
CHAMBERS CREEK 20.0
END DESCRIPTION:
XS GIS Cut Line= 3
      3815767.87      10159311.1      3815956.04     10159600.87
      3816267.81     10159811.04
#Sta/Elev= 30
  4654.5  297.34  4657.4  297.34  4677.2  296.14  4698.3  294.19  4734.5  292.32
  4776.7  290.52  4785.6  289.76  4797.8  288.15    4807  287.11  4821.4  286.51
  4900.6  286.44  5023.7  286.78  5042.7  286.39    5043  285.89  5046.5  285.89
  5046.7  286.39  5131.7  286.56  5146.7  287.53  5152.7   288.3  5209.7  291.31
  5218.6  291.51  5224.6  292.09  5239.6   292.7  5245.6  293.19  5267.5  294.28
  5290.6  295.12  5303.7  295.83  5326.6  296.53    5373   298.6    5376   298.6
#Mann= 3 , 0 , 0
  4654.5     .11       0  4797.8     .06       0  5152.7     .11       0
Bank Sta=4797.8,5152.7
XS Rating Curve= 0 ,0
Exp/Cntr=0.3,0.1

Type RM Length L Ch R = 1 ,11518   ,165,165,165
BEGIN DESCRIPTION:
CHAMBERS CREEK 19.0
END DESCRIPTION:
XS GIS Cut Line= 3
      3815617.85     10159411.06      3815601.22     10159842.84
      3815940.39     10160417.17
#Sta/Elev= 30
  4567.9  296.54  4607.9  295.47    4668  293.14  4695.4  291.61  4700.4  292.08
  4768.1  288.36  4778.1  286.88  4808.1  286.51  4898.2   286.6  4908.2  287.05
  4918.2  286.63  4928.2  287.02  4968.2  286.63    5142  286.93  5230.2  286.55
  5241.4  286.39  5241.7  285.89  5245.2  285.89  5245.4  286.39  5265.1  286.64
  5397.6  286.91  5404.4  287.09 5410.64  288.36  5427.6  290.18  5456.1  291.53
  5462.5  292.49  5471.7  292.89  5485.7   294.5  5493.2   294.9    5667  300.18
#Mann= 3 , 0 , 0
  4567.9     .11       0  4768.1     .06       0 5410.64     .11       0
Bank Sta=4768.1,5410.64
XS Rating Curve= 0 ,0
Exp/Cntr=0.3,0.1

Type RM Length L Ch R = 1 ,11352   ,225,225,225
XS GIS Cut Line= 4
       3815477.7     10159520.74      3815494.88     10159963.79
       3815556.6      10160072.1      3815893.93     10160432.07
#Sta/Elev= 30
       0  295.05    70.4  291.32   110.4  288.29   129.2  288.02   180.5  289.73
   393.3  289.82   439.5  291.55   458.5  290.76     496  290.94   501.7  290.21
   570.8  290.83   624.7  289.96   646.2  290.44     653  289.71   688.6  290.47
   695.5  289.66   702.8  290.63     717   290.6   731.1  290.48     738  287.91
   744.8  289.59   752.2  287.11     759  289.11   766.3  287.26   773.2   288.2
   780.5  286.63   794.7  286.54     844     291   872.3  293.69  1060.6  300.29
#Mann= 3 , 0 , 0
       0     .11       0    70.4     .06       0     844     .11       0
Bank Sta=70.4,844
XS Rating Curve= 0 ,0
Exp/Cntr=0.3,0.1

Type RM Length L Ch R = 1 ,11127   ,498,498,498
BEGIN DESCRIPTION:
CHAMBERS CREEK 18.0
END DESCRIPTION:
XS GIS Cut Line= 3
      3815327.56     10159683.61       3815276.2     10159955.29
      3815238.25     10160415.23
#Sta/Elev= 30
  4723.5   283.5  4792.2  280.07  4883.8  274.21  4904.1   270.9  4909.8  271.57
  4914.9  270.61  4924.5  271.46 4939.46  269.41    4955  265.81  4962.1  264.93
  5003.8  264.72    5004  264.22  5025.9  265.31  5035.8  267.99  5040.8   267.2
  5045.9  268.55    5066  269.41  5086.1  269.42  5096.1   270.2  5146.3  268.61
  5166.9  268.55  5176.4  269.29  5206.5  269.19  5287.8  271.57  5377.1  276.33
  5397.1  277.66  5403.8  278.68  5408.8  278.54  5427.2  281.16  5461.5   283.1
#Mann= 3 , 0 , 0
  4723.5     .11       0 4939.46     .06       0    5066     .11       0
#XS Ineff= 2 , 0
       0                  5096.1       0  270.22
Permanent Ineff=
       F       F
Bank Sta=4939.46,5066
XS Rating Curve= 0 ,0
Exp/Cntr=0.3,0.1

Type RM Length L Ch R = 1 ,10629   ,507,507,507
BEGIN DESCRIPTION:
CHAMBERS CREEK 17.0
END DESCRIPTION:
XS GIS Cut Line= 3
      3815117.83     10159661.09      3814825.42     10159881.37
      3814854.73     10160420.47
#Sta/Elev= 30
  4633.9  274.66    4637  274.66  4641.2  273.99  4705.7  270.96    4841  265.36
  4890.2  263.87  4905.6  262.72  4920.1  262.92    4941  262.52  4947.2  261.15
  4955.5  261.13  4961.8  259.01  4970.1   259.3  4976.4  257.59  4990.9  256.89
  4993.6  255.78  4993.8  255.28  4997.3  255.28  4997.6  255.78  5009.7  255.83
  5019.7  257.06  5039.8  261.94  5049.7  262.47  5049.8  262.48  5135.9  262.18
    5170  263.58  5240.1  267.29  5290.1  268.83  5410.3  275.26  5539.9  279.97
#Mann= 5 ,-1 , 0
  4633.9     .11       0  4890.2     .17       0    4941     .09       0
  5049.7     .12       0  5049.8     .11       0
Bank Sta=4941,5049.7
XS Rating Curve= 0 ,0
Exp/Cntr=0.3,0.1

Type RM Length L Ch R = 1 ,10122   ,522,522,522
BEGIN DESCRIPTION:
CHAMBERS CREEK 16.0
END DESCRIPTION:
XS GIS Cut Line= 3
      3814167.84     10159511.06      3814350.16     10159811.58
       3814539.9      10160155.4
#Sta/Elev= 30
  4648.5  262.69  4656.3  261.83  4677.6  261.71  4733.9  259.41  4772.6  258.19
  4778.4  258.48  4830.7     256  4852.1  255.75  4867.6  251.93  4873.4   252.5
  4882.4  255.58  4925.7  255.57  4931.6  256.19  4947.1  254.71  4969.1  254.61
    4976  254.88  4983.9  251.29  4989.7  250.13    4995  246.43  5002.6  246.93
  5005.3  249.63  5011.1  248.74  5021.4  250.07  5033.7  254.04  5043.2  254.86
  5092.4  254.87  5211.6  261.33  5271.2  262.95  5364.9  267.39  5392.7  268.15
#Mann= 5 ,-1 , 0
  4648.5     .11       0  4733.9     .17       0  4969.1     .11       0
    4976     .06       0  5043.2     .11       0
#XS Ineff= 3 ,-1
  4931.6  4815.3  256.19    4976  4931.6  254.88  5048.9  5108.5  255.18
Permanent Ineff=
       F       F       F
Bank Sta=4976,5043.2
XS Rating Curve= 0 ,0
Exp/Cntr=0.3,0.1

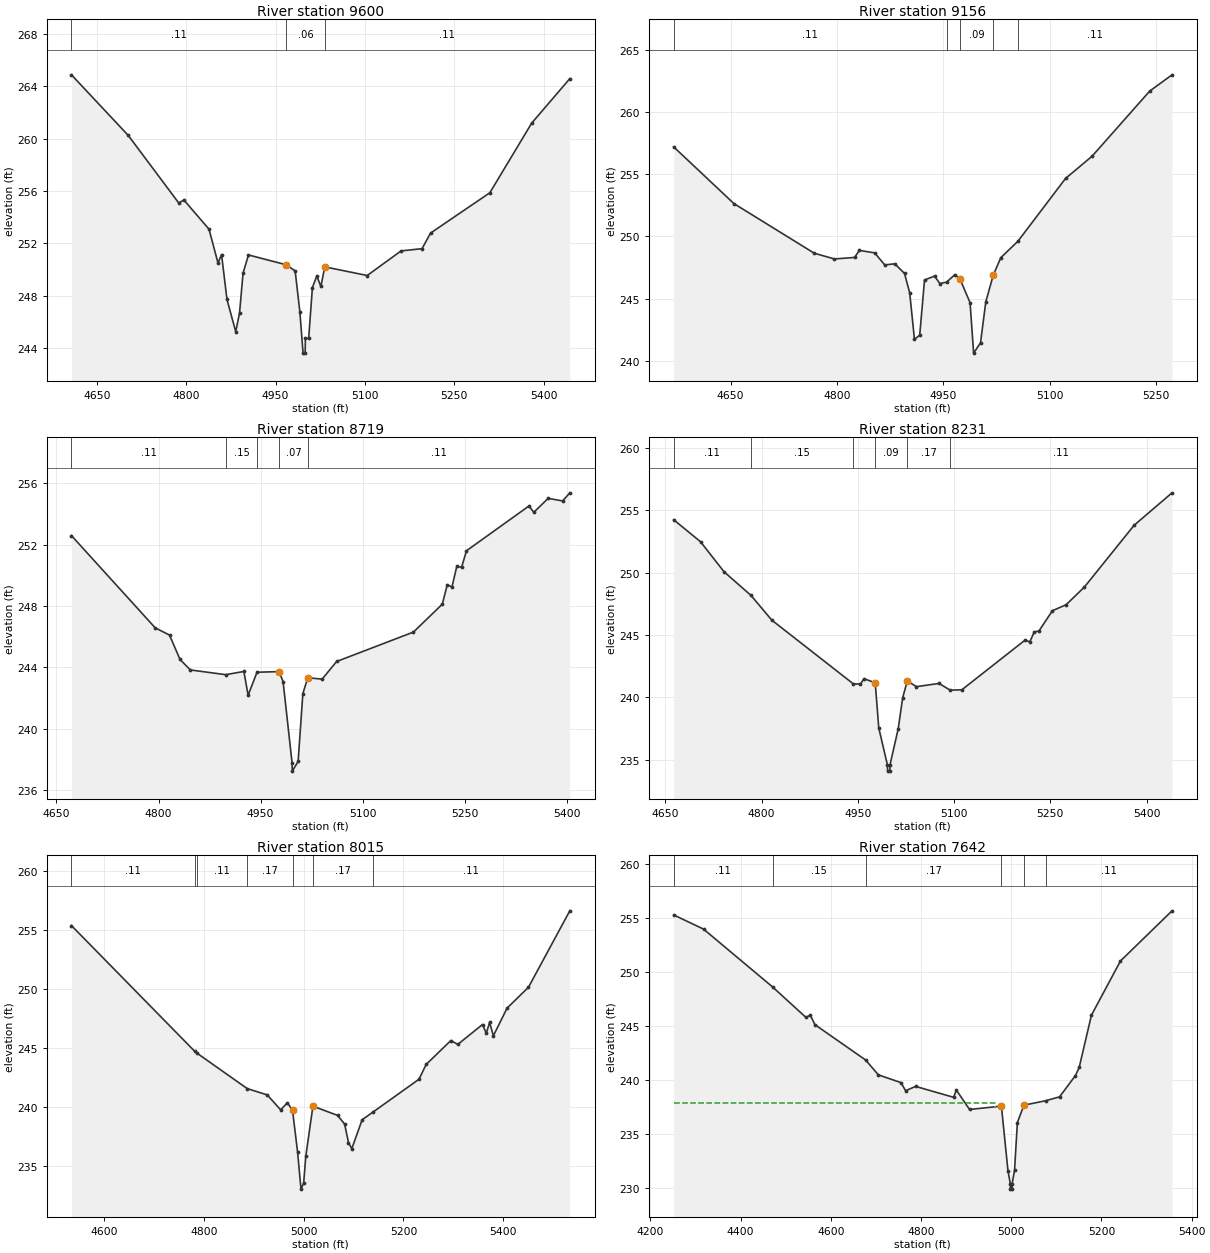
Type RM Length L Ch R = 1 ,9600    ,444,444,444
BEGIN DESCRIPTION:
CHAMBERS CREEK 15.0
END DESCRIPTION:
XS GIS Cut Line= 3
      3813767.78     10159640.41      3813983.37     10159968.87
      3814317.82     10160261.05
#Sta/Elev= 30
  4607.1  264.87  4702.5  260.24  4787.3  255.08  4795.9  255.31  4838.1  253.08
  4853.2   250.5  4859.2  251.14  4868.3  247.71    4883  245.25  4889.4  246.67
  4895.3  249.72  4904.4  251.11  4967.7  250.36  4982.8  249.89  4990.7  246.77
  4996.1  243.61  4999.6  243.61    5000  244.73  5005.5  244.73  5011.8  248.62
  5019.2   249.5    5026   248.7  5032.6   250.2  5103.8  249.54  5160.8  251.42
  5195.9  251.59  5210.2  252.78  5309.8  255.86  5380.1  261.18  5444.1  264.58
#Mann= 3 , 0 , 0
  4607.1     .11       0  4967.7     .06       0  5032.6     .11       0
Bank Sta=4967.7,5032.6
XS Rating Curve= 0 ,0
Exp/Cntr=0.3,0.1

Type RM Length L Ch R = 1 ,9156    ,437,437,437
BEGIN DESCRIPTION:
CHAMBERS CREEK 14.0
END DESCRIPTION:
XS GIS Cut Line= 3
      3813567.86     10160011.09      3813858.37     10160328.24
      3814117.87     10160411.08
#Sta/Elev= 30
  4569.9  257.21  4654.7  252.65  4768.1  248.65  4796.5  248.19  4824.9  248.31
  4831.6  248.88  4853.2  248.68  4867.4  247.71  4881.6   247.8  4895.3  247.02
  4902.6  245.46  4909.3  241.71  4916.7  242.06  4923.5   246.5  4937.7  246.81
  4945.1  246.21  4954.5  246.32  4966.1  246.92  4973.5  246.57  4987.7  244.67
  4992.7  240.61  5002.4  241.44  5009.9  244.75  5020.4  246.89    5031  248.29
  5055.2  249.62  5122.3  254.67  5159.7  256.46  5240.9   261.7  5272.4  263.01
#Mann= 5 ,-1 , 0
  4569.9     .11       0  4954.5     .17       0  4973.5     .09       0
  5020.4     .17       0  5055.2     .11       0
#XS Ineff= 2 , 0
       0  4831.6  248.88               0
Permanent Ineff=
       F       F
Bank Sta=4973.5,5020.4
XS Rating Curve= 0 ,0
Exp/Cntr=0.3,0.1

Type RM Length L Ch R = 1 ,8719    ,488,488,488
BEGIN DESCRIPTION:
CHAMBERS CREEK 13.0
END DESCRIPTION:
XS GIS Cut Line= 3
      3813377.24     10160281.76      3813552.87     10160558.78
      3813842.55     10160841.25
#Sta/Elev= 30
    4672  252.59    4795  246.58  4816.2   246.1  4831.5  244.52  4846.7  243.83
  4898.8  243.52  4925.5  243.73  4931.7  242.18  4944.8  243.68  4977.2  243.72
  4983.1  243.07  4996.4  237.73  4996.6  237.23  5005.2  237.86  5012.2  242.29
  5019.4  243.32  5040.5  243.23  5061.8  244.38  5174.8   246.3  5217.2  248.12
  5224.4  249.38  5231.4  249.24  5238.5  250.59  5245.5  250.52  5252.7   251.6
  5344.5  254.52  5351.7  254.11  5372.8  255.02  5394.1  254.85  5404.6  255.38
#Mann= 5 ,-1 , 0
    4672     .11       0  4898.8     .15       0  4944.8     .11       0
  4977.2     .07       0  5019.4     .11       0
Bank Sta=4977.2,5019.4
XS Rating Curve= 0 ,0
Exp/Cntr=0.3,0.1

Type RM Length L Ch R = 1 ,8231    ,216,216,216
BEGIN DESCRIPTION:
CHAMBERS CREEK 12.0
END DESCRIPTION:
XS GIS Cut Line= 3
      3813150.91     10160403.08      3813291.19     10160709.49
      3813595.27     10161027.09
#Sta/Elev= 30
    4663  254.23  4704.8  252.47  4741.5  250.06  4783.4  248.17    4816  246.18
  4943.1  241.07  4954.1  241.06  4959.6  241.49  4977.1  241.16  4982.6  237.54
  4996.1  234.58  4996.4  234.08  4999.9  234.08  5000.1  234.58    5013  237.49
  5019.9  239.97  5027.1  241.31  5041.3  240.85  5076.5  241.11  5093.9  240.57
  5112.1   240.6  5210.8  244.59    5218  244.44    5225  245.24  5232.2  245.31
  5253.3  246.94  5274.6  247.42    5303  248.83  5380.6  253.79  5439.7  256.39
#Mann= 6 ,-1 , 0
    4663     .11       0  4783.4     .15       0  4943.1     .17       0
  4977.1     .09       0  5027.1     .17       0  5093.9     .11       0
Bank Sta=4977.1,5027.1
XS Rating Curve= 0 ,0
Exp/Cntr=0.3,0.1

Type RM Length L Ch R = 1 ,8015    ,373,373,373
BEGIN DESCRIPTION:
Mapping XS be03fa49
END DESCRIPTION:
XS GIS Cut Line= 3
      3813088.42     10160403.13      3813159.68     10160863.14
      3813509.42     10161266.14
#Sta/Elev= 30
  4534.5  255.36  4781.2  244.74  4786.7  244.55  4886.8  241.57  4927.1  241.03
  4953.9  239.77  4967.5  240.37  4977.7  239.72  4987.8  236.22  4994.7  233.06
    5000  233.56  5004.4  235.87  5018.6  240.08    5068   239.3  5082.2  238.56
  5089.9     237  5096.5  236.48  5117.3  238.93    5139  239.58  5231.3  242.36
  5245.6  243.61    5295  245.63  5309.2  245.31  5358.6  246.99  5366.2  246.25
  5372.8  247.17  5380.4  246.04  5407.9  248.38  5450.7  250.14  5533.6  256.61
#Mann= 7 ,-1 , 0
  4534.5     .11       0  4781.2     .15       0  4786.7     .11       0
  4886.8     .17       0  4977.7     .09       0  5018.6     .17       0
    5139     .11       0
Bank Sta=4977.7,5018.6
XS Rating Curve= 0 ,0
Exp/Cntr=0.3,0.1

Type RM Length L Ch R = 1 ,7642    ,190,190,190
BEGIN DESCRIPTION:
CHAMBERS CREEK 11.0
END DESCRIPTION:
XS GIS Cut Line= 3
      3813019.37     10160399.54      3812966.64     10160928.77
      3813313.87     10161384.64
#Sta/Elev= 30
  4251.6  255.32  4317.9     254  4470.8  248.64  4544.6  245.82  4554.6  246.01
  4564.7  245.14  4677.1  241.86  4705.4  240.48  4755.6  239.76  4765.7  239.01
    4788  239.41  4872.1   238.4  4878.4  239.07  4907.5  237.27  4978.2  237.58
  4992.8  231.56    4998  230.38  4998.3  229.88  5001.8  229.88    5002  230.38
  5007.3  231.62  5013.6  236.06  5028.1  237.67  5076.2  238.08  5107.1  238.44
  5142.4  240.42  5150.7  241.18  5177.8  246.02  5242.2  251.05  5356.5   255.7
#Mann= 6 ,-1 , 0
  4251.6     .11       0  4470.8     .15       0  4677.1     .17       0
  4978.2     .09       0  5028.1     .17       0  5076.2     .11       0
#XS Ineff= 2 , 0
       0  4963.7   237.9               0
Permanent Ineff=
       F       F
Bank Sta=4978.2,5028.1
XS Rating Curve= 0 ,0
Exp/Cntr=0.3,0.1

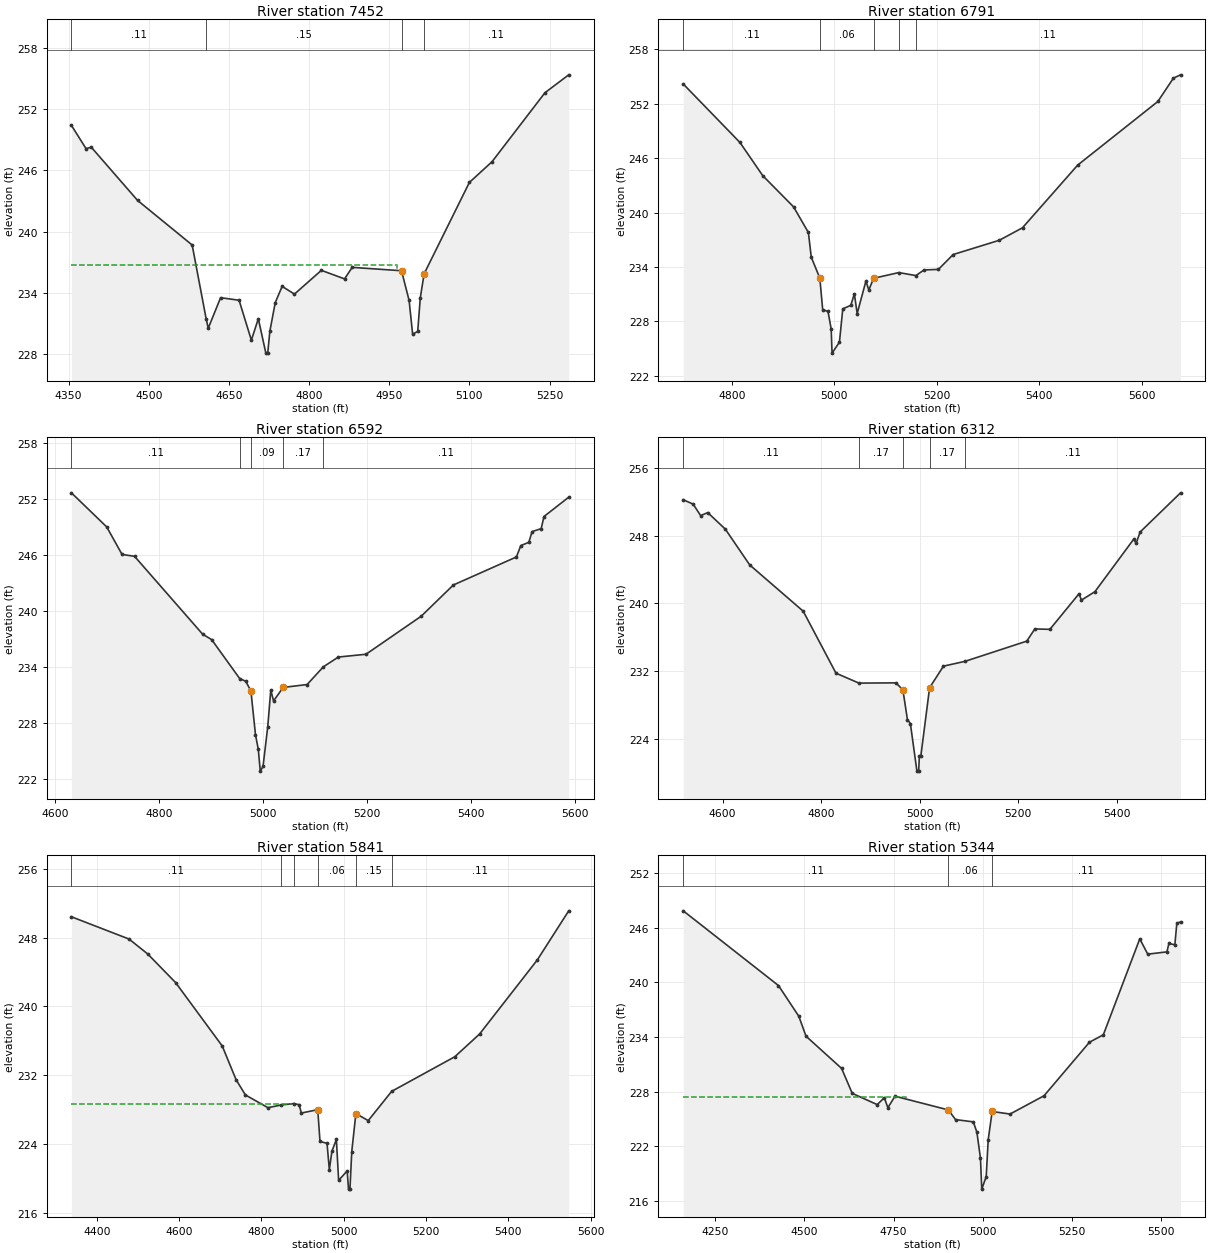
Type RM Length L Ch R = 1 ,7452    ,661,661,661
BEGIN DESCRIPTION:
Mapping XS f9e1727e
END DESCRIPTION:
XS GIS Cut Line= 4
      3812495.52     10160904.48      3812910.08     10161141.68
      3813018.27     10161269.13      3813215.99     10161475.64
#Sta/Elev= 30
  4355.2   250.4  4382.6  248.12  4392.4  248.26    4479  243.05  4581.2  238.68
  4607.5  231.42  4611.3  230.53  4634.4  233.52    4669  233.27    4692  229.36
    4705  231.46  4719.1  228.09  4722.6  228.09  4726.6  230.24  4736.7  233.04
  4749.6  234.63  4772.6  233.87    4823   236.2  4866.4  235.36  4880.7  236.49
    4973  236.16  4987.2  233.25  4993.8  229.95  5003.3  230.21  5008.1   233.5
  5015.3  235.86    5100  244.81  5142.4  246.84  5241.5   253.6  5285.9  255.35
#Mann= 4 ,-1 , 0
  4355.2     .11       0  4607.5     .15       0    4973     .06       0
  5015.3     .11       0
#XS Ineff= 2 , 0
       0  4965.2  236.71               0
Permanent Ineff=
       T       F
Bank Sta=4973,5015.3
XS Rating Curve= 0 ,0
Exp/Cntr=0.3,0.1

Type RM Length L Ch R = 1 ,6791    ,199,199,199
BEGIN DESCRIPTION:
CHAMBERS CREEK 10.0
END DESCRIPTION:
XS GIS Cut Line= 3
      3812296.04     10161134.92       3812558.9     10161268.61
      3813167.81     10161561.05
#Sta/Elev= 30
  4705.1  254.18  4815.8  247.73  4860.3  244.07  4920.3  240.64  4949.3  237.81
  4954.9  235.09  4971.6  232.78  4977.2  229.31  4987.6   229.1  4993.8  227.16
  4995.5  224.51  5009.9  225.72  5016.4  229.39  5032.1  229.78    5039  231.05
  5044.5  228.87  5061.6  232.46  5067.2  231.46  5076.5  232.76  5125.7  233.39
  5159.1  233.06  5174.9  233.68    5203  233.74  5231.8  235.38  5321.8  236.95
  5367.1  238.33  5474.8  245.24  5631.2  252.25  5661.5  254.82  5675.5  255.19
#Mann= 5 ,-1 , 0
  4705.1     .11       0  4971.6     .06       0  5076.5     .15       0
  5125.7     .17       0  5159.1     .11       0
Bank Sta=4971.6,5076.5
XS Rating Curve= 0 ,0
Exp/Cntr=0.3,0.1

Type RM Length L Ch R = 1 ,6592    ,280,280,280
BEGIN DESCRIPTION:
Mapping XS f2bde15e
END DESCRIPTION:
XS GIS Cut Line= 3
      3812247.71     10161301.35      3812589.47     10161440.24
      3813132.99     10161665.88
#Sta/Elev= 30
  4631.1  252.69  4699.1  249.03  4728.6  246.08  4752.6  245.88  4883.8  237.52
  4901.1  236.94  4955.1  232.76  4966.8  232.47  4976.7  231.42  4985.5  226.73
  4990.9  225.17  4994.7  222.83    5000  223.33  5009.1   227.6  5014.9  231.52
  5020.3  230.36  5038.7  231.81  5084.9  232.12  5116.1  234.02    5145  235.07
  5198.2  235.37  5304.5  239.45  5366.4   242.8  5487.8  245.81  5496.3  247.03
  5511.7  247.38    5518  248.53  5535.5  248.85  5540.9  250.15  5588.5  252.22
#Mann= 5 ,-1 , 0
  4631.1     .11       0  4955.1     .17       0  4976.7     .09       0
  5038.7     .17       0  5116.1     .11       0
Bank Sta=4976.7,5038.7
XS Rating Curve= 0 ,0
Exp/Cntr=0.3,0.1

Type RM Length L Ch R = 1 ,6312    ,471,471,471
BEGIN DESCRIPTION:
CHAMBERS CREEK 9.0
END DESCRIPTION:
XS GIS Cut Line= 3
      3812196.25     10161414.89      3812598.23     10161676.84
      3813118.53     10161772.95
#Sta/Elev= 30
  4520.2  252.22  4540.3  251.71  4555.5  250.35  4569.9  250.71  4605.7  248.75
    4655  244.54  4763.6  239.08  4830.1  231.77  4876.6   230.6  4951.8  230.63
  4965.8   229.8    4975   226.3    4981  225.83  4994.3  220.22  4997.8  220.22
  4999.3  222.04  5002.3  222.04    5020  230.06  5048.1   232.6    5092  233.17
  5217.1  235.55  5233.5  236.99    5264  236.94    5323  241.13  5328.1  240.39
  5355.5  241.39    5434  247.57  5439.1  247.09  5447.1  248.42  5529.1  253.04
#Mann= 5 ,-1 , 0
  4520.2     .11       0  4876.6     .17       0  4965.8     .09       0
    5020     .17       0    5092     .11       0
Bank Sta=4965.8,5020
XS Rating Curve= 0 ,0
Exp/Cntr=0.3,0.1

Type RM Length L Ch R = 1 ,5841    ,497,497,497
BEGIN DESCRIPTION:
CHAMBERS CREEK 8.0
END DESCRIPTION:
XS GIS Cut Line= 3
      3812161.96     10161480.39      3812448.23     10162076.84
      3812994.08       10162043.
#Sta/Elev= 30
  4338.4  250.41  4478.5  247.82  4523.8  246.09  4591.7  242.76  4704.9   235.4
  4738.7  231.47  4761.3  229.71  4816.1  228.23  4848.5  228.55  4878.6  228.71
  4891.7  228.58  4897.2  227.61    4937     228  4942.5  224.31  4959.6  224.09
  4965.2  221.02  4971.4  223.16  4982.3  224.54  4987.8  219.79  5008.6  220.89
  5011.8  218.77  5015.3  218.77  5019.7  223.14  5029.7  227.55  5059.7  226.73
  5116.7  230.13  5270.1  234.15  5330.3  236.79  5470.5  245.39  5546.9   251.1
#Mann= 6 ,-1 , 0
  4338.4     .11       0  4848.5     .15       0  4878.6     .11       0
    4937     .06       0  5029.7     .15       0  5116.7     .11       0
#XS Ineff= 2 , 0
       0  4874.6  228.71               0
Permanent Ineff=
       F       F
Bank Sta=4937,5029.7
XS Rating Curve= 0 ,0
Exp/Cntr=0.3,0.1

Type RM Length L Ch R = 1 ,5344    ,471,471,471
BEGIN DESCRIPTION:
CHAMBERS CREEK 7.0
END DESCRIPTION:
XS GIS Cut Line= 3
      3812070.37     10161486.48      3812078.23     10162326.84
      3812328.61     10162823.28
#Sta/Elev= 30
  4159.6  247.87    4427  239.66  4484.2  236.28  4504.2   234.1  4604.2  230.56
  4634.2  227.81  4704.2  226.58  4724.2  227.33  4734.2  226.24  4754.2   227.5
  4904.2  225.99  4924.2  224.93  4974.2  224.68  4984.2  223.53  4994.2  220.68
  4997.8  217.29  5010.3  218.66  5015.9  222.71    5027  225.82  5077.2  225.54
  5172.7  227.55  5300.2  233.43  5339.2  234.25  5441.5  244.79  5463.9  243.11
  5517.7  243.36  5523.3  244.28    5540  244.14  5545.6  246.51    5556  246.65
#Mann= 3 , 0 , 0
  4159.6     .11       0  4904.2     .06       0    5027     .11       0
#XS Ineff= 2 , 0
       0  4784.2   227.4               0
Permanent Ineff=
       F       F
Bank Sta=4904.2,5027
XS Rating Curve= 0 ,0
Exp/Cntr=0.3,0.1

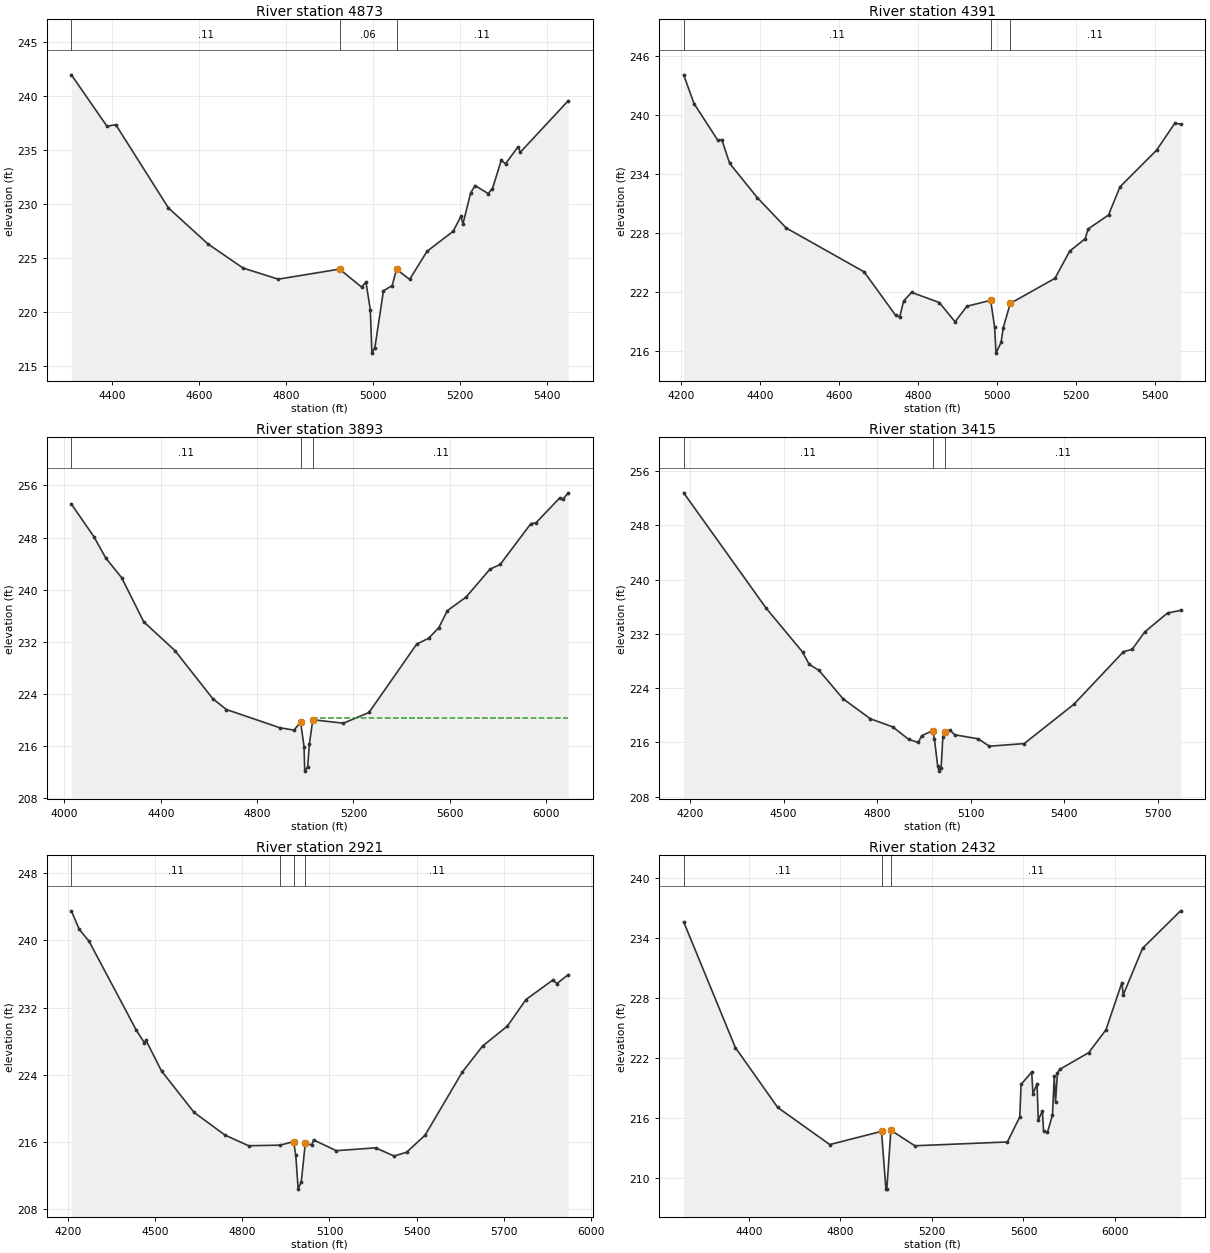
Type RM Length L Ch R = 1 ,4873    ,482,482,482
BEGIN DESCRIPTION:
CHAMBERS CREEK 6.0
END DESCRIPTION:
XS GIS Cut Line= 3
      3811655.87     10161759.93      3811748.23     10162446.84
      3811714.47     10162894.87
#Sta/Elev= 30
  4306.9  241.97  4388.8  237.21    4409  237.36    4530  229.66  4620.8  226.33
  4701.6   224.1  4782.3  223.07  4923.5     224    4974  222.34  4984.1   222.8
  4994.2  220.23  4997.8  216.23  5004.6  216.73  5024.3  221.99  5044.4  222.48
  5054.4  223.98  5084.5  223.05  5124.6  225.65  5184.7   227.5  5202.2  228.87
  5207.2   228.2  5224.9  231.05  5234.9  231.73    5265  230.99    5275  231.45
  5295.1  234.05  5305.1  233.75    5334  235.32    5339  234.81  5449.3  239.58
#Mann= 3 , 0 , 0
  4306.9     .11       0  4923.5     .06       0  5054.4     .11       0
Bank Sta=4923.5,5054.4
XS Rating Curve= 0 ,0
Exp/Cntr=0.3,0.1

Type RM Length L Ch R = 1 ,4391    ,498,498,498
BEGIN DESCRIPTION:
CHAMBERS CREEK 5.0
END DESCRIPTION:
XS GIS Cut Line= 3
      3811349.89     10161744.74      3811328.23     10162536.84
      3811517.86     10162961.09
#Sta/Elev= 30
  4207.6  244.13  4233.9   241.2    4294  237.47    4304  237.54    4324  235.12
    4394  231.63    4467  228.55  4664.1  224.09  4744.1  219.65  4754.1   219.5
  4764.1  221.12  4784.1     222  4854.2  220.97  4894.2  219.01  4924.2  220.59
  4984.2  221.19  4994.2  218.51  4997.8  215.82  5010.7  216.93  5016.2  218.42
  5033.9  220.88    5147  223.43  5184.1  226.19  5223.7  227.47  5230.5  228.44
  5282.4  229.87  5311.3  232.73  5403.9  236.46  5450.3  239.21  5464.7  239.11
#Mann= 3 , 0 , 0
  4207.6     .11       0  4984.2     .06       0  5033.9     .11       0
Bank Sta=4984.2,5033.9
XS Rating Curve= 0 ,0
Exp/Cntr=0.3,0.1

Type RM Length L Ch R = 1 ,3893    ,478,478,478
BEGIN DESCRIPTION:
CHAMBERS CREEK 4.0
END DESCRIPTION:
XS GIS Cut Line= 3
      3810317.83     10161811.04      3810888.23     10162596.84
      3811667.84     10163361.06
#Sta/Elev= 30
    4029  253.14  4122.2  248.14  4172.4  244.81  4237.4  241.84  4329.4  235.04
  4459.2   230.6  4616.2  223.21  4672.6  221.55  4894.4  218.75  4953.2  218.38
  4980.5  219.62  4994.9  215.84  4997.6  212.08  5009.8  212.71  5016.8  216.19
    5031  219.98  5158.3  219.45  5264.4   221.1  5462.3   231.6  5511.9  232.51
  5554.3  234.14  5589.6  236.75  5667.5  238.84  5766.5  243.13  5808.9  243.85
  5936.2  250.13  5957.3  250.25  6056.4   254.1  6070.5  253.93  6091.7  254.87
#Mann= 3 , 0 , 0
    4029     .11       0  4980.5     .06       0    5031     .11       0
#XS Ineff= 2 , 0
       0                  5038.1       0  220.22
Permanent Ineff=
       F       F
Bank Sta=4980.5,5031
XS Rating Curve= 0 ,0
Exp/Cntr=0.3,0.1

Type RM Length L Ch R = 1 ,3415    ,494,494,494
BEGIN DESCRIPTION:
CHAMBERS CREEK 3.0
END DESCRIPTION:
XS GIS Cut Line= 3
      3810267.85     10161861.08      3810468.23     10162656.84
      3810799.99     10163354.92
#Sta/Elev= 30
  4179.4  252.79    4444  235.79  4560.9  229.32  4581.6  227.53  4613.5  226.62
  4690.6  222.44  4777.9   219.5  4849.7   218.3  4901.2  216.46    4932     216
  4942.5     217  4978.3  217.75  4983.7  216.47    4994  212.52  4997.4  212.28
  4997.7  211.78  5005.1  212.28  5010.5  216.75    5016   217.6  5033.2  217.83
    5049  217.13  5124.1  216.54  5159.7  215.45  5271.5  215.84  5430.5  221.62
  5589.6  229.37  5617.8  229.73  5657.7  232.28  5731.4  235.09  5772.9  235.46
#Mann= 3 , 0 , 0
  4179.4     .11       0  4978.3     .06       0    5016     .11       0
Bank Sta=4978.3,5016
XS Rating Curve= 0 ,0
Exp/Cntr=0.3,0.1

Type RM Length L Ch R = 1 ,2921    ,489,489,489
BEGIN DESCRIPTION:
CHAMBERS CREEK 2.0
END DESCRIPTION:
XS GIS Cut Line= 3
      3810167.85     10162011.11      3810028.23     10162786.84
      3810733.44     10163380.47
#Sta/Elev= 30
  4211.8  243.54  4238.6  241.35  4272.7   239.9  4435.3  229.29  4463.3  227.77
  4468.3   228.1    4522  224.42  4634.3  219.47  4740.1  216.78  4821.4   215.5
  4930.5  215.57  4976.4  215.99    4984  214.37  4992.2  210.32    5003  211.21
  5016.7  215.78  5038.7   215.6  5045.3  216.19  5123.4  214.91  5258.6  215.25
  5322.3  214.27  5365.2  214.72    5429  216.76  5556.4  224.26  5626.9   227.4
  5712.5  229.79  5776.2  232.95  5868.6  235.28  5882.9  234.86  5921.8  235.93
#Mann= 4 ,-1 , 0
  4211.8     .11       0  4930.5     .15       0  4976.4     .09       0
  5016.7     .11       0
Bank Sta=4976.4,5016.7
XS Rating Curve= 0 ,0
Exp/Cntr=0.3,0.1

Type RM Length L Ch R = 1 ,2432    ,934,934,934
BEGIN DESCRIPTION:
CHAMBERS CREEK 1.0
END DESCRIPTION:
XS GIS Cut Line= 4
      3809952.33     10162090.21      3809546.07     10162836.76
      3809559.95     10162899.26      3810709.68     10163408.72
#Sta/Elev= 30
  4115.1  235.59  4341.1  223.03  4525.9  217.06  4753.6  213.35  4979.7  214.67
  4998.9   208.9  5002.8   208.9  5020.7  214.78  5125.3  213.23  5529.9  213.61
    5584  216.12  5589.5  219.35    5636  220.59  5641.5  218.42  5659.3  219.41
  5664.8  215.79  5682.6  216.71  5688.1  214.68  5704.9  214.58  5726.8   216.3
  5734.6  220.23  5740.1   217.6  5748.6  220.49  5757.9  220.85  5885.2  222.53
  5960.6  224.81  6030.4  229.53  6035.9  228.29  6120.5  232.95  6286.6  236.69
#Mann= 3 , 0 , 0
  4115.1     .11       0  4979.7     .06       0  5020.7     .11       0
#Block Obstruct= 2 , 0
       0                    5636       0  220.59
Bank Sta=4979.7,5020.7
XS Rating Curve= 0 ,0
Exp/Cntr=0.3,0.1

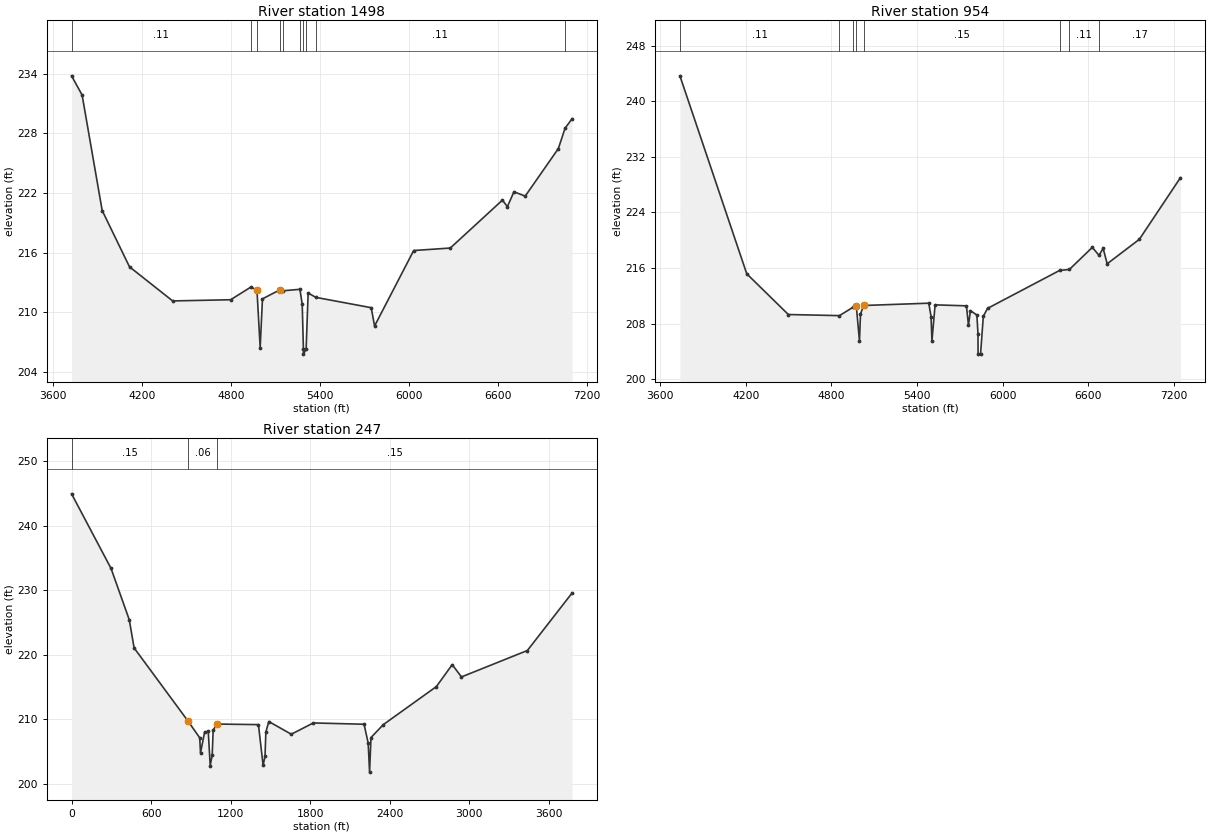
Type RM Length L Ch R = 1 ,1498    ,544,544,544
BEGIN DESCRIPTION:
CHAMBERS CREEK 2.5
END DESCRIPTION:
XS GIS Cut Line= 3
      3809467.87     10162011.04      3808651.91     10162990.36
      3807748.47     10164884.54
#Sta/Elev= 30
  3725.3  233.77  3796.3  231.84  3931.7  220.22  4115.8  214.56  4406.8  211.13
  4797.3  211.25  4934.5  212.53  4974.9  212.21  4996.5  206.44  5011.9  211.34
  5132.7  212.27    5149  212.15  5264.4   212.3  5279.9  210.79    5288  206.28
  5288.5  205.78  5306.2  206.28  5319.8  211.93  5371.3  211.49  5744.9  210.45
  5767.6  208.61  6031.2   216.2  6277.9  216.45  6629.4  221.27  6662.7  220.61
    6707  222.11  6782.7  221.67  7006.1  226.45  7051.3  228.49  7098.6  229.46
#Mann= 10 ,-1 , 0
  3725.3     .11       0  4934.5     .15       0  4974.9     .07       0
  5132.7     .15       0    5149     .17       0  5264.4     .15       0
    5288     .09       0  5306.2     .15       0  5371.3     .11       0
  7051.3     .17       0
Bank Sta=4974.9,5132.7
XS Rating Curve= 0 ,0
Exp/Cntr=0.3,0.1

Type RM Length L Ch R = 1 ,954     ,707,707,707
BEGIN DESCRIPTION:
CHAMBERS CREEK 1.5
END DESCRIPTION:
XS GIS Cut Line= 3
      3809267.87     10161811.05      3808327.32      10162593.7
      3807327.48     10164645.79
#Sta/Elev= 30
  3738.7  243.65  4207.1  215.16  4498.4   209.3  4856.3  209.14    4953  210.36
  4974.3  210.58  4996.8  205.49  5003.9  209.37  5026.1   210.6  5482.2  210.93
  5498.2  209.01  5504.4  205.51  5526.7  210.69  5746.2  210.55  5760.3  207.77
  5774.3  209.85  5819.3  209.23    5827  206.53  5827.7   203.6  5844.9   203.6
  5864.4  209.05  5893.8  210.18  6398.6  215.64  6467.2  215.78  6627.9  218.96
  6674.8  217.82  6703.9  218.82    6732   216.6  6957.4  220.12    7245  228.98
#Mann= 8 ,-1 , 0
  3738.7     .11       0  4856.3     .15       0    4953     .17       0
  4974.3     .09       0  5026.1     .15       0  6398.6     .17       0
  6467.2     .11       0  6674.8     .17       0
Bank Sta=4974.3,5026.1
XS Rating Curve= 0 ,0
Exp/Cntr=0.3,0.1

Type RM Length L Ch R = 1 ,247     ,0,0,0
XS GIS Cut Line= 4
      3808667.85     10161211.07      3808120.45     10162105.58
      3807703.01     10162626.35       3807166.8     10164617.64
#Sta/Elev= 30
       0  244.97     298  233.39   435.4  225.44   472.1  221.06   879.3   209.7
   967.2  207.12   973.2  204.79  1004.1  207.98  1031.7  208.11  1046.4   202.8
  1061.5  204.44  1068.6  208.29  1096.7  209.25  1410.4  209.16  1445.6  202.85
    1460  204.22  1466.4  208.01  1488.8  209.64  1658.5  207.67  1824.6  209.42
  2207.8  209.22  2238.8  206.29  2249.2  201.79    2260  207.16  2352.8  209.16
  2753.3  215.06  2873.1  218.47  2942.7  216.56  3440.2  220.66  3777.5  229.58
#Mann= 3 , 0 , 0
       0     .15       0   879.3     .06       0  1096.7     .15       0
Bank Sta=879.3,1096.7
XS Rating Curve= 0 ,0
Exp/Cntr=0.3,0.1

Chan Stop Cuts=-1
Use User Specified Reach Order=0
Composite Channel Slope=5