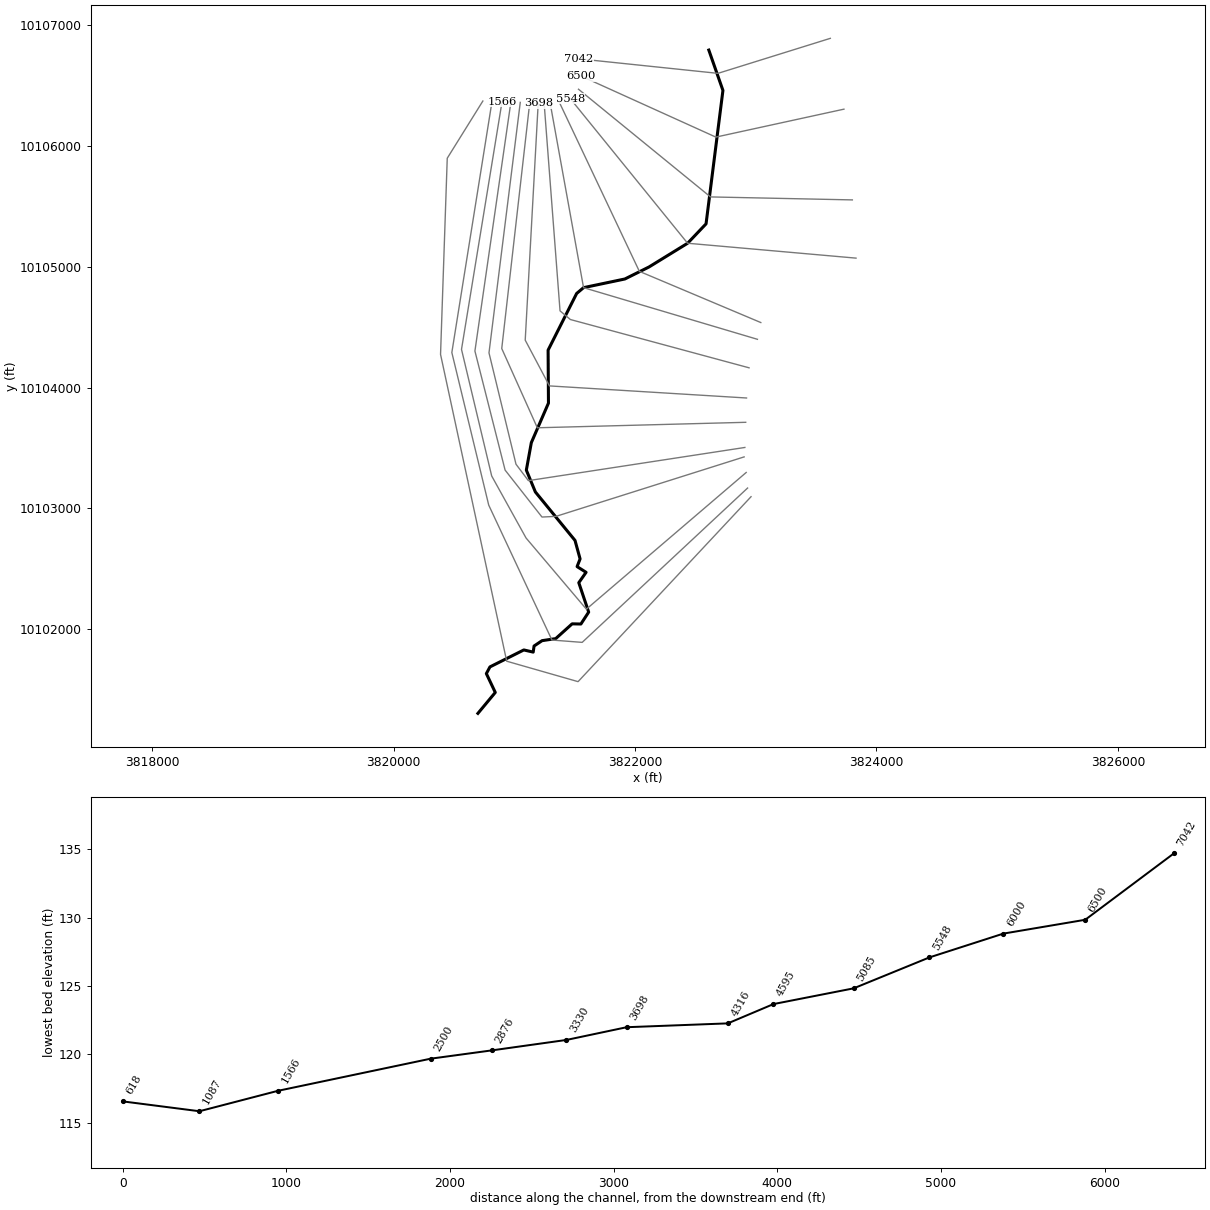
--- Conroe Lake 001.prj (project) ---

Proj Title=Conroe Lake 001 Base Level Engineering
Current Plan=p01
Default Exp/Contr=0.3,0.1
English Units
Geom File=g01
Flow File=f01
Flow File=f02
Plan File=p01
Y Axis Title=Elevation
X Axis Title(PF)=Main Channel Distance
X Axis Title(XS)=Station
BEGIN DESCRIPTION:
Conroe Lake 001
END DESCRIPTION:
DSS File=dss
DSS Export Rating Curves= 0
DSS Export Rating Curve Sorted= 0
DSS Export Volume Flow Curves= 0
DXF OffsetX= 0
DXF OffsetY= 0
DXF ScaleX= 1
DXF ScaleY= 10

--- Conroe Lake 001.p01 (plan) ---

Plan Title=Multiple Run
Program Version=4.10
Short Identifier=Multiple Run
Geom File=g01
Flow File=f01
Subcritical Flow
K Sum by GR= 0
Std Step Tol= 0.01
Critical Tol= 0.01
Num of Std Step Trials= 20
Max Error Tol= 0.3
Flow Tol Ratio= 0.001
Split Flow NTrial= 30
Split Flow Tol= 0.02
Split Flow Ratio= 0.02
Log Output Level= 0
Friction Slope Method= 1
Unsteady Friction Slope Method= 2
Unsteady Bridges Friction Slope Method= 1
Parabolic Critical Depth
Global Vel Dist= 1 , 1 , 1
Global Log Level= 0
CheckData=True
Encroach Param=-1 ,0,0, 0
BEGIN DESCRIPTION:
Multiple Run
END DESCRIPTION:
Computation Interval=1HOUR
Output Interval=1HOUR
Run HTab= 0
Run UNet= 0
Run PostProcess= 0
Run WQNet= 0
UNET Theta= 1
UNET Theta Warmup= 1
UNET ZTol= 0.02
UNET ZSATol= 0.05
UNET MxIter= 20
UNET MaxInSteps= 0
UNET DtIC= 0
UNET DtMin= 0
UNET MaxCRTS= 20
UNET WFStab= 2
UNET SFStab= 1
UNET WFX= 1
UNET SFX= 1
UNET DSS MLevel= 4
UNET DZMax Abort= 100
UNET Convert EG Bridges= 0
UNET Use Existing IB Tables=-1
UNET Froude Reduction=False
UNET Froude Limit= 1
UNET Froude Power= 10
UNET Time Slicing=0,0, 5
UNET Junction Losses=0
Instantaneous Interval=1HOUR
DSS File=dss
Write IC File= 0
Write IC File at Sim End=0
Echo Input=False
Echo Parameters=False
Echo Output=False
Write Detailed= 0
WQ AD Non Conservative
WQ ULTIMATE=-1
WQ Max Comp Step=1HOUR
WQ Output Interval=15MIN
WQ Output Selected Increments= 0
WQ Output face flow=0
WQ Output face velocity=0
WQ Output face area=0
WQ Output face dispersion=0
WQ Output cell volume=0
WQ Output cell surface area=0
WQ Output cell continuity=0
WQ Output cumulative cell continuity=0
WQ Output face conc=0
WQ Output face dconc_dx=0
WQ Output face courant=0
WQ Output face peclet=0
WQ Output face adv mass=0
WQ Output face disp mass=0
WQ Output cell mass=0
WQ Output cell source sink temp=0
WQ Output cell source sink nsm=0
WQ Output MaxMinRange=-1
WQ Daily Max Min Mean=-1
WQ Daily Range=0
WQ Daily Time=0
WQ Create Restart=0
WQ Fixed Restart=0
WQ System Summary=0
WQ Use Fixed Temperature=0
Sorting and Armoring Iterations= 10
XS Update Threshold= 0.02
Hydraulics Update Threshold= 0.02
Energy Slope Method= 1
Volume Change Method= 0
XS Weighting Method= 0
Number of US Weighted Cross Sections= 1
Number of DS Weighted Cross Sections= 1
Upstream XS Weight=0.25
Main XS Weight=0.5
Downstream XS Weight=0.25
Number of DS XS's Weighted with US Boundary= 1
Upstream Boundary Weight= 1
Weight of XSs Associated with US Boundary= 0
Number of US XS's Weighted with DS Boundary= 1
Downstream Boundary Weight= 0.5
Weight of XSs Associated with DS Boundary= 0.5
Sediment Output Level= 4
Mass or Volume Output= 0
Output Increment Type= 1
Profile and TS Output Increment= 10
XS Output Flag= 0
XS Output Increment= 10
Disregard all LS=0
Disregard all Conn=0
Disregard all Breaches=0
Disregard all Pumps=0

--- Conroe Lake 001.f01 (steady flow) ---

Flow Title=Multiple
Program Version=4.10
Number of Profiles= 7
Profile Names=10-year,25-year,50-year,1pct_min,100-year,1pct_plu,500-year
River Rch & RM=Conroe Lake 001,Reach-1         ,7042
     624     838    1126     498    1504    4542    2771
River Rch & RM=Conroe Lake 001,Reach-1         ,6000
     753    1025    1389     620    1871    5650    3507
River Rch & RM=Conroe Lake 001,Reach-1         ,3330
     813    1106    1500     668    2018    6094    3777
Boundary for River Rch & Prof#=Conroe Lake 001,Reach-1         , 1
Up Type= 0
Dn Type= 3
Dn Slope=0.005
Boundary for River Rch & Prof#=Conroe Lake 001,Reach-1         , 2
Up Type= 0
Dn Type= 3
Dn Slope=0.005
Boundary for River Rch & Prof#=Conroe Lake 001,Reach-1         , 3
Up Type= 0
Dn Type= 3
Dn Slope=0.005
Boundary for River Rch & Prof#=Conroe Lake 001,Reach-1         , 4
Up Type= 0
Dn Type= 3
Dn Slope=0.005
Boundary for River Rch & Prof#=Conroe Lake 001,Reach-1         , 5
Up Type= 0
Dn Type= 3
Dn Slope=0.005
Boundary for River Rch & Prof#=Conroe Lake 001,Reach-1         , 6
Up Type= 0
Dn Type= 3
Dn Slope=0.005
Boundary for River Rch & Prof#=Conroe Lake 001,Reach-1         , 7
Up Type= 0
Dn Type= 3
Dn Slope=0.005
DSS Import GetInterval= 0
DSS Import GetPeak= 0
DSS Import FillOption= 0

--- Conroe Lake 001.f02 (steady flow) ---

Flow Title=Orig_BLE_Flow
Program Version=4.10
Number of Profiles= 7
Profile Names=10-year,25-year,50-year,1pct_min,100-year,1pct_plu,500-year
River Rch & RM=Conroe Lake 001,Reach-1         ,7042
     624     822     979     383    1157    3494    1611
River Rch & RM=Conroe Lake 001,Reach-1         ,6000
     753    1005    1208     477    1439    4346    2039
River Rch & RM=Conroe Lake 001,Reach-1         ,3330
     813    1084    1304     514    1552    4688    2196
Boundary for River Rch & Prof#=Conroe Lake 001,Reach-1         , 1
Up Type= 0
Dn Type= 3
Dn Slope=0.005
Boundary for River Rch & Prof#=Conroe Lake 001,Reach-1         , 2
Up Type= 0
Dn Type= 3
Dn Slope=0.005
Boundary for River Rch & Prof#=Conroe Lake 001,Reach-1         , 3
Up Type= 0
Dn Type= 3
Dn Slope=0.005
Boundary for River Rch & Prof#=Conroe Lake 001,Reach-1         , 4
Up Type= 0
Dn Type= 3
Dn Slope=0.005
Boundary for River Rch & Prof#=Conroe Lake 001,Reach-1         , 5
Up Type= 0
Dn Type= 3
Dn Slope=0.005
Boundary for River Rch & Prof#=Conroe Lake 001,Reach-1         , 6
Up Type= 0
Dn Type= 3
Dn Slope=0.005
Boundary for River Rch & Prof#=Conroe Lake 001,Reach-1         , 7
Up Type= 0
Dn Type= 3
Dn Slope=0.005
DSS Import GetInterval= 0
DSS Import GetPeak= 0
DSS Import FillOption= 0

--- Conroe Lake 001.g01 (geometry) ---

Geom Title=Existing Conditions
Program Version=4.10

River Reach=Conroe Lake 001 ,Reach-1
Reach XY= 30
      3822611.66     10106795.55      3822728.65     10106461.32
      3822588.83     10105356.04      3822436.06     10105195.41
      3822116.73     10104999.07      3821916.29     10104899.33
      3821574.11     10104827.57      3821516.93     10104779.35
      3821280.51      10104310.2      3821283.47     10103871.19
      3821141.54     10103543.69      3821100.21     10103316.26
      3821175.11     10103135.13      3821503.38     10102733.77
      3821545.46     10102580.66      3821520.64     10102516.97
      3821595.03     10102469.65      3821534.75     10102383.68
      3821616.55     10102140.09       3821552.2     10102041.42
      3821479.54     10102042.79      3821343.49     10101920.44
      3821230.68     10101903.54      3821164.28     10101859.15
      3821157.11     10101808.69      3821079.29      10101826.6
      3820798.71     10101686.12      3820769.04      10101630.6
        3820843.     10101474.53      3820698.97      10101301.2

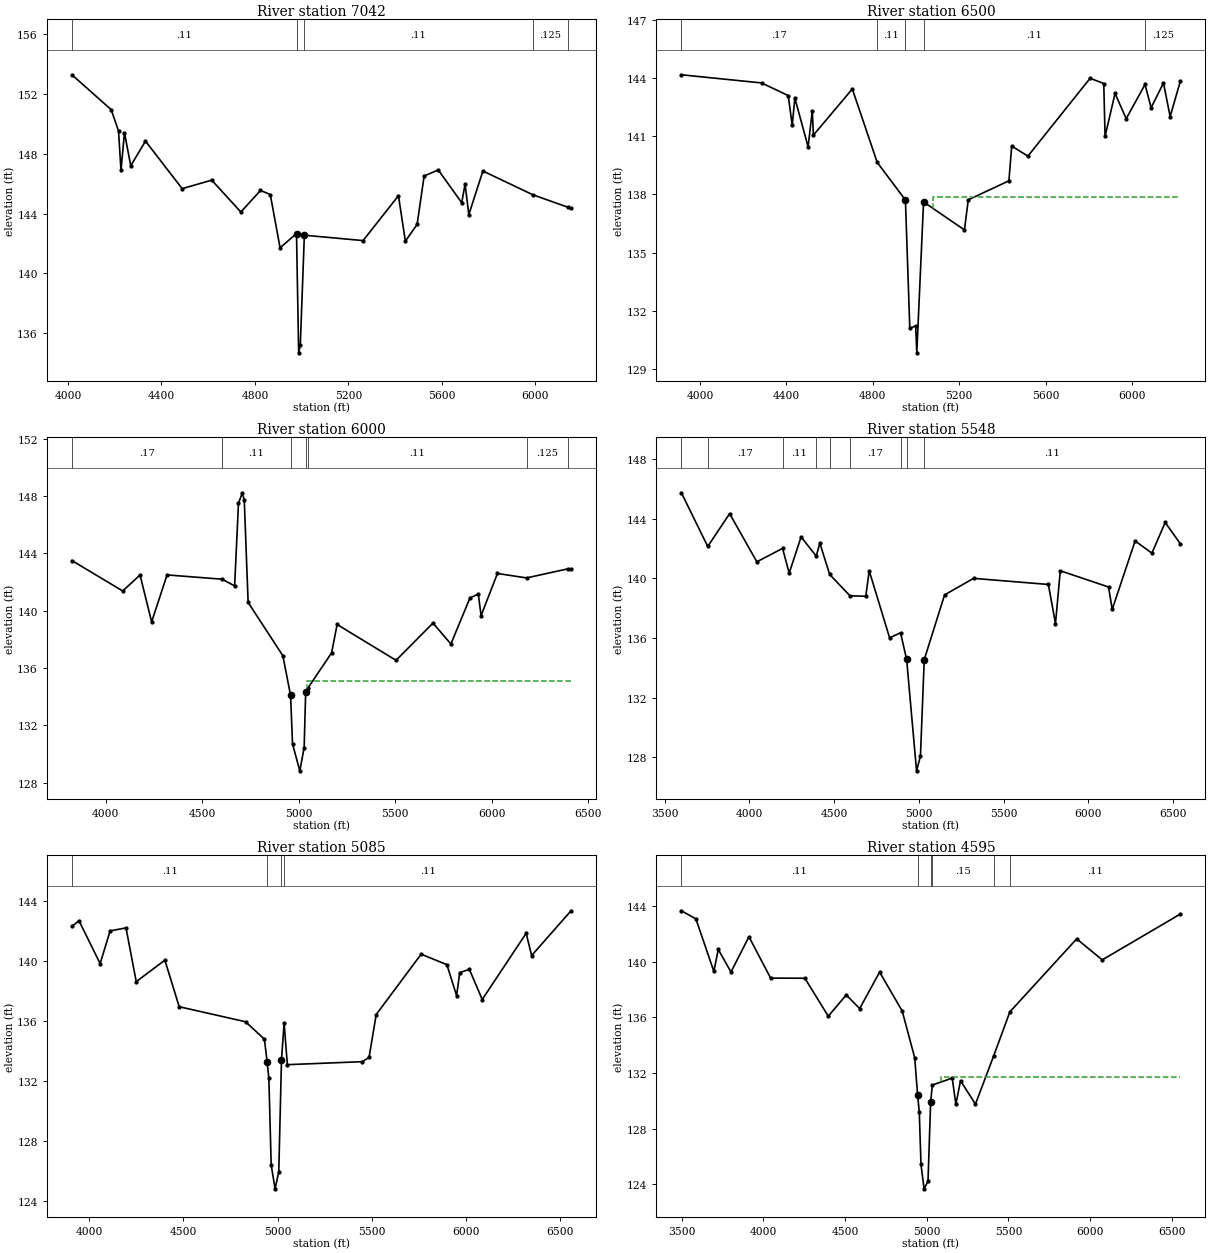
Type RM Length L Ch R = 1 ,7042    ,542,542,542
BEGIN DESCRIPTION:
Conroe Lake 001 11.0
END DESCRIPTION:
XS GIS Cut Line= 3
      3823618.26     10106892.74      3822687.44     10106602.62
       3821532.7     10106723.27
#Sta/Elev= 30
  4016.8  153.27  4184.8  150.94  4216.2  149.52  4226.7  146.88  4241.6   149.4
  4268.6  147.19  4331.5  148.84  4488.6  145.66    4615  146.23  4739.8   144.1
  4823.8  145.54  4865.7  145.27  4907.6  141.71  4977.9  142.66  4987.2  134.69
  4994.1  135.19  5011.5  142.55  5262.8  142.19  5414.3  145.19  5443.8  142.15
  5494.1  143.27  5524.2  146.51  5584.6  146.91  5685.1  144.72  5699.4  145.97
  5715.3  143.92  5775.6  146.84  5988.2  145.26    6141  144.41  6152.8  144.34
#Mann= 5 ,-1 , 0
  4016.8     .11       0  4977.9     .07       0  5011.5     .11       0
  5988.2    .125       0    6141     .11       0
Bank Sta=4977.9,5011.5
XS Rating Curve= 0 ,0
Exp/Cntr=0.3,0.1

Type RM Length L Ch R = 1 ,6500    ,500,500,500
BEGIN DESCRIPTION:
Conroe Lake 001 12.0
END DESCRIPTION:
XS GIS Cut Line= 3
      3823731.21     10106306.13      3822669.96     10106074.64
      3821554.33     10106579.88
#Sta/Elev= 30
  3913.8  144.16    4285  143.74  4408.5  143.09  4427.1  141.56  4439.2  142.96
  4500.6  140.45    4520  142.31  4525.1  141.05  4705.3  143.43  4820.5  139.65
  4951.2  137.71  4971.5   131.1  4998.5  131.23  5003.9  129.84  5035.2  137.61
  5224.5  136.17  5242.1  137.72  5430.4   138.7  5443.3  140.49  5518.3  139.97
  5806.3  143.98  5869.6  143.71  5875.6  140.99  5921.8   143.2  5973.5   141.9
  6060.6  143.66  6088.9  142.46  6146.1  143.74  6176.9  142.01  6224.7  143.85
#Mann= 5 ,-1 , 0
  3913.8     .17       0  4820.5     .11       0  4951.2     .07       0
  5035.2     .11       0  6060.6    .125       0
#XS Ineff= 2 , 0
       0                  5080.4       0  137.88
Permanent Ineff=
       F       F
Bank Sta=4951.2,5035.2
XS Rating Curve= 0 ,0
Exp/Cntr=0.3,0.1

Type RM Length L Ch R = 1 ,6000    ,452,452,452
BEGIN DESCRIPTION:
Conroe Lake 001 11.5
END DESCRIPTION:
XS GIS Cut Line= 3
      3823800.73     10105554.43      3822625.79     10105579.12
      3821532.27     10106471.13
#Sta/Elev= 30
  3824.8   143.5  4087.7  141.38  4177.8  142.49  4237.8  139.22  4317.8   142.5
  4603.4   142.2  4667.9  141.73  4687.9   147.5  4707.9  148.23  4717.9   147.7
  4737.9  140.58  4917.9  136.86  4957.9  134.09  4967.9  130.71  5005.7  128.83
  5028.2  130.45  5036.1  134.35    5049  134.63  5170.4  137.06  5199.1  139.04
  5504.3  136.54    5696  139.14  5788.6  137.68  5887.8   140.9  5930.8  141.16
  5945.1  139.66  6029.9   142.6  6180.6  142.29  6394.2  142.92  6411.2  142.89
#Mann= 7 ,-1 , 0
  3824.8     .17       0  4603.4     .11       0  4957.9     .07       0
  5036.1     .11       0    5049     .11       0  6180.6    .125       0
  6394.2     .11       0
#XS Ineff= 2 , 0
       0                  5042.6       0  135.11
Permanent Ineff=
       F       F
Bank Sta=4957.9,5036.1
XS Rating Curve= 0 ,0
Exp/Cntr=0.3,0.1

Type RM Length L Ch R = 1 ,5548    ,463,463,463
BEGIN DESCRIPTION:
Conroe Lake 001 9.0
END DESCRIPTION:
XS GIS Cut Line= 3
      3823831.22     10105072.11      3822436.06     10105195.41
        3821464.     10106393.46
#Sta/Elev= 30
  3599.4  145.74  3754.9  142.14  3883.9  144.34  4044.5  141.11  4196.3  142.01
  4235.2  140.35  4305.5  142.78    4395  141.49  4415.9  142.37    4474  140.26
  4593.8  138.83    4687   138.8  4707.1  140.51  4827.5  136.01  4891.9  136.35
  4927.9  134.56  4986.4  127.09  5009.4  128.08  5031.7  134.55  5151.7  138.89
  5322.7     140  5763.8  139.59  5805.7  136.97  5834.2  140.51  6118.6  139.42
  6140.5  137.92  6275.3  142.51  6374.4  141.69  6452.7  143.75  6542.8  142.31
#Mann= 9 ,-1 , 0
  3599.4     .11       0  3754.9     .17       0  4196.3     .11       0
    4395     .17       0    4474     .11       0  4593.8     .17       0
  4891.9     .11       0  4927.9     .06       0  5031.7     .11       0
Bank Sta=4927.9,5031.7
XS Rating Curve= 0 ,0
Exp/Cntr=0.3,0.1

Type RM Length L Ch R = 1 ,5085    ,490,490,490
BEGIN DESCRIPTION:
Conroe Lake 001 8.0
END DESCRIPTION:
XS GIS Cut Line= 3
      3823042.34     10104538.57      3822036.43     10104962.51
      3821370.26     10106370.03
#Sta/Elev= 30
  3908.4  142.31  3945.8  142.69  4058.1  139.83    4111  142.01  4195.4  142.21
  4249.7  138.63  4401.6  140.06  4477.6  136.96  4829.6  135.96  4929.9   134.8
  4944.2  133.31  4953.6  132.18  4965.9  126.42  4986.5  124.83  5006.1  125.96
  5020.5  133.39  5034.4  135.88  5051.7   133.1  5449.5   133.3  5485.2  133.58
  5523.3  136.44  5761.8  140.46  5898.4  139.76  5949.9   137.7  5966.6  139.23
  6017.6  139.45  6085.9  137.44  6318.9  141.85  6348.2  140.37  6557.2  143.35
#Mann= 4 ,-1 , 0
  3908.4     .11       0  4944.2     .07       0  5020.5     .11       0
  5034.4     .11       0
Bank Sta=4944.2,5020.5
XS Rating Curve= 0 ,0
Exp/Cntr=0.3,0.1

Type RM Length L Ch R = 1 ,4595    ,279,279,279
BEGIN DESCRIPTION:
Conroe Lake 001 7.0
END DESCRIPTION:
XS GIS Cut Line= 3
       3823014.5      10104399.7      3821574.11     10104827.57
      3821297.44     10106356.54
#Sta/Elev= 30
  3497.4  143.67  3586.3  143.09  3696.3  139.31  3723.4  140.89  3801.2  139.27
  3911.2   141.8  4044.1  138.83  4253.7  138.82    4397  136.09  4507.1  137.62
  4589.2  136.64  4711.5  139.26  4849.6  136.47  4926.4   133.1  4943.9  130.46
  4954.4  129.19  4964.8  125.43  4983.9  123.68  5007.8  124.23  5023.9   129.9
  5034.1  131.14    5156  131.64  5178.5  129.75  5206.8  131.45  5298.3  129.77
  5409.7  133.23    5509   136.4  5918.2  141.65  6074.9  140.14  6553.8  143.44
#Mann= 6 ,-1 , 0
  3497.4     .11       0  4943.9     .09       0  5023.9     .12       0
  5034.1     .15       0  5409.7     .17       0    5509     .11       0
#XS Ineff= 2 , 0
       0                  5084.9       0  131.75
Permanent Ineff=
       F       F
Bank Sta=4943.9,5023.9
XS Rating Curve= 0 ,0
Exp/Cntr=0.3,0.1

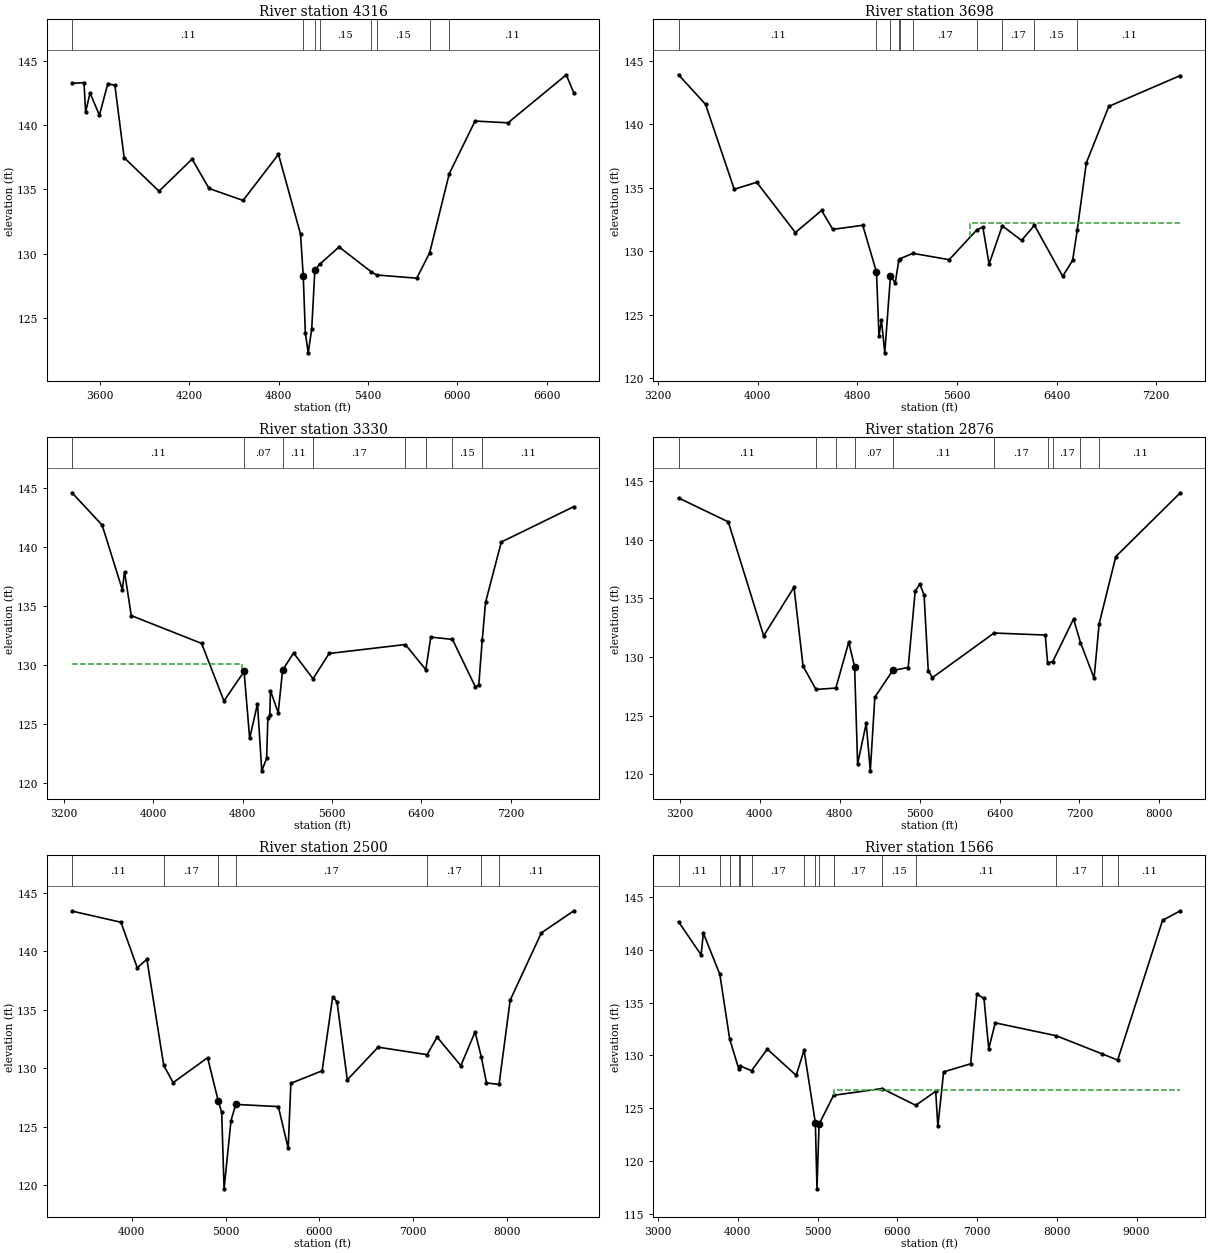
Type RM Length L Ch R = 1 ,4316    ,618,618,618
BEGIN DESCRIPTION:
Conroe Lake 001 6.0
END DESCRIPTION:
XS GIS Cut Line= 4
      3822945.08     10104163.58      3821465.33     10104563.51
      3821379.35     10104635.17      3821247.88     10106351.77
#Sta/Elev= 30
  3414.4  143.24  3494.4   143.3  3505.3     141  3534.8   142.5    3598  140.76
  3654.4  143.23  3701.6  143.09  3763.7  137.46  3997.8  134.85  4219.5  137.35
  4333.5  135.06  4561.4  134.13  4799.1  137.72  4947.2   131.5  4965.2  128.26
  4979.5  123.81  4998.6  122.27  5022.1  124.12  5043.3  128.72  5075.1  129.16
  5205.5  130.51  5418.8   128.6  5457.7  128.33    5727  128.08  5813.5  130.06
  5945.1  136.22  6118.2  140.31  6338.8  140.17    6730  143.91  6780.8  142.48
#Mann= 8 ,-1 , 0
  3414.4     .11       0  4965.2     .07       0  5043.3     .11       0
  5075.1     .15       0  5418.8     .17       0  5457.7     .15       0
  5813.5     .17       0  5945.1     .11       0
#XS Ineff= 2 , 0
       0                  5205.5       0  130.51
Permanent Ineff=
       F       F
Bank Sta=4965.2,5043.3
XS Rating Curve= 0 ,0
Exp/Cntr=0.3,0.1

Type RM Length L Ch R = 1 ,3698    ,368,368,368
BEGIN DESCRIPTION:
Conroe Lake 001 5.0
END DESCRIPTION:
XS GIS Cut Line= 4
      3822924.23     10103913.58       3821291.7      10104013.7
      3821090.94     10104392.74       3821198.4     10106354.37
#Sta/Elev= 30
  3364.4   143.9  3581.2  141.57  3811.6  134.88    3992  135.43  4302.5  131.47
  4512.9  133.21  4603.1  131.72  4843.6  132.04  4953.8  128.35  4973.8  123.34
  4993.8  124.54  5020.4  121.99  5066.1  128.04  5104.4   127.5  5132.8  129.27
  5141.4   129.4    5246  129.83  5537.4  129.33  5760.8  131.69  5807.8   131.9
  5857.9  128.99  5964.1     132  6118.3  130.85  6222.3  132.04  6448.8  128.02
  6528.9  129.28  6565.2  131.63  6639.1  136.97  6819.3  141.41  7393.5  143.84
#Mann= 10 ,-1 , 0
  3364.4     .11       0  4953.8     .07       0  5066.1     .11       0
  5132.8     .17       0  5141.4     .15       0    5246     .17       0
  5760.8     .15       0  5964.1     .17       0  6222.3     .15       0
  6565.2     .11       0
#XS Ineff= 2 , 0
       0                  5707.7       0  132.25
Permanent Ineff=
       F       F
Bank Sta=4953.8,5066.1
XS Rating Curve= 0 ,0
Exp/Cntr=0.3,0.1

Type RM Length L Ch R = 1 ,3330    ,454,454,454
BEGIN DESCRIPTION:
Conroe Lake 001 4.0
END DESCRIPTION:
XS GIS Cut Line= 4
      3822917.35     10103712.19      3821191.34     10103666.89
      3820896.49      10104323.3      3821128.04     10106356.57
#Sta/Elev= 30
  3273.4  144.59    3543  141.85  3723.1  136.39  3743.1  137.91  3803.1   134.2
  4433.3  131.84  4633.4  126.97  4813.4  129.47  4863.4   123.8  4933.5  126.74
  4971.7  121.06  5015.4  122.12  5026.5  125.55    5044  125.78  5049.5  127.84
    5119  125.98  5158.1  129.58  5256.7  131.03  5430.8  128.85  5574.6  130.99
  6257.3  131.75  6440.4  129.62  6485.1  132.38  6679.2  132.18  6884.8  128.15
    6915  128.35  6945.4   132.1  6975.4  135.32  7116.3  140.42    7766  143.42
#Mann= 8 ,-1 , 0
  3273.4     .11       0  4813.4     .07       0  5158.1     .11       0
  5430.8     .17       0  6257.3     .15       0  6440.4     .17       0
  6679.2     .15       0  6945.4     .11       0
#XS Ineff= 2 , 0
       0  4793.4  130.09               0
Permanent Ineff=
       F       F
Bank Sta=4813.4,5158.1
XS Rating Curve= 0 ,0
Exp/Cntr=0.3,0.1

Type RM Length L Ch R = 1 ,2876    ,376,376,376
BEGIN DESCRIPTION:
Conroe Lake 001 3.0
END DESCRIPTION:
XS GIS Cut Line= 5
      3822910.38     10103503.85      3821117.11     10103229.08
      3821014.55     10103364.96      3820790.85     10104287.53
      3821049.96     10106362.17
#Sta/Elev= 30
  3185.8  143.57  3684.1  141.53  4038.2  131.81  4341.7  135.96  4432.7  129.23
  4561.7  127.24    4761  127.36  4890.4  131.28  4948.7  129.17    4979  120.89
  5065.1  124.36    5106   120.3  5151.5  126.58  5330.9  128.86  5485.2  129.11
  5555.7  135.63  5602.7  136.22  5644.5  135.29  5686.3  128.83  5728.1  128.25
  6345.1  132.05  6857.8  131.88  6881.2  129.52  6932.6  129.61    7141  133.25
  7210.7  131.24  7346.8   128.2    7397  132.82  7564.2  138.57  8210.3  144.01
#Mann= 10 ,-1 , 0
  3185.8     .11       0  4561.7     .15       0    4761     .11       0
  4948.7     .07       0  5330.9     .11       0  6345.1     .17       0
  6881.2     .15       0  6932.6     .17       0  7210.7     .15       0
    7397     .11       0
#XS Ineff= 2 , 0
       0  4890.4  131.28               0
Permanent Ineff=
       F       F
Bank Sta=4948.7,5330.9
XS Rating Curve= 0 ,0
Exp/Cntr=0.3,0.1

Type RM Length L Ch R = 1 ,2500    ,934,934,934
BEGIN DESCRIPTION:
Conroe Lake 001 4.5
END DESCRIPTION:
XS GIS Cut Line= 6
       3822904.2     10103425.63      3821345.69     10102933.05
      3821229.82     10102927.46      3820924.27     10103316.35
      3820674.27     10104302.46      3820971.84     10106362.21
#Sta/Elev= 30
  3365.5  143.43    3886  142.48    4060  138.58  4162.2  139.32  4341.6  130.24
  4441.9  128.77    4809   130.9  4921.3  127.23  4958.9  126.22  4984.1  119.69
  5057.9  125.51    5108  126.91  5561.8  126.72    5667  123.17  5695.3  128.71
  6028.3  129.78  6140.9   136.1    6187  135.68  6296.3  129.01  6624.6   131.8
  7146.2  131.16  7252.9  132.66  7505.5  130.22  7657.1   133.1  7724.2  130.95
  7778.3  128.75  7912.4  128.61  8030.9  135.82  8362.8  141.57    8709  143.46
#Mann= 7 ,-1 , 0
  3365.5     .11       0  4341.6     .17       0  4921.3     .09       0
    5108     .17       0  7146.2     .17       0  7724.2     .15       0
  7912.4     .11       0
Bank Sta=4921.3,5108
XS Rating Curve= 0 ,0
Exp/Cntr=0.3,0.1

Type RM Length L Ch R = 1 ,1566    ,479,479,479
BEGIN DESCRIPTION:
Conroe Lake 001 2.0
END DESCRIPTION:
XS GIS Cut Line= 6
      3822921.37     10103296.64      3821597.47     10102164.45
      3821097.88     10102753.85      3820813.16     10103267.74
      3820563.16     10104316.35      3820898.82     10106366.75
#Sta/Elev= 30
    3258  142.67  3540.7  139.53  3569.2  141.59  3775.6  137.69  3898.7  131.56
  4014.6  128.67  4024.4  129.01    4173  128.54  4370.6  130.59  4732.9   128.1
  4831.6  130.49  4973.2  123.59  4993.3  117.34  5019.6  123.47  5201.2  126.21
  5808.6  126.85  6232.1  125.26  6481.6  126.59  6508.9  123.26  6580.9  128.43
  6920.1   129.2  6997.3   135.8  7086.7   135.4  7146.3  130.63  7228.5  133.08
  7992.7  131.86  8570.6  130.13  8762.4  129.55    9325   142.8  9548.1  143.71
#Mann= 15 ,-1 , 0
    3258     .11       0  3775.6     .17       0  3898.7     .15       0
  4014.6     .11       0  4024.4     .15       0    4173     .17       0
  4831.6     .12       0  4973.2     .09       0  5019.6     .12       0
  5201.2     .17       0  5808.6     .15       0  6232.1     .11       0
  7992.7     .17       0  8570.6     .15       0  8762.4     .11       0
#XS Ineff= 2 , 0
       0                  5207.3       0  126.74
Permanent Ineff=
       F       F
Bank Sta=4973.2,5019.6
XS Rating Curve= 0 ,0
Exp/Cntr=0.3,0.1

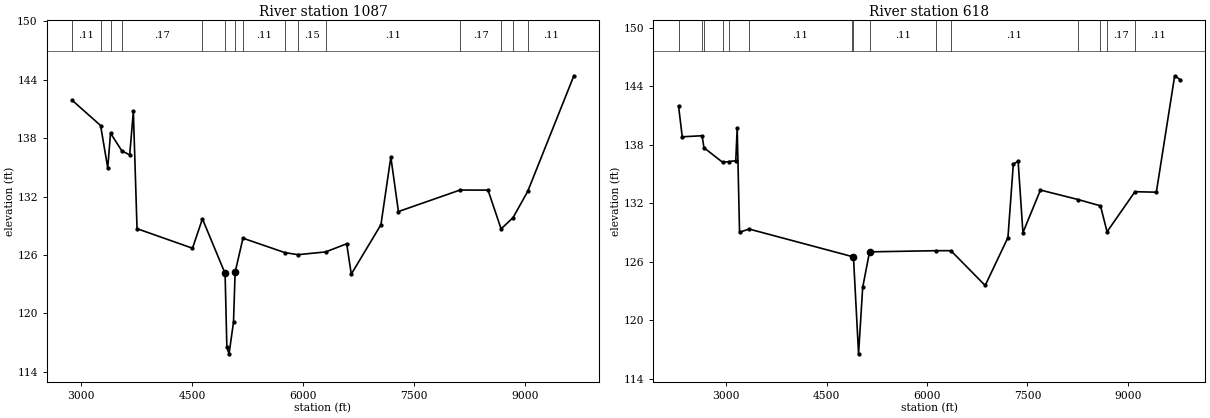
Type RM Length L Ch R = 1 ,1087    ,469,469,469
BEGIN DESCRIPTION:
Conroe Lake 001 2.5
END DESCRIPTION:
XS GIS Cut Line= 6
      3822932.87     10103167.69      3821562.78     10101889.33
      3821312.18     10101908.59      3820788.68     10103026.25
      3820483.12     10104290.14      3820816.46     10106373.48
#Sta/Elev= 30
  2874.8  141.91  3260.5  139.31  3357.2  134.96  3395.1  138.52  3547.5  136.71
  3654.2  136.29  3703.6  140.75  3753.4  128.71  4503.3   126.7  4637.7  129.72
  4944.2  124.11  4968.2  116.52  4997.7  115.85    5058   119.1    5080  124.24
    5186  127.73  5753.3  126.25  5929.4  126.04  6303.6  126.32  6588.9  127.16
  6650.7  124.04  7051.9  129.12  7185.7  136.07  7288.5  130.47  8121.4  132.68
  8500.2  132.67  8676.8  128.69  8838.1  129.84  9036.1  132.53  9660.9  144.42
#Mann= 15 ,-1 , 0
  2874.8     .11       0  3260.5     .17       0  3395.1     .15       0
  3547.5     .17       0  4637.7     .12       0  4944.2     .09       0
    5080     .12       0    5186     .11       0  5753.3     .17       0
  5929.4     .15       0  6303.6     .11       0  8121.4     .17       0
  8676.8     .15       0  8838.1     .17       0  9036.1     .11       0
Bank Sta=4944.2,5080
XS Rating Curve= 0 ,0
Exp/Cntr=0.3,0.1

Type RM Length L Ch R = 1 ,618     ,0,0,0
BEGIN DESCRIPTION:
Conroe Lake 001 1.0
END DESCRIPTION:
XS GIS Cut Line= 6
      3822961.52     10103096.03       3821528.7     10101564.01
       3820937.6      10101733.3      3820389.55     10104274.69
       3820445.1     10105899.69      3820740.09     10106373.51
#Sta/Elev= 30
  2287.5  141.99  2343.2  138.83  2638.7  138.94  2667.6  137.71  2946.8  136.21
  3040.5  136.29  3142.8  136.38  3163.8  139.75    3199  129.04  3341.2  129.37
  4874.9  126.56    4901  126.47    4977  116.57  5038.6  123.38  5140.9  127.03
  6132.4  127.15  6356.4  127.15  6868.6  123.58  7208.6   128.5  7289.2  136.05
  7360.8  136.31  7432.4     129  7693.9  133.37  8254.6   132.4  8590.9  131.75
  8689.3  129.09  9106.2   133.2  9425.7  133.15  9699.5  145.09  9783.9  144.69
#Mann= 15 ,-1 , 0
  2287.5     .11       0  2638.7     .17       0  2667.6     .15       0
  2946.8     .11       0  3040.5     .15       0  3341.2     .11       0
  4874.9     .09       0    4901     .06       0  5140.9     .11       0
  6132.4     .15       0  6356.4     .11       0  8254.6     .17       0
  8590.9     .15       0  8689.3     .17       0  9106.2     .11       0
Bank Sta=4901,5140.9
XS Rating Curve= 0 ,0
Exp/Cntr=0.3,0.1

Chan Stop Cuts=-1
Use User Specified Reach Order=0
Composite Channel Slope=5