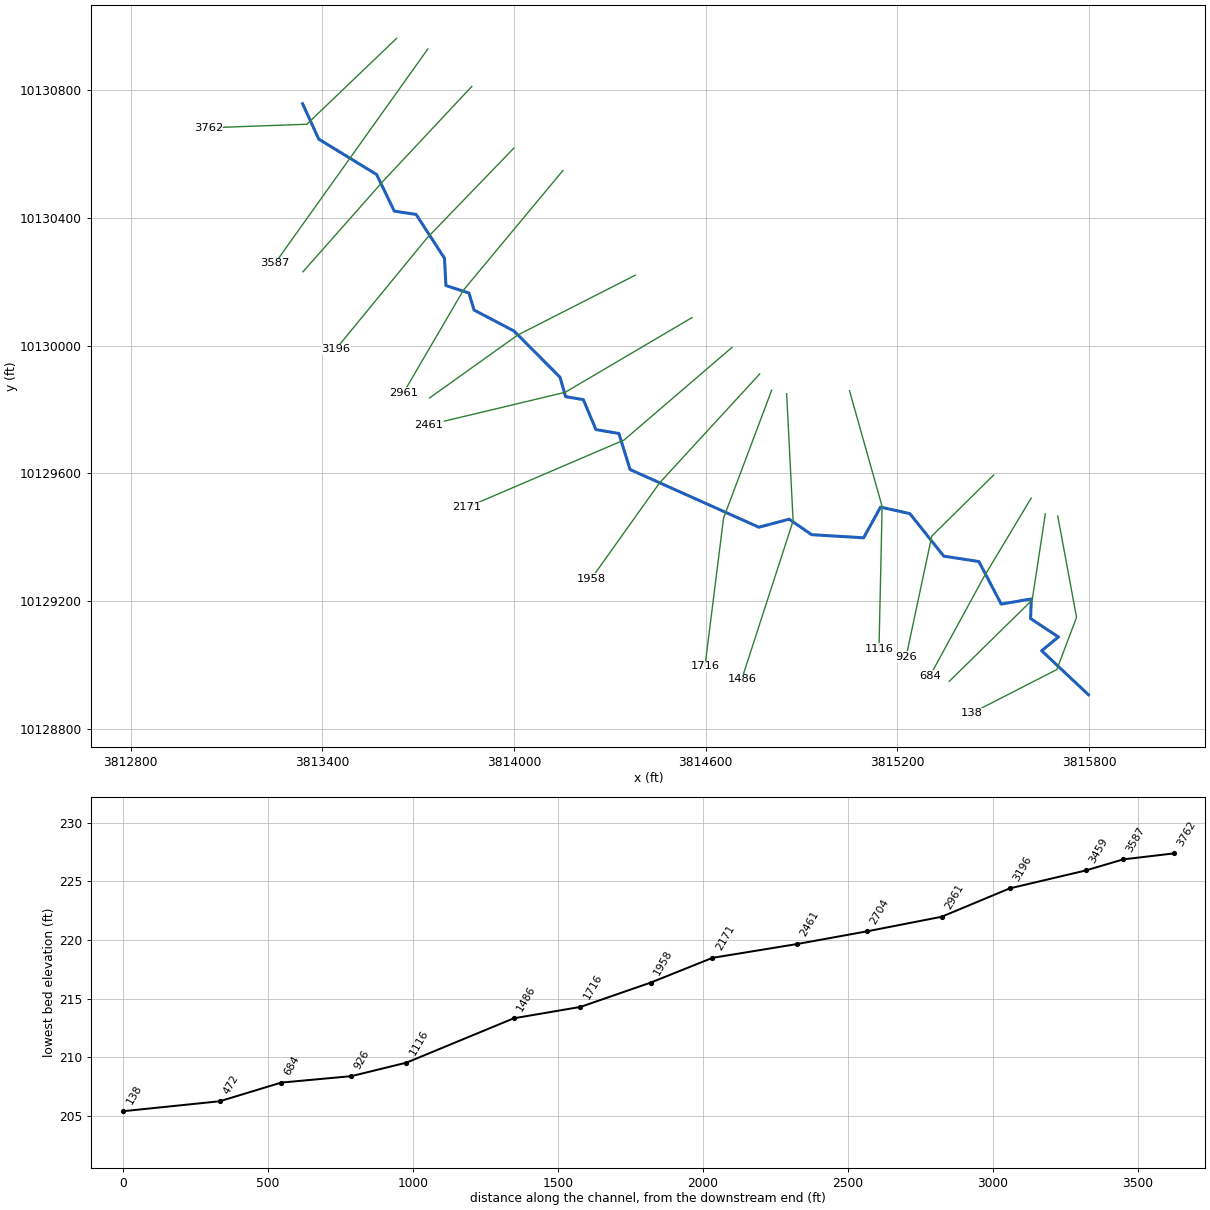
--- Conroe Lake 003.prj (project) ---

Proj Title=Conroe Lake 003 Base Level Engineering
Current Plan=p01
Default Exp/Contr=0.3,0.1
English Units
Geom File=g01
Flow File=f01
Flow File=f02
Plan File=p01
Y Axis Title=Elevation
X Axis Title(PF)=Main Channel Distance
X Axis Title(XS)=Station
BEGIN DESCRIPTION:
Conroe Lake 003
END DESCRIPTION:
DSS File=dss
DSS Export Rating Curves= 0
DSS Export Rating Curve Sorted= 0
DSS Export Volume Flow Curves= 0
DXF OffsetX= 0
DXF OffsetY= 0
DXF ScaleX= 1
DXF ScaleY= 10

--- Conroe Lake 003.p01 (plan) ---

Plan Title=Multiple Run
Program Version=4.10
Short Identifier=Multiple Run
Geom File=g01
Flow File=f01
Subcritical Flow
K Sum by GR= 0
Std Step Tol= 0.01
Critical Tol= 0.01
Num of Std Step Trials= 20
Max Error Tol= 0.3
Flow Tol Ratio= 0.001
Split Flow NTrial= 30
Split Flow Tol= 0.02
Split Flow Ratio= 0.02
Log Output Level= 0
Friction Slope Method= 1
Unsteady Friction Slope Method= 2
Unsteady Bridges Friction Slope Method= 1
Parabolic Critical Depth
Global Vel Dist= 1 , 1 , 1
Global Log Level= 0
CheckData=True
Encroach Param=-1 ,0,0, 0
BEGIN DESCRIPTION:
Multiple Run
END DESCRIPTION:
Computation Interval=1HOUR
Output Interval=1HOUR
Run HTab= 0
Run UNet= 0
Run PostProcess= 0
Run WQNet= 0
UNET Theta= 1
UNET Theta Warmup= 1
UNET ZTol= 0.02
UNET ZSATol= 0.05
UNET MxIter= 20
UNET MaxInSteps= 0
UNET DtIC= 0
UNET DtMin= 0
UNET MaxCRTS= 20
UNET WFStab= 2
UNET SFStab= 1
UNET WFX= 1
UNET SFX= 1
UNET DSS MLevel= 4
UNET DZMax Abort= 100
UNET Convert EG Bridges= 0
UNET Use Existing IB Tables=-1
UNET Froude Reduction=False
UNET Froude Limit= 1
UNET Froude Power= 10
UNET Time Slicing=0,0, 5
UNET Junction Losses=0
Instantaneous Interval=1HOUR
DSS File=dss
Write IC File= 0
Write IC File at Sim End=0
Echo Input=False
Echo Parameters=False
Echo Output=False
Write Detailed= 0
WQ AD Non Conservative
WQ ULTIMATE=-1
WQ Max Comp Step=1HOUR
WQ Output Interval=15MIN
WQ Output Selected Increments= 0
WQ Output face flow=0
WQ Output face velocity=0
WQ Output face area=0
WQ Output face dispersion=0
WQ Output cell volume=0
WQ Output cell surface area=0
WQ Output cell continuity=0
WQ Output cumulative cell continuity=0
WQ Output face conc=0
WQ Output face dconc_dx=0
WQ Output face courant=0
WQ Output face peclet=0
WQ Output face adv mass=0
WQ Output face disp mass=0
WQ Output cell mass=0
WQ Output cell source sink temp=0
WQ Output cell source sink nsm=0
WQ Output MaxMinRange=-1
WQ Daily Max Min Mean=-1
WQ Daily Range=0
WQ Daily Time=0
WQ Create Restart=0
WQ Fixed Restart=0
WQ System Summary=0
WQ Use Fixed Temperature=0
Sorting and Armoring Iterations= 10
XS Update Threshold= 0.02
Hydraulics Update Threshold= 0.02
Energy Slope Method= 1
Volume Change Method= 0
XS Weighting Method= 0
Number of US Weighted Cross Sections= 1
Number of DS Weighted Cross Sections= 1
Upstream XS Weight=0.25
Main XS Weight=0.5
Downstream XS Weight=0.25
Number of DS XS's Weighted with US Boundary= 1
Upstream Boundary Weight= 1
Weight of XSs Associated with US Boundary= 0
Number of US XS's Weighted with DS Boundary= 1
Downstream Boundary Weight= 0.5
Weight of XSs Associated with DS Boundary= 0.5
Sediment Output Level= 4
Mass or Volume Output= 0
Output Increment Type= 1
Profile and TS Output Increment= 10
XS Output Flag= 0
XS Output Increment= 10
Disregard all LS=0
Disregard all Conn=0
Disregard all Breaches=0
Disregard all Pumps=0

--- Conroe Lake 003.f01 (steady flow) ---

Flow Title=Multiple
Program Version=4.10
Number of Profiles= 7
Profile Names=10-year,25-year,50-year,1pct_min,100-year,1pct_plu,500-year
River Rch & RM=Conroe Lake 003,Reach-1         ,3762
     683     933    1271     571    1723    5203    3265
River Rch & RM=Conroe Lake 003,Reach-1         ,3459
     786    1081    1478     665    2009    6067    3834
Boundary for River Rch & Prof#=Conroe Lake 003,Reach-1         , 1
Up Type= 0
Dn Type= 3
Dn Slope=0.005
Boundary for River Rch & Prof#=Conroe Lake 003,Reach-1         , 2
Up Type= 0
Dn Type= 3
Dn Slope=0.005
Boundary for River Rch & Prof#=Conroe Lake 003,Reach-1         , 3
Up Type= 0
Dn Type= 3
Dn Slope=0.005
Boundary for River Rch & Prof#=Conroe Lake 003,Reach-1         , 4
Up Type= 0
Dn Type= 3
Dn Slope=0.005
Boundary for River Rch & Prof#=Conroe Lake 003,Reach-1         , 5
Up Type= 0
Dn Type= 3
Dn Slope=0.005
Boundary for River Rch & Prof#=Conroe Lake 003,Reach-1         , 6
Up Type= 0
Dn Type= 3
Dn Slope=0.005
Boundary for River Rch & Prof#=Conroe Lake 003,Reach-1         , 7
Up Type= 0
Dn Type= 3
Dn Slope=0.005
DSS Import GetInterval= 0
DSS Import GetPeak= 0
DSS Import FillOption= 0

--- Conroe Lake 003.f02 (steady flow) ---

Flow Title=Orig_BLE_Flow
Program Version=4.10
Number of Profiles= 7
Profile Names=10-year,25-year,50-year,1pct_min,100-year,1pct_plu,500-year
River Rch & RM=Conroe Lake 003,Reach-1         ,3762
     683     915    1105     439    1325    4001    1898
River Rch & RM=Conroe Lake 003,Reach-1         ,3459
     786    1060    1285     512    1545    4666    2229
Boundary for River Rch & Prof#=Conroe Lake 003,Reach-1         , 1
Up Type= 0
Dn Type= 3
Dn Slope=0.005
Boundary for River Rch & Prof#=Conroe Lake 003,Reach-1         , 2
Up Type= 0
Dn Type= 3
Dn Slope=0.005
Boundary for River Rch & Prof#=Conroe Lake 003,Reach-1         , 3
Up Type= 0
Dn Type= 3
Dn Slope=0.005
Boundary for River Rch & Prof#=Conroe Lake 003,Reach-1         , 4
Up Type= 0
Dn Type= 3
Dn Slope=0.005
Boundary for River Rch & Prof#=Conroe Lake 003,Reach-1         , 5
Up Type= 0
Dn Type= 3
Dn Slope=0.005
Boundary for River Rch & Prof#=Conroe Lake 003,Reach-1         , 6
Up Type= 0
Dn Type= 3
Dn Slope=0.005
Boundary for River Rch & Prof#=Conroe Lake 003,Reach-1         , 7
Up Type= 0
Dn Type= 3
Dn Slope=0.005
DSS Import GetInterval= 0
DSS Import GetPeak= 0
DSS Import FillOption= 0

--- Conroe Lake 003.g01 (geometry) ---

Geom Title=Existing Conditions
Program Version=4.10

River Reach=Conroe Lake 003 ,Reach-1
Reach XY= 30
      3813338.23     10130756.84      3813388.81     10130646.15
       3813569.9     10130535.38      3813625.34     10130420.75
      3813693.57     10130410.41      3813782.44     10130273.08
      3813786.79     10130187.88       3813859.1     10130164.34
      3813874.73     10130111.31      3813999.66     10130045.67
      3814143.78     10129901.17      3814161.41     10129840.12
      3814217.04     10129830.62      3814256.38     10129737.01
      3814328.28      10129724.8       3814363.3     10129611.95
      3814766.43     10129431.39      3814861.19     10129456.49
      3814931.57     10129408.04      3815094.21     10129398.25
      3815147.27     10129494.36      3815238.98       10129474.
      3815345.02     10129340.87      3815455.09     10129323.92
      3815525.02     10129190.74      3815618.93     10129206.88
      3815617.07     10129145.36      3815704.03     10129087.79
      3815651.61     10129044.74      3815798.23     10128906.84

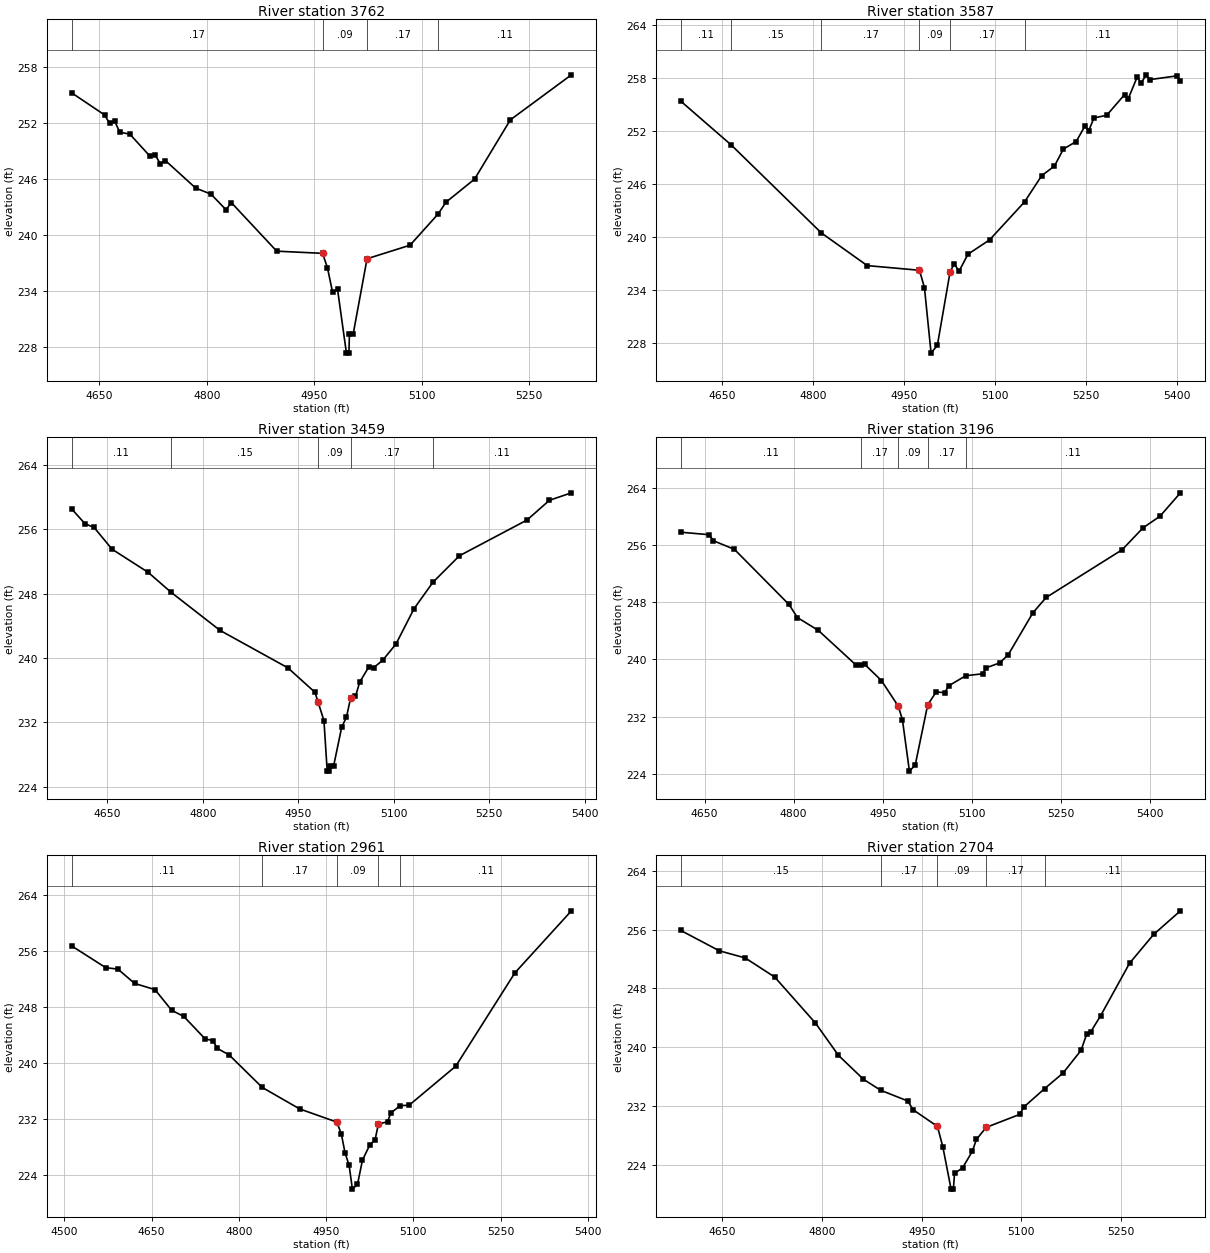
Type RM Length L Ch R = 1 ,3762    ,175,175,175
BEGIN DESCRIPTION:
Conroe Lake 003 14.0
END DESCRIPTION:
XS GIS Cut Line= 3
      3813632.51     10130961.63      3813351.52     10130692.76
      3813042.73     10130681.54
#Sta/Elev= 30
  4611.1  255.26  4657.3  252.88  4664.3  251.97  4671.5  252.19  4678.4  251.04
  4692.6  250.82  4720.9  248.44  4728.1  248.56    4735  247.67  4742.1     248
  4784.4  245.05  4805.8   244.4  4826.9  242.72  4834.1   243.5  4897.6  238.29
  4961.5  238.06  4968.4  236.52  4975.6  233.87  4982.5   234.2  4994.9  227.37
  4998.4  227.37  4999.1   229.4  5004.3   229.4  5023.7  237.48  5083.7  238.93
  5123.1  242.29  5133.8  243.53  5173.8  246.01  5223.8  252.36    5309  257.18
#Mann= 4 ,-1 , 0
  4611.1     .17       0  4961.5     .09       0  5023.7     .17       0
  5123.1     .11       0
Bank Sta=4961.5,5023.7
XS Rating Curve= 0 ,0
Exp/Cntr=0.3,0.1

Type RM Length L Ch R = 1 ,3587    ,128,128,128
BEGIN DESCRIPTION:
Mapping XS 3e325292
END DESCRIPTION:
XS GIS Cut Line= 2
      3813730.21     10130928.26      3813251.95     10130257.63
#Sta/Elev= 30
  4581.7  255.41    4665  250.44  4813.7  240.47  4889.3  236.77  4975.4  236.24
  4983.6  234.27  4994.5  226.86  5004.9  227.75  5025.8  236.04  5032.7     237
  5040.5  236.12  5055.3  238.06  5090.9  239.68  5148.5  243.98  5176.9  246.96
  5197.8  248.04  5212.6  249.97  5233.5  250.81  5248.2  252.58  5254.4  252.06
    5263  253.49  5283.9  253.79  5313.4  256.13  5319.5  255.68  5334.3  258.15
  5340.4  257.41    5349  258.37  5355.2  257.83  5399.4  258.25  5405.4  257.67
#Mann= 6 ,-1 , 0
  4581.7     .11       0    4665     .15       0  4813.7     .17       0
  4975.4     .09       0  5025.8     .17       0  5148.5     .11       0
Bank Sta=4975.4,5025.8
XS Rating Curve= 0 ,0
Exp/Cntr=0.3,0.1

Type RM Length L Ch R = 1 ,3459    ,263,263,263
BEGIN DESCRIPTION:
Conroe Lake 003 13.0
END DESCRIPTION:
XS GIS Cut Line= 3
      3813867.83     10130811.04      3813590.29     10130514.71
      3813339.39     10130230.92
#Sta/Elev= 30
    4594  258.56  4615.2   256.7  4629.4  256.24  4657.7  253.53  4714.4  250.65
  4749.9   248.2  4827.2  243.43  4933.7  238.77  4976.2  235.73  4981.2  234.48
  4990.3   232.2  4995.4  225.92  4998.9  225.92    5000  226.61  5005.6  226.61
  5018.2   231.4  5025.6  232.63  5032.3  235.06  5039.8  235.22  5046.5  237.01
  5060.7  238.88  5068.3  238.79  5082.5  239.71  5103.4  241.74  5131.8  246.14
  5161.5  249.43    5203  252.72  5309.2  257.17  5344.3  259.62  5378.8  260.55
#Mann= 5 ,-1 , 0
    4594     .11       0  4749.9     .15       0  4981.2     .09       0
  5032.3     .17       0  5161.5     .11       0
Bank Sta=4981.2,5032.3
XS Rating Curve= 0 ,0
Exp/Cntr=0.3,0.1

Type RM Length L Ch R = 1 ,3196    ,235,235,235
BEGIN DESCRIPTION:
Conroe Lake 003 12.0
END DESCRIPTION:
XS GIS Cut Line= 3
      3813999.27     10130617.73      3813728.02     10130336.95
        3813442.     10129988.38
#Sta/Elev= 30
  4609.6  257.77  4657.8  257.42  4664.8  256.58  4700.3  255.37  4792.1  247.67
  4806.3  245.84  4841.5  244.05  4905.3  239.18  4913.3  239.24  4919.4  239.32
  4947.7  237.04    4976  233.47    4983  231.58  4994.8  224.39  5004.6  225.25
  5025.5  233.64  5039.8  235.45  5054.2  235.35  5060.6  236.29  5089.6  237.72
    5118  237.99  5124.5  238.84  5146.7  239.51  5161.1  240.65  5202.7  246.52
  5224.9  248.65  5352.7  255.31  5387.9  258.37  5416.6  260.01  5450.9  263.27
#Mann= 5 ,-1 , 0
  4609.6     .11       0  4913.3     .17       0    4976     .09       0
  5025.5     .17       0  5089.6     .11       0
Bank Sta=4976,5025.5
XS Rating Curve= 0 ,0
Exp/Cntr=0.3,0.1

Type RM Length L Ch R = 1 ,2961    ,257,257,257
BEGIN DESCRIPTION:
Conroe Lake 003 11.0
END DESCRIPTION:
XS GIS Cut Line= 3
       3814153.2     10130548.13      3813841.49     10130173.18
      3813653.91     10129852.05
#Sta/Elev= 30
  4512.4  256.79  4571.3  253.66  4592.1  253.46  4620.8  251.41  4655.9  250.52
  4684.6  247.56  4705.4  246.69  4741.9  243.49  4755.7  243.21  4762.7  242.13
  4783.5  241.17  4840.4  236.52  4904.6  233.45  4968.4  231.57  4976.2  229.91
  4982.7  227.15  4989.7  225.38  4995.3  221.97  5004.1  222.65  5012.7  226.14
  5025.6  228.35  5034.2  228.98    5040  231.28  5055.7  231.61  5061.5  232.88
  5077.7  233.92  5092.9  233.98  5173.1  239.57  5274.7  252.92  5371.9   261.8
#Mann= 5 ,-1 , 0
  4512.4     .11       0  4840.4     .17       0  4968.4     .09       0
    5040     .17       0  5077.7     .11       0
Bank Sta=4968.4,5040
XS Rating Curve= 0 ,0
Exp/Cntr=0.3,0.1

Type RM Length L Ch R = 1 ,2704    ,243,243,243
BEGIN DESCRIPTION:
Conroe Lake 003 10.0
END DESCRIPTION:
XS GIS Cut Line= 3
      3814379.39     10130220.18      3814011.69       10130033.
      3813735.64     10129836.07
#Sta/Elev= 30
  4587.4  255.89  4645.7  253.11  4684.6  252.14    4729  249.54  4790.2   243.3
  4824.8  238.91  4862.5  235.65  4888.1  234.17  4929.2   232.7    4937  231.52
  4973.7  229.25  4981.9  226.44  4994.2  220.73  4997.7  220.73  4999.4  222.87
  5011.4  223.61  5026.1  225.85  5032.3  227.48    5047  229.12  5097.4  230.88
  5103.6  231.88  5135.1   234.4  5162.6   236.5  5189.6  239.58  5198.2   241.8
  5204.4  242.12  5219.1  244.29  5262.7  251.43    5299  255.35  5339.1  258.54
#Mann= 5 ,-1 , 0
  4587.4     .15       0  4888.1     .17       0  4973.7     .09       0
    5047     .17       0  5135.1     .11       0
Bank Sta=4973.7,5047
XS Rating Curve= 0 ,0
Exp/Cntr=0.3,0.1

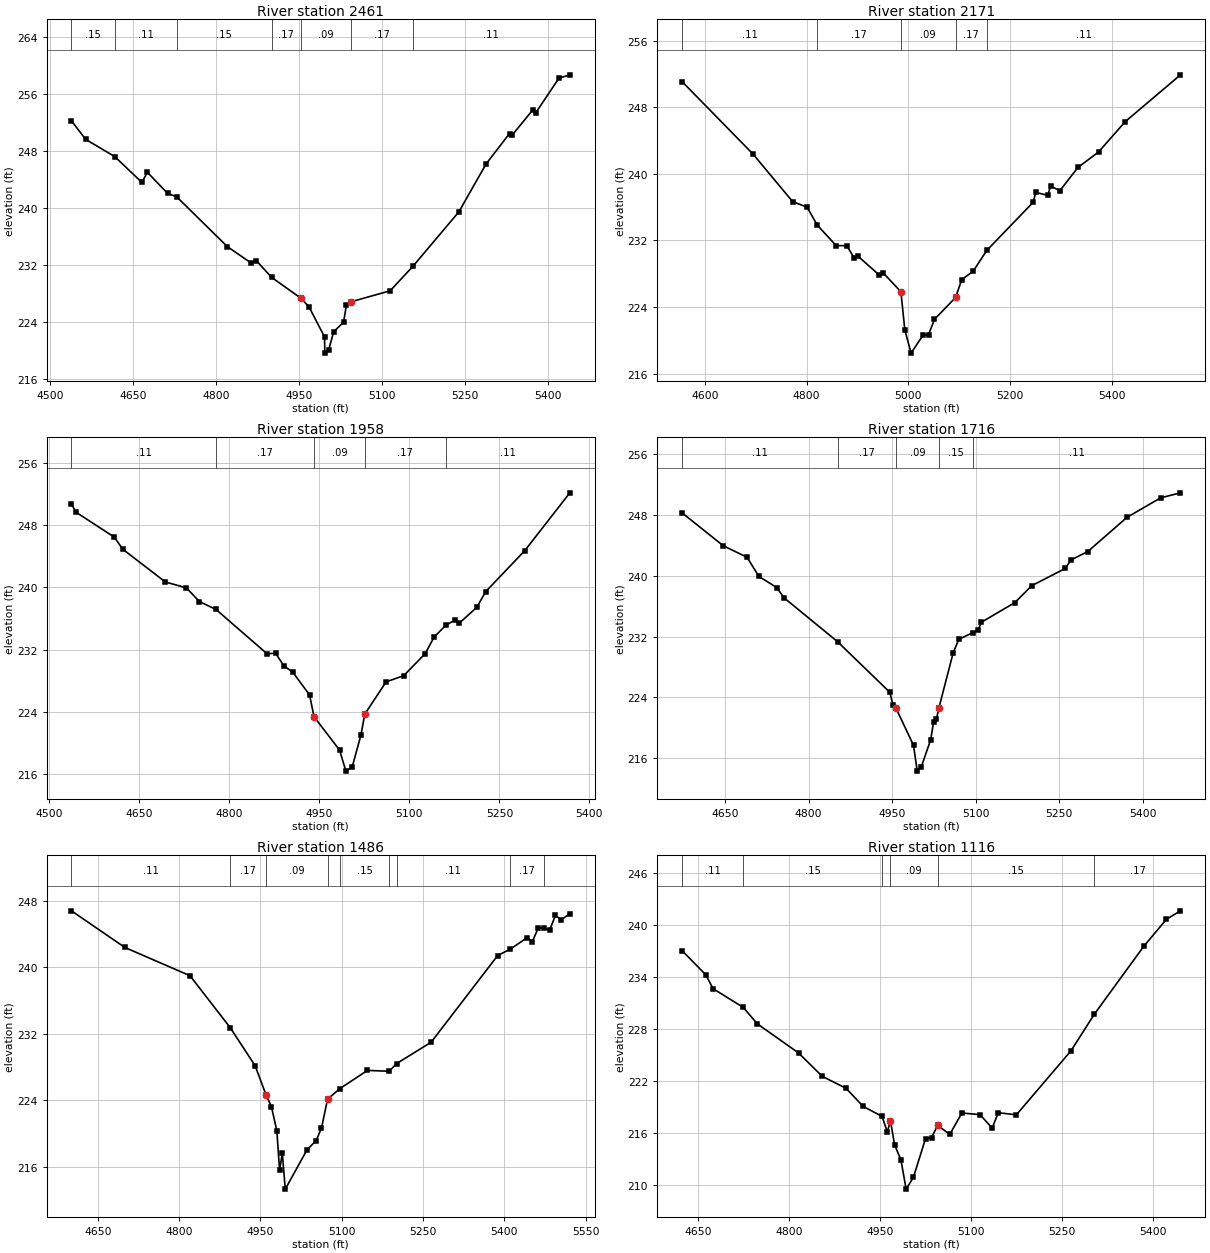
Type RM Length L Ch R = 1 ,2461    ,290,290,290
BEGIN DESCRIPTION:
Conroe Lake 003 9.0
END DESCRIPTION:
XS GIS Cut Line= 3
      3814557.48     10130087.69      3814160.06     10129853.69
      3813732.87     10129751.69
#Sta/Elev= 30
  4538.8   252.2  4564.5   249.6    4617  247.19    4666  243.57  4675.9  244.99
  4712.4  242.04  4728.9  241.55  4820.3  234.58  4863.3  232.28  4873.1  232.58
  4900.4  230.26  4953.1  227.35  4967.7  226.16    4996  221.92  4996.6  219.64
  5003.7  220.14  5012.5  222.64  5030.4  223.97  5035.5  226.33  5043.4  226.83
  5114.6  228.38  5155.8  231.82  5238.7  239.44  5288.1  246.18  5330.2  250.42
  5335.3  250.23  5372.3  253.73  5377.4   253.3  5419.5  258.18  5439.2  258.65
#Mann= 7 ,-1 , 0
  4538.8     .15       0    4617     .11       0  4728.9     .15       0
  4900.4     .17       0  4953.1     .09       0  5043.4     .17       0
  5155.8     .11       0
Bank Sta=4953.1,5043.4
XS Rating Curve= 0 ,0
Exp/Cntr=0.3,0.1

Type RM Length L Ch R = 1 ,2171    ,213,213,213
BEGIN DESCRIPTION:
Conroe Lake 003 8.0
END DESCRIPTION:
XS GIS Cut Line= 3
      3814681.96       10129994.      3814344.56     10129704.45
      3813852.46     10129493.54
#Sta/Elev= 30
  4555.4  251.08  4694.8  242.38  4772.7  236.67  4801.2     236  4821.1  233.85
  4858.3  231.38  4879.2  231.38  4893.4  229.94  4901.1  230.12    4943  227.85
  4950.5  228.13  4985.6  225.84  4993.3  221.28  5005.6  218.47  5029.1  220.62
  5039.9  220.67  5051.5  222.52  5093.2  225.16  5105.2   227.3  5127.6   228.3
  5154.5  230.81  5245.5  236.58  5250.9  237.77  5274.5  237.43  5279.9  238.55
  5298.1  237.98  5333.7  240.77  5374.2  242.63  5426.8  246.28  5535.4   251.9
#Mann= 5 ,-1 , 0
  4555.4     .11       0  4821.1     .17       0  4985.6     .09       0
  5093.2     .17       0  5154.5     .11       0
Bank Sta=4985.6,5093.2
XS Rating Curve= 0 ,0
Exp/Cntr=0.3,0.1

Type RM Length L Ch R = 1 ,1958    ,242,242,242
BEGIN DESCRIPTION:
Conroe Lake 003 7.0
END DESCRIPTION:
XS GIS Cut Line= 3
      3814768.97     10129911.02      3814455.42     10129569.94
      3814242.21     10129270.74
#Sta/Elev= 30
  4536.7   250.7  4544.6  249.66  4608.1  246.47  4622.3  244.91  4693.2   240.7
  4728.3  239.94  4749.9  238.18  4777.7  237.16  4862.7  231.46  4876.9  231.53
  4891.1  229.87  4905.3  229.13  4933.6  226.16    4941  223.36  4983.6  219.07
  4994.1  216.36  5004.6  216.89  5019.3  221.02  5025.5  223.67  5061.1  227.84
  5090.6  228.65  5126.3  231.48  5141.1   233.6  5160.4  235.11  5176.7  235.83
  5182.8  235.38  5212.4  237.44  5227.1  239.45  5292.3  244.73  5367.4  252.17
#Mann= 5 ,-1 , 0
  4536.7     .11       0  4777.7     .17       0    4941     .09       0
  5025.5     .17       0  5160.4     .11       0
Bank Sta=4941,5025.5
XS Rating Curve= 0 ,0
Exp/Cntr=0.3,0.1

Type RM Length L Ch R = 1 ,1716    ,230,230,230
BEGIN DESCRIPTION:
Conroe Lake 003 6.0
END DESCRIPTION:
XS GIS Cut Line= 3
      3814806.43     10129860.15      3814655.91     10129460.24
      3814597.65     10128995.78
#Sta/Elev= 30
  4572.7  248.28  4646.5  243.96  4689.3  242.44  4710.6  239.92  4742.7  238.45
    4756  237.09  4851.9  231.33  4945.7  224.68  4951.5  223.03  4956.8  222.59
  4988.4   217.7  4995.1  214.29  5002.1  214.79  5019.3  218.43  5024.5  220.76
  5029.5   221.1 5033.96  222.59  5059.6  229.84  5069.7  231.63  5095.2  232.53
    5105  232.88    5110  233.87  5170.5  236.47  5200.7  238.69  5260.9  240.96
  5271.3  242.08  5301.5  243.19  5372.1   247.7  5432.5  250.26  5468.1  250.92
#Mann= 5 ,-1 , 0
  4572.7     .11       0  4851.9     .17       0  4956.8     .09       0
 5033.96     .15       0  5095.2     .11       0
Bank Sta=4956.8,5033.96
XS Rating Curve= 0 ,0
Exp/Cntr=0.3,0.1

Type RM Length L Ch R = 1 ,1486    ,370,370,370
BEGIN DESCRIPTION:
Conroe Lake 003 5.0
END DESCRIPTION:
XS GIS Cut Line= 3
      3814853.27     10129849.45       3814873.6     10129451.27
      3814712.92     10128955.87
#Sta/Elev= 30
  4601.3  246.82  4699.8  242.41    4820  239.01  4894.2  232.76  4940.1  228.18
  4960.1   224.7  4970.2  223.25  4980.2  220.35  4985.3  215.58  4990.3  217.65
  4995.8  213.32  5035.9  218.05  5052.8  219.17  5062.6  220.66  5073.8  224.15
  5096.6  225.42  5147.4  227.61  5187.5  227.51  5201.2  228.43    5265  231.01
  5387.7  241.44  5410.5  242.19  5441.7  243.57  5451.6  243.11  5462.8   244.8
  5473.6  244.71  5483.6  244.52  5494.3  246.27  5504.8  245.74  5520.8  246.47
#Mann= 9 ,-1 , 0
  4601.3     .11       0  4894.2     .17       0  4960.1     .09       0
  5073.8     .17       0  5096.6     .15       0  5187.5     .17       0
  5201.2     .11       0  5410.5     .17       0  5473.6     .11       0
Bank Sta=4960.1,5073.8
XS Rating Curve= 0 ,0
Exp/Cntr=0.3,0.1

Type RM Length L Ch R = 1 ,1116    ,190,190,190
BEGIN DESCRIPTION:
Conroe Lake 003 4.0
END DESCRIPTION:
XS GIS Cut Line= 3
      3815050.05     10129858.74      3815152.24     10129496.17
       3815142.4     10129050.28
#Sta/Elev= 30
  4623.3  237.07  4662.4  234.28  4674.3  232.69  4724.2  230.52  4747.5  228.62
  4815.5  225.26  4854.7  222.56  4893.9  221.18  4922.2  219.09  4953.3  217.94
    4962  216.15  4967.2  217.41  4974.1  214.64  4984.5  212.92  4993.1  209.54
  5005.1   210.9  5025.1  215.37  5035.1  215.49  5045.1   216.9  5065.1  215.86
  5085.1  218.33  5115.1  218.14  5135.1  216.58  5145.1  218.36  5175.1  218.12
  5265.2  225.51  5303.9  229.75  5385.2  237.56  5422.8  240.69    5446  241.67
#Mann= 6 ,-1 , 0
  4623.3     .11       0  4724.2     .15       0  4953.3     .12       0
  4967.2     .09       0  5045.1     .15       0  5303.9     .17       0
Bank Sta=4967.2,5045.1
XS Rating Curve= 0 ,0
Exp/Cntr=0.3,0.1

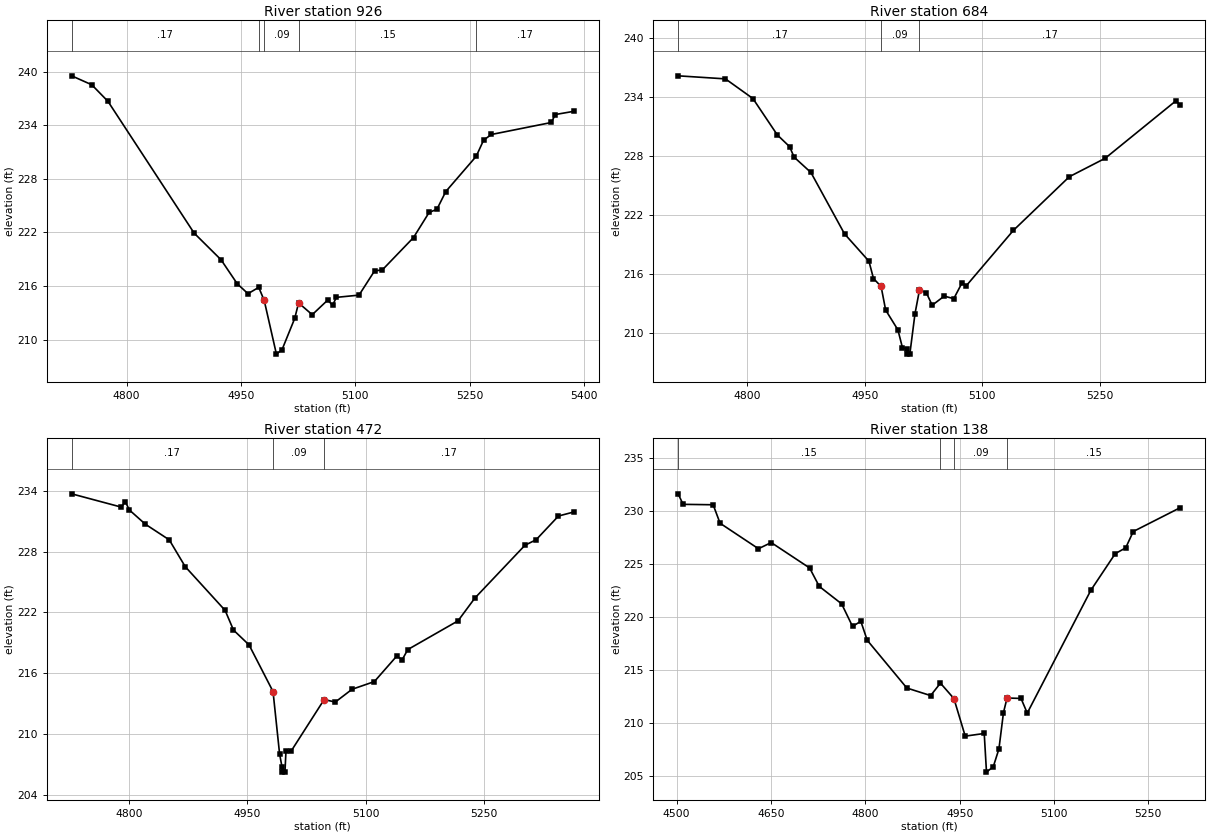
Type RM Length L Ch R = 1 ,926     ,242,242,242
BEGIN DESCRIPTION:
Conroe Lake 003 3.0
END DESCRIPTION:
XS GIS Cut Line= 3
       3815501.4     10129594.83      3815307.66     10129403.63
      3815227.11     10129025.31
#Sta/Elev= 30
  4727.8  239.52  4754.2  238.52  4775.4  236.67  4888.5  221.93  4923.9  218.94
  4945.1  216.26  4959.2  215.15  4973.3  215.86  4980.5  214.39  4996.5  208.39
  5003.9  208.89  5020.5  212.38  5025.6  214.12  5043.5   212.8    5064  214.45
  5070.1  213.84  5075.2  214.74  5104.9  214.99  5125.3   217.7  5135.5  217.81
  5176.4  221.43  5196.9  224.24  5207.1  224.59  5218.8  226.58  5258.7  230.52
  5268.4  232.33  5278.7  232.96  5357.3   234.3  5362.4  235.19  5386.8  235.55
#Mann= 5 ,-1 , 0
  4727.8     .17       0  4973.3     .12       0  4980.5     .09       0
  5025.6     .15       0  5258.7     .17       0
Bank Sta=4980.5,5025.6
XS Rating Curve= 0 ,0
Exp/Cntr=0.3,0.1

Type RM Length L Ch R = 1 ,684     ,212,212,212
BEGIN DESCRIPTION:
Conroe Lake 003 1.0
END DESCRIPTION:
XS GIS Cut Line= 3
      3815618.92     10129522.81      3815470.89     10129276.11
      3815302.42     10128966.93
#Sta/Elev= 30
  4712.3  236.14  4772.6  235.83  4807.6  233.83  4838.7  230.13  4854.3  228.94
  4860.1  227.87  4881.5  226.31  4924.3  220.07  4955.4  217.29  4961.2  215.53
  4970.9  214.72  4976.7  212.32  4992.3  210.31  4998.1   208.5  5003.7  208.34
    5004  207.84  5007.5  207.84  5014.1  211.96  5019.8  214.36  5028.5  214.09
    5036  212.81  5051.3  213.74  5063.5  213.48  5073.9  215.07  5079.6  214.81
  5139.4  220.42  5210.7  225.88  5256.3  227.75  5346.4  233.59  5352.1  233.19
#Mann= 3 , 0 , 0
  4712.3     .17       0  4970.9     .09       0  5019.8     .17       0
Bank Sta=4970.9,5019.8
XS Rating Curve= 0 ,0
Exp/Cntr=0.3,0.1

Type RM Length L Ch R = 1 ,472     ,334,334,334
BEGIN DESCRIPTION:
Conroe Lake 003 2.0
END DESCRIPTION:
XS GIS Cut Line= 3
       3815663.1     10129473.31      3815621.94     10129203.63
      3815362.37     10128949.02
#Sta/Elev= 30
  4727.2   233.7  4790.1  232.39  4795.2  232.93  4800.3  232.11  4820.5  230.71
  4850.9  229.16  4871.1  226.52  4921.7   222.2  4932.3  220.26    4952   218.8
  4982.4   214.2  4990.7  208.05  4993.8  206.75    4994  206.25  4997.5  206.25
  4998.8  208.33  5005.4  208.33  5047.2  213.41  5061.3  213.16  5082.5  214.42
  5110.8  215.18  5139.1  217.69  5146.1  217.34  5153.2  218.34  5216.8  221.17
  5238.1  223.41  5301.7  228.63  5315.8  229.17  5344.1  231.51  5363.6  231.91
#Mann= 3 ,-1 , 0
  4727.2     .17       0  4982.4     .09       0  5047.2     .17       0
Bank Sta=4982.4,5047.2
XS Rating Curve= 0 ,0
Exp/Cntr=0.3,0.1

Type RM Length L Ch R = 1 ,138     ,0,0,0
BEGIN DESCRIPTION:
Conroe Lake 003 15.0
END DESCRIPTION:
XS GIS Cut Line= 4
      3815701.91     10129466.61      3815760.77     10129149.21
        3815699.      10128985.8      3815431.27      10128848.7
#Sta/Elev= 30
  4502.5  231.61  4510.4  230.62  4558.2  230.58  4569.2  228.84  4630.2  226.44
  4650.5  227.02  4711.5  224.63  4726.9  222.89  4762.4  221.25  4779.8  219.12
  4792.9  219.61  4803.1  217.82  4866.1  213.32  4903.9  212.61  4919.5  213.78
  4940.9  212.33  4958.9  208.79  4989.1  209.04  4992.7   205.4  5003.5  205.91
  5012.5  207.59  5019.7  211.01  5025.4  212.38  5047.6  212.34  5057.5  210.96
  5158.6  222.53  5197.4  225.98    5214  226.52    5226  228.06  5300.8  230.31
#Mann= 4 ,-1 , 0
  4502.5     .15       0  4919.5     .12       0  4940.9     .09       0
  5025.4     .15       0
Bank Sta=4940.9,5025.4
XS Rating Curve= 0 ,0
Exp/Cntr=0.3,0.1

Chan Stop Cuts=-1
Use User Specified Reach Order=0
Composite Channel Slope=5