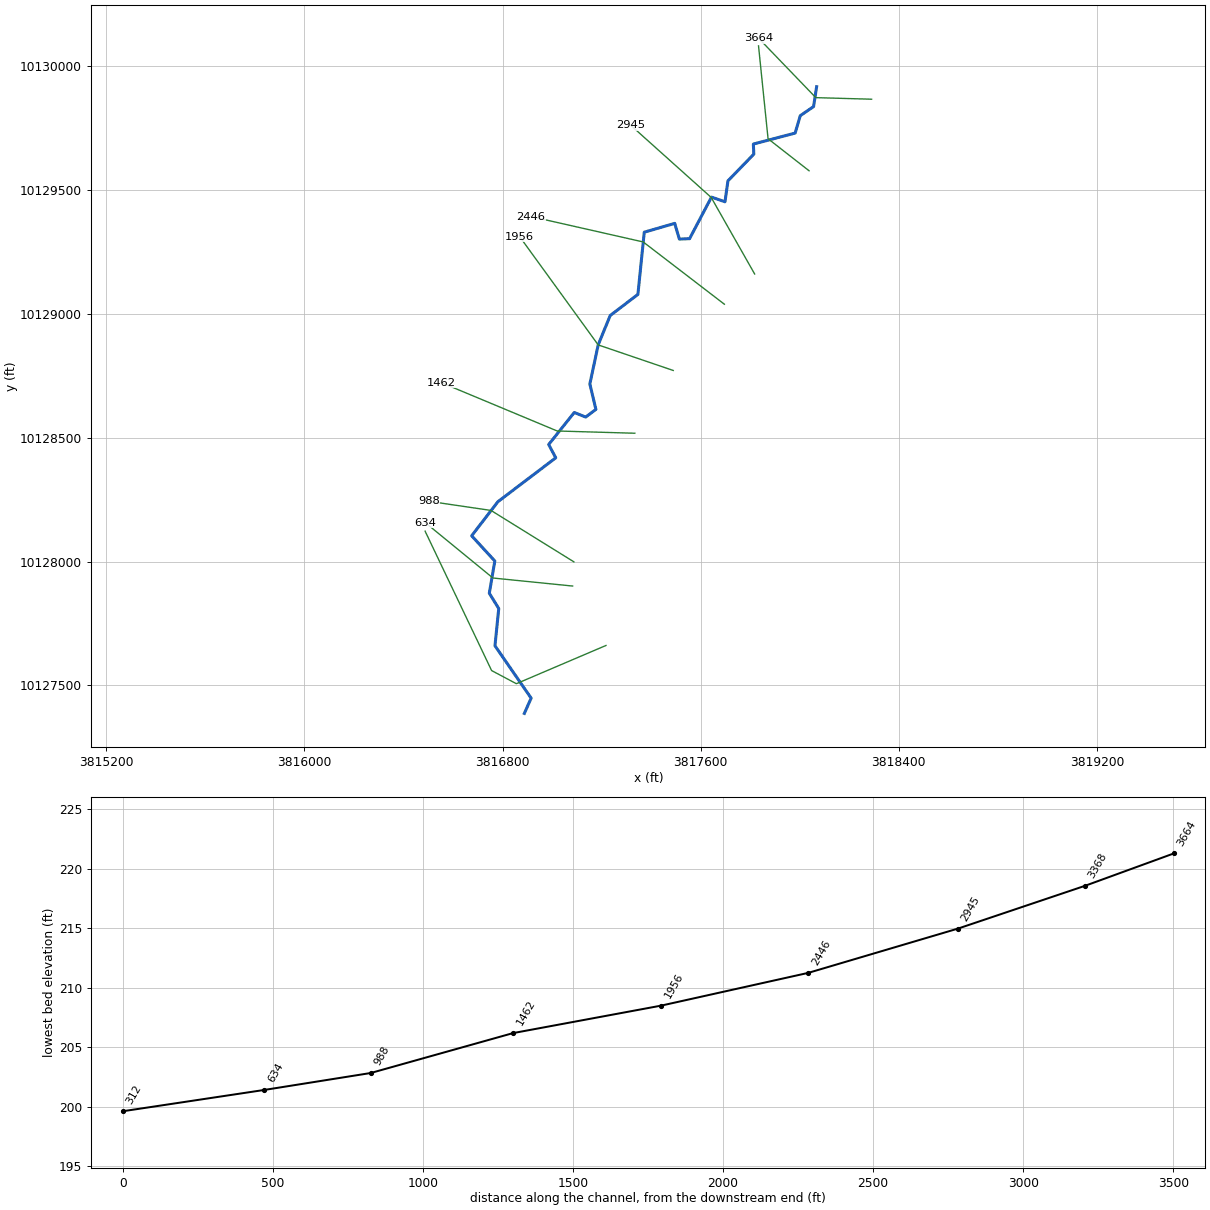
--- Conroe Lake 005.prj (project) ---

Proj Title=Conroe Lake 005 Base Level Engineering
Current Plan=p01
Default Exp/Contr=0.3,0.1
English Units
Geom File=g01
Flow File=f01
Flow File=f02
Plan File=p01
Y Axis Title=Elevation
X Axis Title(PF)=Main Channel Distance
X Axis Title(XS)=Station
BEGIN DESCRIPTION:
Conroe Lake 005
END DESCRIPTION:
DSS Export Rating Curves= 0
DSS Export Rating Curve Sorted= 0
DSS Export Volume Flow Curves= 0
DXF OffsetX= 0
DXF OffsetY= 0
DXF ScaleX= 1
DXF ScaleY= 10

--- Conroe Lake 005.p01 (plan) ---

Plan Title=Multiple Run
Short Identifier=Multiple
Geom File=g01
Flow File=f01
Subcritical Flow
K Sum by GR= 0
Std Step Tol= 0.01
Critical Tol= 0.01
Num of Std Step Trials= 20
Max Error Tol= 0.3
Flow Tol Ratio= 0.001
Split Flow NTrial= 30
Split Flow Tol= 0.02
Split Flow Ratio= 0.02
Log Output Level= 0
Friction Slope Method= 1
Unsteady Friction Slope Method= 2
Unsteady Bridges Friction Slope Method= 1
Parabolic Critical Depth
Global Vel Dist=  1 , 1 , 1
Global Log Level= 0
CheckData=True
Encroach Param= -1, 0, 0, 0
BEGIN DESCRIPTION:
Multiple Run
END DESCRIPTION:

--- Conroe Lake 005.f01 (steady flow) ---

Flow Title=Multiple
Program Version=4.10
Number of Profiles= 7
Profile Names=10-year,25-year,50-year,1pct_min,100-year,1pct_plu,500-year
River Rch & RM=Conroe Lake 005,Reach-1         ,3664
     649     885    1205     540    1632    4929    3091
River Rch & RM=Conroe Lake 005,Reach-1         ,2945
     744    1022    1395     627    1895    5723    3612
River Rch & RM=Conroe Lake 005,Reach-1         ,312
    1664    2378    3333    1533    4629   13979    9245
Boundary for River Rch & Prof#=Conroe Lake 005,Reach-1         , 1
Up Type= 0
Dn Type= 3
Dn Slope=0.005
Boundary for River Rch & Prof#=Conroe Lake 005,Reach-1         , 2
Up Type= 0
Dn Type= 3
Dn Slope=0.005
Boundary for River Rch & Prof#=Conroe Lake 005,Reach-1         , 3
Up Type= 0
Dn Type= 3
Dn Slope=0.005
Boundary for River Rch & Prof#=Conroe Lake 005,Reach-1         , 4
Up Type= 0
Dn Type= 3
Dn Slope=0.005
Boundary for River Rch & Prof#=Conroe Lake 005,Reach-1         , 5
Up Type= 0
Dn Type= 3
Dn Slope=0.005
Boundary for River Rch & Prof#=Conroe Lake 005,Reach-1         , 6
Up Type= 0
Dn Type= 3
Dn Slope=0.005
Boundary for River Rch & Prof#=Conroe Lake 005,Reach-1         , 7
Up Type= 0
Dn Type= 3
Dn Slope=0.005
DSS Import GetInterval= 0
DSS Import GetPeak= 0
DSS Import FillOption= 0

--- Conroe Lake 005.f02 (steady flow) ---

Flow Title=Orig_BLE_Flow
Program Version=4.10
Number of Profiles= 7
Profile Names=10-year,25-year,50-year,1pct_min,100-year,1pct_plu,500-year
River Rch & RM=Conroe Lake 005,Reach-1         ,3664
     649     868    1048     416    1255    3791    1797
River Rch & RM=Conroe Lake 005,Reach-1         ,2945
     744    1002    1213     483    1458    4403    2100
River Rch & RM=Conroe Lake 005,Reach-1         ,312
    1664    2331    2898    1179    3561   10755    5375
Boundary for River Rch & Prof#=Conroe Lake 005,Reach-1         , 1
Up Type= 0
Dn Type= 3
Dn Slope=0.02
Boundary for River Rch & Prof#=Conroe Lake 005,Reach-1         , 2
Up Type= 0
Dn Type= 3
Dn Slope=0.02
Boundary for River Rch & Prof#=Conroe Lake 005,Reach-1         , 3
Up Type= 0
Dn Type= 3
Dn Slope=0.02
Boundary for River Rch & Prof#=Conroe Lake 005,Reach-1         , 4
Up Type= 0
Dn Type= 3
Dn Slope=0.02
Boundary for River Rch & Prof#=Conroe Lake 005,Reach-1         , 5
Up Type= 0
Dn Type= 3
Dn Slope=0.02
Boundary for River Rch & Prof#=Conroe Lake 005,Reach-1         , 6
Up Type= 0
Dn Type= 3
Dn Slope=0.02
Boundary for River Rch & Prof#=Conroe Lake 005,Reach-1         , 7
Up Type= 0
Dn Type= 3
Dn Slope=0.02
DSS Import GetInterval= 0
DSS Import GetPeak= 0
DSS Import FillOption= 0

--- Conroe Lake 005.g01 (geometry) ---

Geom Title=Existing Conditions
Program Version=4.10

River Reach=Conroe Lake 005 ,Reach-1
Reach XY= 30
      3818068.23     10129916.84       3818055.9     10129836.76
      3818002.19     10129800.09      3817981.42     10129729.81
      3817812.71     10129685.46       3817814.7      10129644.9
      3817710.16     10129536.94      3817698.17     10129452.52
      3817643.59     10129471.31      3817555.27     10129303.49
      3817513.95     10129301.87      3817495.23     10129365.29
      3817372.28     10129329.66       3817346.6     10129078.46
      3817234.67     10128993.05      3817186.22     10128874.58
      3817152.63     10128716.73      3817176.98      10128614.3
      3817135.84     10128583.24      3817089.66     10128601.71
      3816986.39     10128472.41      3817014.94     10128418.67
       3816781.3     10128241.46      3816675.33     10128103.89
      3816768.91     10128001.95      3816746.62     10127871.82
      3816784.72     10127810.27       3816769.5      10127659.8
       3816915.5     10127448.42      3816888.23     10127386.84

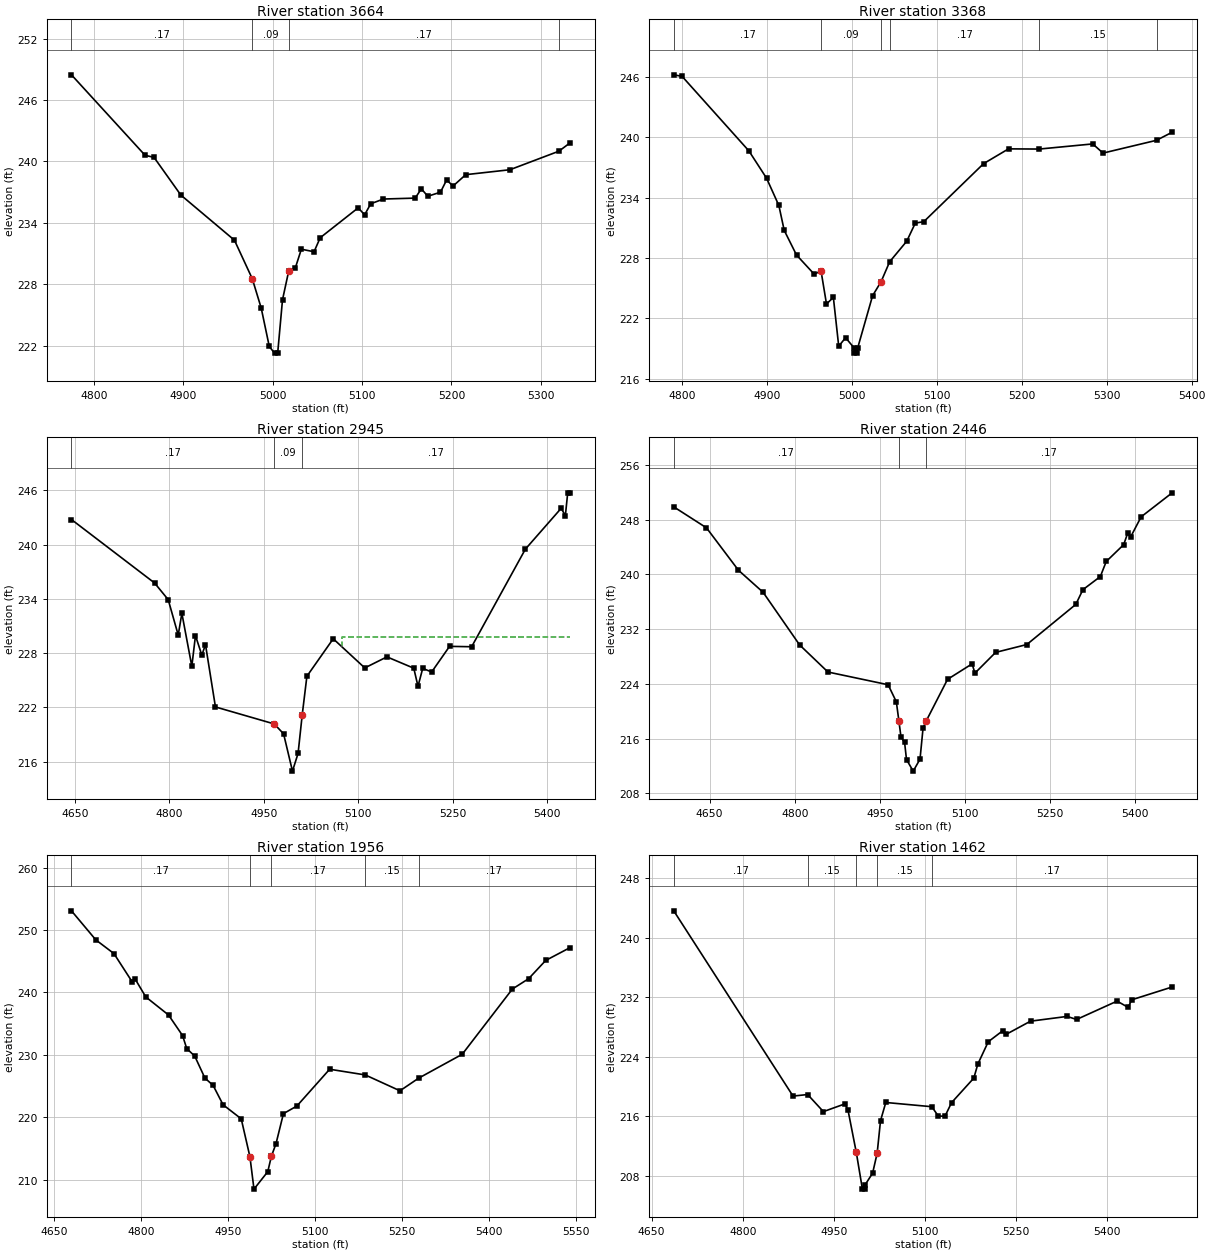
Type RM Length L Ch R = 1 ,3664    ,296,296,296
BEGIN DESCRIPTION:
Conroe Lake 005 7.5
END DESCRIPTION:
XS GIS Cut Line= 3
       3818290.2     10129866.57      3818064.99     10129872.91
      3817834.29     10130112.36
#Sta/Elev= 30
  4774.7  248.46  4857.1   240.6  4867.1   240.4  4897.1  236.72  4957.1  232.31
  4977.1  228.54  4987.1  225.67  4996.1  221.93    5002  221.28  5005.5  221.28
  5010.9  226.49  5017.9  229.32  5025.1  229.56    5032  231.43  5046.2  231.18
  5053.1  232.55  5095.6  235.47  5102.8  234.79  5109.7  235.87  5123.9  236.33
  5159.4  236.42  5166.3  237.33  5173.5   236.6  5187.7     237  5194.6  238.19
  5201.8   237.6    5216  238.71  5265.4  239.19  5320.2     241  5332.5   241.8
#Mann= 4 ,-1 , 0
  4774.7     .17       0  4977.1     .09       0  5017.9     .17       0
  5320.2     .11       0
Bank Sta=4977.1,5017.9
XS Rating Curve= 0 ,0
Exp/Cntr=0.3,0.1

Type RM Length L Ch R = 1 ,3368    ,423,423,423
BEGIN DESCRIPTION:
Conroe Lake 005 7.0
END DESCRIPTION:
XS GIS Cut Line= 3
      3818037.61     10129577.71      3817872.11     10129706.98
      3817833.61     10130082.01
#Sta/Elev= 30
    4790  246.19  4799.8  246.04  4878.5  238.64  4899.3  235.93  4913.8  233.22
  4920.1  230.75  4934.6   228.3  4955.4   226.4  4963.5  226.71  4969.9  223.44
    4978  224.09  4984.3  219.25  4992.4  220.09  5002.6  219.06  5002.8  218.56
  5006.3  218.56  5006.6  219.06  5024.2  224.26  5034.3  225.67  5044.3  227.63
  5064.4  229.67  5074.5  231.47  5084.5  231.61  5154.9  237.37  5184.3  238.84
  5220.5  238.82  5283.5  239.33  5295.6  238.42  5358.6  239.69    5377  240.49
#Mann= 6 ,-1 , 0
    4790     .17       0  4963.5     .09       0  5034.3     .12       0
  5044.3     .17       0  5220.5     .15       0  5358.6     .11       0
Bank Sta=4963.5,5034.3
XS Rating Curve= 0 ,0
Exp/Cntr=0.3,0.1

Type RM Length L Ch R = 1 ,2945    ,499,499,499
BEGIN DESCRIPTION:
Conroe Lake 005 6.0
END DESCRIPTION:
XS GIS Cut Line= 3
      3817817.87     10129161.03      3817642.48     10129470.02
      3817317.85     10129761.07
#Sta/Elev= 30
  4644.7  242.76  4776.7  235.75  4798.3  233.91  4814.2     230    4820   232.4
  4835.8  226.55  4841.6  229.94  4851.7  227.78  4857.5  228.95  4873.3  222.06
  4966.7  220.18  4981.5  219.09  4995.6  214.97  5004.5  216.93    5011  221.14
  5018.5  225.45  5060.3  229.59  5110.4  226.37  5145.6  227.59  5188.2  226.34
  5194.9  224.34  5202.4  226.32  5216.6  225.92    5245  228.75  5280.1  228.71
  5365.4  239.49  5422.2     244  5428.9  243.19  5432.6  245.71    5436  245.71
#Mann= 3 , 0 , 0
  4644.7     .17       0  4966.7     .09       0    5011     .17       0
#XS Ineff= 2 , 0
       0                  5074.5       0  229.84
Permanent Ineff=
       F       F
Bank Sta=4966.7,5011
XS Rating Curve= 0 ,0
Exp/Cntr=0.3,0.1

Type RM Length L Ch R = 1 ,2446    ,490,490,490
BEGIN DESCRIPTION:
Conroe Lake 005 5.0
END DESCRIPTION:
XS GIS Cut Line= 3
      3817695.83     10129038.75       3817368.1     10129290.23
      3816914.57     10129392.91
#Sta/Elev= 30
  4586.9  249.89  4644.6  246.82  4700.8  240.63  4744.3   237.4  4808.7   229.7
  4858.6  225.74  4964.6  223.88  4979.1  221.38 4983.53  218.62  4987.3  216.22
  4993.6  215.46    4997  212.94  5008.8  211.25  5020.8     213  5026.2  217.58
  5031.3  218.52  5069.3  224.67  5112.5  226.93  5117.6  225.58    5154  228.61
    5209  229.76  5295.3  235.63  5307.8  237.78  5338.5   239.7  5348.9   241.9
  5379.6  244.36  5386.7  246.04  5391.9  245.49  5410.4  248.43    5465  251.94
#Mann= 3 , 0 , 0
  4586.9     .17       0 4983.53     .09       0  5031.3     .17       0
Bank Sta=4983.53,5031.3
XS Rating Curve= 0 ,0
Exp/Cntr=0.3,0.1

Type RM Length L Ch R = 1 ,1956    ,494,494,494
BEGIN DESCRIPTION:
Conroe Lake 005 4.0
END DESCRIPTION:
XS GIS Cut Line= 3
      3817489.23     10128771.38      3817186.22     10128874.58
      3816869.46      10129311.3
#Sta/Elev= 30
  4679.9  253.07  4721.9  248.42  4753.2  246.22  4784.6   241.7  4789.9  242.12
  4808.1  239.28  4847.3  236.39  4871.5   233.1  4878.7  231.02  4892.6  229.79
    4910   226.3  4924.3   225.1  4941.4  222.01  4972.7  219.76  4987.7  213.69
  4994.7   208.5  5018.5   211.3  5024.7  213.76  5032.7  215.78  5045.5  220.59
  5068.7  221.81  5125.2   227.7  5186.6  226.79  5246.5  224.25  5278.7  226.27
  5353.9   230.1  5440.4  240.55  5468.4   242.2  5497.8  245.12  5539.5  247.16
#Mann= 5 ,-1 , 0
  4679.9     .17       0  4987.7     .09       0  5024.7     .17       0
  5186.6     .15       0  5278.7     .17       0
Bank Sta=4987.7,5024.7
XS Rating Curve= 0 ,0
Exp/Cntr=0.3,0.1

Type RM Length L Ch R = 1 ,1462    ,474,474,474
BEGIN DESCRIPTION:
Conroe Lake 005 3.0
END DESCRIPTION:
XS GIS Cut Line= 3
      3817334.28      10128517.9      3817020.81     10128526.98
      3816552.55     10128722.39
#Sta/Elev= 30
  4686.4  243.64  4882.9  218.71    4907  218.92  4932.9  216.62  4968.3  217.66
  4973.3  216.89 4987.14  211.12  4997.2  206.19  5000.7  206.19    5001  206.69
    5014  208.34  5021.5  211.03    5027  215.39  5035.7  217.85  5111.5  217.28
  5122.2  216.02  5133.2     216  5144.1  217.83  5180.7  221.13  5187.4  223.03
  5204.5  226.02  5228.3   227.5  5233.8  227.01  5274.1  228.79  5334.4  229.43
    5350  229.02  5416.7  231.49  5435.1  230.64  5440.6  231.66  5507.4  233.39
#Mann= 5 ,-1 , 0
  4686.4     .17       0    4907     .15       0 4987.14     .09       0
  5021.5     .15       0  5111.5     .17       0
Bank Sta=4987.14,5021.5
XS Rating Curve= 0 ,0
Exp/Cntr=0.3,0.1

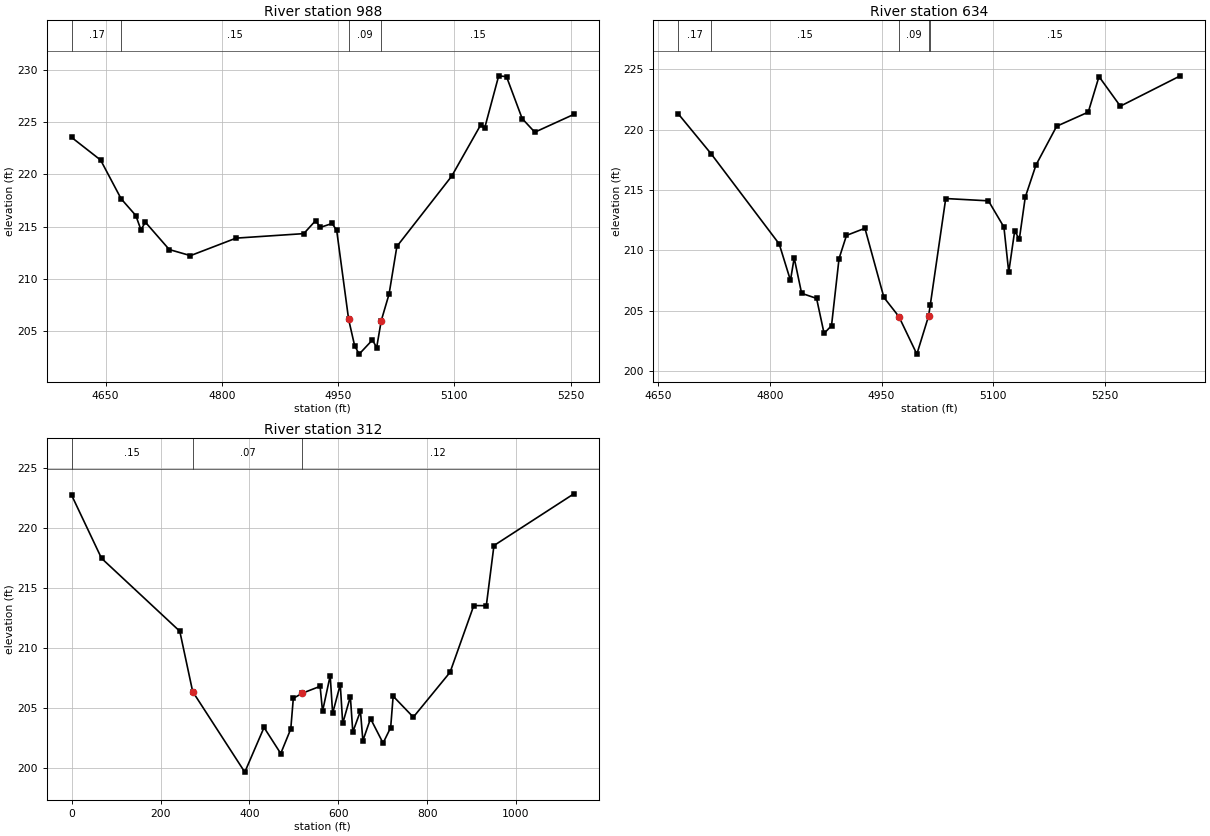
Type RM Length L Ch R = 1 ,988     ,354,354,354
BEGIN DESCRIPTION:
Conroe Lake 005 2.0
END DESCRIPTION:
XS GIS Cut Line= 3
       3817088.2      10127998.6      3816753.48     10128206.26
      3816501.89     10128243.24
#Sta/Elev= 30
  4606.1  223.52  4643.5  221.36    4670  217.66  4688.9  216.07  4695.5  214.71
  4701.3  215.43  4732.1  212.82  4759.5  212.24  4818.3  213.91  4905.7  214.34
  4921.1  215.59  4926.9  214.93  4942.3  215.31  4948.2  214.65  4963.6  206.16
  4971.3  203.66  4977.2  202.84  4994.3  204.19  4999.8  203.47  5005.7  206.03
  5015.8  208.57  5025.9  213.12  5096.7  219.83  5134.1  224.72  5139.2  224.41
  5157.3   229.4  5167.4  229.32  5187.6  225.32  5203.9  224.02  5254.3  225.72
#Mann= 4 ,-1 , 0
  4606.1     .17       0    4670     .15       0  4963.6     .09       0
  5005.7     .15       0
Bank Sta=4963.6,5005.7
XS Rating Curve= 0 ,0
Exp/Cntr=0.3,0.1

Type RM Length L Ch R = 1 ,634     ,472,472,472
BEGIN DESCRIPTION:
Mapping XS 1865088a
END DESCRIPTION:
XS GIS Cut Line= 3
      3817083.05     10127900.93      3816761.28     10127933.36
      3816489.26     10128156.13
#Sta/Elev= 30
  4676.6  221.31  4721.1  217.98  4812.5  210.53  4827.6  207.52  4832.6  209.38
  4842.6  206.45  4862.7  206.03  4872.8  203.13  4882.8  203.78  4892.9  209.32
  4902.9  211.24  4927.7  211.83  4953.2  206.11  4973.3  204.53  4997.5  201.42
 5013.21  204.56  5015.5  205.47  5036.3  214.29  5093.7   214.1  5114.5  211.93
    5121   208.2  5128.9  211.58  5135.3  210.96  5143.2   214.4  5157.6  217.06
  5185.4  220.27  5227.9  221.44  5242.3  224.38    5271  221.93  5351.6  224.44
#Mann= 5 ,-1 , 0
  4676.6     .17       0  4721.1     .15       0  4973.3     .09       0
 5013.21     .12       0  5015.5     .15       0
Bank Sta=4973.3,5013.21
XS Rating Curve= 0 ,0
Exp/Cntr=0.3,0.1

Type RM Length L Ch R = 1 ,312     ,0,0,0
XS GIS Cut Line= 4
      3817217.85     10127661.07      3816855.88     10127506.63
      3816755.97     10127559.68       3816487.4     10128122.52
#Sta/Elev= 30
       0   222.7    67.2  217.45   243.4  211.37   272.4  206.34   389.7  199.63
     433  203.35   470.6  201.18   493.2  203.23   498.9  205.78   519.4  206.21
   559.2  206.78   564.7   204.7   581.9  207.67   587.4  204.53   604.6  206.93
   610.1  203.69   627.3  205.92   632.8  202.98     650  204.71   655.5  202.25
   672.7  204.09   700.9  202.05     718  203.34   723.6  205.96     769  204.21
   851.7  207.95   905.1  213.51   933.3   213.5   950.5  218.51  1130.3  222.82
#Mann= 3 , 0 , 0
       0     .15       0   272.4     .07       0   519.4     .12       0
Bank Sta=272.4,519.4
XS Rating Curve= 0 ,0
Exp/Cntr=0.3,0.1

Chan Stop Cuts=-1
Use User Specified Reach Order=0
Composite Channel Slope=5