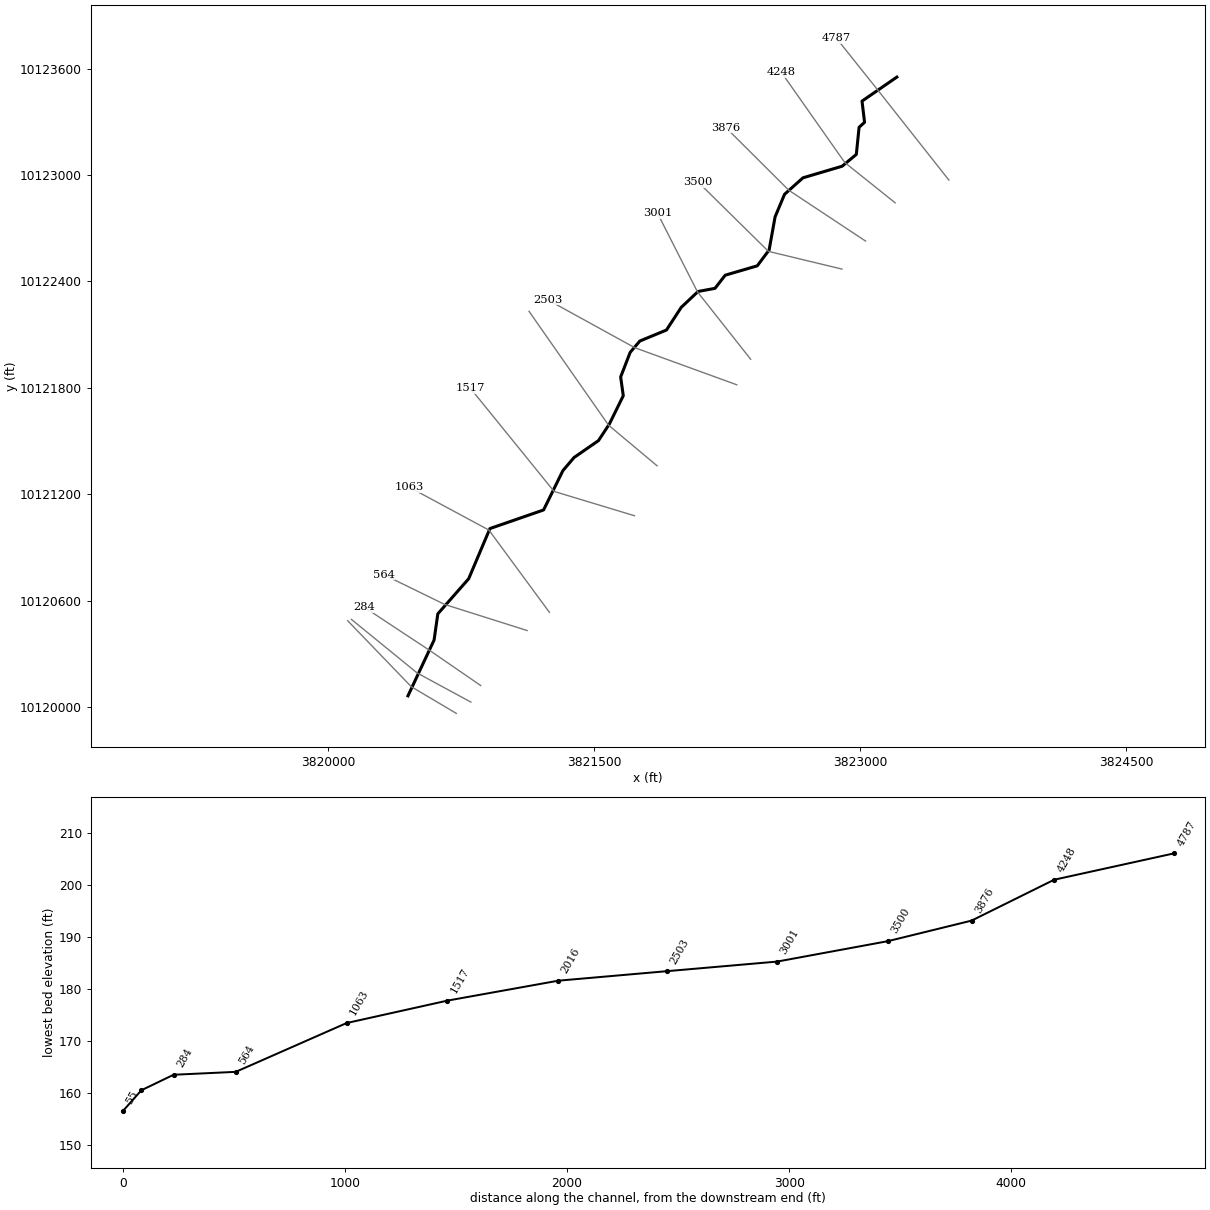
--- Conroe Lake 007.prj (project) ---

Proj Title=Conroe Lake 007 Base Level Engineering
Current Plan=p01
Default Exp/Contr=0.3,0.1
English Units
Geom File=g01
Flow File=f01
Flow File=f02
Plan File=p01
Y Axis Title=Elevation
X Axis Title(PF)=Main Channel Distance
X Axis Title(XS)=Station
BEGIN DESCRIPTION:
Conroe Lake 007
END DESCRIPTION:
DSS Export Rating Curves= 0
DSS Export Rating Curve Sorted= 0
DSS Export Volume Flow Curves= 0
DXF OffsetX= 0
DXF OffsetY= 0
DXF ScaleX= 1
DXF ScaleY= 10

--- Conroe Lake 007.p01 (plan) ---

Plan Title=Multiple Run
Short Identifier=Multiple
Geom File=g01
Flow File=f01
Subcritical Flow
K Sum by GR= 0
Std Step Tol= 0.01
Critical Tol= 0.01
Num of Std Step Trials= 20
Max Error Tol= 0.3
Flow Tol Ratio= 0.001
Split Flow NTrial= 30
Split Flow Tol= 0.02
Split Flow Ratio= 0.02
Log Output Level= 0
Friction Slope Method= 1
Unsteady Friction Slope Method= 2
Unsteady Bridges Friction Slope Method= 1
Parabolic Critical Depth
Global Vel Dist=  1 , 1 , 1
Global Log Level= 0
CheckData=True
Encroach Param= -1, 0, 0, 0
BEGIN DESCRIPTION:
Multiple Run
END DESCRIPTION:

--- Conroe Lake 007.f01 (steady flow) ---

Flow Title=Multiple
Program Version=4.10
Number of Profiles= 7
Profile Names=10-year,25-year,50-year,1pct_min,100-year,1pct_plu,500-year
River Rch & RM=Conroe Lake 007,Reach-1         ,4787
     496     663     890     393    1188    3588    2190
River Rch & RM=Conroe Lake 007,Reach-1         ,4248
     804    1107    1513     681    2057    6212    3925
Boundary for River Rch & Prof#=Conroe Lake 007,Reach-1         , 1
Up Type= 0
Dn Type= 3
Dn Slope=0.005
Boundary for River Rch & Prof#=Conroe Lake 007,Reach-1         , 2
Up Type= 0
Dn Type= 3
Dn Slope=0.005
Boundary for River Rch & Prof#=Conroe Lake 007,Reach-1         , 3
Up Type= 0
Dn Type= 3
Dn Slope=0.005
Boundary for River Rch & Prof#=Conroe Lake 007,Reach-1         , 4
Up Type= 0
Dn Type= 3
Dn Slope=0.005
Boundary for River Rch & Prof#=Conroe Lake 007,Reach-1         , 5
Up Type= 0
Dn Type= 3
Dn Slope=0.005
Boundary for River Rch & Prof#=Conroe Lake 007,Reach-1         , 6
Up Type= 0
Dn Type= 3
Dn Slope=0.005
Boundary for River Rch & Prof#=Conroe Lake 007,Reach-1         , 7
Up Type= 0
Dn Type= 3
Dn Slope=0.005
DSS Import GetInterval= 0
DSS Import GetPeak= 0
DSS Import FillOption= 0

--- Conroe Lake 007.f02 (steady flow) ---

Flow Title=Orig_BLE_Flow
Program Version=4.10
Number of Profiles= 7
Profile Names=10-year,25-year,50-year,1pct_min,100-year,1pct_plu,500-year
River Rch & RM=Conroe Lake 007,Reach-1         ,4787
     496     650     774     303     914    2762    1273
River Rch & RM=Conroe Lake 007,Reach-1         ,4248
     804    1085    1316     524    1582    4778    2282
Boundary for River Rch & Prof#=Conroe Lake 007,Reach-1         , 1
Up Type= 0
Dn Type= 3
Dn Slope=0.005
Boundary for River Rch & Prof#=Conroe Lake 007,Reach-1         , 2
Up Type= 0
Dn Type= 3
Dn Slope=0.005
Boundary for River Rch & Prof#=Conroe Lake 007,Reach-1         , 3
Up Type= 0
Dn Type= 3
Dn Slope=0.005
Boundary for River Rch & Prof#=Conroe Lake 007,Reach-1         , 4
Up Type= 0
Dn Type= 3
Dn Slope=0.005
Boundary for River Rch & Prof#=Conroe Lake 007,Reach-1         , 5
Up Type= 0
Dn Type= 3
Dn Slope=0.005
Boundary for River Rch & Prof#=Conroe Lake 007,Reach-1         , 6
Up Type= 0
Dn Type= 3
Dn Slope=0.005
Boundary for River Rch & Prof#=Conroe Lake 007,Reach-1         , 7
Up Type= 0
Dn Type= 3
Dn Slope=0.005
DSS Import GetInterval= 0
DSS Import GetPeak= 0
DSS Import FillOption= 0

--- Conroe Lake 007.g01 (geometry) ---

Geom Title=Existing Conditions
Program Version=4.10

River Reach=Conroe Lake 007 ,Reach-1
Reach XY= 30
      3823206.12     10123551.66      3823009.58     10123416.09
      3823024.03     10123296.77      3822993.08     10123268.43
      3822977.49     10123115.49      3822897.35     10123048.96
      3822676.65     10122983.64      3822572.86     10122890.78
      3822519.44     10122763.44      3822485.91     10122576.86
      3822418.93     10122487.42       3822238.2     10122434.52
      3822180.64     10122360.45      3822085.04     10122342.75
      3821990.17     10122253.05      3821907.02     10122125.43
      3821756.98     10122063.47      3821702.45      10121999.5
      3821648.75     10121860.82      3821663.53     10121755.02
      3821584.99      10121595.3      3821523.77     10121502.06
      3821385.73     10121406.44      3821323.09     10121332.62
      3821214.17      10121110.9      3820911.56     10121006.03
      3820791.83     10120723.07      3820617.88     10120525.25
      3820596.82     10120377.56      3820449.51     10120062.81

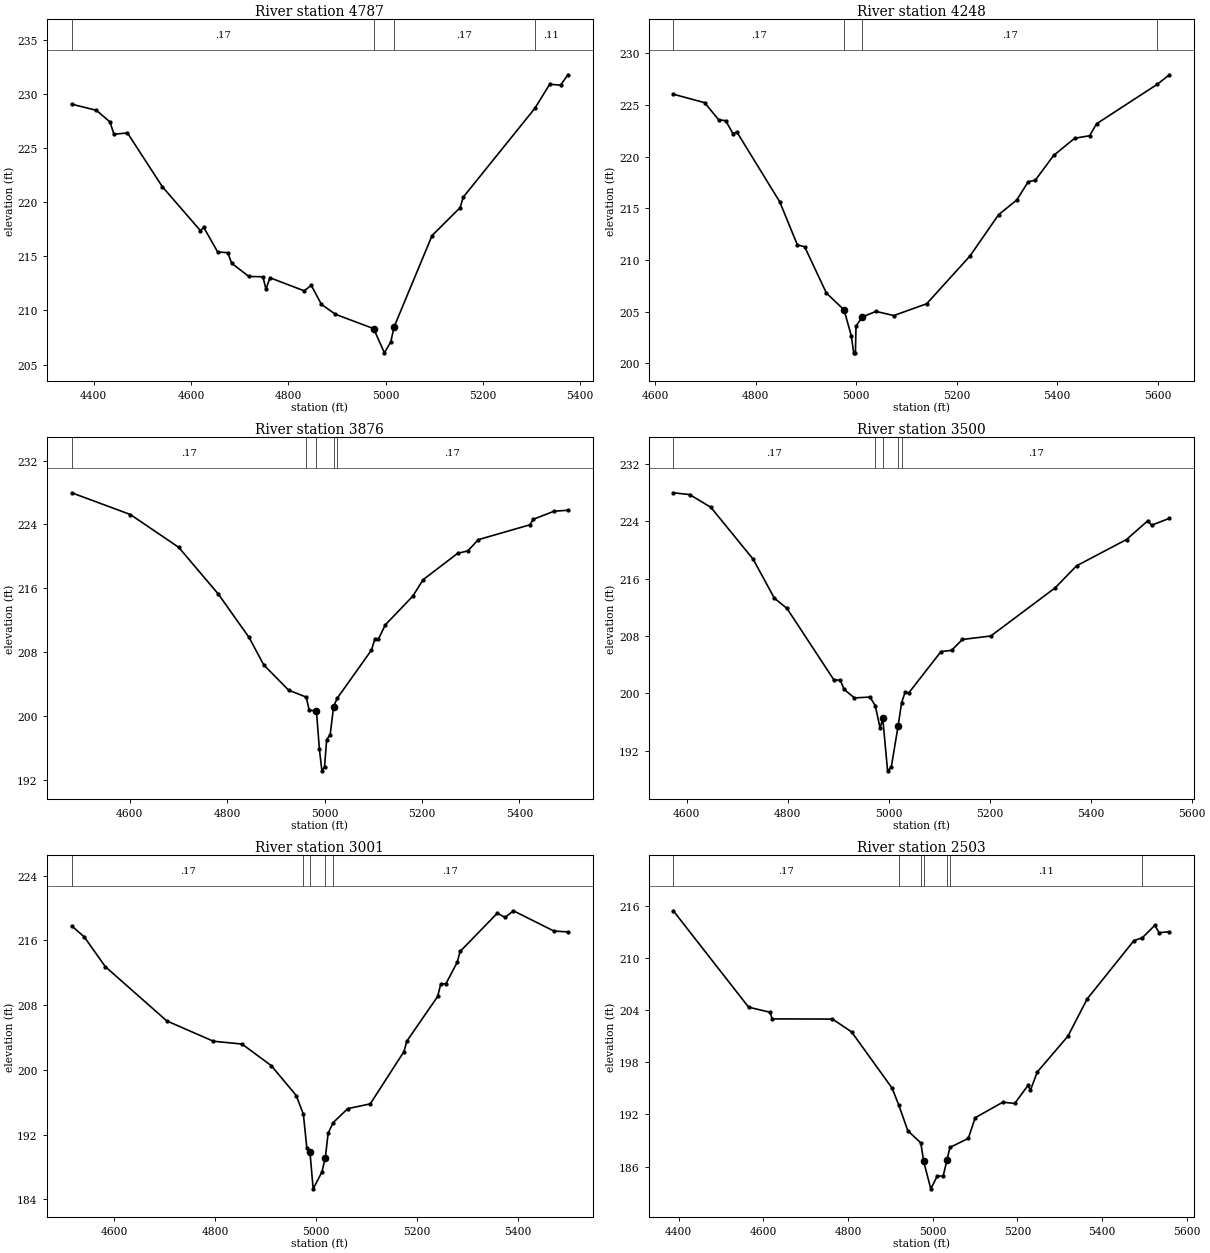
Type RM Length L Ch R = 1 ,4787    ,539,539,539
BEGIN DESCRIPTION:
Conroe Lake 007 10.0
END DESCRIPTION:
XS GIS Cut Line= 3
      3823499.24     10122971.12      3823099.26     10123477.64
      3822865.67      10123770.1
#Sta/Elev= 30
  4354.6   229.1  4405.5  228.53  4433.4  227.45  4441.5  226.31  4469.2  226.44
  4540.8  221.47  4619.4  217.38  4625.8  217.71  4654.7  215.42  4675.5  215.35
  4683.5  214.37  4718.8  213.15  4747.7  213.12    4754  211.97  4762.1  213.03
  4832.6  211.82    4847  212.33  4867.9  210.57  4896.7  209.65  4975.3  208.32
  4997.3  206.08  5010.5  207.09  5017.2  208.47  5095.4  216.94    5153  219.52
  5159.4  220.49  5306.7  228.72  5337.1  230.94  5359.6  230.86  5374.3  231.82
#Mann= 4 ,-1 , 0
  4354.6     .17       0  4975.3     .09       0  5017.2     .17       0
  5306.7     .11       0
Bank Sta=4975.3,5017.2
XS Rating Curve= 0 ,0
Exp/Cntr=0.3,0.1

Type RM Length L Ch R = 1 ,4248    ,372,372,372
BEGIN DESCRIPTION:
Mapping XS 7ecede4c
END DESCRIPTION:
XS GIS Cut Line= 3
      3823196.47     10122842.67      3822912.53     10123069.79
      3822554.08     10123579.58
#Sta/Elev= 30
  4636.4  226.05  4698.7  225.23  4726.3  223.59  4740.7  223.48  4755.1  222.23
  4762.7   222.4  4847.9  215.65  4883.2  211.46  4897.6  211.29  4940.8  206.81
    4976  205.18  4990.4  202.67  4995.1  201.02  4998.6  201.02  4999.8  203.62
  5012.3  204.49  5039.3  205.03    5075  204.63  5140.3  205.77  5226.6   210.4
  5283.2  214.38  5319.4  215.81  5342.5  217.59  5356.1  217.71  5392.8  220.12
  5434.8  221.79  5464.4  222.03  5478.3  223.19  5598.4  226.99  5623.2  227.93
#Mann= 4 ,-1 , 0
  4636.4     .17       0    4976     .09       0  5012.3     .17       0
  5598.4     .11       0
Bank Sta=4976,5012.3
XS Rating Curve= 0 ,0
Exp/Cntr=0.3,0.1

Type RM Length L Ch R = 1 ,3876    ,376,376,376
BEGIN DESCRIPTION:
Conroe Lake 007 9.0
END DESCRIPTION:
XS GIS Cut Line= 3
      3823029.62     10122627.04      3822596.69     10122913.64
      3822242.89      10123266.1
#Sta/Elev= 30
  4480.8  227.97  4601.3  225.25  4700.6  221.14  4781.9  215.29    4845  209.86
  4875.1  206.43  4926.3  203.26  4962.4  202.39  4968.4  200.78  4983.4  200.62
  4989.4  195.88  4994.6  193.16    5000  193.66  5004.4  197.08  5011.5  197.66
  5018.6  201.19  5025.7  202.22  5096.4  208.28  5103.4  209.71  5110.5  209.65
  5124.7  211.43  5181.2  215.03  5202.4  217.09  5273.1  220.38  5294.4   220.7
  5315.6   222.1  5421.6  223.96  5428.7  224.65  5471.1  225.66  5499.4  225.78
#Mann= 5 ,-1 , 0
  4480.8     .17       0  4962.4     .12       0  4983.4     .09       0
  5018.6     .12       0  5025.7     .17       0
Bank Sta=4983.4,5018.6
XS Rating Curve= 0 ,0
Exp/Cntr=0.3,0.1

Type RM Length L Ch R = 1 ,3500    ,499,499,499
BEGIN DESCRIPTION:
Conroe Lake 007 8.0
END DESCRIPTION:
XS GIS Cut Line= 3
       3822896.7     10122469.04      3822481.87     10122568.99
      3822085.93     10122959.34
#Sta/Elev= 30
  4573.3  227.96  4605.7  227.71  4647.6  225.94  4731.5   218.7  4773.4  213.28
  4798.4  211.85    4891  201.93  4904.3  201.82  4911.6  200.57  4932.1  199.38
    4963   199.5  4973.3  198.29    4983  195.14  4988.1  196.58  4997.7  189.22
    5005  189.72  5018.5  195.45  5025.5  198.72  5032.6  200.21  5039.7  200.08
  5103.4  205.83  5124.5  206.01  5145.8  207.52  5202.3  208.01  5329.5  214.71
    5372  217.78    5471  221.45  5513.4  224.08  5520.5  223.44    5556   224.4
#Mann= 5 ,-1 , 0
  4573.3     .17       0  4973.3     .12       0  4988.1     .09       0
  5018.5     .12       0  5025.5     .17       0
Bank Sta=4988.1,5018.5
XS Rating Curve= 0 ,0
Exp/Cntr=0.3,0.1

Type RM Length L Ch R = 1 ,3001    ,498,498,498
BEGIN DESCRIPTION:
Conroe Lake 007 7.0
END DESCRIPTION:
XS GIS Cut Line= 3
      3822381.73     10121960.71      3822081.96     10122340.44
      3821855.67      10122785.4
#Sta/Elev= 30
  4516.2  217.78  4541.2  216.42  4582.8  212.75  4704.7  206.04    4797  203.53
  4853.8  203.18  4911.6  200.52  4961.2  196.82  4975.3  194.51  4982.1  190.37
  4988.4  189.79  4994.7  185.29  5011.9  187.35  5018.8  189.15  5024.4  192.17
  5034.4  193.48  5063.3   195.2  5107.8  195.79  5174.6  202.25  5180.2  203.53
  5241.3  209.06  5247.5   210.6  5257.9  210.65  5280.2   213.3  5285.8  214.62
  5359.7  219.36  5374.8  218.82  5391.4  219.65  5471.9  217.14  5499.2  217.04
#Mann= 5 ,-1 , 0
  4516.2     .17       0  4975.3     .12       0  4988.4     .09       0
  5018.8     .12       0  5034.4     .17       0
Bank Sta=4988.4,5018.8
XS Rating Curve= 0 ,0
Exp/Cntr=0.3,0.1

Type RM Length L Ch R = 1 ,2503    ,487,487,487
BEGIN DESCRIPTION:
Conroe Lake 007 6.0
END DESCRIPTION:
XS GIS Cut Line= 3
      3822303.61     10121816.62      3821727.71     10122026.06
      3821237.64     10122295.79
#Sta/Elev= 30
  4387.2  215.41    4565  204.33  4615.6  203.74  4620.9  202.98  4763.2  202.96
  4808.3  201.49  4904.1  195.02  4919.8  193.08  4941.4  190.11    4972  188.72
  4978.6  186.61  4995.5  183.44  5011.3  184.95  5024.6  184.88  5034.1   186.8
  5040.6   188.2  5084.2  189.24  5100.3  191.61  5165.6   193.4  5193.9  193.26
  5225.3  195.34    5231  194.78  5247.1  196.87  5319.5  200.99  5365.1  205.28
  5475.3  211.97  5495.6  212.32  5524.9  213.74  5534.9  212.89  5559.4     213
#Mann= 7 ,-1 , 0
  4387.2     .17       0  4919.8     .11       0    4972     .08       0
  4978.6     .06       0  5034.1     .08       0  5040.6     .11       0
  5495.6    .125       0
Bank Sta=4978.6,5034.1
XS Rating Curve= 0 ,0
Exp/Cntr=0.3,0.1

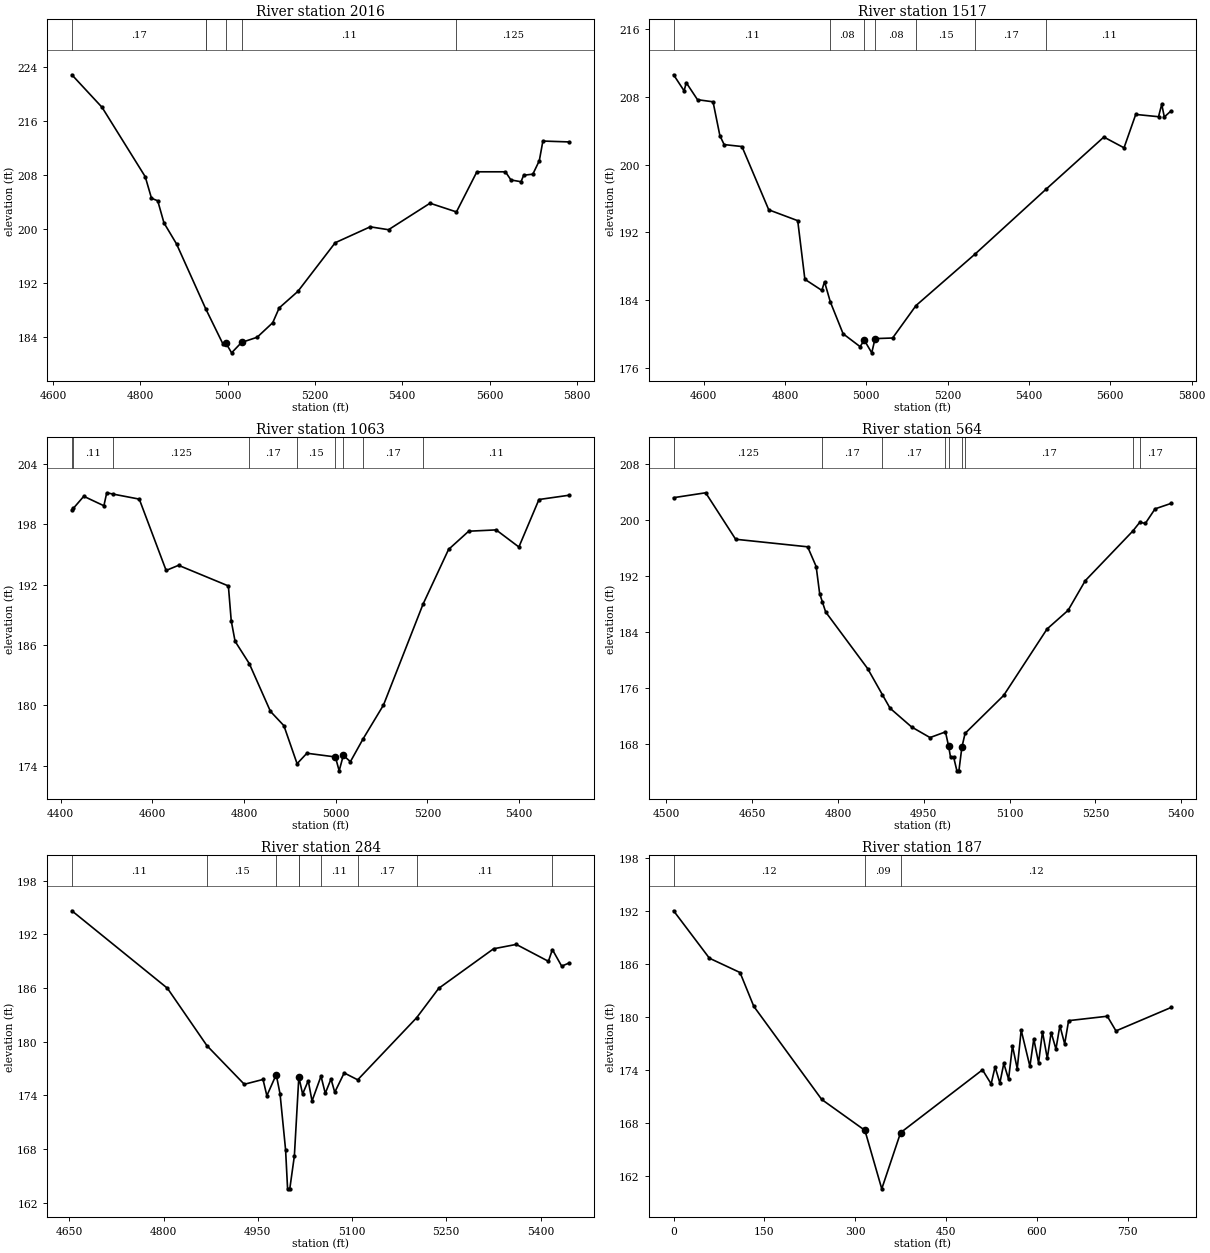
Type RM Length L Ch R = 1 ,2016    ,499,499,499
BEGIN DESCRIPTION:
Conroe Lake 007 5.0
END DESCRIPTION:
XS GIS Cut Line= 3
      3821853.97     10121360.01      3821580.37     10121589.03
      3821132.27     10122230.77
#Sta/Elev= 30
  4643.2  222.86  4712.4  218.03  4811.3  207.74  4825.6  204.55  4839.9  204.17
  4854.2  200.89  4882.9  197.78  4949.6  188.18  4989.6  182.89  4996.1  183.06
  5009.1  181.62  5031.8  183.16  5067.6  183.93  5103.3  186.09  5118.1  188.28
    5161  190.74  5246.4  197.95  5326.6  200.31  5368.5  199.88  5463.6  203.81
  5524.1  202.52  5570.9  208.47  5636.3  208.47  5648.9  207.26    5672     207
  5678.1  207.96  5699.1  208.12  5713.9  210.12  5722.1  213.03  5782.7   212.9
#Mann= 6 ,-1 , 0
  4643.2     .17       0  4949.6     .15       0  4949.6     .11       0
  4996.1     .06       0  5031.8     .11       0  5524.1    .125       0
Bank Sta=4996.1,5031.8
XS Rating Curve= 0 ,0
Exp/Cntr=0.3,0.1

Type RM Length L Ch R = 1 ,1517    ,454,454,454
BEGIN DESCRIPTION:
Conroe Lake 007 4.0
END DESCRIPTION:
XS GIS Cut Line= 3
      3821726.81     10121078.34      3821273.27     10121215.43
      3820801.23     10121797.47
#Sta/Elev= 30
  4526.2  210.61  4552.1  208.71  4557.3  209.68    4585  207.67  4623.2  207.42
    4640  203.43  4650.5  202.37  4694.3  202.14  4760.2  194.67  4831.4  193.39
    4849  186.47  4890.7  185.16  4897.3  186.18  4911.6   183.8    4943  180.04
  4984.8  178.52    4995  179.29  5013.4  177.79  5021.6  179.47  5064.7  179.54
  5122.2  183.37  5268.2  189.48  5441.9   197.1  5584.1  203.26  5633.7  201.99
  5662.5  205.93  5718.5  205.66  5726.4  207.12  5732.8  205.63  5749.4  206.35
#Mann= 7 ,-1 , 0
  4526.2     .11       0  4911.6     .08       0    4995     .06       0
  5021.6     .08       0  5122.2     .15       0  5268.2     .17       0
  5441.9     .11       0
Bank Sta=4995,5021.6
XS Rating Curve= 0 ,0
Exp/Cntr=0.3,0.1

Type RM Length L Ch R = 1 ,1063    ,499,499,499
BEGIN DESCRIPTION:
Conroe Lake 007 3.0
END DESCRIPTION:
XS GIS Cut Line= 3
      3821247.17     10120533.65      3820905.86     10120997.51
      3820457.21     10121238.96
#Sta/Elev= 30
  4424.1  199.42  4427.5  199.58  4450.1  200.77    4494  199.83  4500.2  201.12
  4513.9  200.99  4571.2  200.49  4629.8   193.4  4656.9  193.91  4765.6  191.86
  4771.8  188.41  4780.2  186.36  4811.2  184.14  4857.4  179.39  4886.7  177.97
  4915.5  174.19  4936.9  175.23  4999.1  174.86  5007.3  173.48  5016.4  175.02
  5031.8  174.39  5059.4  176.65    5104  180.02  5190.3  190.05    5246  195.49
  5289.9   197.3  5349.8  197.43  5399.4  195.73  5443.2  200.45  5509.5  200.88
#Mann= 9 ,-1 , 0
  4424.1    .125       0  4427.5     .11       0  4513.9    .125       0
  4811.2     .17       0  4915.5     .15       0  4999.1     .09       0
  5016.4     .15       0  5059.4     .17       0  5190.3     .11       0
Bank Sta=4999.1,5016.4
XS Rating Curve= 0 ,0
Exp/Cntr=0.3,0.1

Type RM Length L Ch R = 1 ,564     ,280,280,280
BEGIN DESCRIPTION:
Conroe Lake 007 2.0
END DESCRIPTION:
XS GIS Cut Line= 3
      3821121.33      10120431.1      3820656.45     10120578.22
      3820312.99      10120746.1
#Sta/Elev= 30
  4512.4  203.18  4568.5  203.88  4620.9  197.23  4746.8  196.15  4761.7  193.33
  4767.8  189.46  4772.6  188.26  4778.3  186.83  4851.7  178.73  4877.3  175.02
  4890.9  173.06  4928.5  170.38  4960.8  168.86  4987.8  169.67  4993.1   167.7
  4996.6  166.09    5002  166.09  5007.8   164.1  5011.3   164.1  5016.5  167.48
  5022.1  169.46  5089.6  174.89  5165.4  184.39  5202.2  187.06  5232.2   191.3
  5315.2  198.39  5327.6  199.66  5337.3   199.5  5354.3  201.58  5382.3  202.36
#Mann= 9 ,-1 , 0
  4512.4    .125       0  4772.6     .17       0  4877.3     .17       0
  4987.8     .12       0  4993.1     .09       0  5016.5     .12       0
  5022.1     .17       0  5315.2     .11       0  5327.6     .17       0
Bank Sta=4993.1,5016.5
XS Rating Curve= 0 ,0
Exp/Cntr=0.3,0.1

Type RM Length L Ch R = 1 ,284     ,145,145,145
BEGIN DESCRIPTION:
Mapping XS 17586adc
END DESCRIPTION:
XS GIS Cut Line= 3
      3820859.71     10120120.92      3820574.65     10120317.03
      3820202.59     10120562.78
#Sta/Elev= 30
    4654  194.63  4806.1  185.97    4869  179.55  4928.5  175.23  4958.3  175.77
  4964.4  173.95  4979.3  176.31  4985.4  174.16  4994.2  167.92  4997.4  163.54
  5000.9  163.54  5008.2  167.22  5015.3  176.05  5021.3  174.15  5030.3  175.62
  5036.3  173.36  5050.6  176.14  5057.4  174.22  5066.5  175.82  5072.5  174.34
  5087.5   176.5    5109  175.73  5202.8  182.67    5238  185.96  5325.3  190.38
  5361.4  190.87  5412.6  188.98  5418.9  190.29  5433.7  188.44  5445.9   188.8
#Mann= 9 ,-1 , 0
    4654     .11       0    4869     .15       0  4979.3     .09       0
  5015.3     .12       0  5015.3     .15       0  5050.6     .11       0
    5109     .17       0  5202.8     .11       0  5418.9     .17       0
Bank Sta=4979.3,5015.3
XS Rating Curve= 0 ,0
Exp/Cntr=0.3,0.1

Type RM Length L Ch R = 1 ,187     ,84,84,84
XS GIS Cut Line= 3
      3820804.29     10120027.65      3820501.34     10120191.71
      3820130.68     10120493.96
#Sta/Elev= 30
       0  191.99    59.1  186.63   109.7  185.01   132.4  181.19   244.6  170.66
   315.9  167.17   343.7  160.56   374.8  166.91     510  174.01   524.3  172.42
   530.8  174.35   538.7  172.52   545.2  174.73   553.1  172.96   559.5  176.72
   567.4  174.14   573.9   178.5   588.3   174.4   594.7   177.5   602.6  174.81
   609.1  178.32     617  175.31   623.4  178.23   631.3  176.36   637.8     179
   645.7  176.94   652.2  179.57   716.1  180.07   730.4  178.41   821.4  181.06
#Mann= 3 , 0 , 0
       0     .12       0   315.9     .09       0   374.8     .12       0
Bank Sta=315.9,374.8
XS Rating Curve= 0 ,0
Exp/Cntr=0.3,0.1

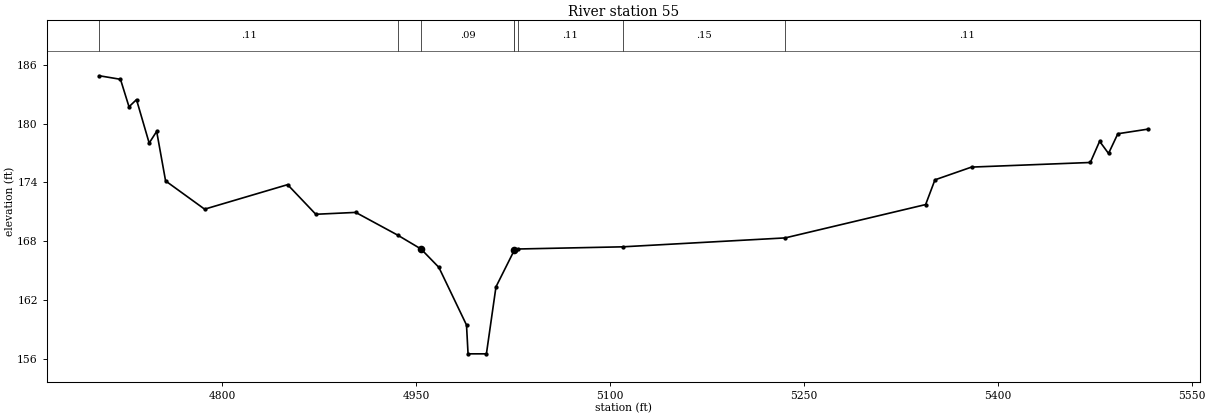
Type RM Length L Ch R = 1 ,55      ,0,0,0
BEGIN DESCRIPTION:
Conroe Lake 007 1.5
END DESCRIPTION:
XS GIS Cut Line= 3
      3820721.86     10119963.99      3820468.15     10120114.51
      3820109.87     10120486.12
#Sta/Elev= 30
    4705  184.88  4721.3  184.52  4727.9  181.72  4733.7  182.45  4743.5  178.02
  4749.3  179.21  4756.2  174.16  4786.4  171.28  4850.6  173.78  4872.4  170.76
  4903.3  170.95  4935.8  168.63  4953.8  167.22  4967.6  165.35    4989  159.47
  4990.2  156.53  5004.4  156.53  5011.8  163.36    5026   167.1  5029.1  167.22
  5109.7  167.44  5235.5  168.35  5344.2  171.75  5351.4  174.27  5379.7  175.57
  5471.6  176.04  5478.8   178.2  5485.7  176.96  5492.9  178.97  5516.2  179.44
#Mann= 8 ,-1 , 0
    4705     .11       0  4935.8     .15       0  4953.8     .09       0
    5026     .12       0    5026     .15       0  5029.1     .11       0
  5109.7     .15       0  5235.5     .11       0
Bank Sta=4953.8,5026
XS Rating Curve= 0 ,0
Exp/Cntr=0.3,0.1

Chan Stop Cuts=-1
Use User Specified Reach Order=0
Composite Channel Slope=5