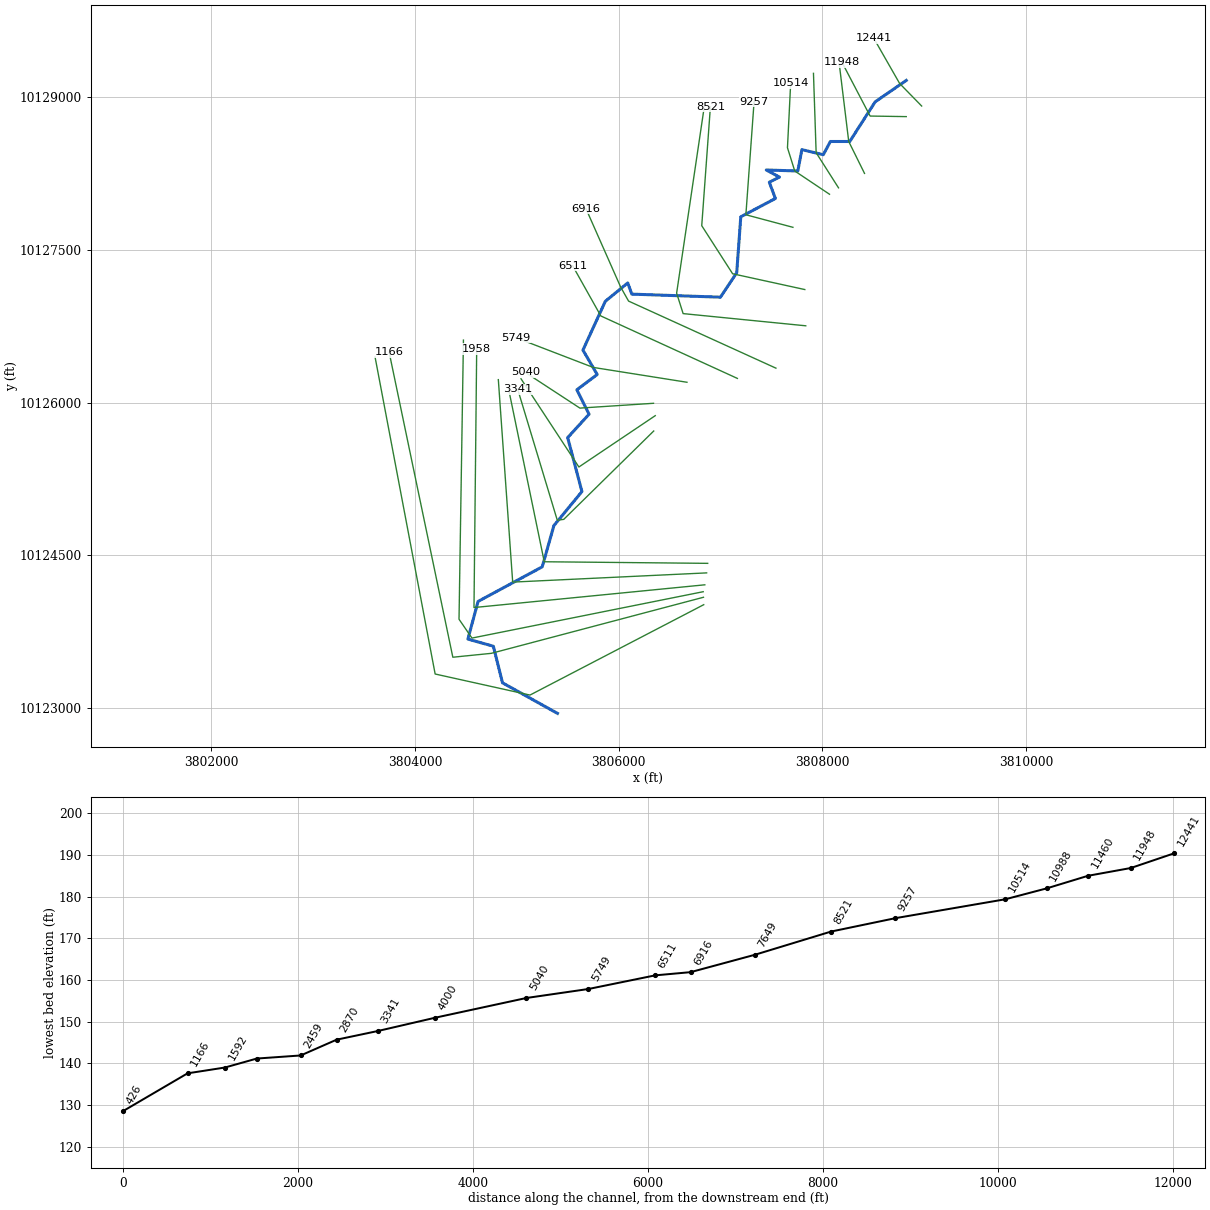
--- Conroe Lake 008.prj (project) ---

Proj Title=Conroe Lake 008 Base Level Engineering
Current Plan=p01
Default Exp/Contr=0.3,0.1
English Units
Geom File=g01
Flow File=f01
Flow File=f02
Plan File=p01
Y Axis Title=Elevation
X Axis Title(PF)=Main Channel Distance
X Axis Title(XS)=Station
BEGIN DESCRIPTION:
Conroe Lake 008
END DESCRIPTION:
DSS Export Rating Curves= 0
DSS Export Rating Curve Sorted= 0
DSS Export Volume Flow Curves= 0
DXF OffsetX= 0
DXF OffsetY= 0
DXF ScaleX= 1
DXF ScaleY= 10

--- Conroe Lake 008.p01 (plan) ---

Plan Title=Multiple Run
Short Identifier=Multiple
Geom File=g01
Flow File=f01
Subcritical Flow
K Sum by GR= 0
Std Step Tol= 0.01
Critical Tol= 0.01
Num of Std Step Trials= 20
Max Error Tol= 0.3
Flow Tol Ratio= 0.001
Split Flow NTrial= 30
Split Flow Tol= 0.02
Split Flow Ratio= 0.02
Log Output Level= 0
Friction Slope Method= 1
Unsteady Friction Slope Method= 2
Unsteady Bridges Friction Slope Method= 1
Parabolic Critical Depth
Global Vel Dist=  1 , 1 , 1
Global Log Level= 0
CheckData=True
Encroach Param= -1, 0, 0, 0
BEGIN DESCRIPTION:
Multiple Run
END DESCRIPTION:

--- Conroe Lake 008.f01 (steady flow) ---

Flow Title=Multiple
Program Version=4.10
Number of Profiles= 7
Profile Names=10-year,25-year,50-year,1pct_min,100-year,1pct_plu,500-year
River Rch & RM=Conroe Lake 008,Reach-1         ,12441
     681     935    1278     576    1738    5249    3320
River Rch & RM=Conroe Lake 008,Reach-1         ,11948
     868    1200    1643     741    2239    6762    4290
River Rch & RM=Conroe Lake 008,Reach-1         ,6511
    1003    1388    1904     859    2594    7834    4969
Boundary for River Rch & Prof#=Conroe Lake 008,Reach-1         , 1
Up Type= 0
Dn Type= 3
Dn Slope=0.01
Boundary for River Rch & Prof#=Conroe Lake 008,Reach-1         , 2
Up Type= 0
Dn Type= 3
Dn Slope=0.01
Boundary for River Rch & Prof#=Conroe Lake 008,Reach-1         , 3
Up Type= 0
Dn Type= 3
Dn Slope=0.01
Boundary for River Rch & Prof#=Conroe Lake 008,Reach-1         , 4
Up Type= 0
Dn Type= 3
Dn Slope=0.01
Boundary for River Rch & Prof#=Conroe Lake 008,Reach-1         , 5
Up Type= 0
Dn Type= 3
Dn Slope=0.01
Boundary for River Rch & Prof#=Conroe Lake 008,Reach-1         , 6
Up Type= 0
Dn Type= 3
Dn Slope=0.01
Boundary for River Rch & Prof#=Conroe Lake 008,Reach-1         , 7
Up Type= 0
Dn Type= 3
Dn Slope=0.01
DSS Import GetInterval= 0
DSS Import GetPeak= 0
DSS Import FillOption= 0

--- Conroe Lake 008.f02 (steady flow) ---

Flow Title=Orig_BLE_Flow
Program Version=4.10
Number of Profiles= 7
Profile Names=10-year,25-year,50-year,1pct_min,100-year,1pct_plu,500-year
River Rch & RM=Conroe Lake 008,Reach-1         ,12441
     681     917    1111     443    1337    4036    1930
River Rch & RM=Conroe Lake 008,Reach-1         ,11948
     868    1176    1429     570    1722    5200    2494
River Rch & RM=Conroe Lake 008,Reach-1         ,6511
    1003    1361    1656     661    1995    6025    2889
Boundary for River Rch & Prof#=Conroe Lake 008,Reach-1         , 1
Up Type= 0
Dn Type= 3
Dn Slope=0.005
Boundary for River Rch & Prof#=Conroe Lake 008,Reach-1         , 2
Up Type= 0
Dn Type= 3
Dn Slope=0.005
Boundary for River Rch & Prof#=Conroe Lake 008,Reach-1         , 3
Up Type= 0
Dn Type= 3
Dn Slope=0.005
Boundary for River Rch & Prof#=Conroe Lake 008,Reach-1         , 4
Up Type= 0
Dn Type= 3
Dn Slope=0.005
Boundary for River Rch & Prof#=Conroe Lake 008,Reach-1         , 5
Up Type= 0
Dn Type= 3
Dn Slope=0.005
Boundary for River Rch & Prof#=Conroe Lake 008,Reach-1         , 6
Up Type= 0
Dn Type= 3
Dn Slope=0.005
Boundary for River Rch & Prof#=Conroe Lake 008,Reach-1         , 7
Up Type= 0
Dn Type= 3
Dn Slope=0.005
DSS Import GetInterval= 0
DSS Import GetPeak= 0
DSS Import FillOption= 0

--- Conroe Lake 008.g01 (geometry) ---

Geom Title=Existing Conditions
Program Version=4.10

River Reach=Conroe Lake 008 ,Reach-1
Reach XY= 30
      3808823.23     10129166.84      3808518.23     10128956.84
      3808268.23     10128566.84      3808078.23     10128566.84
      3808008.23     10128436.84      3807798.23     10128486.84
      3807758.23     10128276.84      3807448.23     10128286.84
      3807578.23     10128216.84      3807478.23     10128166.84
      3807538.23     10128006.84      3807198.23     10127826.84
      3807158.23     10127276.84      3806998.23     10127036.84
      3806128.23     10127066.84      3806088.23     10127176.84
      3805868.23     10126996.84      3805648.23     10126516.84
      3805788.23     10126276.84      3805588.23     10126126.84
      3805708.23     10125886.84      3805498.23     10125656.84
      3805638.23     10125126.84      3805362.85     10124792.13
      3805248.23     10124386.84      3804618.23     10124046.84
      3804518.23     10123676.84      3804768.23     10123606.84
      3804858.23     10123246.84      3805398.23     10122946.84

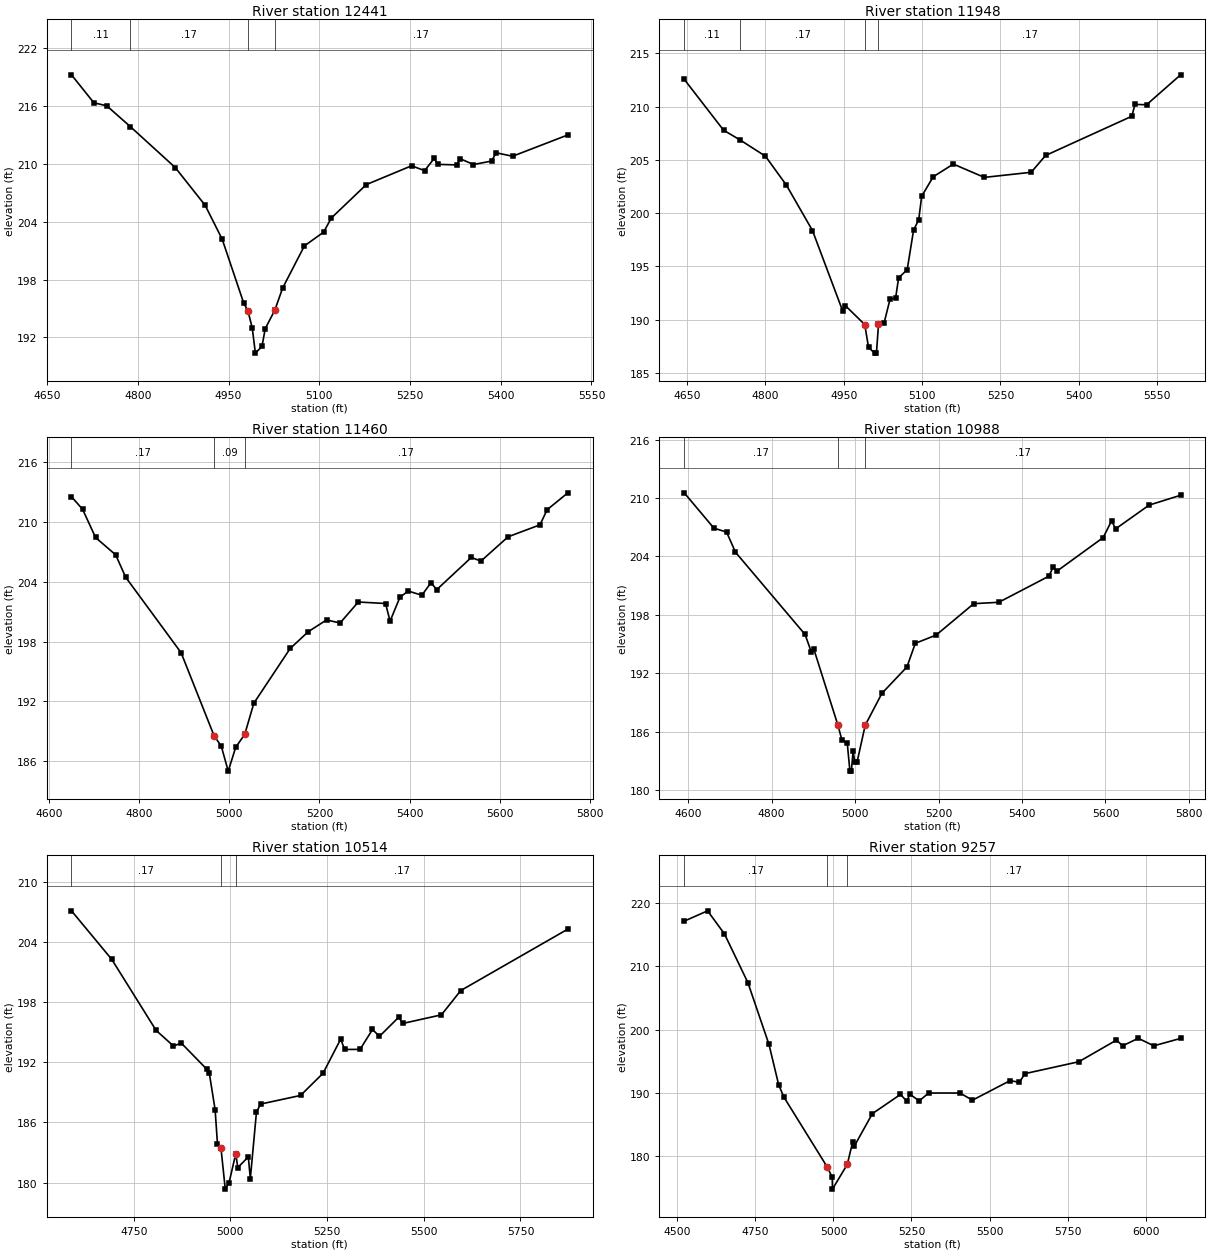
Type RM Length L Ch R = 1 ,12441   ,493,493,493
BEGIN DESCRIPTION:
Conroe Lake 008 21.0
END DESCRIPTION:
XS GIS Cut Line= 3
      3808974.52     10128915.32      3808758.23     10129136.84
      3808504.76     10129580.55
#Sta/Elev= 30
  4690.4  219.22  4727.4  216.32  4748.7  216.01  4787.7  213.85  4861.9  209.61
  4911.3   205.7  4939.6  202.17    4975  195.58    4982  194.77  4989.2  192.99
  4994.4  190.37  5005.3  191.06  5010.7  192.91  5026.6  194.83  5039.4  197.11
  5075.5  201.49  5107.2  202.91    5120  204.38  5177.8  207.84  5252.6  209.79
  5274.2  209.29  5290.1  210.56  5295.8  209.94  5327.3  209.88  5333.3  210.52
  5354.8  209.92  5384.9  210.28  5392.3  211.14  5419.6  210.78    5511  212.99
#Mann= 4 ,-1 , 0
  4690.4     .11       0  4787.7     .17       0    4982     .09       0
  5026.6     .17       0
Bank Sta=4982,5026.6
XS Rating Curve= 0 ,0
Exp/Cntr=0.3,0.1

Type RM Length L Ch R = 1 ,11948   ,488,488,488
BEGIN DESCRIPTION:
Conroe Lake 008 20.0
END DESCRIPTION:
XS GIS Cut Line= 3
      3808823.19     10128811.25      3808468.23     10128816.84
      3808192.74     10129343.89
#Sta/Elev= 30
    4645  212.57  4720.3  207.79  4752.4  206.86  4800.4  205.35  4840.4  202.64
  4890.4  198.37  4948.1  190.83  4953.1  191.33  4990.4  189.54  4997.7  187.39
  5009.3  186.86  5012.8  186.86  5016.7  189.56  5027.3  189.67  5038.7  191.91
  5049.5  192.04  5055.2  193.93  5071.6  194.69  5083.8   198.4  5093.7   199.4
  5099.3  201.59  5121.4  203.42  5159.9  204.61  5219.2  203.36  5308.8  203.84
  5336.5  205.42  5501.3   209.1  5507.5  210.21  5529.6  210.18  5594.7  212.99
#Mann= 4 ,-1 , 0
    4645     .11       0  4752.4     .17       0  4990.4     .09       0
  5016.7     .17       0
Bank Sta=4990.4,5016.7
XS Rating Curve= 0 ,0
Exp/Cntr=0.3,0.1

Type RM Length L Ch R = 1 ,11460   ,472,472,472
BEGIN DESCRIPTION:
Conroe Lake 008 19.0
END DESCRIPTION:
XS GIS Cut Line= 3
      3808413.33      10128253.2      3808258.23     10128566.84
      3808167.41     10129312.53
#Sta/Elev= 30
  4650.1  212.52  4674.7  211.26  4703.5  208.43  4748.1  206.69  4770.4  204.44
  4893.2  196.88  4966.3  188.56  4982.4   187.5  4997.8     185  5014.3  187.38
  5034.5   188.7  5054.6  191.81  5135.2   197.3  5175.5  198.99  5215.8  200.16
    5246  199.86  5286.3  201.96  5346.8  201.81  5356.8  200.04  5378.7  202.44
  5397.1  203.06  5427.4  202.64  5447.5   203.9  5460.3   203.2    5537  206.43
  5558.3  206.06  5618.6   208.5  5689.3   209.7  5705.3  211.22  5751.2  212.91
#Mann= 3 , 0 , 0
  4650.1     .17       0  4966.3     .09       0  5034.5     .17       0
Bank Sta=4966.3,5034.5
XS Rating Curve= 0 ,0
Exp/Cntr=0.3,0.1

Type RM Length L Ch R = 1 ,10988   ,474,474,474
BEGIN DESCRIPTION:
Conroe Lake 008 18.0
END DESCRIPTION:
XS GIS Cut Line= 3
      3808157.97     10128111.29      3807938.23     10128456.84
      3807912.04     10129236.51
#Sta/Elev= 30
  4590.5  210.53  4661.6  206.91  4692.1   206.5  4713.3  204.44  4880.1     196
  4895.3  194.19  4901.2  194.49  4958.8   186.7  4968.1  185.22  4981.3  184.83
  4987.6  181.98  4991.1  181.98  4995.2  184.06  4999.5  182.87  5004.6  182.87
  5024.2  186.68  5064.3  189.96  5124.3  192.67  5144.3  195.09  5194.3  195.94
  5284.4  199.16  5344.4   199.3  5464.5  201.98  5474.5   202.9  5484.5  202.52
  5594.6  205.94  5614.6  207.65  5624.6  206.84  5704.6  209.27  5780.1  210.28
#Mann= 3 , 0 , 0
  4590.5     .17       0  4958.8     .09       0  5024.2     .17       0
Bank Sta=4958.8,5024.2
XS Rating Curve= 0 ,0
Exp/Cntr=0.3,0.1

Type RM Length L Ch R = 1 ,10514   ,1257,1257,1257
BEGIN DESCRIPTION:
Conroe Lake 008 17.0
END DESCRIPTION:
XS GIS Cut Line= 4
      3808069.68     10128048.26      3807728.23     10128276.84
      3807656.65     10128505.43       3807688.1     10129137.62
#Sta/Elev= 30
  4589.1  207.08  4693.3  202.24  4807.9  195.17  4852.4  193.63  4873.4  193.89
  4939.5  191.28  4945.5  190.89  4960.5  187.26  4966.5  183.88  4975.5  183.49
  4986.7  179.36  4996.5     180  5013.8  182.88  5019.1  181.51  5046.3  182.57
  5051.5  180.41  5067.3  187.01  5077.8  187.83  5181.3  188.69  5239.5   190.9
  5285.2  194.31  5295.2  193.27  5335.3  193.28  5367.3  195.26  5385.4  194.58
  5435.4  196.49  5445.4  195.86  5545.6  196.72  5595.6  199.14  5872.5  205.26
#Mann= 3 , 0 , 0
  4589.1     .17       0  4975.5     .09       0  5013.8     .17       0
Bank Sta=4975.5,5013.8
XS Rating Curve= 0 ,0
Exp/Cntr=0.3,0.1

Type RM Length L Ch R = 1 ,9257    ,736,736,736
BEGIN DESCRIPTION:
Conroe Lake 008 15.0
END DESCRIPTION:
XS GIS Cut Line= 3
      3807710.25     10127723.52      3807248.23     10127846.84
      3807328.75     10128956.23
#Sta/Elev= 30
  4521.8  217.12  4596.7  218.75  4650.8   215.1  4725.8  207.42  4793.4  197.66
  4824.4   191.3  4840.9  189.37  4979.7  178.34  4996.1  176.69  4996.8  174.82
  5044.3  178.72  5061.6  182.28  5066.6  181.59  5124.6  186.73  5214.8  189.77
  5234.8   188.7  5244.9  189.79  5274.9  188.75    5305  189.99  5405.3  189.99
  5445.4  188.86  5565.7  191.94  5595.8  191.69  5613.6  193.05  5786.3  194.93
  5906.6  198.34  5926.7  197.45  5976.8  198.63  6026.4  197.44  6112.3  198.61
#Mann= 3 , 0 , 0
  4521.8     .17       0  4979.7     .09       0  5044.3     .17       0
Bank Sta=4979.7,5044.3
XS Rating Curve= 0 ,0
Exp/Cntr=0.3,0.1

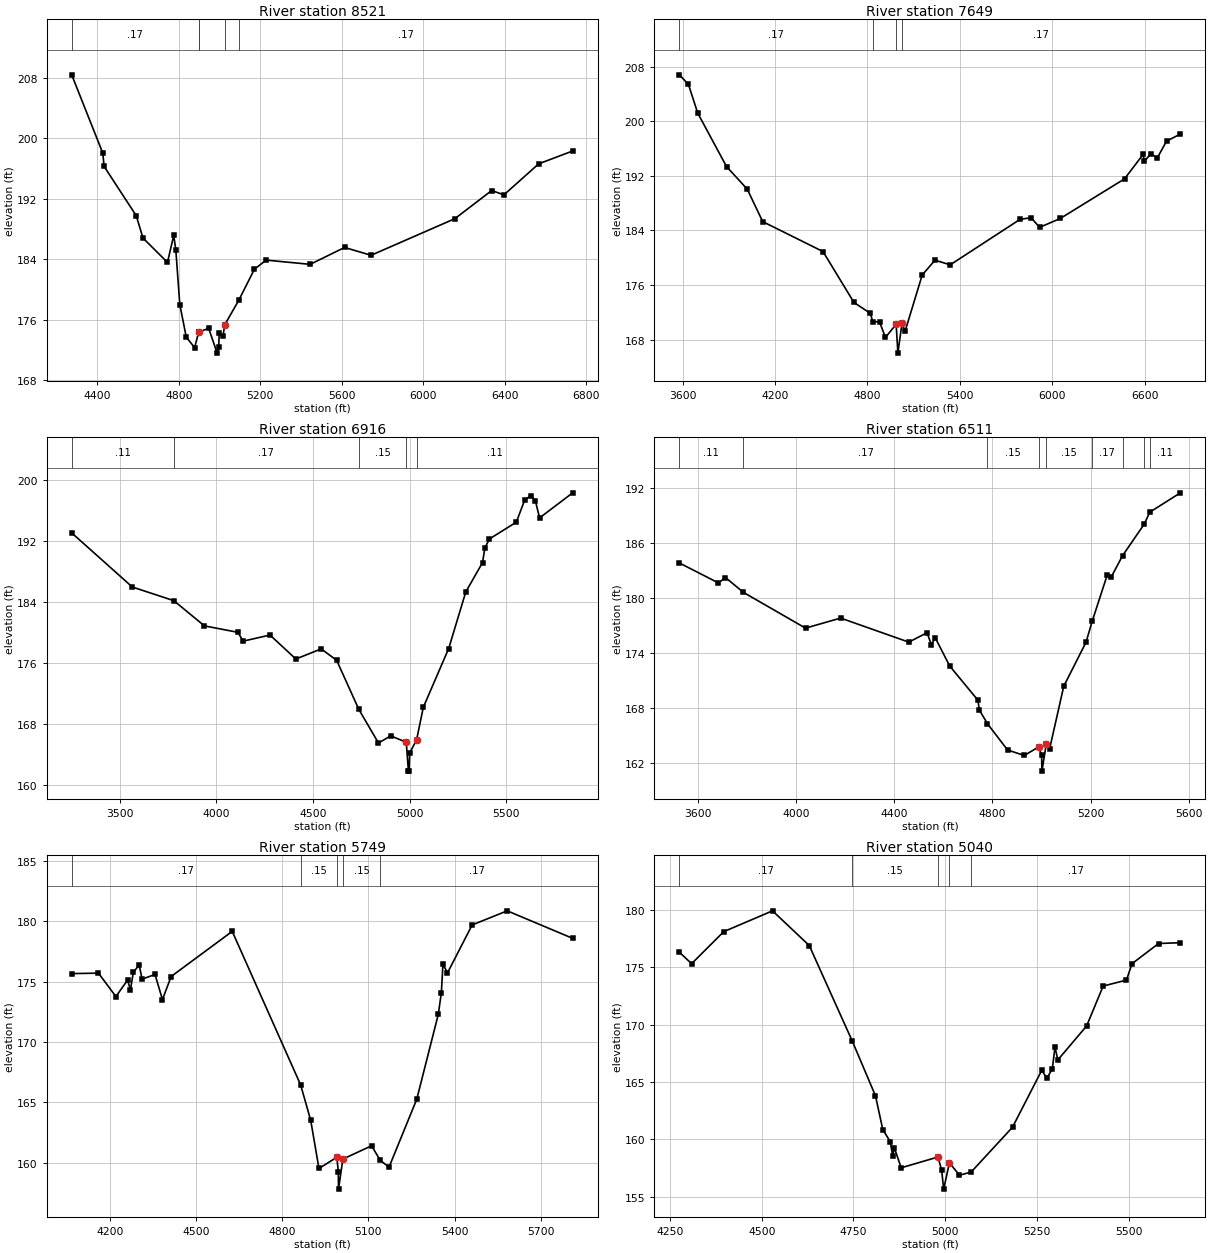
Type RM Length L Ch R = 1 ,8521    ,872,872,872
BEGIN DESCRIPTION:
Conroe Lake 008 17.5
END DESCRIPTION:
XS GIS Cut Line= 4
      3807826.88     10127111.88      3807118.23     10127266.84
      3806814.84     10127739.29      3806899.86     10128907.53
#Sta/Elev= 30
  4274.6   208.4  4427.2  198.04  4433.5  196.29  4590.9  189.79  4624.3  186.82
  4744.5   183.6  4775.2  187.18  4785.4  185.26    4805  178.02  4836.6  173.73
  4877.6  172.32  4897.3  174.34  4897.8  174.39  4946.8  174.87  4988.4   171.6
  4995.8  172.41  4998.2  174.21  5016.9  173.87  5025.7  175.36  5094.5   178.6
    5171  182.69  5228.5   183.9  5444.7  183.34  5613.4  185.57  5743.7  184.54
  6154.8  189.38  6335.3   193.1  6395.5  192.53  6565.9  196.63  6732.8  198.33
#Mann= 5 ,-1 , 0
  4274.6     .17       0  4897.3     .12       0  4897.8     .09       0
  5025.7     .15       0  5094.5     .17       0
Bank Sta=4897.8,5025.7
XS Rating Curve= 0 ,0
Exp/Cntr=0.3,0.1

Type RM Length L Ch R = 1 ,7649    ,733,733,733
BEGIN DESCRIPTION:
Conroe Lake 008 13.0
END DESCRIPTION:
XS GIS Cut Line= 4
      3807836.35      10126755.6      3806631.98     10126875.41
      3806568.23     10127076.84      3806836.91     10128890.05
#Sta/Elev= 30
  3578.4   206.8  3637.2  205.39  3697.5  201.19  3884.8  193.35  4019.1  190.05
  4119.6  185.29  4511.5   180.9  4712.5  173.44  4819.9  171.84  4833.9  170.63
  4878.6  170.61  4916.8  168.32  4986.7  170.24  4997.8  166.02  5024.5   170.4
  5044.7  169.23  5155.9  177.47    5239  179.64  5337.9  178.96  5792.8  185.64
  5863.6  185.85  5918.8  184.45  6052.7  185.75  6470.1  191.55  6591.4  195.15
  6598.6  194.11    6642  195.26  6682.4   194.6  6743.1  197.08    6833  198.12
#Mann= 4 ,-1 , 0
  3578.4     .17       0  4833.9     .15       0  4986.7     .09       0
  5024.5     .17       0
Bank Sta=4986.7,5024.5
XS Rating Curve= 0 ,0
Exp/Cntr=0.3,0.1

Type RM Length L Ch R = 1 ,6916    ,405,405,405
BEGIN DESCRIPTION:
Conroe Lake 008 14.0
END DESCRIPTION:
XS GIS Cut Line= 4
      3807543.16     10126339.42      3806096.32     10126998.39
      3806018.23     10127136.84      3805677.44     10127907.78
#Sta/Elev= 30
  3251.2  193.12  3564.7  186.02  3779.3  184.23  3937.8  180.92  4110.1  180.08
  4138.7  178.92    4277  179.72  4410.8  176.57  4541.6   177.9  4621.7  176.41
  4736.6  169.96  4838.2  165.55  4901.5  166.49  4981.9  165.65  4993.1  161.86
  4996.6  161.86  4999.6  164.26    5035  165.92  5070.2  170.24  5201.4  177.95
  5289.9  185.38  5376.4  189.22  5388.5  191.13  5411.8  192.32  5551.3  194.53
    5595  197.47    5627     198  5649.7  197.35  5671.6  195.09  5842.9  198.38
#Mann= 5 ,-1 , 0
  3251.2     .11       0  3779.3     .17       0  4736.6     .15       0
  4981.9     .09       0    5035     .11       0
Bank Sta=4981.9,5035
XS Rating Curve= 0 ,0
Exp/Cntr=0.3,0.1

Type RM Length L Ch R = 1 ,6511    ,762,762,762
BEGIN DESCRIPTION:
Conroe Lake 008 13.5
END DESCRIPTION:
XS GIS Cut Line= 3
      3807164.76     10126238.55      3805823.78      10126852.4
       3805547.4     10127345.18
#Sta/Elev= 30
  3525.2  183.84  3684.3  181.66  3712.9  182.25  3785.8  180.63  4038.7  176.72
  4181.7  177.82  4459.2  175.19  4533.7  176.22  4551.2   174.9  4566.6  175.68
  4625.8  172.58  4740.8  168.84  4746.3  167.78  4779.6  166.27  4861.4   163.4
  4929.5   162.8  4987.4  163.72    5000  162.85  5001.3  161.09    5019  164.05
  5032.9  163.56  5090.2  170.37    5181  175.19  5205.7  177.45  5267.8  182.58
  5283.7  182.32  5329.8  184.65  5417.9  188.09  5440.2  189.39    5565  191.51
#Mann= 9 ,-1 , 0
  3525.2     .11       0  3785.8     .17       0  4779.6     .15       0
  4987.4     .09       0    5019     .15       0  5205.7     .17       0
  5329.8     .11       0  5417.9     .17       0  5440.2     .11       0
Bank Sta=4987.4,5019
XS Rating Curve= 0 ,0
Exp/Cntr=0.3,0.1

Type RM Length L Ch R = 1 ,5749    ,709,709,709
BEGIN DESCRIPTION:
Conroe Lake 008 9.0
END DESCRIPTION:
XS GIS Cut Line= 3
      3806669.81      10126200.7      3805748.23     10126346.84
      3804991.08     10126638.28
#Sta/Elev= 30
  4066.9  175.67    4160  175.71  4220.8  173.77  4261.3  175.13  4271.4  174.33
  4281.5  175.79  4301.8  176.38  4311.9  175.21    4357   175.6  4382.8  173.52
  4413.1  175.43  4625.8  179.17  4863.9  166.46  4899.1  163.52  4927.8  159.53
  4990.1  160.46  4995.2  159.26  4995.9  157.82  5011.1  160.31  5111.1  161.41
  5141.3   160.2  5171.8  159.64  5268.3  165.26  5343.3  172.29    5354  174.09
  5359.6  176.46  5375.4  175.73  5461.2   179.7  5583.4  180.87  5811.3  178.59
#Mann= 5 ,-1 , 0
  4066.9     .17       0  4863.9     .15       0  4990.1     .09       0
  5011.1     .15       0  5141.3     .17       0
Bank Sta=4990.1,5011.1
XS Rating Curve= 0 ,0
Exp/Cntr=0.3,0.1

Type RM Length L Ch R = 1 ,5040    ,1040,1040,1040
BEGIN DESCRIPTION:
Conroe Lake 008 10.0
END DESCRIPTION:
XS GIS Cut Line= 3
      3806341.09     10125994.09      3805618.23     10125946.84
      3805081.82     10126297.76
#Sta/Elev= 30
  4275.6  176.32  4308.9  175.32  4396.3  178.11  4529.4  179.93  4629.6   176.9
  4746.9  168.56    4810   163.8    4830  160.85  4850.1  159.81  4856.8  158.58
  4861.8  159.23  4880.1  157.52  4980.3  158.46  4990.4  157.31  4995.9  155.66
  5011.6  157.97  5038.7  156.87  5070.8  157.15  5183.5  161.06  5263.3  166.03
  5276.9  165.33    5292  166.13  5299.2  168.04  5307.1  166.93  5385.5  169.89
  5430.6  173.37  5494.1  173.89  5509.2  175.32  5581.6  177.08    5641  177.15
#Mann= 5 ,-1 , 0
  4275.6     .17       0  4746.9     .15       0  4980.3     .09       0
  5011.6     .15       0  5070.8     .17       0
Bank Sta=4980.3,5011.6
XS Rating Curve= 0 ,0
Exp/Cntr=0.3,0.1

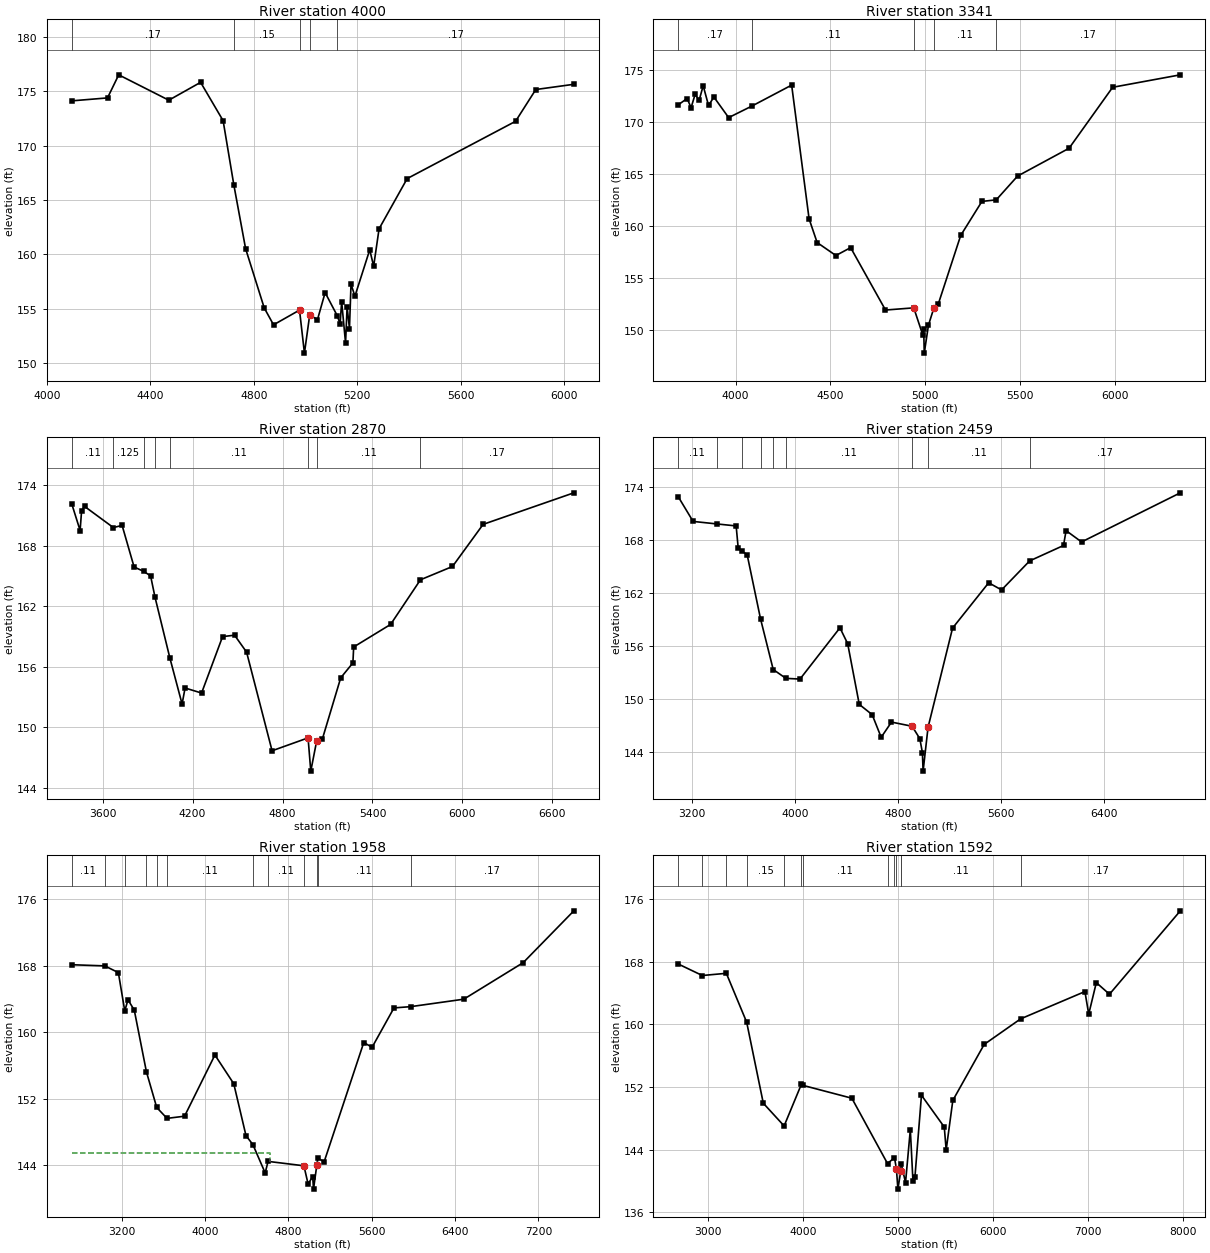
Type RM Length L Ch R = 1 ,4000    ,659,659,659
BEGIN DESCRIPTION:
Conroe Lake 008 8.0
END DESCRIPTION:
XS GIS Cut Line= 3
      3806358.44     10125872.57      3805608.23     10125368.01
      3805039.81     10126235.35
#Sta/Elev= 30
  4095.9  174.11  4234.1  174.38  4277.4   176.5  4471.1  174.17    4594  175.81
    4681  172.29  4722.5  166.39    4768  160.53    4840  155.09    4876  153.54
  4976.4  154.89  4995.4  150.94  5015.7  154.43  5045.9  154.02  5075.4   156.5
    5122  154.39  5133.4  153.63  5139.3  155.67  5154.4  151.87  5160.4  155.19
  5169.5   153.2  5175.5  157.27  5190.6  156.17  5247.9  160.43    5263  158.92
    5284  162.36  5392.6  166.97  5811.6  172.23  5889.9  175.15    6037  175.63
#Mann= 5 ,-1 , 0
  4095.9     .17       0  4722.5     .15       0  4976.4     .09       0
  5015.7     .15       0    5122     .17       0
Bank Sta=4976.4,5015.7
XS Rating Curve= 0 ,0
Exp/Cntr=0.3,0.1

Type RM Length L Ch R = 1 ,3341    ,471,471,471
BEGIN DESCRIPTION:
Mapping XS 369856e8
END DESCRIPTION:
XS GIS Cut Line= 4
      3806343.21     10125721.69      3805459.52     10124853.29
      3805396.25      10124844.8      3805007.28     10126132.74
#Sta/Elev= 30
  3697.2  171.64  3743.9  172.25    3765  171.37  3786.3  172.65  3807.5  172.08
  3828.8  173.48    3857  171.58  3885.3  172.39  3963.1  170.41  4086.6  171.53
  4295.4  173.54  4387.4  160.66  4429.8  158.38  4528.8  157.13  4606.5  157.89
  4790.4  151.88  4939.5  152.09  4986.8  149.49  4991.9  150.06  4994.8  147.73
    5017  150.42  5044.7  152.03  5069.2  152.48    5187  159.06    5299  162.34
  5374.5  162.49  5487.1  164.78  5758.7  167.46  5988.5  173.33  6345.4  174.53
#Mann= 5 ,-1 , 0
  3697.2     .17       0  4086.6     .11       0  4939.5     .06       0
  5044.7     .11       0  5374.5     .17       0
Bank Sta=4939.5,5044.7
XS Rating Curve= 0 ,0
Exp/Cntr=0.3,0.1

Type RM Length L Ch R = 1 ,2870    ,411,411,411
BEGIN DESCRIPTION:
Conroe Lake 008 4.0
END DESCRIPTION:
XS GIS Cut Line= 3
      3806873.45     10124421.16      3805268.23     10124436.84
      3804916.14     10126143.61
#Sta/Elev= 30
  3394.7  172.17  3450.3  169.53  3460.3   171.5  3480.3  171.92  3672.2  169.82
  3730.3  170.04  3810.3  165.91  3873.4  165.48  3920.3  165.03    3950   162.9
  4048.7  156.89  4130.3  152.31  4150.3   153.9  4260.3   153.4  4400.3     159
  4480.4  159.14  4560.4  157.46  4730.4  147.67  4970.4  148.95  4988.5  145.65
  5028.2  148.68  5065.6  148.83  5188.1  154.91  5269.4  156.39  5274.5  157.97
  5520.8  160.21  5719.8  164.64  5933.5  165.96  6137.7  170.14  6742.7  173.27
#Mann= 8 ,-1 , 0
  3394.7     .11       0  3672.2    .125       0  3873.4     .17       0
    3950     .15       0  4048.7     .11       0  4970.4     .07       0
  5028.2     .11       0  5719.8     .17       0
Bank Sta=4970.4,5028.2
XS Rating Curve= 0 ,0
Exp/Cntr=0.3,0.1

Type RM Length L Ch R = 1 ,2459    ,501,501,501
BEGIN DESCRIPTION:
Conroe Lake 008 3.0
END DESCRIPTION:
XS GIS Cut Line= 3
      3806863.08     10124327.41      3804958.23     10124236.84
      3804817.22     10126226.45
#Sta/Elev= 30
    3093  172.86  3208.4  170.07  3390.5  169.79    3543  169.56  3558.8  167.09
  3587.5  166.74  3628.8  166.29  3732.4  159.07    3831  153.34  3929.6  152.34
  4039.3  152.26  4349.6  158.05  4409.7  156.26  4499.8   149.4    4600  148.24
    4670  145.68  4750.1   147.4  4910.3  146.93  4970.3  145.53  4990.4  143.95
  4995.8  141.86  5034.3  146.81  5224.8  158.02  5505.5  163.14  5605.7  162.33
  5823.9  165.61  6086.9  167.35    6107  169.03  6227.3  167.75  6994.6   173.3
#Mann= 9 ,-1 , 0
    3093     .11       0  3390.5    .125       0  3587.5     .17       0
  3732.4     .15       0    3831     .17       0  3929.6     .11       0
  4910.3     .07       0  5034.3     .11       0  5823.9     .17       0
#XS Ineff= 2 , 0
       0    4600  148.24               0
Permanent Ineff=
       F       F
Bank Sta=4910.3,5034.3
XS Rating Curve= 0 ,0
Exp/Cntr=0.3,0.1

Type RM Length L Ch R = 1 ,1958    ,366,366,366
BEGIN DESCRIPTION:
Conroe Lake 008 2.0
END DESCRIPTION:
XS GIS Cut Line= 3
      3806844.85     10124210.22      3804578.23     10123986.84
      3804604.79     10126527.11
#Sta/Elev= 30
  2722.4  168.14  3039.2     168  3169.6  167.19  3230.8  162.58    3262  163.92
  3322.3  162.67  3438.9  155.24  3537.7  150.95  3636.5  149.64  3804.6   149.9
    4096  157.27  4276.9  153.81  4394.3  147.56  4460.6  146.48  4578.3  143.07
  4606.1  144.46  4950.1  143.93  4990.3  141.73  5034.2  142.64  5042.2  141.12
  5074.2  144.04  5084.2  144.85  5144.2  144.41  5524.3  158.77  5604.3   158.2
  5814.3  162.94  5973.2  163.09  6484.3  163.99  7054.3  168.39  7540.4  174.63
#Mann= 12 ,-1 , 0
  2722.4     .11       0  3039.2    .125       0  3230.8     .17       0
  3438.9     .15       0  3537.7     .17       0  3636.5     .11       0
  4460.6     .15       0  4606.1     .11       0  4950.1     .07       0
  5074.2     .11       0  5084.2     .11       0  5973.2     .17       0
#XS Ineff= 2 , 0
       0  4628.6  145.43               0
Permanent Ineff=
       F       F
Bank Sta=4950.1,5074.2
XS Rating Curve= 0 ,0
Exp/Cntr=0.3,0.1

Type RM Length L Ch R = 1 ,1592    ,426,426,426
BEGIN DESCRIPTION:
Conroe Lake 008 1.0
END DESCRIPTION:
XS GIS Cut Line= 4
      3806829.17     10124142.51      3804558.23     10123686.84
      3804431.19     10123871.89      3804474.59     10126614.99
#Sta/Elev= 30
  2683.8  167.71  2937.2  166.24    3190  166.52    3404  160.28  3579.1  149.93
  3798.1  147.03  3979.9  152.35  3992.9  152.22  4510.8  150.57  4886.2  142.23
  4959.6  142.97    4980  141.57  4995.6  138.96  5025.2  141.24  5031.3  142.16
    5076   139.8  5126.4  146.56  5153.8  140.04  5174.9   140.5  5243.6  150.95
  5483.7  146.89  5503.7  143.97  5573.7  150.29  5903.7  157.44  6286.8   160.7
  6963.9  164.19  7003.9  161.31  7083.9  165.33  7222.4  163.85  7967.9   174.5
#Mann= 13 ,-1 , 0
  2683.8     .11       0  2937.2    .125       0    3190     .17       0
    3404     .15       0  3798.1     .17       0  3979.9     .15       0
  3992.9     .11       0  4886.2     .15       0  4959.6     .12       0
    4980     .09       0  5025.2     .12       0  5031.3     .11       0
  6286.8     .17       0
#XS Ineff= 2 , 0
       0                  5126.4       0  146.56
Permanent Ineff=
       F       F
Bank Sta=4980,5025.2
XS Rating Curve= 0 ,0
Exp/Cntr=0.3,0.1

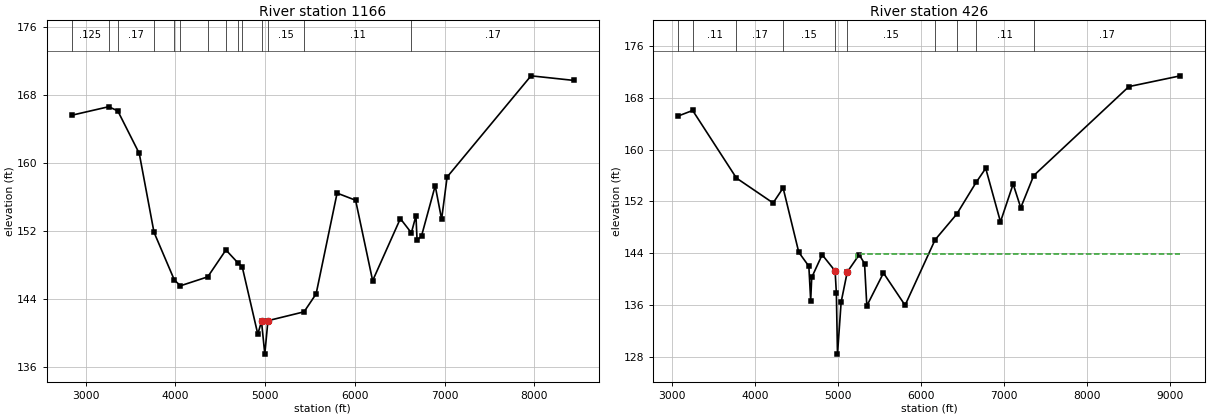
Type RM Length L Ch R = 1 ,1166    ,740,740,740
BEGIN DESCRIPTION:
Conroe Lake 008 2.5
END DESCRIPTION:
XS GIS Cut Line= 4
      3806831.81     10124087.83      3804748.23     10123536.84
      3804370.42     10123498.63      3803745.43     10126493.38
#Sta/Elev= 30
  2844.8  165.64  3256.5  166.64  3357.5  166.15  3596.8  161.15    3761  151.89
  3988.2  146.27  4055.7   145.6  4359.8  146.65  4562.4  149.81  4695.3   148.3
  4743.5  147.85  4917.6  139.92  4958.9  141.42  4995.6  137.57  5030.5   141.5
  5433.1  142.54  5567.4  144.65  5801.1  156.49  6007.3  155.65  6197.2   146.2
  6505.9  153.49  6628.7  151.82  6679.6  153.83  6692.2  150.94  6742.2  151.47
  6894.1  157.35  6965.6  153.42  7026.9  158.38  7961.9  170.27    8439  169.73
#Mann= 14 ,-1 , 0
  2844.8    .125       0  3256.5     .11       0  3357.5     .17       0
    3761     .15       0  3988.2     .17       0  4055.7     .15       0
  4359.8     .11       0  4562.4     .15       0  4695.3     .11       0
  4743.5     .15       0  4958.9     .09       0  5030.5     .15       0
  5433.1     .11       0  6628.7     .17       0
Bank Sta=4958.9,5030.5
XS Rating Curve= 0 ,0
Exp/Cntr=0.3,0.1

Type RM Length L Ch R = 1 ,426     ,0,0,0
BEGIN DESCRIPTION:
Conroe Lake 008 1.5
END DESCRIPTION:
XS GIS Cut Line= 4
      3806834.44     10124014.93      3805128.23     10123126.84
      3804196.81      10123333.7      3803606.54     10126449.98
#Sta/Elev= 30
  3076.5  165.18  3250.4  166.03  3777.7  155.61  4219.4  151.77  4340.2  154.09
  4528.9  144.17  4650.2  142.02  4672.3  136.73  4684.8  140.29  4810.6  143.79
  4966.6  141.29  4981.8  137.85  4995.3  128.47  5039.4  136.51  5113.1  141.13
  5256.5  143.79  5321.2  142.44  5348.7  135.91  5549.2  140.98  5809.6     136
  6171.1  146.09  6432.9  150.07  6664.9  154.93  6781.2  157.11    6959  148.86
  7111.7  154.69  7203.3  151.04  7359.3  155.99  8506.1  169.71  9125.8  171.37
#Mann= 10 ,-1 , 0
  3076.5    .125       0  3250.4     .11       0  3777.7     .17       0
  4340.2     .15       0  4966.6     .09       0  5113.1     .15       0
  6171.1     .11       0  6432.9     .15       0  6664.9     .11       0
  7359.3     .17       0
#XS Ineff= 2 , 0
       0                  5223.8       0  143.97
Permanent Ineff=
       F       F
Bank Sta=4966.6,5113.1
XS Rating Curve= 0 ,0
Exp/Cntr=0.3,0.1

Chan Stop Cuts=-1
Use User Specified Reach Order=0
Composite Channel Slope=5