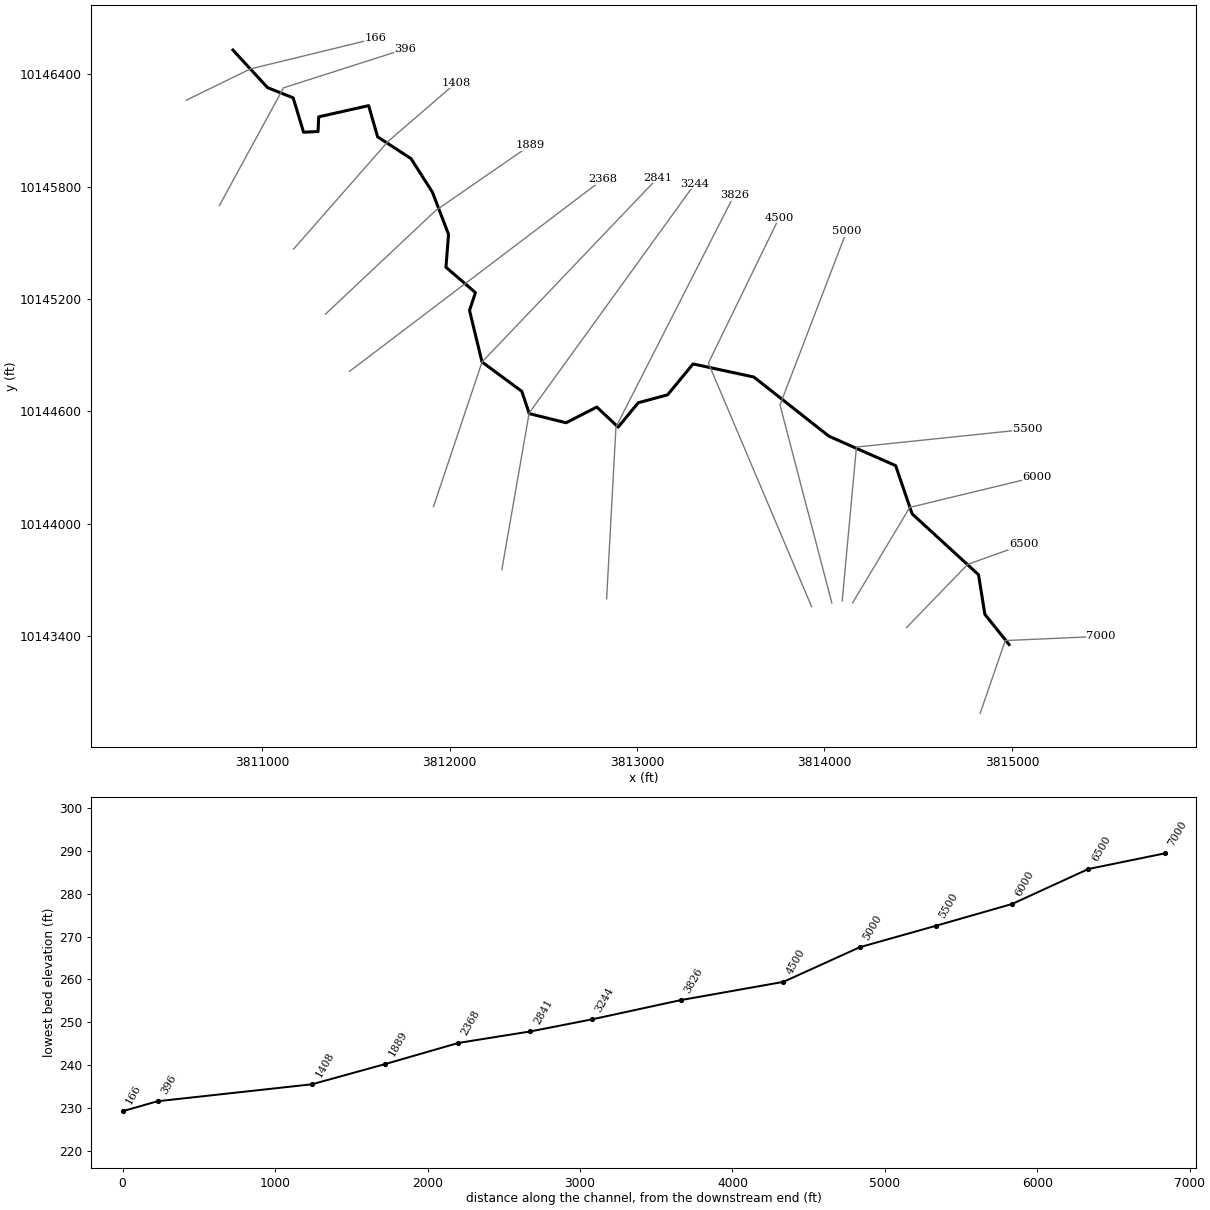
--- Conroe Lake 011.prj (project) ---

Proj Title=Conroe Lake 011 Base Level Engineering
Current Plan=p01
Default Exp/Contr=0.3,0.1
English Units
Geom File=g01
Flow File=f01
Flow File=f02
Plan File=p01
Y Axis Title=Elevation
X Axis Title(PF)=Main Channel Distance
X Axis Title(XS)=Station
BEGIN DESCRIPTION:
Conroe Lake 011
END DESCRIPTION:
DSS Export Rating Curves= 0
DSS Export Rating Curve Sorted= 0
DSS Export Volume Flow Curves= 0
DXF OffsetX= 0
DXF OffsetY= 0
DXF ScaleX= 1
DXF ScaleY= 10

--- Conroe Lake 011.p01 (plan) ---

Plan Title=Multiple Run
Short Identifier=Multiple
Geom File=g01
Flow File=f01
Subcritical Flow
K Sum by GR= 0
Std Step Tol= 0.01
Critical Tol= 0.01
Num of Std Step Trials= 20
Max Error Tol= 0.3
Flow Tol Ratio= 0.001
Split Flow NTrial= 30
Split Flow Tol= 0.02
Split Flow Ratio= 0.02
Log Output Level= 0
Friction Slope Method= 1
Unsteady Friction Slope Method= 2
Unsteady Bridges Friction Slope Method= 1
Parabolic Critical Depth
Global Vel Dist=  1 , 1 , 1
Global Log Level= 0
CheckData=True
Encroach Param= -1, 0, 0, 0
BEGIN DESCRIPTION:
Multiple Run
END DESCRIPTION:

--- Conroe Lake 011.f01 (steady flow) ---

Flow Title=Multiple
Program Version=4.10
Number of Profiles= 7
Profile Names=10-year,25-year,50-year,1pct_min,100-year,1pct_plu,500-year
River Rch & RM=Conroe Lake 011,Reach-1         ,7000
     414     551     736     325     982    2966    1801
River Rch & RM=Conroe Lake 011,Reach-1         ,6500
     722     984    1339     599    1808    5460    3412
Boundary for River Rch & Prof#=Conroe Lake 011,Reach-1         , 1
Up Type= 0
Dn Type= 3
Dn Slope=0.01
Boundary for River Rch & Prof#=Conroe Lake 011,Reach-1         , 2
Up Type= 0
Dn Type= 3
Dn Slope=0.01
Boundary for River Rch & Prof#=Conroe Lake 011,Reach-1         , 3
Up Type= 0
Dn Type= 3
Dn Slope=0.01
Boundary for River Rch & Prof#=Conroe Lake 011,Reach-1         , 4
Up Type= 0
Dn Type= 3
Dn Slope=0.01
Boundary for River Rch & Prof#=Conroe Lake 011,Reach-1         , 5
Up Type= 0
Dn Type= 3
Dn Slope=0.01
Boundary for River Rch & Prof#=Conroe Lake 011,Reach-1         , 6
Up Type= 0
Dn Type= 3
Dn Slope=0.01
Boundary for River Rch & Prof#=Conroe Lake 011,Reach-1         , 7
Up Type= 0
Dn Type= 3
Dn Slope=0.01
DSS Import GetInterval= 0
DSS Import GetPeak= 0
DSS Import FillOption= 0

--- Conroe Lake 011.f02 (steady flow) ---

Flow Title=Orig_BLE_Flow
Program Version=4.10
Number of Profiles= 7
Profile Names=10-year,25-year,50-year,1pct_min,100-year,1pct_plu,500-year
River Rch & RM=Conroe Lake 011,Reach-1         ,7000
     414     540     640     250     755    2281    1047
River Rch & RM=Conroe Lake 011,Reach-1         ,6500
     722     965    1164     461    1391    4201    1984
Boundary for River Rch & Prof#=Conroe Lake 011,Reach-1         , 1
Up Type= 0
Dn Type= 3
Dn Slope=0.01
Boundary for River Rch & Prof#=Conroe Lake 011,Reach-1         , 2
Up Type= 0
Dn Type= 3
Dn Slope=0.01
Boundary for River Rch & Prof#=Conroe Lake 011,Reach-1         , 3
Up Type= 0
Dn Type= 3
Dn Slope=0.01
Boundary for River Rch & Prof#=Conroe Lake 011,Reach-1         , 4
Up Type= 0
Dn Type= 3
Dn Slope=0.01
Boundary for River Rch & Prof#=Conroe Lake 011,Reach-1         , 5
Up Type= 0
Dn Type= 3
Dn Slope=0.01
Boundary for River Rch & Prof#=Conroe Lake 011,Reach-1         , 6
Up Type= 0
Dn Type= 3
Dn Slope=0.01
Boundary for River Rch & Prof#=Conroe Lake 011,Reach-1         , 7
Up Type= 0
Dn Type= 3
Dn Slope=0.01
DSS Import GetInterval= 0
DSS Import GetPeak= 0
DSS Import FillOption= 0

--- Conroe Lake 011.g01 (geometry) ---

Geom Title=Existing Conditions
Program Version=4.10

River Reach=Conroe Lake 011 ,Reach-1
Reach XY= 30
      3814984.98     10143355.01      3814855.75     10143516.19
      3814821.87     10143727.89      3814467.45     10144052.99
      3814379.77     10144310.19      3814023.69     10144467.47
      3813622.97      10144783.5      3813298.81     10144853.37
      3813163.04     10144688.44       3813006.1     10144646.08
      3812899.15     10144515.87      3812785.26     10144623.16
      3812621.38     10144539.13      3812424.85     10144588.09
      3812384.92     10144707.19      3812172.77     10144863.79
       3812106.1     10145139.13       3812137.7     10145234.27
       3811980.4     10145369.69      3811994.09     10145545.19
      3811908.15     10145770.45        3811794.     10145949.71
      3811615.62     10146066.03      3811567.87     10146232.69
      3811301.38      10146172.8      3811297.91     10146094.24
      3811220.65     10146090.77       3811165.1     10146274.36
      3811028.81     10146328.61      3810843.82     10146529.36

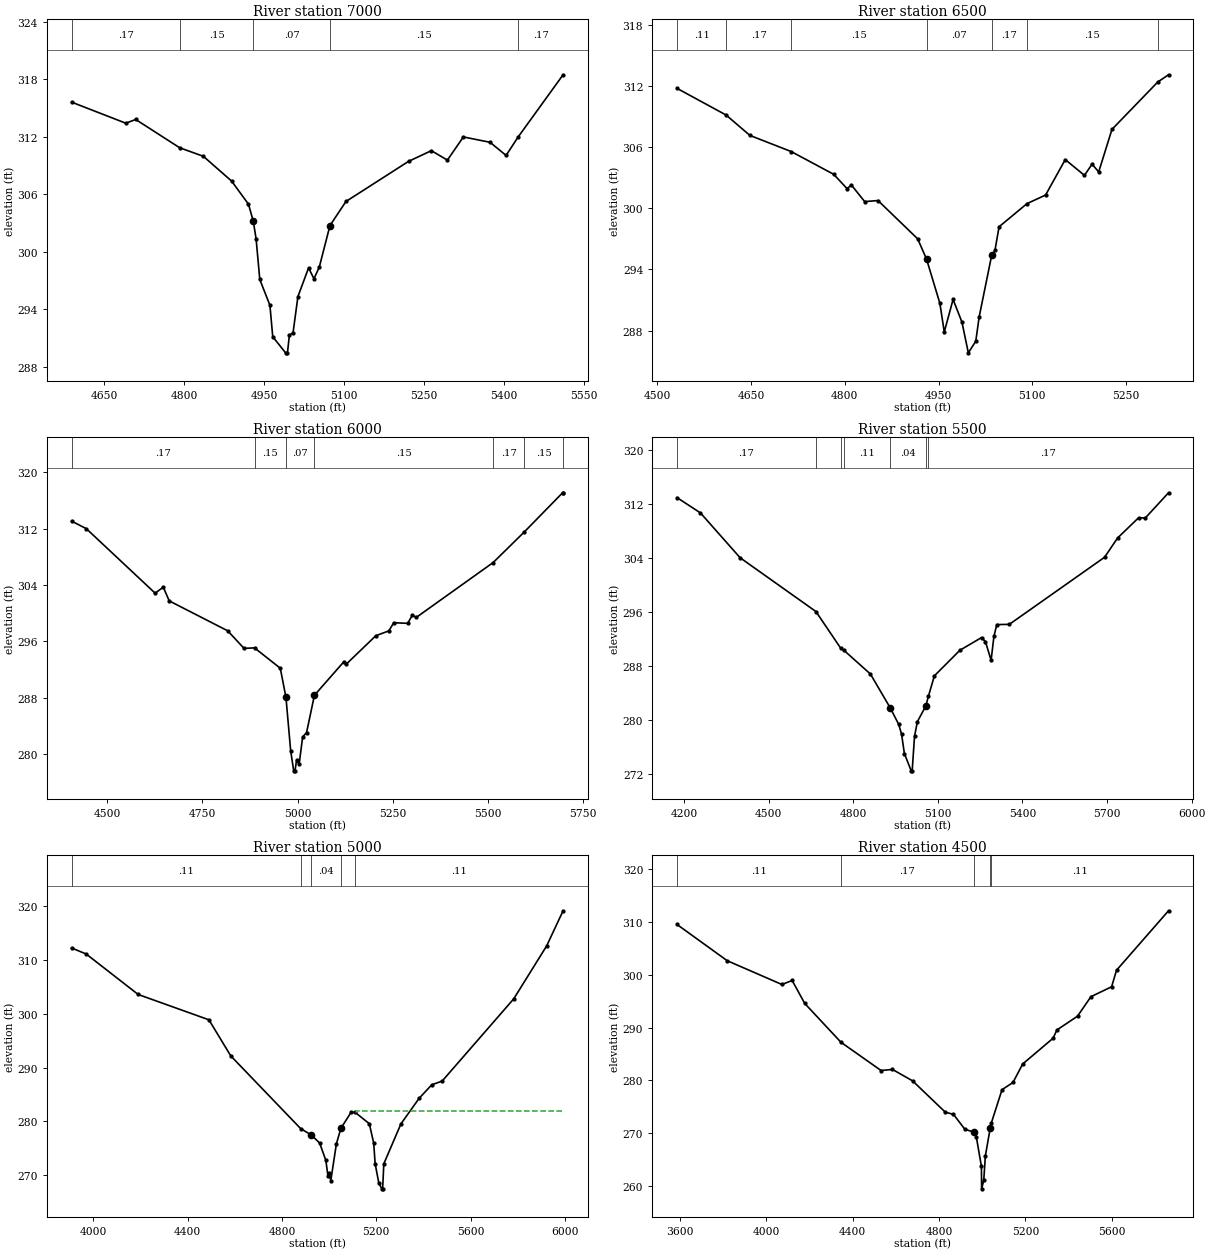
Type RM Length L Ch R = 1 ,7000    ,500,500,500
BEGIN DESCRIPTION:
Conroe Lake 011 14.0
END DESCRIPTION:
XS GIS Cut Line= 3
      3814830.52     10142987.39      3814964.64     10143376.21
      3815474.64      10143398.8
#Sta/Elev= 30
  4588.7   315.6  4690.5   313.4    4709  313.79  4791.5  310.84  4835.9  309.95
  4888.8  307.37  4920.5  304.96  4929.5  303.18  4934.8  301.34  4941.7  297.11
  4960.7  294.42    4966  291.14  4990.1  289.46  4993.6  289.46  4997.2  291.31
  5004.1  291.56  5013.2  295.32  5033.2  298.32  5043.3  297.18  5053.3   298.4
  5073.3  302.73  5103.3  305.24  5220.6  309.42  5263.5  310.54  5293.5  309.55
  5323.5  311.97  5373.6  311.41  5403.6  310.04    5426  311.95  5510.5  318.45
#Mann= 5 ,-1 , 0
  4588.7     .17       0  4791.5     .15       0  4929.5     .07       0
  5073.3     .15       0    5426     .17       0
Bank Sta=4929.5,5073.3
XS Rating Curve= 0 ,0
Exp/Cntr=0.3,0.1

Type RM Length L Ch R = 1 ,6500    ,500,500,500
BEGIN DESCRIPTION:
Conroe Lake 011 13.0
END DESCRIPTION:
XS GIS Cut Line= 3
       3814438.3      10143445.8      3814763.75     10143782.94
      3815063.03     10143890.14
#Sta/Elev= 30
  4531.4  311.76    4610  309.14  4648.1  307.14  4714.1  305.56  4782.3  303.32
  4803.4  301.93  4810.6  302.27  4831.7  300.65  4853.1  300.75  4916.6  296.99
  4930.8  294.99  4952.1  290.66  4959.1  287.86  4973.2  291.05  4987.4  288.82
  4997.6  285.81  5009.5  286.95    5015  289.36  5034.9  295.36  5040.2  295.86
  5046.8  298.18  5091.5  300.45  5121.2  301.29  5152.7  304.77  5183.4  303.22
  5195.6  304.32  5206.2  303.56  5227.4  307.73  5300.7  312.38  5317.9  313.09
#Mann= 7 ,-1 , 0
  4531.4     .11       0    4610     .17       0  4714.1     .15       0
  4930.8     .07       0  5034.9     .17       0  5091.5     .15       0
  5300.7     .17       0
Bank Sta=4930.8,5034.9
XS Rating Curve= 0 ,0
Exp/Cntr=0.3,0.1

Type RM Length L Ch R = 1 ,6000    ,500,500,500
BEGIN DESCRIPTION:
Conroe Lake 011 12.0
END DESCRIPTION:
XS GIS Cut Line= 3
       3814150.1     10143577.73      3814454.89     10144087.22
       3815132.7     10144251.34
#Sta/Elev= 30
  4406.3  313.08    4445  312.01  4625.9  302.85  4647.2  303.71  4662.8  301.76
  4816.5  297.51  4859.3  295.02  4886.9  295.09  4954.6   292.2  4969.5  288.05
  4981.8  280.51  4989.8  277.64  4993.3  277.64  4997.3  279.14  5004.1  278.58
  5013.3  282.45  5023.6  283.07  5044.2  288.36    5122  293.15  5127.1  292.74
  5205.6  296.82  5239.7   297.5  5252.6  298.66  5289.3  298.57  5301.4  299.73
  5311.7  299.41  5513.7   307.2  5595.5  311.54  5696.1   317.1  5697.4   317.1
#Mann= 7 ,-1 , 0
  4406.3     .17       0  4886.9     .15       0  4969.5     .07       0
  5044.2     .15       0  5513.7     .17       0  5595.5     .15       0
  5696.1     .17       0
Bank Sta=4969.5,5044.2
XS Rating Curve= 0 ,0
Exp/Cntr=0.3,0.1

Type RM Length L Ch R = 1 ,5500    ,500,500,500
BEGIN DESCRIPTION:
Conroe Lake 011 11.0
END DESCRIPTION:
XS GIS Cut Line= 3
      3814094.55     10143588.17      3814170.52     10144409.46
      3815083.46     10144504.75
#Sta/Elev= 30
  4175.2  312.95  4258.5  310.68  4399.1  304.05  4667.8   296.1  4755.1  290.71
  4766.9  290.37    4861  286.86  4931.3  281.85  4961.4  279.41  4971.5  277.95
  4981.5   275.1  5005.6  272.54  5009.1  272.54  5017.4  277.64  5027.5  279.81
  5057.6  282.14  5066.9   283.6  5087.8  286.59  5178.3  290.37    5255  292.25
  5268.8  291.66  5288.9  288.89  5298.9  292.41    5309  294.17  5353.5   294.2
  5691.1  304.12  5737.1  306.96  5811.7  309.96  5835.6  309.93  5917.9  313.66
#Mann= 7 ,-1 , 0
  4175.2     .17       0  4667.8     .11       0  4755.1     .17       0
  4766.9     .11       0  4931.3     .04       0  5057.6     .11       0
  5066.9     .17       0
Bank Sta=4931.3,5057.6
XS Rating Curve= 0 ,0
Exp/Cntr=0.3,0.1

Type RM Length L Ch R = 1 ,5000    ,500,500,500
BEGIN DESCRIPTION:
Conroe Lake 011 10.0
END DESCRIPTION:
XS GIS Cut Line= 3
        3814039.     10143577.71      3813762.67     10144634.28
      3814117.84     10145561.05
#Sta/Elev= 30
  3907.9  312.15    3970  311.03  4190.5  303.53  4490.4  298.84  4583.2  292.15
  4879.3  278.69  4924.9  277.49  4960.1     276  4986.4  272.78  4995.4  269.87
  4999.7  270.52  5007.3  269.04  5031.2  275.88  5050.1  278.72    5093  281.68
  5110.6  281.69  5170.7  279.59  5189.3     276  5195.4  272.19  5210.8  268.62
  5223.7  267.52  5227.2  267.52  5232.2  272.16  5304.8  279.56  5382.1   284.3
  5435.6   286.8  5479.7  287.49  5783.3  302.73  5922.8  312.53  5992.5  319.04
#Mann= 5 ,-1 , 0
  3907.9     .11       0  4879.3     .08       0  4924.9     .04       0
  5050.1     .08       0  5110.6     .11       0
#XS Ineff= 2 , 0
       0                    5116       0   281.9
Permanent Ineff=
       F       F
Bank Sta=4924.9,5050.1
XS Rating Curve= 0 ,0
Exp/Cntr=0.3,0.1

Type RM Length L Ch R = 1 ,4500    ,674,674,674
BEGIN DESCRIPTION:
Conroe Lake 011 9.0
END DESCRIPTION:
XS GIS Cut Line= 3
      3813931.36     10143556.89      3813380.69     10144857.95
      3813757.76     10145633.33
#Sta/Elev= 30
  3587.2  309.57  3819.8  302.69  4072.9  298.18  4120.3  298.94  4178.5  294.59
  4346.3  287.22  4531.8  281.87  4584.6  282.07  4677.6  279.91  4829.6  273.95
  4866.9  273.56  4919.7  270.72    4960  270.21  4972.5  269.32  4996.2  263.71
  4997.2  259.43    5007  261.04  5014.6  265.69  5036.8  270.91  5042.9  272.01
  5091.6  278.23  5142.3   279.6  5187.4  283.11  5328.3     288  5345.3  289.55
    5441  292.17  5503.1  295.87  5598.9  297.75  5621.5  300.88  5862.2  312.16
#Mann= 5 ,-1 , 0
  3587.2     .11       0  4346.3     .17       0    4960     .07       0
  5036.8     .17       0  5042.9     .11       0
Bank Sta=4960,5036.8
XS Rating Curve= 0 ,0
Exp/Cntr=0.3,0.1

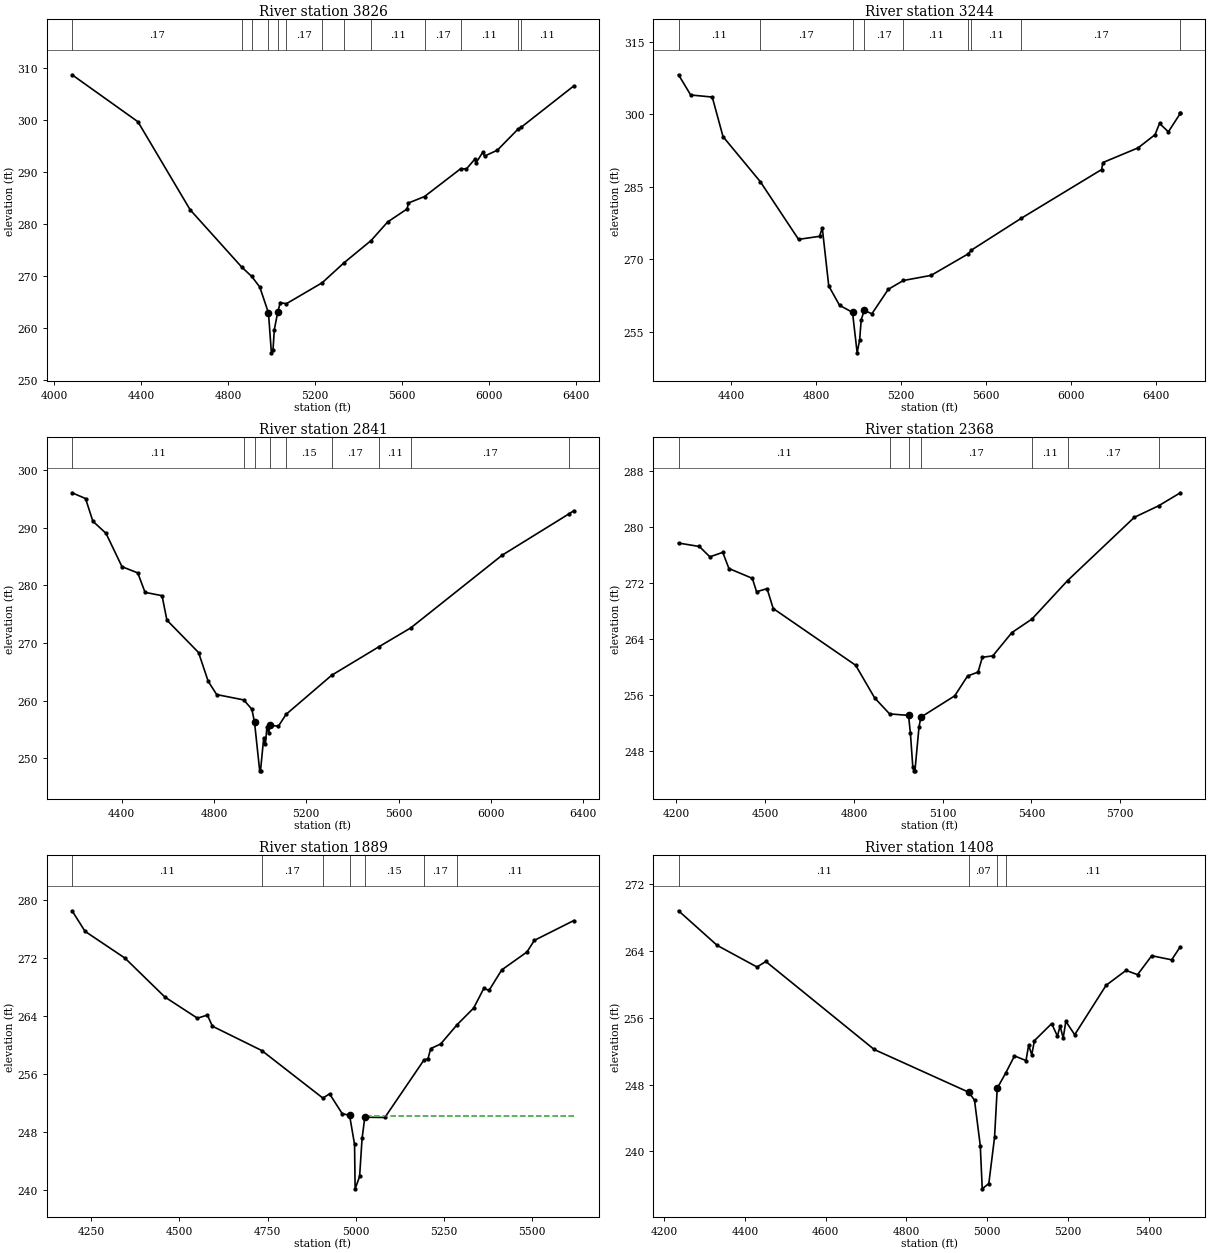
Type RM Length L Ch R = 1 ,3826    ,582,582,582
BEGIN DESCRIPTION:
Conroe Lake 011 8.0
END DESCRIPTION:
XS GIS Cut Line= 3
       3812837.6     10143598.56      3812887.35     10144516.22
      3813518.17     10145754.83
#Sta/Elev= 30
    4081  308.76    4384  299.71  4624.3  282.74  4861.9  271.68  4907.4   269.9
  4944.8  267.84  4984.8  262.84  4998.2  255.16  5005.5  255.66  5011.6  259.62
  5027.9  263.12  5039.4  264.86  5066.8  264.62  5231.9  268.67  5331.6  272.49
    5457  276.81  5532.9  280.38  5622.7   282.9  5628.7  284.04  5702.8  285.29
  5869.5  290.66  5895.6  290.61  5934.4   292.5    5940  291.78  5970.6  293.82
  5978.9  293.08  6037.9  294.22    6132  298.24  6146.9  298.62    6390  306.62
#Mann= 13 ,-1 , 0
    4081     .17       0  4861.9     .11       0  4907.4     .15       0
  4984.8     .07       0  5027.9     .15       0  5066.8     .17       0
  5231.9     .11       0  5331.6     .17       0    5457     .11       0
  5702.8     .17       0  5869.5     .11       0    6132     .17       0
  6146.9     .11       0
Bank Sta=4984.8,5027.9
XS Rating Curve= 0 ,0
Exp/Cntr=0.3,0.1

Type RM Length L Ch R = 1 ,3244    ,403,403,403
BEGIN DESCRIPTION:
Mapping XS 0619b9dd
END DESCRIPTION:
XS GIS Cut Line= 3
      3812278.58     10143754.87      3812424.41     10144591.62
      3813309.35     10145816.66
#Sta/Elev= 30
  4153.4   308.2  4210.5  304.02    4312  303.59  4362.7   295.4  4538.1  286.08
    4718  274.14  4816.7  274.77  4829.6  276.51  4860.1   264.5  4910.9  260.49
  4971.8  259.04  4993.7  250.66  5005.5  253.35  5012.7  257.47  5026.8  259.45
    5063  258.74  5140.3  263.81  5211.1  265.63  5341.5  266.69  5515.9  271.14
  5531.2  271.92  5765.3  278.49  6143.7  288.59  6149.9  290.04  6315.5  293.08
  6395.2  295.81  6416.1  298.13  6457.8   296.4  6513.6  300.19    6514   300.2
#Mann= 9 ,-1 , 0
  4153.4     .11       0  4538.1     .17       0  4971.8     .07       0
  5026.8     .17       0  5211.1     .11       0  5515.9     .17       0
  5531.2     .11       0  5765.3     .17       0  6513.6     .11       0
Bank Sta=4971.8,5026.8
XS Rating Curve= 0 ,0
Exp/Cntr=0.3,0.1

Type RM Length L Ch R = 1 ,2841    ,473,473,473
BEGIN DESCRIPTION:
Conroe Lake 011 6.0
END DESCRIPTION:
XS GIS Cut Line= 3
      3811913.98      10144091.6      3812172.77     10144863.79
      3813110.73     10145847.34
#Sta/Elev= 30
  4185.6  296.08    4244  295.08  4275.6  291.15  4332.7  289.04  4401.8  283.26
  4470.2  282.18  4501.7  278.81  4575.3  278.23  4596.4  273.99  4733.5  268.37
  4775.2  263.38    4812  261.08  4929.2  260.15  4964.5  258.53    4976  256.24
  4998.3  247.85  5001.8  247.85  5015.8   253.6    5023  252.48  5029.9   255.5
  5037.2   254.5  5044.1  255.75  5079.3  255.59  5112.4  257.64  5310.2  264.43
    5515  269.38  5652.5  272.64  6048.4  285.25  6339.8  292.47  6359.1  292.98
#Mann= 9 ,-1 , 0
  4185.6     .11       0  4929.2     .17       0    4976     .07       0
  5044.1     .17       0  5112.4     .15       0  5310.2     .17       0
    5515     .11       0  5652.5     .17       0  6339.8     .11       0
Bank Sta=4976,5044.1
XS Rating Curve= 0 ,0
Exp/Cntr=0.3,0.1

Type RM Length L Ch R = 1 ,2368    ,479,479,479
BEGIN DESCRIPTION:
Mapping XS 0b73cda4
END DESCRIPTION:
XS GIS Cut Line= 3
      3811466.09     10144813.86      3812101.49     10145296.48
       3812817.7     10145839.33
#Sta/Elev= 30
  4206.9  277.72  4277.4  277.23  4312.8  275.75  4356.4  276.39  4377.3  274.08
  4456.3  272.68  4470.8  270.76  4506.2   271.2    4527  268.36  4805.7  260.25
  4870.1  255.57  4920.6  253.29  4984.5  253.08  4990.8  250.57    4999   245.7
  5002.7  245.15  5006.2  245.15  5019.9   251.4  5026.2  252.82  5140.6  255.87
  5184.2  258.71  5219.6  259.27  5234.1  261.39  5269.5  261.59    5334  264.92
    5402  266.86  5522.4  272.36    5748   281.4  5830.6  283.06  5903.5  284.91
#Mann= 7 ,-1 , 0
  4206.9     .11       0  4920.6     .17       0  4984.5     .07       0
  5026.2     .17       0    5402     .11       0  5522.4     .17       0
  5830.6     .11       0
Bank Sta=4984.5,5026.2
XS Rating Curve= 0 ,0
Exp/Cntr=0.3,0.1

Type RM Length L Ch R = 1 ,1889    ,481,481,481
BEGIN DESCRIPTION:
Conroe Lake 011 4.0
END DESCRIPTION:
XS GIS Cut Line= 3
      3811337.62     10145119.42      3811923.34     10145670.63
      3812431.36     10146022.19
#Sta/Elev= 30
  4195.7  278.48  4232.5  275.65  4345.8  271.96  4458.6  266.62  4550.9   263.7
  4579.2  264.13  4593.4   262.6  4733.3  259.25  4906.5  252.71  4925.5  253.29
  4961.1  250.58  4982.2  250.32  4996.3  246.33  4997.9  240.22  5010.6  241.92
  5017.6  247.16  5025.4  250.07  5082.2  250.04  5192.6  257.92  5204.5  258.15
  5212.2  259.52  5240.3  260.15    5287  262.81  5333.8  265.09  5362.6   267.8
  5377.5  267.53  5413.3  270.34  5484.9  272.81  5505.9  274.41  5617.8  277.14
#Mann= 7 ,-1 , 0
  4195.7     .11       0  4733.3     .17       0  4906.5     .15       0
  4982.2     .07       0  5025.4     .15       0  5192.6     .17       0
    5287     .11       0
#XS Ineff= 2 , 0
       0                  5031.5       0  250.29
Permanent Ineff=
       F       F
Bank Sta=4982.2,5025.4
XS Rating Curve= 0 ,0
Exp/Cntr=0.3,0.1

Type RM Length L Ch R = 1 ,1408    ,1012,1012,1012
BEGIN DESCRIPTION:
Conroe Lake 011 3.0
END DESCRIPTION:
XS GIS Cut Line= 3
      3811167.45     10145466.61      3811671.61     10146041.72
      3812034.22     10146354.39
#Sta/Elev= 30
  4235.2  268.83    4331  264.68  4429.7  262.09  4451.5  262.75  4720.1   252.2
  4954.5  247.07  4968.7  246.12    4983  240.68  4987.9  235.49  5004.2  236.13
  5018.4  241.67    5025  247.55  5046.5  249.42  5067.8  251.43  5096.3  250.87
  5102.9  252.72  5110.6  251.56  5117.2  253.26  5159.9   255.3  5174.2   253.8
  5180.8     255  5188.5  253.58  5195.1  255.57    5217  253.97  5294.9   259.9
  5344.3  261.68  5372.8  261.17  5407.9  263.44  5457.3  262.95  5478.8  264.52
#Mann= 4 ,-1 , 0
  4235.2     .11       0  4954.5     .07       0    5025     .15       0
  5046.5     .11       0
Bank Sta=4954.5,5025
XS Rating Curve= 0 ,0
Exp/Cntr=0.3,0.1

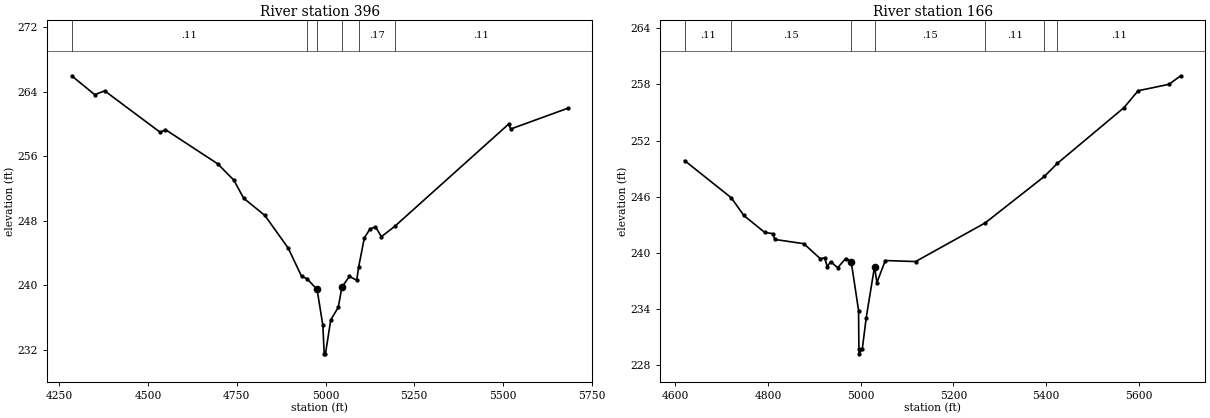
Type RM Length L Ch R = 1 ,396     ,230,230,230
BEGIN DESCRIPTION:
Conroe Lake 011 2.0
END DESCRIPTION:
XS GIS Cut Line= 3
      3810771.64     10145699.29      3811113.88     10146327.75
       3811763.8     10146535.78
#Sta/Elev= 30
  4284.4  265.99  4349.4  263.65  4377.5  264.12  4534.5  258.97  4548.3  259.33
  4696.3  255.07  4741.6  253.05  4769.1  250.82  4828.9  248.68  4894.5  244.65
  4932.4  241.14  4947.5  240.85  4976.1  239.51  4992.3  235.09  4996.2  231.53
  4999.7  231.53  5014.7  235.75  5035.7  237.28  5046.2  239.81  5067.2  241.12
  5087.9  240.65  5093.1  242.25  5109.2  245.89  5125.3  247.01  5140.7  247.27
  5157.5  246.05  5195.5  247.35  5516.4  260.02  5521.6  259.39  5682.4  261.96
#Mann= 6 ,-1 , 0
  4284.4     .11       0  4947.5     .15       0  4976.1     .07       0
  5046.2     .15       0  5093.1     .17       0  5195.5     .11       0
Bank Sta=4976.1,5046.2
XS Rating Curve= 0 ,0
Exp/Cntr=0.3,0.1

Type RM Length L Ch R = 1 ,166     ,0,0,0
BEGIN DESCRIPTION:
Conroe Lake 011 1.0
END DESCRIPTION:
XS GIS Cut Line= 3
      3810594.89      10146261.5      3810936.36     10146428.44
       3811606.9       10146592.
#Sta/Elev= 30
  4619.9  249.86  4720.7  245.88  4747.7  243.99  4792.7  242.18  4809.7  242.05
  4815.2  241.42  4877.2  240.97  4912.6  239.37  4922.2  239.46  4927.8  238.51
  4934.9  239.05  4950.3   238.4  4967.3  239.38  4979.4  239.06  4995.3  233.82
    4996  229.69  4996.3  229.19  5003.3  229.69  5011.8  233.05  5029.7   238.5
  5034.9  236.82    5053  239.17  5118.3  239.06  5268.7   243.2  5396.3  248.17
  5424.5  249.57  5567.7  255.51  5598.5  257.33  5665.3  258.02  5690.2  258.93
#Mann= 7 ,-1 , 0
  4619.9     .11       0  4720.7     .15       0  4979.4     .07       0
  5029.7     .15       0  5268.7     .11       0  5396.3     .17       0
  5424.5     .11       0
Bank Sta=4979.4,5029.7
XS Rating Curve= 0 ,0
Exp/Cntr=0.3,0.1

Chan Stop Cuts=-1
Use User Specified Reach Order=0
Composite Channel Slope=5