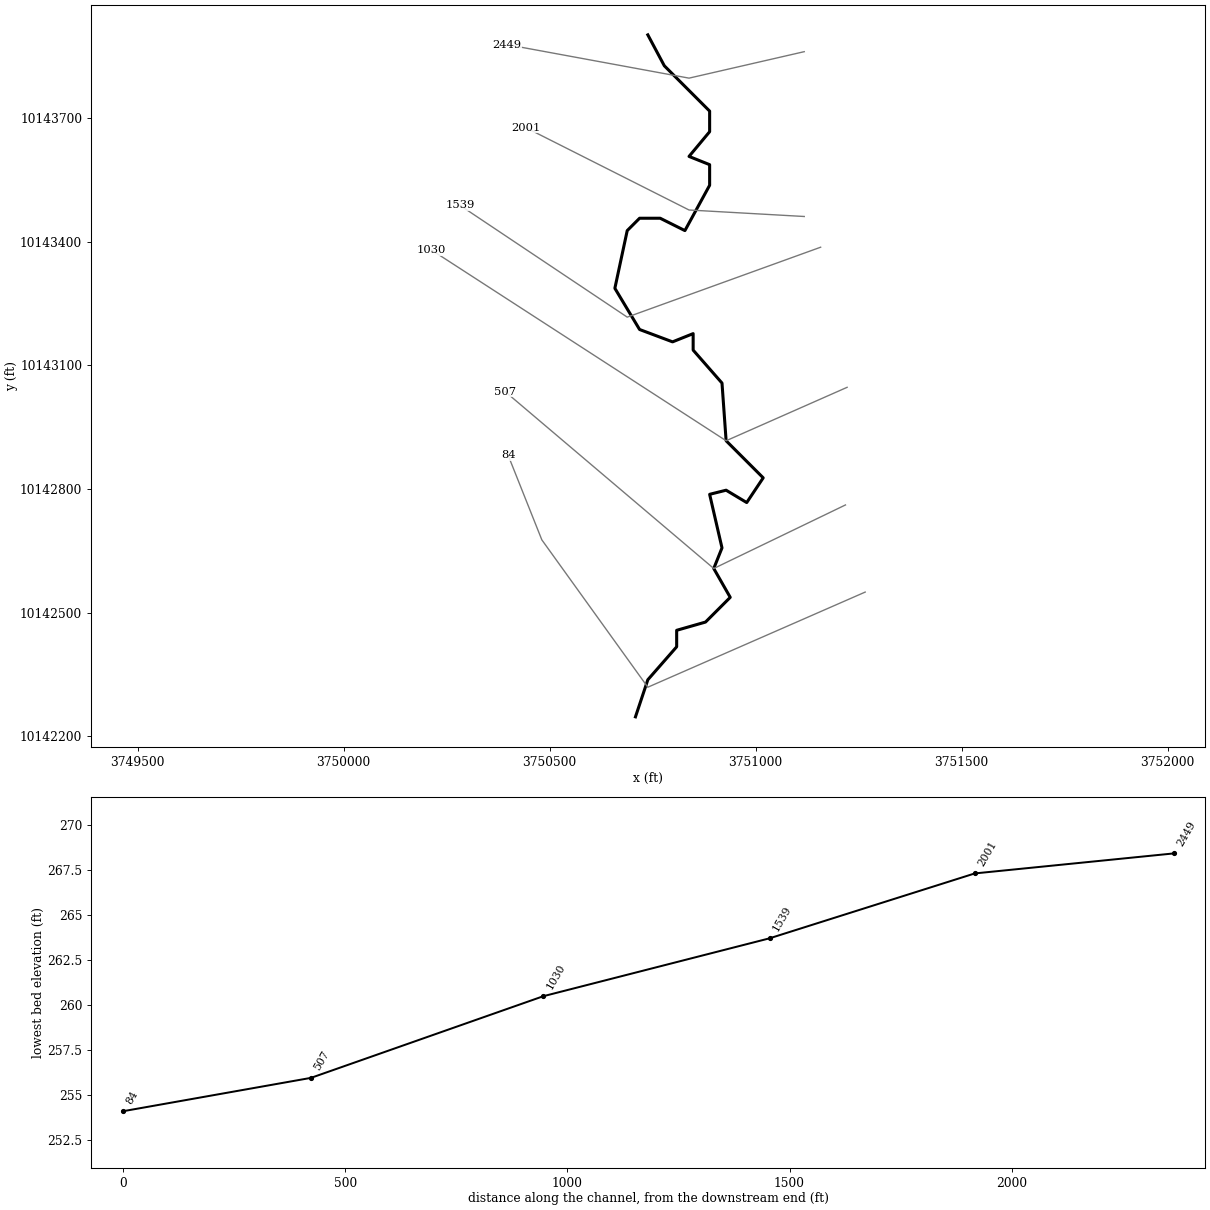
--- Conroe Lake 015.prj (project) ---

Proj Title=Conroe Lake 015 Base Level Engineering
Current Plan=p01
Default Exp/Contr=0.3,0.1
English Units
Geom File=g01
Flow File=f01
Flow File=f02
Plan File=p01
Y Axis Title=Elevation
X Axis Title(PF)=Main Channel Distance
X Axis Title(XS)=Station
BEGIN DESCRIPTION:
Conroe Lake 015
END DESCRIPTION:
DSS Export Rating Curves= 0
DSS Export Rating Curve Sorted= 0
DSS Export Volume Flow Curves= 0
DXF OffsetX= 0
DXF OffsetY= 0
DXF ScaleX= 1
DXF ScaleY= 10

--- Conroe Lake 015.p01 (plan) ---

Plan Title=Multiple Run
Short Identifier=Multiple
Geom File=g01
Flow File=f01
Subcritical Flow
K Sum by GR= 0
Std Step Tol= 0.01
Critical Tol= 0.01
Num of Std Step Trials= 20
Max Error Tol= 0.3
Flow Tol Ratio= 0.001
Split Flow NTrial= 30
Split Flow Tol= 0.02
Split Flow Ratio= 0.02
Log Output Level= 0
Friction Slope Method= 1
Unsteady Friction Slope Method= 2
Unsteady Bridges Friction Slope Method= 1
Parabolic Critical Depth
Global Vel Dist=  1 , 1 , 1
Global Log Level= 0
CheckData=True
Encroach Param= -1, 0, 0, 0
BEGIN DESCRIPTION:
Multiple Run
END DESCRIPTION:

--- Conroe Lake 015.f01 (steady flow) ---

Flow Title=Multiple
Program Version=4.10
Number of Profiles= 7
Profile Names=10-year,25-year,50-year,1pct_min,100-year,1pct_plu,500-year
River Rch & RM=Conroe Lake 015,Reach-1         ,2449
     433     569     754     329     995    3005    1785
River Rch & RM=Conroe Lake 015,Reach-1         ,84
    1089    1516    2086     943    2847    8598    5483
Boundary for River Rch & Prof#=Conroe Lake 015,Reach-1         , 1
Up Type= 0
Dn Type= 3
Dn Slope=0.006
Boundary for River Rch & Prof#=Conroe Lake 015,Reach-1         , 2
Up Type= 0
Dn Type= 3
Dn Slope=0.006
Boundary for River Rch & Prof#=Conroe Lake 015,Reach-1         , 3
Up Type= 0
Dn Type= 3
Dn Slope=0.006
Boundary for River Rch & Prof#=Conroe Lake 015,Reach-1         , 4
Up Type= 0
Dn Type= 3
Dn Slope=0.006
Boundary for River Rch & Prof#=Conroe Lake 015,Reach-1         , 5
Up Type= 0
Dn Type= 3
Dn Slope=0.006
Boundary for River Rch & Prof#=Conroe Lake 015,Reach-1         , 6
Up Type= 0
Dn Type= 3
Dn Slope=0.006
Boundary for River Rch & Prof#=Conroe Lake 015,Reach-1         , 7
Up Type= 0
Dn Type= 3
Dn Slope=0.006
DSS Import GetInterval= 0
DSS Import GetPeak= 0
DSS Import FillOption= 0

--- Conroe Lake 015.f02 (steady flow) ---

Flow Title=Orig_BLE_Flow
Program Version=4.10
Number of Profiles= 7
Profile Names=10-year,25-year,50-year,1pct_min,100-year,1pct_plu,500-year
River Rch & RM=Conroe Lake 015,Reach-1         ,2449
     433     558     656     253     765    2311    1038
River Rch & RM=Conroe Lake 015,Reach-1         ,84
    1089    1486    1814     725    2190    6613    3188
Boundary for River Rch & Prof#=Conroe Lake 015,Reach-1         , 1
Up Type= 0
Dn Type= 3
Dn Slope=0.009
Boundary for River Rch & Prof#=Conroe Lake 015,Reach-1         , 2
Up Type= 0
Dn Type= 3
Dn Slope=0.009
Boundary for River Rch & Prof#=Conroe Lake 015,Reach-1         , 3
Up Type= 0
Dn Type= 3
Dn Slope=0.009
Boundary for River Rch & Prof#=Conroe Lake 015,Reach-1         , 4
Up Type= 0
Dn Type= 3
Dn Slope=0.009
Boundary for River Rch & Prof#=Conroe Lake 015,Reach-1         , 5
Up Type= 0
Dn Type= 3
Dn Slope=0.009
Boundary for River Rch & Prof#=Conroe Lake 015,Reach-1         , 6
Up Type= 0
Dn Type= 3
Dn Slope=0.009
Boundary for River Rch & Prof#=Conroe Lake 015,Reach-1         , 7
Up Type= 0
Dn Type= 3
Dn Slope=0.009
DSS Import GetInterval= 0
DSS Import GetPeak= 0
DSS Import FillOption= 0

--- Conroe Lake 015.g01 (geometry) ---

Geom Title=Existing Conditions
Program Version=4.10

River Reach=Conroe Lake 015 ,Reach-1
Reach XY= 30
      3750738.23     10143901.84      3750778.23     10143826.84
      3750888.23     10143716.84      3750888.23     10143666.84
      3750838.23     10143606.84      3750888.23     10143586.84
      3750888.23     10143536.84      3750828.23     10143426.84
      3750768.23     10143456.84      3750718.23     10143456.84
      3750688.23     10143426.84      3750658.23     10143286.84
      3750718.23     10143186.84      3750798.23     10143156.84
      3750848.23     10143176.84      3750848.23     10143136.84
      3750918.23     10143056.84      3750928.23     10142916.84
      3751018.23     10142826.84      3750978.23     10142766.84
      3750928.23     10142796.84      3750888.23     10142786.84
      3750918.23     10142656.84      3750898.23     10142606.84
      3750938.23     10142536.84      3750878.23     10142476.84
      3750808.23     10142456.84      3750808.23     10142416.84
      3750738.23     10142336.84      3750708.23     10142246.84

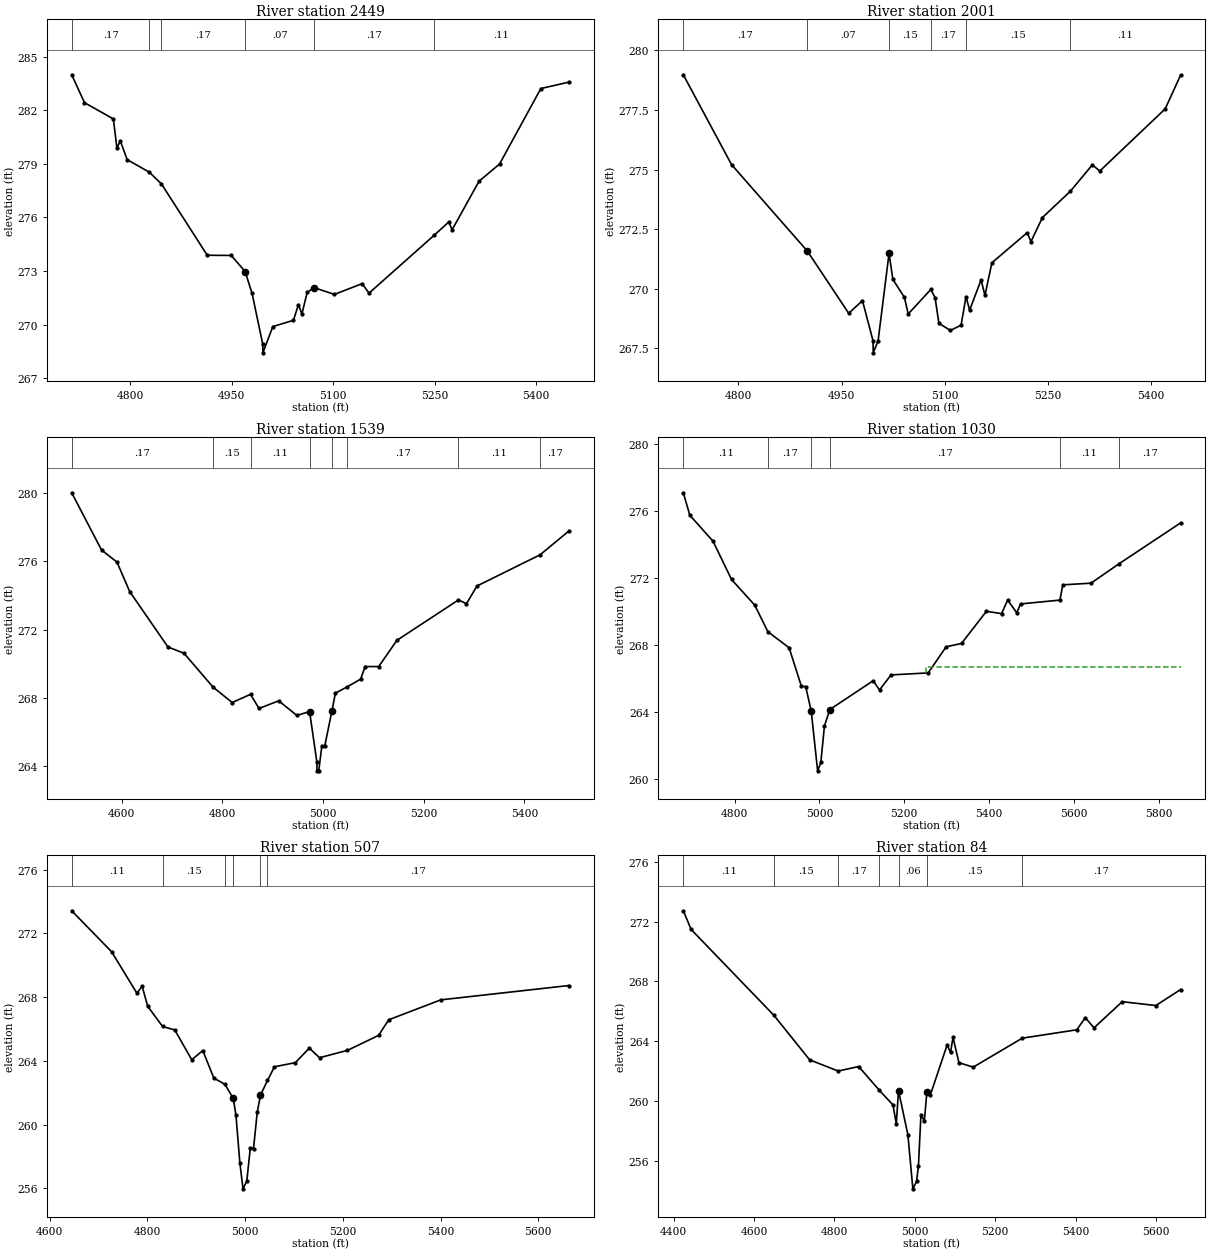
Type RM Length L Ch R = 1 ,2449    ,448,448,448
BEGIN DESCRIPTION:
Conroe Lake 015 5.0
END DESCRIPTION:
XS GIS Cut Line= 3
      3751117.85     10143861.07      3750838.23     10143796.84
      3750396.95      10143878.1
#Sta/Elev= 30
  4713.1  283.98    4732  282.42  4774.7  281.51  4779.9   279.9  4785.1  280.27
  4795.2  279.23  4827.9  278.53  4845.9  277.87  4913.6  273.88  4949.1  273.87
  4969.6  272.97  4979.9  271.75  4995.6  268.92  4995.9  268.42  5010.6  269.89
  5041.1  270.24  5048.5  271.12  5053.6  270.59  5061.4   271.8  5071.6  272.07
  5101.6  271.69  5142.7  272.29  5152.9  271.76    5249  274.99  5270.8  275.74
  5275.9  275.31  5315.6  278.02  5346.1  278.99  5407.1  283.21  5448.7  283.57
#Mann= 6 ,-1 , 0
  4713.1     .17       0  4827.9     .11       0  4845.9     .17       0
  4969.6     .07       0  5071.6     .17       0    5249     .11       0
Bank Sta=4969.6,5071.6
XS Rating Curve= 0 ,0
Exp/Cntr=0.3,0.1

Type RM Length L Ch R = 1 ,2001    ,462,462,462
BEGIN DESCRIPTION:
Conroe Lake 015 4.0
END DESCRIPTION:
XS GIS Cut Line= 3
      3751117.89     10143461.07      3750838.23     10143476.84
      3750443.06     10143676.18
#Sta/Elev= 30
  4719.9  278.98    4790  275.21  4900.2  271.58  4960.3  268.97  4980.3   269.5
  4995.7  267.81  4995.9  267.31    5003  267.81  5018.9  271.48  5024.5  270.39
  5041.2  269.64  5046.8  268.94  5079.6  269.97  5085.8  269.63  5091.4  268.55
  5108.1  268.25  5123.6  268.47  5130.8  269.67    5136   269.1  5152.7  270.37
  5158.3  269.72  5168.4  271.09  5219.6  272.35  5225.2  271.98  5241.9  272.99
  5282.4  274.09  5314.4   275.2  5325.2  274.94  5420.3  277.55  5442.6  278.96
#Mann= 6 ,-1 , 0
  4719.9     .17       0  4900.2     .07       0  5018.9     .15       0
  5079.6     .17       0  5130.8     .15       0  5282.4     .11       0
Bank Sta=4900.2,5018.9
XS Rating Curve= 0 ,0
Exp/Cntr=0.3,0.1

Type RM Length L Ch R = 1 ,1539    ,509,509,509
BEGIN DESCRIPTION:
Conroe Lake 015 3.0
END DESCRIPTION:
XS GIS Cut Line= 3
       3751157.6     10143386.54      3750688.23     10143216.84
       3750282.2     10143488.27
#Sta/Elev= 30
  4500.9  280.03  4560.1  276.67  4590.8  275.96  4616.1  274.23    4692  270.98
  4723.9  270.61  4781.7  268.62  4819.6  267.72    4856   268.2  4872.8  267.37
    4912  267.82    4948  266.96  4973.3  267.19  4987.8  264.21    4988  263.71
  4991.5  263.71  4997.5  265.14  5003.2  265.14  5017.6  267.21  5024.5  268.27
  5047.2  268.63  5074.6  269.09  5083.6  269.83  5110.6  269.83  5146.7  271.37
  5268.9  273.74  5284.8  273.52  5305.8  274.56  5431.1  276.39  5488.4  277.79
#Mann= 8 ,-1 , 0
  4500.9     .17       0  4781.7     .15       0    4856     .11       0
  4973.3     .07       0  5017.6     .15       0  5047.2     .17       0
  5268.9     .11       0  5431.1     .17       0
Bank Sta=4973.3,5017.6
XS Rating Curve= 0 ,0
Exp/Cntr=0.3,0.1

Type RM Length L Ch R = 1 ,1030    ,523,523,523
BEGIN DESCRIPTION:
Conroe Lake 015 2.0
END DESCRIPTION:
XS GIS Cut Line= 3
      3751221.86     10143046.54      3750928.23     10142916.84
      3750213.62      10143379.5
#Sta/Elev= 30
    4679  277.11  4694.3  275.77    4749  274.22  4792.7  271.93  4847.4   270.4
  4878.4  268.81  4928.5  267.85  4957.3  265.56  4967.6  265.53  4980.6  264.06
  4995.7   260.5  5003.2     261  5011.7  263.17  5024.3  264.16  5126.5  265.88
  5141.6  265.33  5168.7  266.23  5256.4  266.35  5298.6  267.91  5334.9  268.11
  5393.6  270.03  5429.3  269.89  5443.7   270.7  5465.1  269.94    5474  270.47
    5567   270.7  5573.6  271.61  5640.2  271.71  5705.7  272.86  5851.3  275.31
#Mann= 6 ,-1 , 0
    4679     .11       0  4878.4     .17       0  4980.6     .09       0
  5024.3     .17       0    5567     .11       0  5705.7     .17       0
#XS Ineff= 2 , 0
       0                  5250.4       0  266.72
Permanent Ineff=
       F       F
Bank Sta=4980.6,5024.3
XS Rating Curve= 0 ,0
Exp/Cntr=0.3,0.1

Type RM Length L Ch R = 1 ,507     ,423,423,423
BEGIN DESCRIPTION:
Conroe Lake 015 1.0
END DESCRIPTION:
XS GIS Cut Line= 3
      3751217.86     10142761.08      3750898.23     10142606.84
      3750392.64     10143035.58
#Sta/Elev= 30
  4645.1  273.42    4727  270.84  4778.4  268.25  4789.3  268.68  4800.6  267.43
    4831  266.16  4856.1  265.94  4890.8  264.07  4913.4  264.65    4936  262.92
  4958.7  262.53  4975.7  261.65  4981.3  260.59  4989.3  257.59  4995.7  255.97
  5003.5  256.47  5010.7  258.55  5017.2   258.5  5024.9  260.79  5031.5  261.85
  5045.8  262.77  5060.1  263.63  5102.9  263.89  5131.5   264.8  5152.3   264.2
  5209.5  264.66  5273.2   265.6    5294  266.58  5400.6  267.83  5662.9  268.73
#Mann= 6 ,-1 , 0
  4645.1     .11       0    4831     .15       0  4958.7     .12       0
  4975.7     .09       0  5031.5     .12       0  5045.8     .17       0
Bank Sta=4975.7,5031.5
XS Rating Curve= 0 ,0
Exp/Cntr=0.3,0.1

Type RM Length L Ch R = 1 ,84      ,0,0,0
BEGIN DESCRIPTION:
Conroe Lake 015 1.5
END DESCRIPTION:
XS GIS Cut Line= 4
      3751265.71     10142549.63      3750738.23     10142318.73
      3750480.99     10142676.37      3750399.38     10142881.27
#Sta/Elev= 30
  4424.2  272.72  4443.7  271.47  4649.8  265.72  4738.4  262.75  4809.4     262
  4860.5   262.3  4911.6  260.72  4945.8  259.73    4954  258.47  4959.5  260.69
  4982.9  257.73  4995.2  254.12  5004.5  254.62  5009.1  255.67  5015.3  259.05
  5023.9  258.67    5030  260.57  5038.6  260.39  5080.3  263.73  5088.9  263.25
  5095.1  264.25  5109.8  262.56  5145.4  262.26  5267.5   264.2  5403.2  264.76
    5424  265.57  5445.8  264.89  5516.1  266.64  5599.7  266.38  5661.1  267.45
#Mann= 7 ,-1 , 0
  4424.2     .11       0  4649.8     .15       0  4809.4     .17       0
  4911.6     .15       0  4959.5     .06       0    5030     .15       0
  5267.5     .17       0
#XS Ineff= 2 , 0
       0                  5080.3       0  263.73
Permanent Ineff=
       F       F
Bank Sta=4959.5,5030
XS Rating Curve= 0 ,0
Exp/Cntr=0.3,0.1

Chan Stop Cuts=-1
Use User Specified Reach Order=0
Composite Channel Slope=5