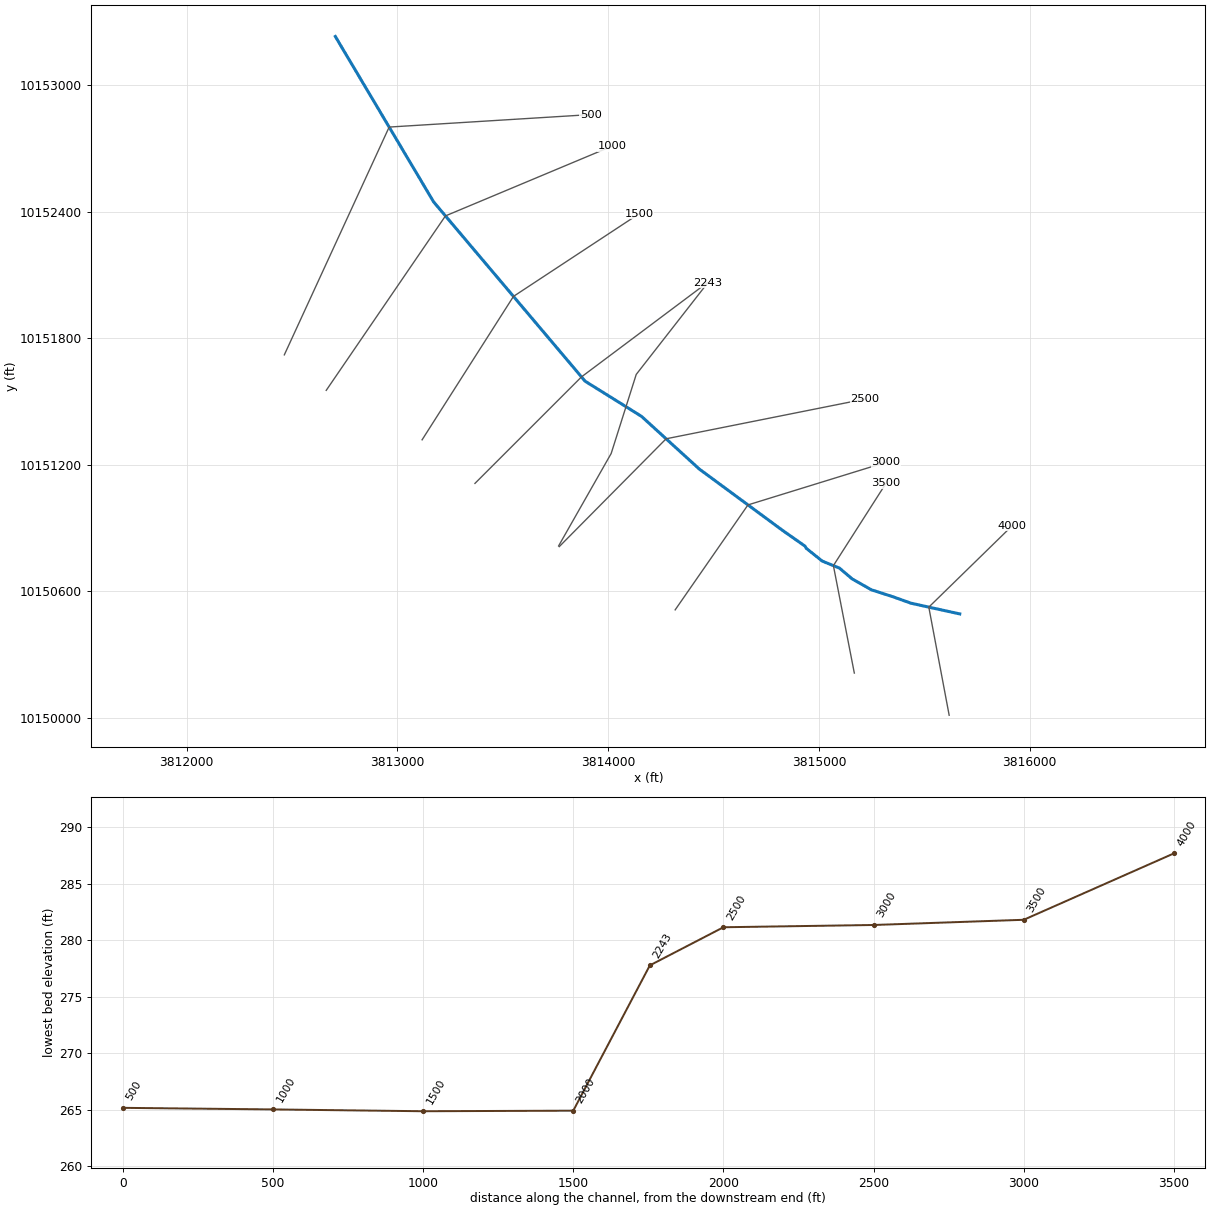
--- Conroe Lake 026.prj (project) ---

Proj Title=Conroe Lake 026 Base Level Engineering
Current Plan=p01
Default Exp/Contr=0.3,0.1
English Units
Geom File=g01
Flow File=f01
Flow File=f02
Plan File=p01
Y Axis Title=Elevation
X Axis Title(PF)=Main Channel Distance
X Axis Title(XS)=Station
BEGIN DESCRIPTION:
Conroe Lake 026
END DESCRIPTION:
DSS File=dss
DSS Export Rating Curves= 0
DSS Export Rating Curve Sorted= 0
DSS Export Volume Flow Curves= 0
DXF OffsetX= 0
DXF OffsetY= 0
DXF ScaleX= 1
DXF ScaleY= 10

--- Conroe Lake 026.p01 (plan) ---

Plan Title=Multiple Run
Program Version=4.10
Short Identifier=Multiple Run
Geom File=g01
Flow File=f01
Subcritical Flow
K Sum by GR= 0
Std Step Tol= 0.01
Critical Tol= 0.01
Num of Std Step Trials= 20
Max Error Tol= 0.3
Flow Tol Ratio= 0.001
Split Flow NTrial= 30
Split Flow Tol= 0.02
Split Flow Ratio= 0.02
Log Output Level= 0
Friction Slope Method= 1
Unsteady Friction Slope Method= 2
Unsteady Bridges Friction Slope Method= 1
Parabolic Critical Depth
Global Vel Dist= 1 , 1 , 1
Global Log Level= 0
CheckData=True
Encroach Param=-1 ,0,0, 0
BEGIN DESCRIPTION:
Multiple Run
END DESCRIPTION:
Computation Interval=1HOUR
Output Interval=1HOUR
Run HTab= 0
Run UNet= 0
Run PostProcess= 0
Run WQNet= 0
UNET Theta= 1
UNET Theta Warmup= 1
UNET ZTol= 0.02
UNET ZSATol= 0.05
UNET MxIter= 20
UNET MaxInSteps= 0
UNET DtIC= 0
UNET DtMin= 0
UNET MaxCRTS= 20
UNET WFStab= 2
UNET SFStab= 1
UNET WFX= 1
UNET SFX= 1
UNET DSS MLevel= 4
UNET DZMax Abort= 100
UNET Convert EG Bridges= 0
UNET Use Existing IB Tables=-1
UNET Froude Reduction=False
UNET Froude Limit= 1
UNET Froude Power= 10
UNET Time Slicing=0,0, 5
UNET Junction Losses=0
Instantaneous Interval=1HOUR
DSS File=dss
Write IC File= 0
Write IC File at Sim End=0
Echo Input=False
Echo Parameters=False
Echo Output=False
Write Detailed= 0
WQ AD Non Conservative
WQ ULTIMATE=-1
WQ Max Comp Step=1HOUR
WQ Output Interval=15MIN
WQ Output Selected Increments= 0
WQ Output face flow=0
WQ Output face velocity=0
WQ Output face area=0
WQ Output face dispersion=0
WQ Output cell volume=0
WQ Output cell surface area=0
WQ Output cell continuity=0
WQ Output cumulative cell continuity=0
WQ Output face conc=0
WQ Output face dconc_dx=0
WQ Output face courant=0
WQ Output face peclet=0
WQ Output face adv mass=0
WQ Output face disp mass=0
WQ Output cell mass=0
WQ Output cell source sink temp=0
WQ Output cell source sink nsm=0
WQ Output MaxMinRange=-1
WQ Daily Max Min Mean=-1
WQ Daily Range=0
WQ Daily Time=0
WQ Create Restart=0
WQ Fixed Restart=0
WQ System Summary=0
WQ Use Fixed Temperature=0
Sorting and Armoring Iterations= 10
XS Update Threshold= 0.02
Hydraulics Update Threshold= 0.02
Energy Slope Method= 1
Volume Change Method= 0
XS Weighting Method= 0
Number of US Weighted Cross Sections= 1
Number of DS Weighted Cross Sections= 1
Upstream XS Weight=0.25
Main XS Weight=0.5
Downstream XS Weight=0.25
Number of DS XS's Weighted with US Boundary= 1
Upstream Boundary Weight= 1
Weight of XSs Associated with US Boundary= 0
Number of US XS's Weighted with DS Boundary= 1
Downstream Boundary Weight= 0.5
Weight of XSs Associated with DS Boundary= 0.5
Sediment Output Level= 4
Mass or Volume Output= 0
Output Increment Type= 1
Profile and TS Output Increment= 10
XS Output Flag= 0
XS Output Increment= 10
Disregard all LS=0
Disregard all Conn=0
Disregard all Breaches=0
Disregard all Pumps=0

--- Conroe Lake 026.f01 (steady flow) ---

Flow Title=Multiple
Program Version=4.10
Number of Profiles= 7
Profile Names=10-year,25-year,50-year,1pct_min,100-year,1pct_plu,500-year
River Rch & RM=Conroe Lake 026,Reach-1         ,4000
     383     507     675     297     898    2712    1639
River Rch & RM=Conroe Lake 026,Reach-1         ,3500
     576     776    1045     465    1403    4237    2608
Boundary for River Rch & Prof#=Conroe Lake 026,Reach-1         , 1
Up Type= 0
Dn Type= 3
Dn Slope=0.005
Boundary for River Rch & Prof#=Conroe Lake 026,Reach-1         , 2
Up Type= 0
Dn Type= 3
Dn Slope=0.005
Boundary for River Rch & Prof#=Conroe Lake 026,Reach-1         , 3
Up Type= 0
Dn Type= 3
Dn Slope=0.005
Boundary for River Rch & Prof#=Conroe Lake 026,Reach-1         , 4
Up Type= 0
Dn Type= 3
Dn Slope=0.005
Boundary for River Rch & Prof#=Conroe Lake 026,Reach-1         , 5
Up Type= 0
Dn Type= 3
Dn Slope=0.005
Boundary for River Rch & Prof#=Conroe Lake 026,Reach-1         , 6
Up Type= 0
Dn Type= 3
Dn Slope=0.005
Boundary for River Rch & Prof#=Conroe Lake 026,Reach-1         , 7
Up Type= 0
Dn Type= 3
Dn Slope=0.005
DSS Import GetInterval= 0
DSS Import GetPeak= 0
DSS Import FillOption= 0

--- Conroe Lake 026.f02 (steady flow) ---

Flow Title=Orig_BLE_Flow
Program Version=4.10
Number of Profiles= 7
Profile Names=10-year,25-year,50-year,1pct_min,100-year,1pct_plu,500-year
River Rch & RM=Conroe Lake 026,Reach-1         ,4000
     383     497     587     229     691    2088     953
River Rch & RM=Conroe Lake 026,Reach-1         ,3500
     576     761     909     357    1079    3259    1516
Boundary for River Rch & Prof#=Conroe Lake 026,Reach-1         , 1
Up Type= 0
Dn Type= 3
Dn Slope=0.005
Boundary for River Rch & Prof#=Conroe Lake 026,Reach-1         , 2
Up Type= 0
Dn Type= 3
Dn Slope=0.005
Boundary for River Rch & Prof#=Conroe Lake 026,Reach-1         , 3
Up Type= 0
Dn Type= 3
Dn Slope=0.005
Boundary for River Rch & Prof#=Conroe Lake 026,Reach-1         , 4
Up Type= 0
Dn Type= 3
Dn Slope=0.005
Boundary for River Rch & Prof#=Conroe Lake 026,Reach-1         , 5
Up Type= 0
Dn Type= 3
Dn Slope=0.005
Boundary for River Rch & Prof#=Conroe Lake 026,Reach-1         , 6
Up Type= 0
Dn Type= 3
Dn Slope=0.005
Boundary for River Rch & Prof#=Conroe Lake 026,Reach-1         , 7
Up Type= 0
Dn Type= 3
Dn Slope=0.005
DSS Import GetInterval= 0
DSS Import GetPeak= 0
DSS Import FillOption= 0

--- Conroe Lake 026.g01 (geometry) ---

Geom Title=Existing Conditions
Program Version=4.10

River Reach=Conroe Lake 026 ,Reach-1
Reach XY= 16
      3815668.38     10150491.72      3815517.75      10150524.7
      3815436.07     10150542.86      3815351.36     10150573.11
       3815248.5     10150606.39      3815157.74     10150657.82
      3815097.24     10150709.24      3815015.56     10150742.52
      3814939.92     10150803.03      3814933.72     10150813.47
       3814828.1     10150887.56      3814432.27     10151179.22
      3814157.96     10151429.22       3813890.6     10151595.89
      3813171.85     10152446.58      3812705.37     10153231.61

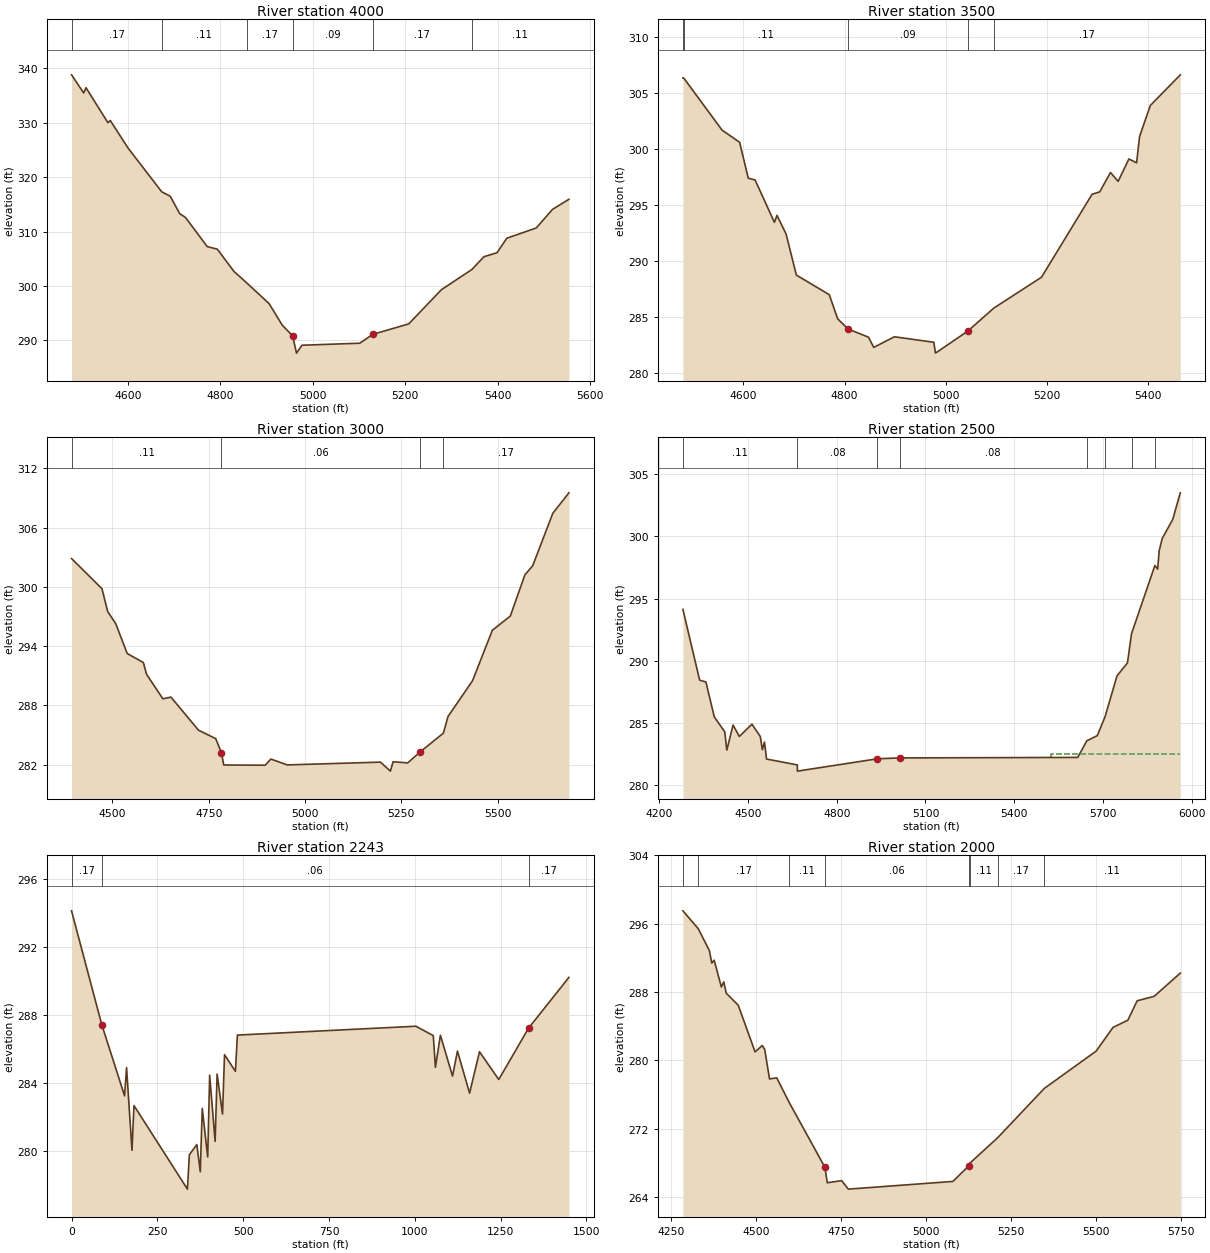
Type RM Length L Ch R = 1 ,4000    ,500,500,500
BEGIN DESCRIPTION:
Conroe Lake 026 8.0
END DESCRIPTION:
XS GIS Cut Line= 3
      3815617.86     10150011.05      3815521.28     10150523.93
      3815917.84     10150911.06
#Sta/Elev= 30
  4478.1  338.77  4504.4  335.44  4509.4   336.4  4556.8  329.99  4561.9  330.39
  4600.2  325.35  4673.2   317.3  4691.8  316.47  4712.2  313.27  4724.4  312.61
  4771.7  307.24  4793.6  306.76  4829.3   302.7  4857.3  300.56  4905.5  296.77
  4934.2  292.79  4956.4  290.86  4964.8  287.68  4976.7  289.13  5101.7   289.5
  5129.9  291.13  5207.7  293.05  5278.4  299.33  5343.9  303.01  5370.4  305.38
  5398.7  306.12  5419.8  308.77  5483.6  310.66  5518.8  314.08  5554.2  315.92
#Mann= 6 ,-1 , 0
  4478.1     .17       0  4673.2     .11       0  4857.3     .17       0
  4956.4     .09       0  5129.9     .17       0  5343.9     .11       0
Bank Sta=4956.4,5129.9
XS Rating Curve= 0 ,0
Exp/Cntr=0.3,0.1

Type RM Length L Ch R = 1 ,3500    ,500,500,500
BEGIN DESCRIPTION:
Conroe Lake 026 7.0
END DESCRIPTION:
XS GIS Cut Line= 3
      3815167.85     10150211.09      3815068.59     10150720.92
      3815317.86     10151111.09
#Sta/Elev= 30
  4480.6  306.38  4482.2  306.38    4558  301.72  4592.6  300.64  4609.7  297.43
  4623.2  297.27  4661.3  293.49  4666.4  294.11  4684.3  292.46  4704.7  288.78
  4769.7  287.03  4786.2  284.88  4806.6  283.97  4847.3  283.23  4857.5  282.32
  4898.3  283.27  4976.2  282.78  4979.5  281.81  5043.4  283.78    5095  285.84
  5188.9  288.59  5288.7  295.99  5303.9  296.21  5325.1  297.94  5340.3  297.15
  5361.5  299.15  5376.7   298.8  5382.6  301.16  5403.8  303.92    5463  306.66
#Mann= 5 ,-1 , 0
  4480.6     .17       0  4482.2     .11       0  4806.6     .09       0
  5043.4     .17       0    5095     .17       0
Bank Sta=4806.6,5043.4
XS Rating Curve= 0 ,0
Exp/Cntr=0.3,0.1

Type RM Length L Ch R = 1 ,3000    ,500,500,500
BEGIN DESCRIPTION:
Conroe Lake 026 6.0
END DESCRIPTION:
XS GIS Cut Line= 3
      3814317.86     10150511.08      3814663.29       10151009.
      3815317.81     10151211.06
#Sta/Elev= 30
    4394  302.86    4473  299.81  4487.9  297.49  4508.8  296.27  4538.5  293.25
  4580.4  292.34  4588.7  291.15  4631.1  288.67    4652  288.84  4723.6  285.49
  4768.2  284.64    4783  283.22  4789.1  281.97  4896.5  281.95  4911.4  282.57
  4953.8  281.98  5195.9  282.26  5221.6  281.35  5228.6   282.3  5266.5  282.18
  5299.1   283.3  5359.1  285.19  5371.1  286.87  5434.9   290.5  5486.2   295.6
  5532.9  297.04  5570.8  301.22  5590.9  302.12  5643.2  307.44    5685  309.51
#Mann= 4 ,-1 , 0
    4394     .11       0    4783     .06       0  5299.1     .11       0
  5359.1     .17       0
Bank Sta=4783,5299.1
XS Rating Curve= 0 ,0
Exp/Cntr=0.3,0.1

Type RM Length L Ch R = 1 ,2500    ,245,245,245
BEGIN DESCRIPTION:
Conroe Lake 026 5.0
END DESCRIPTION:
XS GIS Cut Line= 3
      3813767.84     10150811.06      3814274.81     10151322.72
      3815217.89     10151511.08
#Sta/Elev= 30
  4279.7  294.13  4336.3  288.45  4357.5   288.3  4385.8   285.5  4421.1  284.31
  4428.2  282.84  4449.4  284.85  4470.6  283.93  4513.1  284.92  4541.4  283.93
  4548.4  282.87  4555.5  283.48  4562.5  282.12  4666.6  281.65  4666.9  281.15
  4937.4  282.14  5012.6  282.21  5614.9  282.25  5645.5  283.58    5681     284
  5707.4  285.52  5747.5  288.78  5783.1  289.84  5796.7  292.17  5875.8  297.65
  5885.1  297.36  5890.3  298.83  5900.5  299.81  5936.2  301.35  5961.7  303.48
#Mann= 8 ,-1 , 0
  4279.7     .11       0  4666.6     .08       0  4937.4     .06       0
  5012.6     .08       0  5645.5     .11       0  5707.4     .17       0
  5796.7     .11       0  5875.8     .17       0
#XS Ineff= 2 , 0
       0                  5522.9       0  282.52
Permanent Ineff=
       F       F
Bank Sta=4937.4,5012.6
XS Rating Curve= 0 ,0
Exp/Cntr=0.3,0.1

Type RM Length L Ch R = 1 ,2243    ,255,255,255
XS GIS Cut Line= 4
      3813764.87     10150814.56      3814014.14     10151252.88
      3814133.06      10151628.1      3814472.18      10152062.5
#Sta/Elev= 30
       0  294.13      88  287.45   154.5  283.26   160.3  284.92   176.1  280.06
   181.9  282.69   337.6  277.78   343.3   279.8     365   280.4   375.1   278.8
   380.8  282.52   396.7  279.67   402.4  284.47   418.3  280.58   424.1  284.54
   439.9  282.19   445.7  285.68   477.4   284.7   483.2  286.83  1003.1  287.35
  1053.8   286.8  1060.1  284.94  1074.6  286.82  1109.9  284.42  1124.3  285.89
  1159.6  283.42  1188.5  285.85  1244.6  284.22  1331.5  287.24    1449  290.22
#Mann= 3 , 0 , 0
       0     .17       0      88     .06       0  1331.5     .17       0
Bank Sta=88,1331.5
XS Rating Curve= 0 ,0
Exp/Cntr=0.3,0.1

Type RM Length L Ch R = 1 ,2000    ,500,500,500
BEGIN DESCRIPTION:
Conroe Lake 026 4.0
END DESCRIPTION:
XS GIS Cut Line= 3
      3813367.86     10151111.08      3813873.28     10151616.39
      3814471.24     10152064.28
#Sta/Elev= 30
  4285.3  297.51  4330.2  295.43  4363.1  292.86  4370.1   291.4  4377.2  291.73
  4398.4  288.59  4405.5  289.19  4412.6  287.87  4447.9  286.46  4497.4     281
  4518.6  281.74  4525.7  281.28  4539.9  277.83  4561.1  277.96  4597.6  275.08
  4702.5   267.5  4709.6  265.68    4752  265.92  4771.4  264.93  5078.7  265.83
 5126.45  267.69  5128.7  267.97  5210.2  270.94  5347.4  276.72  5499.6  281.08
  5549.6  283.87  5592.9   284.7  5620.4  286.98  5670.4   287.5  5747.1  290.22
#Mann= 8 ,-1 , 0
  4285.3     .15       0  4330.2     .17       0  4597.6     .11       0
  4702.5     .06       0 5126.45     .08       0  5128.7     .11       0
  5210.2     .17       0  5347.4     .11       0
Bank Sta=4702.5,5126.45
XS Rating Curve= 0 ,0
Exp/Cntr=0.3,0.1

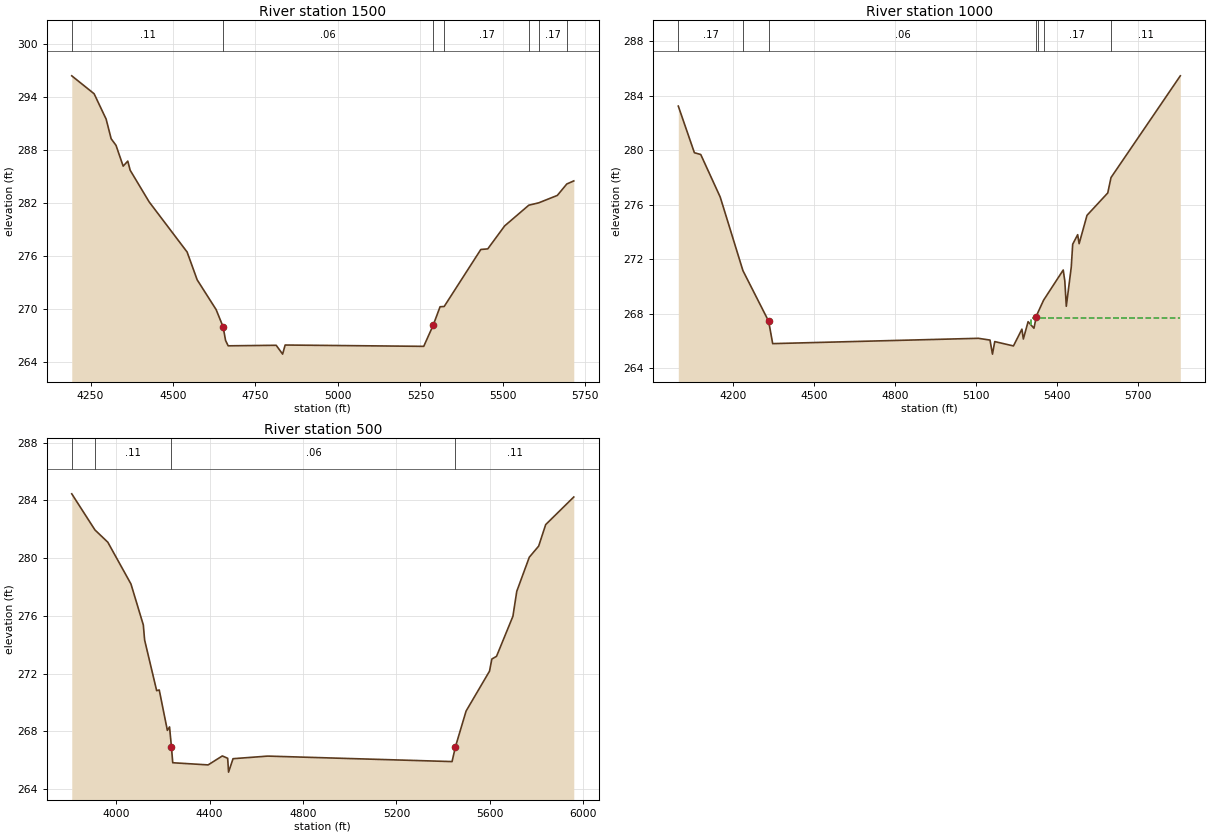
Type RM Length L Ch R = 1 ,1500    ,500,500,500
BEGIN DESCRIPTION:
Conroe Lake 026 3.0
END DESCRIPTION:
XS GIS Cut Line= 3
      3813117.09     10151317.88      3813550.59     10151998.32
      3814147.82     10152391.25
#Sta/Elev= 30
  4193.2  296.37    4261  294.34  4297.4  291.47  4312.6  289.25  4327.4   288.5
    4349  286.15    4363  286.72  4370.2  285.69  4427.7  282.11  4542.9  276.43
  4573.3  273.29  4630.9  269.91    4652  267.96  4659.4  266.43  4667.3  265.82
  4812.9  265.88  4832.3  264.88    4840  265.91  5260.1  265.76  5288.5  268.13
  5309.6  270.24  5322.1  270.27  5433.1  276.72  5454.2  276.79  5505.4  279.39
  5578.5  281.73  5608.7     282  5665.1  282.84  5693.7  284.13  5714.9  284.48
#Mann= 7 ,-1 , 0
  4193.2     .11       0    4652     .06       0  5288.5     .11       0
  5322.1     .17       0  5578.5     .11       0  5608.7     .17       0
  5693.7     .11       0
Bank Sta=4652,5288.5
XS Rating Curve= 0 ,0
Exp/Cntr=0.3,0.1

Type RM Length L Ch R = 1 ,1000    ,500,500,500
BEGIN DESCRIPTION:
Conroe Lake 026 2.0
END DESCRIPTION:
XS GIS Cut Line= 3
      3812662.19     10151552.49      3813227.89     10152380.25
      3814017.82     10152711.06
#Sta/Elev= 30
  3997.4  283.23    4057  279.81  4080.5  279.68  4152.6  276.56  4236.8  271.16
    4332  267.45  4346.9  265.81  5108.4   266.2  5151.7  266.07  5160.8  265.04
  5169.2  265.96  5238.5  265.64  5269.8  266.87  5275.2  266.15  5292.7  267.42
  5314.4  266.94  5322.7  267.74  5328.2  268.05  5349.9  268.99  5422.8  271.21
  5428.7   270.4  5434.2  268.55  5452.5  271.41  5457.9   273.1  5476.3   273.8
  5481.7  273.14  5510.9  275.22  5587.7  276.86  5599.8  277.99  5856.4  285.45
#Mann= 7 ,-1 , 0
  3997.4     .17       0  4236.8     .11       0    4332     .06       0
  5322.7     .08       0  5328.2     .11       0  5349.9     .17       0
  5599.8     .11       0
#XS Ineff= 2 , 0
       0                  5304.4       0  267.71
Permanent Ineff=
       F       F
Bank Sta=4332,5322.7
XS Rating Curve= 0 ,0
Exp/Cntr=0.3,0.1

Type RM Length L Ch R = 1 ,500     ,0,0,0
BEGIN DESCRIPTION:
Conroe Lake 026 1.0
END DESCRIPTION:
XS GIS Cut Line= 3
      3812463.35     10151720.95      3812960.79     10152801.77
      3813917.85     10152861.07
#Sta/Elev= 30
  3810.2  284.45  3909.4  281.95  3964.5   281.1  4063.5  278.21  4116.5  275.37
    4122  274.33  4173.6  270.82  4184.6  270.87  4219.4  268.07  4228.7  268.31
  4236.8  266.93  4242.4  265.83  4393.8  265.68  4454.6   266.3  4477.5  266.14
  4481.3  265.18  4500.5  266.11  4649.3  266.29  5437.9  265.91 5452.64  266.95
    5498  269.41  5598.2  272.17  5608.2  273.01  5628.3   273.2  5698.4  275.97
  5714.9   277.7  5768.5  280.06  5808.6  280.83  5838.7  282.32  5958.9  284.23
#Mann= 4 ,-1 , 0
  3810.2     .17       0  3909.4     .11       0  4236.8     .06       0
 5452.64     .11       0
Bank Sta=4236.8,5452.64
XS Rating Curve= 0 ,0
Exp/Cntr=0.3,0.1

Chan Stop Cuts=-1
Use User Specified Reach Order=0
Composite Channel Slope=5