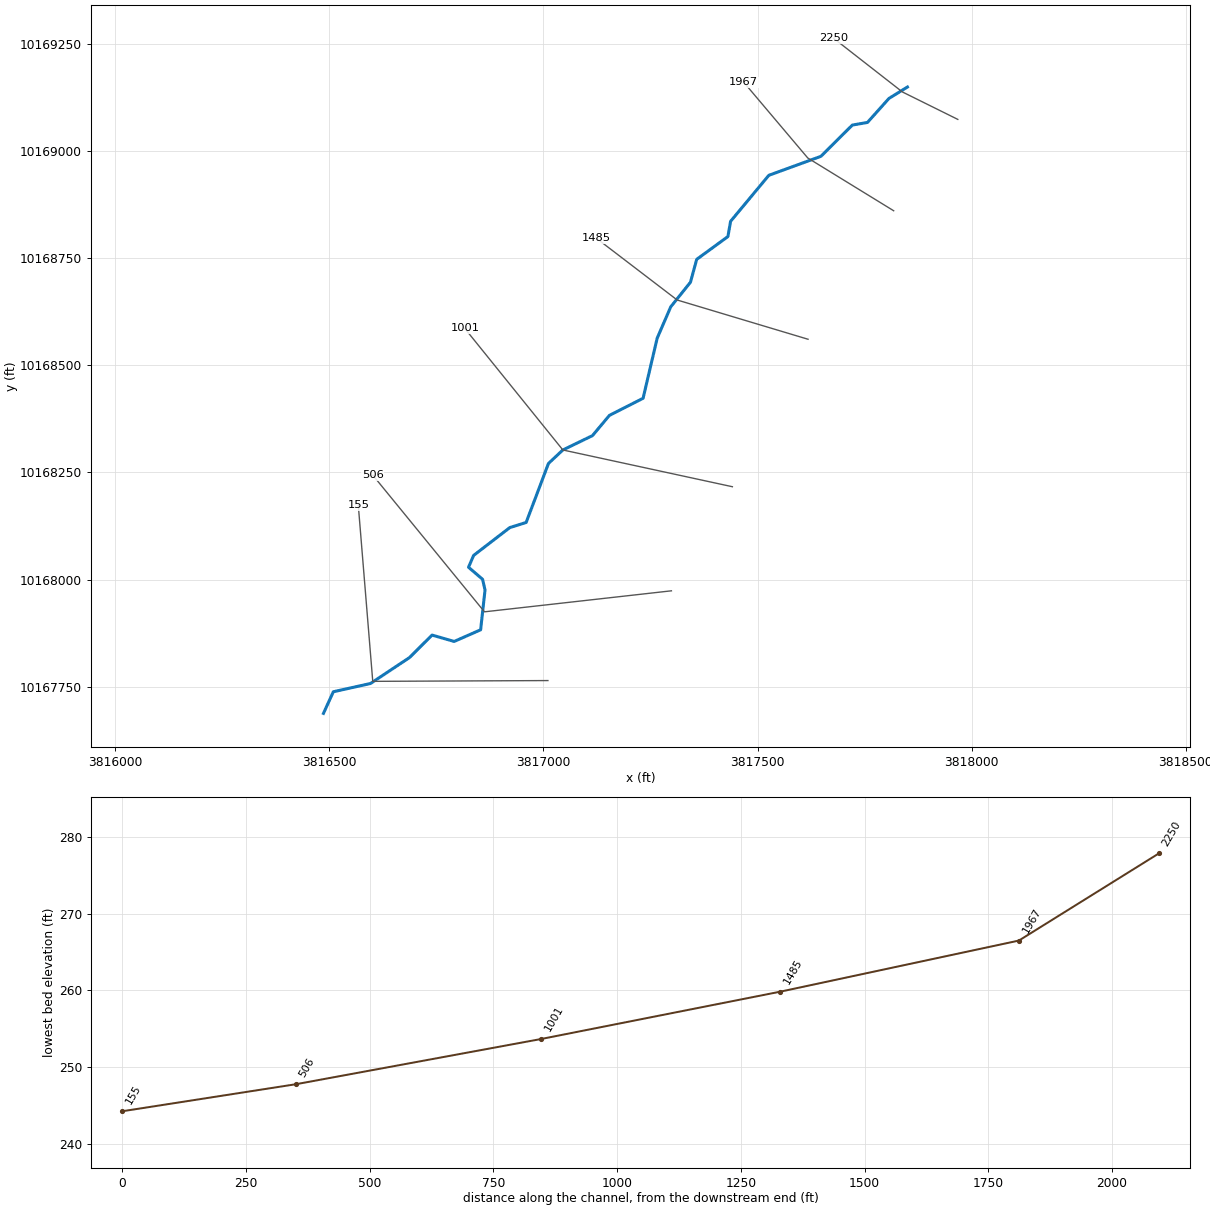
--- Conroe Lake 030.prj (project) ---

Proj Title=Conroe Lake 030 Base Level Engineering
Current Plan=p01
Default Exp/Contr=0.3,0.1
English Units
Geom File=g01
Flow File=f01
Flow File=f02
Plan File=p01
Y Axis Title=Elevation
X Axis Title(PF)=Main Channel Distance
X Axis Title(XS)=Station
BEGIN DESCRIPTION:
Conroe Lake 030
END DESCRIPTION:
DSS Export Rating Curves= 0
DSS Export Rating Curve Sorted= 0
DSS Export Volume Flow Curves= 0
DXF OffsetX= 0
DXF OffsetY= 0
DXF ScaleX= 1
DXF ScaleY= 10

--- Conroe Lake 030.p01 (plan) ---

Plan Title=Multiple Run
Short Identifier=Multiple
Geom File=g01
Flow File=f01
Subcritical Flow
K Sum by GR= 0
Std Step Tol= 0.01
Critical Tol= 0.01
Num of Std Step Trials= 20
Max Error Tol= 0.3
Flow Tol Ratio= 0.001
Split Flow NTrial= 30
Split Flow Tol= 0.02
Split Flow Ratio= 0.02
Log Output Level= 0
Friction Slope Method= 1
Unsteady Friction Slope Method= 2
Unsteady Bridges Friction Slope Method= 1
Parabolic Critical Depth
Global Vel Dist=  1 , 1 , 1
Global Log Level= 0
CheckData=True
Encroach Param= -1, 0, 0, 0
BEGIN DESCRIPTION:
Multiple Run
END DESCRIPTION:

--- Conroe Lake 030.f01 (steady flow) ---

Flow Title=Multiple
Program Version=4.10
Number of Profiles= 7
Profile Names=10-year,25-year,50-year,1pct_min,100-year,1pct_plu,500-year
River Rch & RM=Conroe Lake 030,Reach-1         ,2250
     209     263     340     146     441    1332     757
River Rch & RM=Conroe Lake 030,Reach-1         ,155
     729     999    1363     612    1849    5584    3517
Boundary for River Rch & Prof#=Conroe Lake 030,Reach-1         , 1
Up Type= 0
Dn Type= 3
Dn Slope=0.01
Boundary for River Rch & Prof#=Conroe Lake 030,Reach-1         , 2
Up Type= 0
Dn Type= 3
Dn Slope=0.01
Boundary for River Rch & Prof#=Conroe Lake 030,Reach-1         , 3
Up Type= 0
Dn Type= 3
Dn Slope=0.01
Boundary for River Rch & Prof#=Conroe Lake 030,Reach-1         , 4
Up Type= 0
Dn Type= 3
Dn Slope=0.01
Boundary for River Rch & Prof#=Conroe Lake 030,Reach-1         , 5
Up Type= 0
Dn Type= 3
Dn Slope=0.01
Boundary for River Rch & Prof#=Conroe Lake 030,Reach-1         , 6
Up Type= 0
Dn Type= 3
Dn Slope=0.01
Boundary for River Rch & Prof#=Conroe Lake 030,Reach-1         , 7
Up Type= 0
Dn Type= 3
Dn Slope=0.01
DSS Import GetInterval= 0
DSS Import GetPeak= 0
DSS Import FillOption= 0

--- Conroe Lake 030.f02 (steady flow) ---

Flow Title=Orig_BLE_Flow
Program Version=4.10
Number of Profiles= 7
Profile Names=10-year,25-year,50-year,1pct_min,100-year,1pct_plu,500-year
River Rch & RM=Conroe Lake 030,Reach-1         ,2250
     209     258     296     112     339    1023     440
River Rch & RM=Conroe Lake 030,Reach-1         ,155
     729     979    1185     471    1422    4296    2045
Boundary for River Rch & Prof#=Conroe Lake 030,Reach-1         , 1
Up Type= 0
Dn Type= 3
Dn Slope=0.01
Boundary for River Rch & Prof#=Conroe Lake 030,Reach-1         , 2
Up Type= 0
Dn Type= 3
Dn Slope=0.01
Boundary for River Rch & Prof#=Conroe Lake 030,Reach-1         , 3
Up Type= 0
Dn Type= 3
Dn Slope=0.01
Boundary for River Rch & Prof#=Conroe Lake 030,Reach-1         , 4
Up Type= 0
Dn Type= 3
Dn Slope=0.01
Boundary for River Rch & Prof#=Conroe Lake 030,Reach-1         , 5
Up Type= 0
Dn Type= 3
Dn Slope=0.01
Boundary for River Rch & Prof#=Conroe Lake 030,Reach-1         , 6
Up Type= 0
Dn Type= 3
Dn Slope=0.01
Boundary for River Rch & Prof#=Conroe Lake 030,Reach-1         , 7
Up Type= 0
Dn Type= 3
Dn Slope=0.01
DSS Import GetInterval= 0
DSS Import GetPeak= 0
DSS Import FillOption= 0

--- Conroe Lake 030.g01 (geometry) ---

Geom Title=Existing Conditions
Program Version=4.10

River Reach=Conroe Lake 030 ,Reach-1
Reach XY= 30
      3817849.98     10169150.03      3817806.84     10169123.38
      3817756.68     10169067.37      3817721.27     10169061.13
      3817647.95      10168988.2      3817526.35     10168943.86
      3817437.03     10168836.42      3817430.76     10168800.81
       3817357.9     10168747.61      3817343.31     10168694.18
      3817297.33     10168636.84      3817265.67      10168563.7
      3817232.71     10168423.25      3817153.99     10168383.22
      3817114.55     10168336.04      3817045.39     10168302.53
      3817011.76     10168271.06      3816959.67     10168133.26
      3816921.47     10168121.27      3816837.02     10168056.33
      3816825.11     10168028.66      3816857.97     10168000.55
      3816863.62     10167975.38      3816853.34     10167882.61
      3816791.56     10167855.41      3816739.92     10167870.34
      3816687.57     10167818.01      3816596.17     10167757.22
      3816509.45     10167737.97      3816486.39     10167687.48

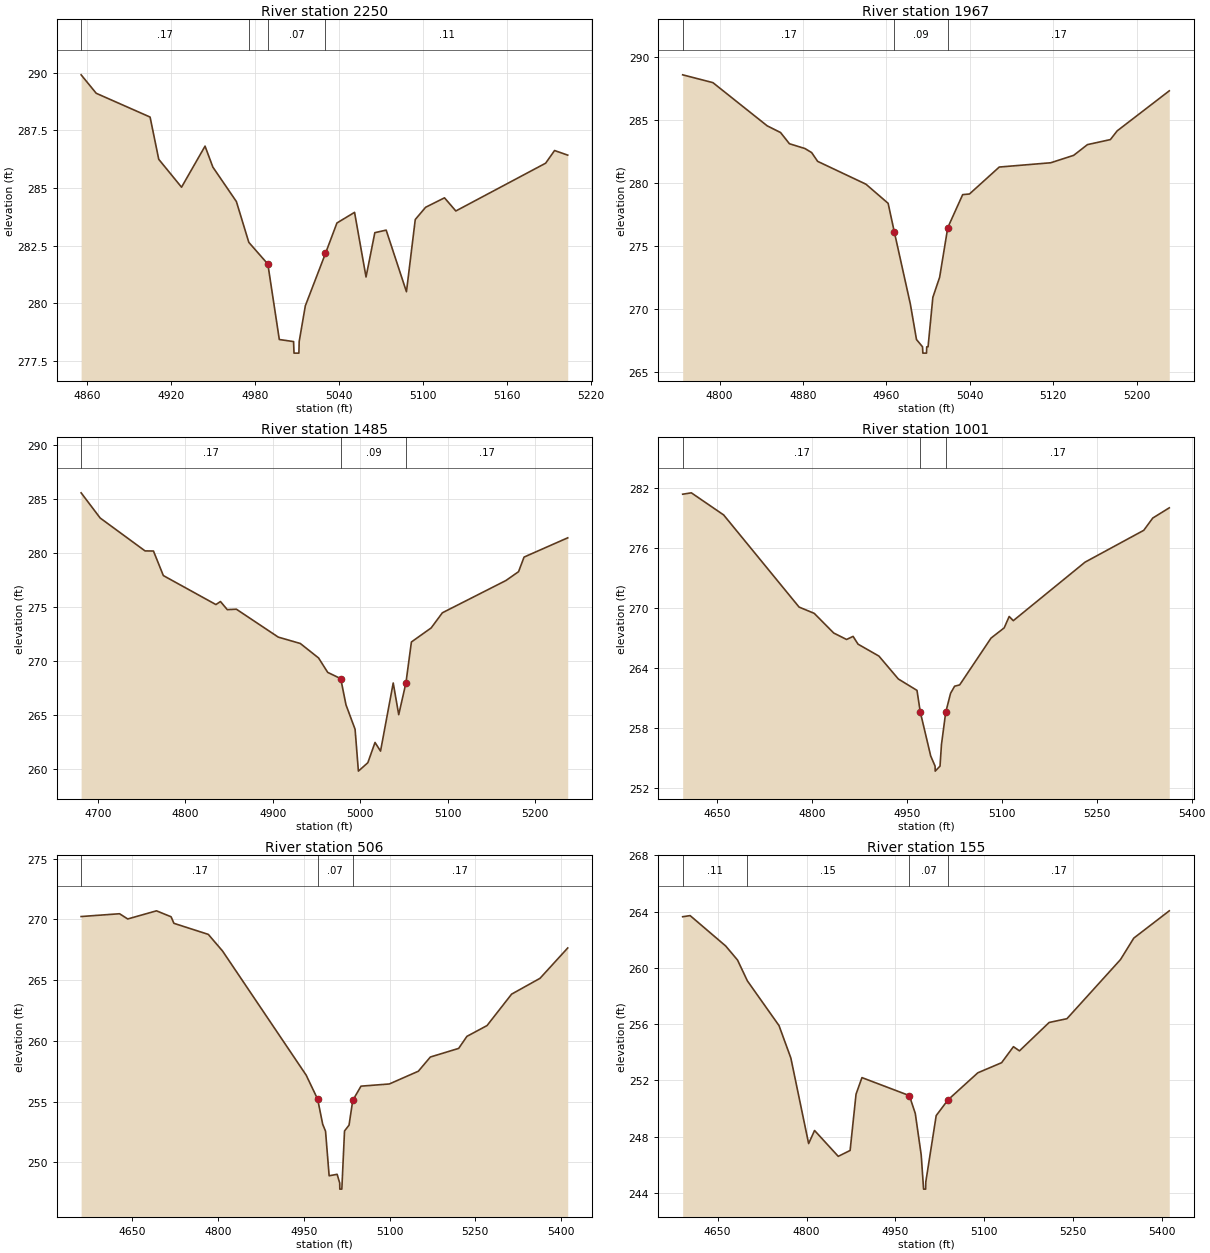
Type RM Length L Ch R = 1 ,2250    ,283,283,283
BEGIN DESCRIPTION:
Conroe Lake 030 4.5
END DESCRIPTION:
XS GIS Cut Line= 3
      3817967.57     10169074.43      3817838.25     10169138.46
      3817677.73      10169263.7
#Sta/Elev= 30
  4855.7   289.9  4866.5   289.1    4905  288.07  4911.2  286.24  4927.5  285.03
  4944.3  286.81  4949.9   285.9  4966.7  284.41  4975.6  282.64  4989.2   281.7
  4997.4  278.43  5007.6  278.34  5007.9  277.84  5011.4  277.84  5011.6  278.34
    5016  279.89  5030.4  282.16  5038.6  283.48  5051.2  283.94  5059.4  281.14
  5065.7  283.06  5073.8  283.17  5088.3   280.5  5094.6  283.63    5102  284.16
  5115.5  284.57  5123.6     284  5187.8  286.07  5194.2  286.62  5203.6  286.42
#Mann= 4 ,-1 , 0
  4855.7     .17       0  4975.6     .11       0  4989.2     .07       0
  5030.4     .11       0
#XS Ineff= 2 , 0
       0                  5051.2       0  283.94
Permanent Ineff=
       F       F
Bank Sta=4989.2,5030.4
XS Rating Curve= 0 ,0
Exp/Cntr=0.3,0.1

Type RM Length L Ch R = 1 ,1967    ,482,482,482
BEGIN DESCRIPTION:
Conroe Lake 030 4.0
END DESCRIPTION:
XS GIS Cut Line= 3
      3817817.83     10168861.09      3817617.25      10168984.3
      3817467.88     10169161.03
#Sta/Elev= 30
  4764.6  288.58  4793.6  287.96  4845.7  284.53  4858.5     284    4867  283.11
  4881.9  282.73  4888.3  282.41  4894.1  281.71  4940.4   279.9  4961.7  278.38
  4967.6  276.12    4983  270.39  4988.9  267.57  4994.7  266.99    4995  266.49
  4998.5  266.49  4998.7  266.99    5000  266.99  5004.6  270.92  5011.1  272.51
  5018.9  276.45  5033.2  279.07  5039.7  279.12  5068.3  281.26  5117.7   281.6
  5139.7  282.19  5152.9  283.04  5174.9  283.44  5181.4  284.13  5231.4  287.31
#Mann= 3 , 0 , 0
  4764.6     .17       0  4967.6     .09       0  5018.9     .17       0
Bank Sta=4967.6,5018.9
XS Rating Curve= 0 ,0
Exp/Cntr=0.3,0.1

Type RM Length L Ch R = 1 ,1485    ,484,484,484
BEGIN DESCRIPTION:
Conroe Lake 030 3.0
END DESCRIPTION:
XS GIS Cut Line= 3
      3817617.89     10168561.06      3817312.34     10168652.68
      3817123.79     10168796.78
#Sta/Elev= 30
    4681  285.57  4702.8  283.24  4754.1   280.2  4763.7  280.19    4775  277.92
  4835.1  275.24  4840.3  275.52  4848.1  274.77  4858.5  274.81  4906.4  272.23
  4931.6  271.64  4952.5   270.3  4962.9  268.97  4977.8  268.39  4983.8  265.97
  4994.2  263.71    4998  259.84  5008.8  260.62    5017  262.49  5023.3  261.69
  5037.8  267.99  5044.1  265.06  5052.3  267.98  5058.6  271.78  5081.2  273.08
    5094  274.48  5166.6  277.46  5181.1  278.28  5187.4  279.63  5237.3  281.41
#Mann= 3 , 0 , 0
    4681     .17       0  4977.8     .09       0  5052.3     .17       0
Bank Sta=4977.8,5052.3
XS Rating Curve= 0 ,0
Exp/Cntr=0.3,0.1

Type RM Length L Ch R = 1 ,1001    ,495,495,495
BEGIN DESCRIPTION:
Conroe Lake 030 2.0
END DESCRIPTION:
XS GIS Cut Line= 3
       3817441.2     10168216.72      3817045.39     10168302.53
      3816816.42     10168586.26
#Sta/Elev= 30
    4595  281.35  4608.7  281.49  4659.8  279.28  4779.1  270.07  4803.1  269.44
  4833.8  267.48  4854.2  266.83  4864.5  267.14  4872.4  266.36  4905.4  265.17
  4936.1  262.88  4965.6  261.74  4970.7  259.61  4987.3  255.18  4994.2  254.17
  4994.4  253.67    5002  254.17  5004.3  256.33    5011  259.54  5018.7  261.45
  5025.1  262.16  5033.1  262.29  5082.7  266.97  5103.5  267.99  5111.4  269.13
  5117.9  268.71  5231.4  274.56  5324.2  277.74  5338.5  278.97  5364.6  279.99
#Mann= 3 , 0 , 0
    4595     .17       0  4970.7     .09       0    5011     .17       0
Bank Sta=4970.7,5011
XS Rating Curve= 0 ,0
Exp/Cntr=0.3,0.1

Type RM Length L Ch R = 1 ,506     ,351,351,351
BEGIN DESCRIPTION:
Conroe Lake 030 1.0
END DESCRIPTION:
XS GIS Cut Line= 3
      3817298.87     10167973.66      3816862.31      10167924.6
      3816601.89     10168243.34
#Sta/Elev= 30
  4560.7  270.24  4627.9  270.47  4642.2  270.04  4692.5  270.71    4718  270.22
    4723  269.68  4783.1  268.77    4808   267.4  4954.2  257.18  4974.3   255.2
  4983.1  253.14  4988.1  252.56  4994.4  248.89  5008.4  249.01  5012.9  248.29
  5013.1  247.79  5016.6  247.79  5021.3  252.58  5029.2  253.06  5035.7   255.1
  5050.1  256.27  5099.6  256.45  5150.4   257.5  5171.4  258.67  5220.9  259.38
  5235.3  260.37  5270.5  261.26  5313.5  263.85  5363.1  265.15  5411.6  267.65
#Mann= 3 , 0 , 0
  4560.7     .17       0  4974.3     .07       0  5035.7     .17       0
Bank Sta=4974.3,5035.7
XS Rating Curve= 0 ,0
Exp/Cntr=0.3,0.1

Type RM Length L Ch R = 1 ,155     ,0,0,0
BEGIN DESCRIPTION:
Conroe Lake 030 1.5
END DESCRIPTION:
XS GIS Cut Line= 3
      3817010.48      10167764.1      3816601.48     10167762.25
      3816567.74     10168173.17
#Sta/Elev= 30
    4591  263.64  4603.6  263.72  4663.6  261.56  4683.6  260.56  4700.2  259.08
  4753.6   255.9  4773.6  253.59  4803.6  247.51  4813.6  248.44  4853.6   246.6
  4873.6  247.02  4883.6  251.02  4893.6   252.2  4973.6  250.92  4983.6  249.65
  4993.6   246.7  4997.6  244.27  5001.1  244.27  5001.3  244.77  5018.9   249.5
  5038.9  250.62  5089.1  252.54  5129.3  253.26  5149.3   254.4  5159.4   254.1
  5209.5  256.12  5239.6  256.39  5329.9  260.59  5352.4  262.12  5412.3  264.06
#Mann= 4 ,-1 , 0
    4591     .11       0  4700.2     .15       0  4973.6     .07       0
  5038.9     .17       0
Bank Sta=4973.6,5038.9
XS Rating Curve= 0 ,0
Exp/Cntr=0.3,0.1

Chan Stop Cuts=-1
Use User Specified Reach Order=0
Composite Channel Slope=5