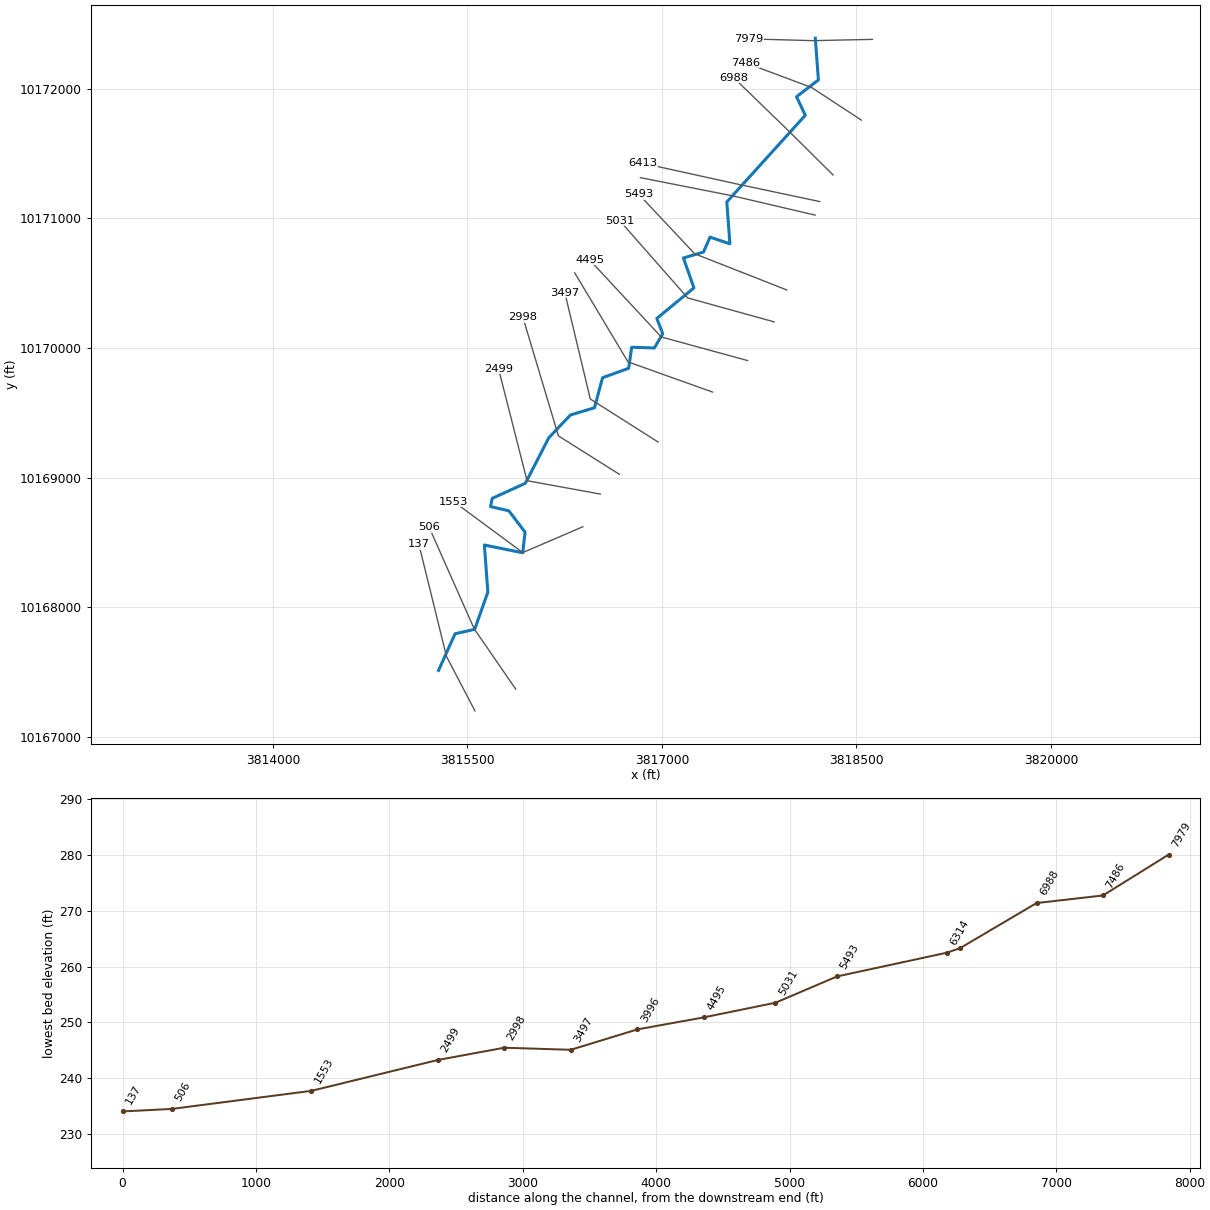
--- Conroe Lake 032.prj (project) ---

Proj Title=Conroe Lake 032 Base Level Engineering
Current Plan=p01
Default Exp/Contr=0.3,0.1
English Units
Geom File=g01
Flow File=f01
Flow File=f02
Plan File=p01
Y Axis Title=Elevation
X Axis Title(PF)=Main Channel Distance
X Axis Title(XS)=Station
BEGIN DESCRIPTION:
Conroe Lake 032
END DESCRIPTION:
DSS Export Rating Curves= 0
DSS Export Rating Curve Sorted= 0
DSS Export Volume Flow Curves= 0
DXF OffsetX= 0
DXF OffsetY= 0
DXF ScaleX= 1
DXF ScaleY= 10

--- Conroe Lake 032.p01 (plan) ---

Plan Title=Multiple Run
Short Identifier=Multiple
Geom File=g01
Flow File=f01
Subcritical Flow
K Sum by GR= 0
Std Step Tol= 0.01
Critical Tol= 0.01
Num of Std Step Trials= 20
Max Error Tol= 0.3
Flow Tol Ratio= 0.001
Split Flow NTrial= 30
Split Flow Tol= 0.02
Split Flow Ratio= 0.02
Log Output Level= 0
Friction Slope Method= 1
Unsteady Friction Slope Method= 2
Unsteady Bridges Friction Slope Method= 1
Parabolic Critical Depth
Global Vel Dist=  1 , 1 , 1
Global Log Level= 0
CheckData=True
Encroach Param= -1, 0, 0, 0
BEGIN DESCRIPTION:
Multiple Run
END DESCRIPTION:

--- Conroe Lake 032.f01 (steady flow) ---

Flow Title=Multiple
Program Version=4.10
Number of Profiles= 7
Profile Names=10-year,25-year,50-year,1pct_min,100-year,1pct_plu,500-year
River Rch & RM=Conroe Lake 032,Reach-1         ,7979
     583     779    1045     462    1394    4210    2556
River Rch & RM=Conroe Lake 032,Reach-1         ,506
     748    1021    1389     622    1879    5674    3545
River Rch & RM=Conroe Lake 032,Reach-1         ,137
     748    1021    1389     622    1879    5674    3545
Boundary for River Rch & Prof#=Conroe Lake 032,Reach-1         , 1
Up Type= 0
Dn Type= 3
Dn Slope=0.005
Boundary for River Rch & Prof#=Conroe Lake 032,Reach-1         , 2
Up Type= 0
Dn Type= 3
Dn Slope=0.005
Boundary for River Rch & Prof#=Conroe Lake 032,Reach-1         , 3
Up Type= 0
Dn Type= 3
Dn Slope=0.005
Boundary for River Rch & Prof#=Conroe Lake 032,Reach-1         , 4
Up Type= 0
Dn Type= 3
Dn Slope=0.005
Boundary for River Rch & Prof#=Conroe Lake 032,Reach-1         , 5
Up Type= 0
Dn Type= 3
Dn Slope=0.005
Boundary for River Rch & Prof#=Conroe Lake 032,Reach-1         , 6
Up Type= 0
Dn Type= 3
Dn Slope=0.005
Boundary for River Rch & Prof#=Conroe Lake 032,Reach-1         , 7
Up Type= 0
Dn Type= 3
Dn Slope=0.005
DSS Import GetInterval= 0
DSS Import GetPeak= 0
DSS Import FillOption= 0

--- Conroe Lake 032.f02 (steady flow) ---

Flow Title=Orig_BLE_Flow
Program Version=4.10
Number of Profiles= 7
Profile Names=10-year,25-year,50-year,1pct_min,100-year,1pct_plu,500-year
River Rch & RM=Conroe Lake 032,Reach-1         ,7979
     583     764     909     355    1072    3237    1486
River Rch & RM=Conroe Lake 032,Reach-1         ,506
     748    1001    1208     478    1445    4363    2061
Boundary for River Rch & Prof#=Conroe Lake 032,Reach-1         , 1
Up Type= 0
Dn Type= 3
Dn Slope=0.005
Boundary for River Rch & Prof#=Conroe Lake 032,Reach-1         , 2
Up Type= 0
Dn Type= 3
Dn Slope=0.005
Boundary for River Rch & Prof#=Conroe Lake 032,Reach-1         , 3
Up Type= 0
Dn Type= 3
Dn Slope=0.005
Boundary for River Rch & Prof#=Conroe Lake 032,Reach-1         , 4
Up Type= 0
Dn Type= 3
Dn Slope=0.005
Boundary for River Rch & Prof#=Conroe Lake 032,Reach-1         , 5
Up Type= 0
Dn Type= 3
Dn Slope=0.005
Boundary for River Rch & Prof#=Conroe Lake 032,Reach-1         , 6
Up Type= 0
Dn Type= 3
Dn Slope=0.005
Boundary for River Rch & Prof#=Conroe Lake 032,Reach-1         , 7
Up Type= 0
Dn Type= 3
Dn Slope=0.005
DSS Import GetInterval= 0
DSS Import GetPeak= 0
DSS Import FillOption= 0

--- Conroe Lake 032.g01 (geometry) ---

Geom Title=Existing Conditions
Program Version=4.10

River Reach=Conroe Lake 032 ,Reach-1
Reach XY= 30
      3818183.23     10172391.84      3818207.23     10172069.61
      3818038.48     10171940.03      3818106.08     10171796.84
      3817500.85      10171127.7       3817524.7     10170804.67
      3817371.51     10170856.12      3817321.06     10170740.91
      3817166.31     10170695.26      3817247.55     10170464.51
      3816961.33      10170228.4      3817006.86     10170110.14
      3816941.98     10170000.53      3816767.29     10170005.96
      3816744.29     10169844.05      3816542.57     10169770.41
      3816480.65     10169539.07      3816295.02     10169482.78
      3816128.61     10169307.71      3815948.05     10168956.36
      3815691.99     10168839.15      3815678.83     10168775.68
      3815820.34     10168743.35      3815945.18     10168578.45
      3815926.98     10168419.09      3815631.62     10168479.19
      3815658.31     10168115.86      3815556.69      10167828.2
      3815405.43     10167793.97      3815278.14     10167511.63

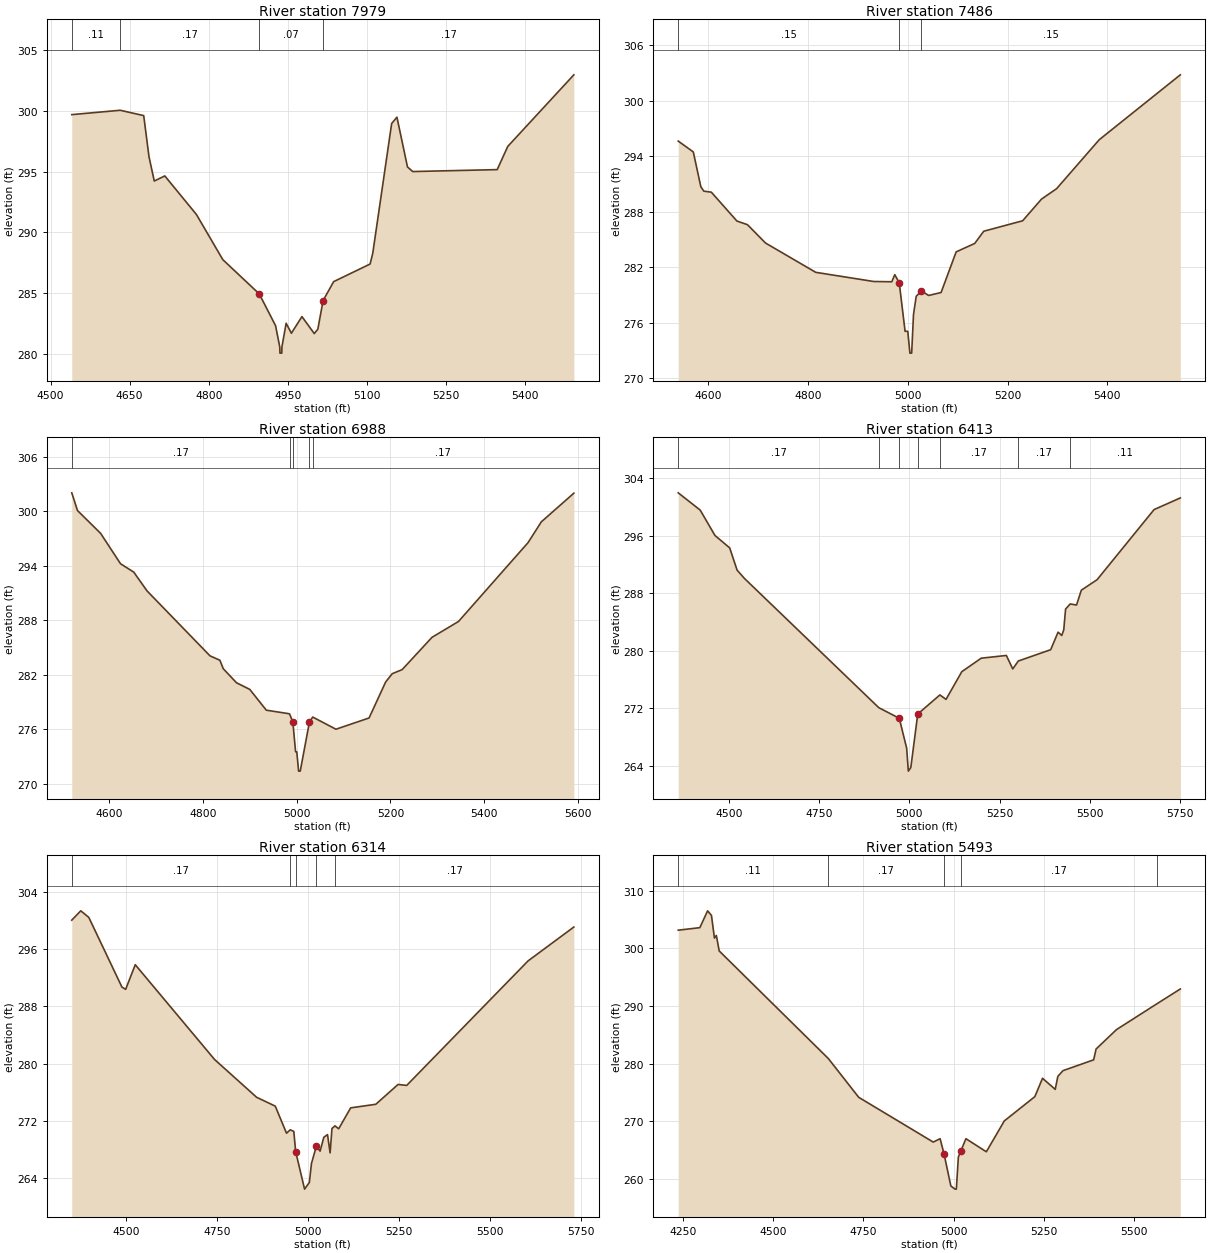
Type RM Length L Ch R = 1 ,7979    ,493,493,493
BEGIN DESCRIPTION:
Conroe Lake 032 13.0
END DESCRIPTION:
XS GIS Cut Line= 3
       3818624.2     10172382.99       3818164.5     10172373.01
       3817672.6     10172386.72
#Sta/Elev= 30
  4540.2  299.71    4632  300.07  4676.6  299.63  4686.6  296.25  4696.6  294.24
  4716.6  294.66  4776.6  291.48  4826.6  287.76 4895.68  284.94  4926.6  282.32
  4934.6  280.56  4934.9  280.06  4938.4  280.06  4938.6  280.56  4946.6  282.52
  4956.6   281.7  4976.6  283.07    5000  281.67  5006.7  282.03  5016.7  284.39
  5036.7  285.95  5105.8   287.4  5110.8  288.27  5146.7  298.98  5156.7   299.5
  5176.7   295.4  5186.7  295.02  5346.8  295.18  5366.8  297.09  5492.1  302.99
#Mann= 4 ,-1 , 0
  4540.2     .11       0    4632     .17       0 4895.68     .07       0
  5016.7     .17       0
Bank Sta=4895.68,5016.7
XS Rating Curve= 0 ,0
Exp/Cntr=0.3,0.1

Type RM Length L Ch R = 1 ,7486    ,498,498,498
BEGIN DESCRIPTION:
Conroe Lake 032 12.0
END DESCRIPTION:
XS GIS Cut Line= 3
      3818538.39     10171759.65      3818153.54     10172011.99
      3817641.77     10172203.43
#Sta/Elev= 30
  4539.8  295.64    4570  294.47  4585.1  290.71  4591.1  290.23  4606.2  290.12
  4657.5     287  4678.6  286.61  4714.7  284.63  4815.5  281.46  4931.8  280.47
    4968  280.44  4973.9  281.21  4982.9  280.33  4994.6  275.09    5000  275.09
  5004.3  272.73  5007.8  272.73  5011.5  276.91  5016.9  278.87  5027.4  279.45
  5041.8  278.96  5066.8  279.28    5097  283.67  5134.2  284.58  5152.3   285.9
  5230.3  287.03  5268.1  289.37  5298.4   290.5  5383.9  295.79  5546.4   302.8
#Mann= 3 ,-1 , 0
  4539.8     .15       0  4982.9     .09       0  5027.4     .15       0
Bank Sta=4982.9,5027.4
XS Rating Curve= 0 ,0
Exp/Cntr=0.3,0.1

Type RM Length L Ch R = 1 ,6988    ,575,575,575
BEGIN DESCRIPTION:
Conroe Lake 032 11.0
END DESCRIPTION:
XS GIS Cut Line= 3
        3818320.     10171336.03      3817979.29     10171674.42
      3817554.92     10172086.18
#Sta/Elev= 30
  4519.8  302.05    4532   300.1  4581.4  297.58  4623.9  294.23  4652.1  293.31
  4680.4  291.24  4814.8  284.08    4836  283.59  4843.1  282.66  4871.4  281.11
  4899.7  280.38    4935  278.09  4984.5  277.69  4991.6  276.79  4997.5   273.5
    5000   273.5  5003.9  271.37  5007.4  271.37    5027  276.78    5034  277.33
  5083.6  275.99  5154.3  277.23  5189.6  281.19  5203.7  282.11  5224.9  282.56
  5288.6  286.12  5345.2  287.87  5493.6  296.56  5521.9  298.85  5591.3  302.01
#Mann= 5 ,-1 , 0
  4519.8     .17       0  4984.5     .08       0  4991.6     .06       0
    5027     .08       0    5034     .17       0
Bank Sta=4991.6,5027
XS Rating Curve= 0 ,0
Exp/Cntr=0.3,0.1

Type RM Length L Ch R = 1 ,6413    ,99,99,99
BEGIN DESCRIPTION:
Conroe Lake 032 10.0
END DESCRIPTION:
XS GIS Cut Line= 3
       3818217.4     10171130.71      3817590.38     10171263.88
       3816856.9     10171425.58
#Sta/Elev= 30
    4359  301.98  4419.9  299.58  4460.8  296.05  4501.7  294.32  4522.1  291.24
  4542.6  290.07    4915   272.1  4971.9  270.62  4992.4  266.46    4997  263.27
  5003.9  263.77  5023.1  271.21  5084.5  273.87  5101.5  273.25  5145.2   277.1
  5199.1  278.98  5268.8  279.36  5286.5  277.49  5302.1  278.59  5391.7  280.16
  5412.2   282.6  5422.4  282.14  5427.9  282.91    5433  285.81  5445.7  286.52
  5463.4  286.38  5476.7  288.44  5520.4   289.9  5678.4  299.65  5751.1  301.27
#Mann= 7 ,-1 , 0
    4359     .17       0    4915     .08       0  4971.9     .06       0
  5023.1     .08       0  5084.5     .17       0  5302.1     .17       0
  5445.7     .11       0
Bank Sta=4971.9,5023.1
XS Rating Curve= 0 ,0
Exp/Cntr=0.3,0.1

Type RM Length L Ch R = 1 ,6314    ,821,821,821
BEGIN DESCRIPTION:
Conroe Lake 032 9.0
END DESCRIPTION:
XS GIS Cut Line= 3
      3818181.89     10171026.21      3817550.82     10171173.81
      3816834.49     10171315.47
#Sta/Elev= 30
  4351.9  300.01  4376.6  301.31  4398.7  300.39  4489.6  290.67  4499.8  290.35
  4526.2  293.79  4743.8  280.57  4859.3  275.29  4910.6  274.05  4941.4  270.27
  4951.7  270.75  4961.4  270.52  4966.6   267.7    4991  262.47  5004.1   263.4
  5009.9  266.04  5023.4  268.48  5033.6  267.77  5043.8   269.7    5054  270.08
  5061.1  267.53  5066.2  270.93  5074.4   271.3  5084.6  270.89  5117.5  273.81
  5186.5  274.31  5247.7  277.08  5271.3  276.94  5604.5  294.32  5730.2  299.05
#Mann= 5 ,-1 , 0
  4351.9     .17       0  4951.7     .08       0  4966.6     .06       0
  5023.4     .08       0  5074.4     .17       0
Bank Sta=4966.6,5023.4
XS Rating Curve= 0 ,0
Exp/Cntr=0.3,0.1

Type RM Length L Ch R = 1 ,5493    ,462,462,462
BEGIN DESCRIPTION:
Conroe Lake 032 8.0
END DESCRIPTION:
XS GIS Cut Line= 3
      3817963.56     10170448.29      3817252.95     10170727.79
      3816822.86     10171186.08
#Sta/Elev= 30
  4236.4  303.15  4296.3  303.59  4317.8  306.51  4328.5  305.72  4336.8  301.78
  4342.1  302.24    4350  299.55  4652.5  280.89  4736.8  274.16  4943.5  266.39
  4962.5  266.98  4973.3  264.36  4992.3  258.78    5004  258.23  5007.5  258.23
  5013.1  263.79  5019.9  264.83  5034.1  266.98  5090.7  264.71  5140.5  270.06
  5225.1  274.27  5246.5  277.46  5281.7  275.54    5289   277.8  5303.2  278.78
  5388.2  280.66    5395  282.54  5451.7  285.91  5563.3  290.37  5628.5  292.95
#Mann= 5 ,-1 , 0
  4236.4     .11       0  4652.5     .17       0  4973.3     .09       0
  5019.9     .17       0  5563.3     .11       0
Bank Sta=4973.3,5019.9
XS Rating Curve= 0 ,0
Exp/Cntr=0.3,0.1

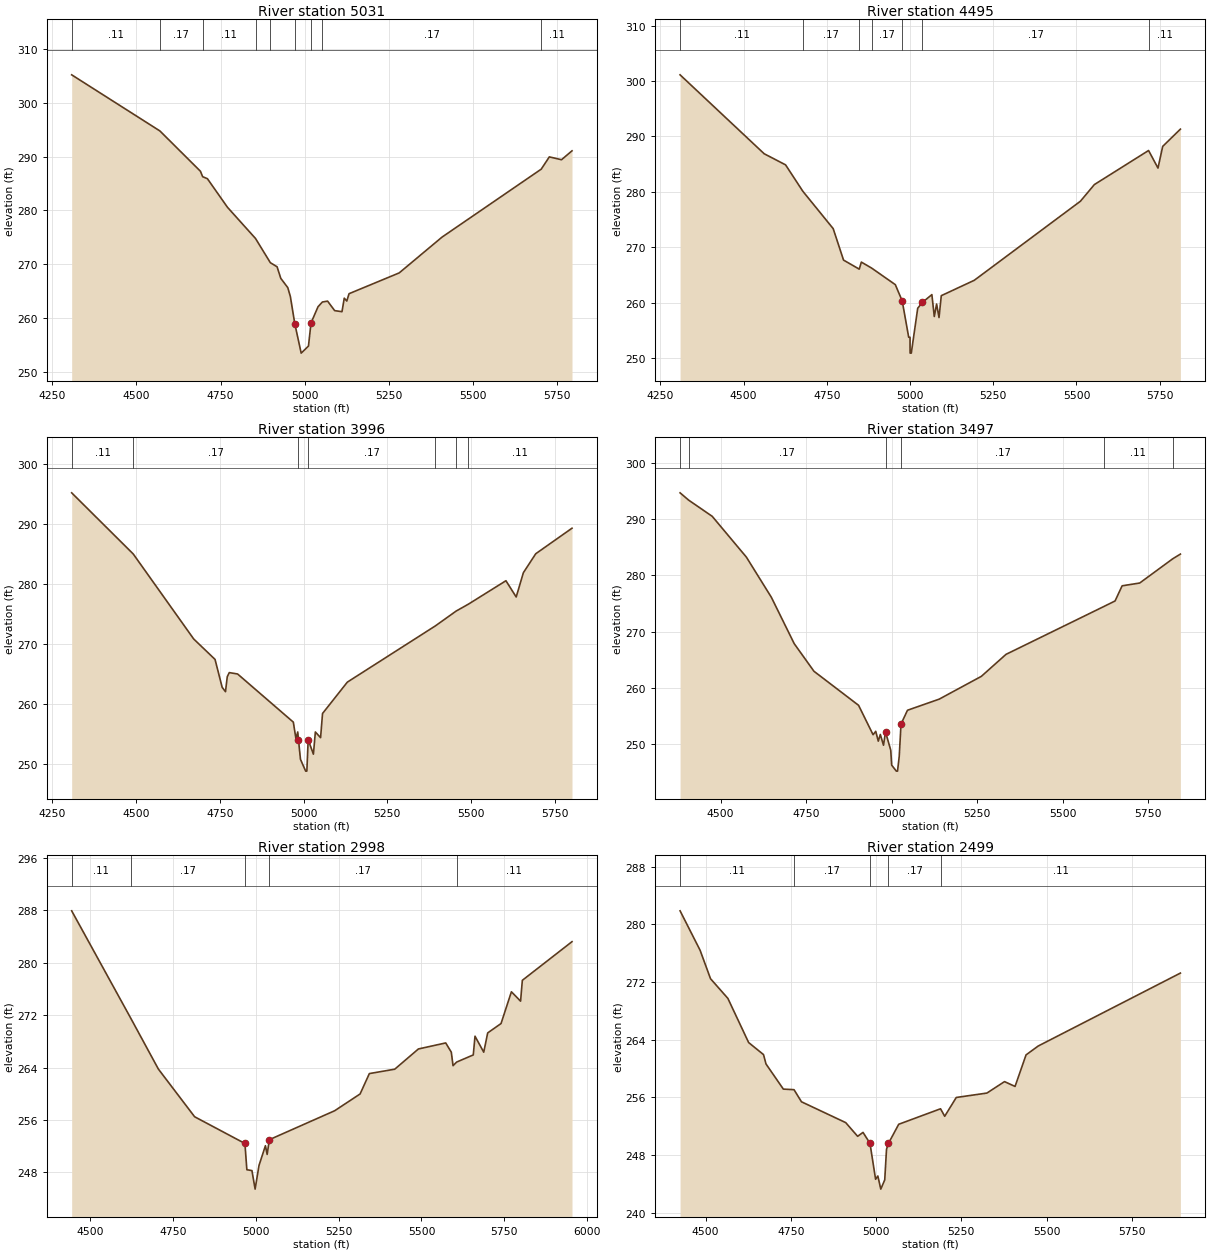
Type RM Length L Ch R = 1 ,5031    ,536,536,536
BEGIN DESCRIPTION:
Conroe Lake 032 7.0
END DESCRIPTION:
XS GIS Cut Line= 3
      3817866.29     10170201.78      3817199.38     10170386.81
      3816675.33     10170983.03
#Sta/Elev= 30
  4307.9  305.18    4570  294.76  4690.3  287.28  4696.9  286.27    4711   285.9
  4770.5   280.6  4853.9   274.8    4898   270.3  4917.9  269.55  4928.9   267.4
  4949.7  265.68  4957.4  264.02  4970.5  258.99  4989.5  253.52  5011.1  254.83
  5018.7  259.12  5039.6  262.14  5052.5  263.01    5068  263.17  5088.9  261.41
  5110.7  261.21  5117.4  263.72    5125  263.19  5131.6  264.55  5280.6  268.41
  5407.7  275.05  5702.4  287.67  5726.5  289.95  5762.6  289.42  5793.8  291.07
#Mann= 9 ,-1 , 0
  4307.9     .11       0    4570     .17       0  4696.9     .11       0
  4853.9     .17       0    4898     .15       0  4970.5     .09       0
  5018.7     .15       0  5052.5     .17       0  5702.4     .11       0
Bank Sta=4970.5,5018.7
XS Rating Curve= 0 ,0
Exp/Cntr=0.3,0.1

Type RM Length L Ch R = 1 ,4495    ,499,499,499
BEGIN DESCRIPTION:
Conroe Lake 032 6.0
END DESCRIPTION:
XS GIS Cut Line= 3
      3817661.41     10169903.17      3816995.23     10170085.59
      3816442.79     10170680.84
#Sta/Elev= 30
  4309.3  301.13  4561.8  286.89  4626.2  284.88  4678.1  280.11  4769.2  273.37
  4800.3  267.69  4847.5  266.06  4853.8  267.33  4884.9  266.24  4955.8  263.26
  4976.5  260.33    4996  253.77    5000  253.77  5000.1   251.4  5000.3   250.9
  5003.8   250.9  5023.1     259  5037.2  260.06  5065.6  261.46  5072.9  257.51
  5079.8  259.76  5087.1  257.32  5093.9  261.27  5193.1  264.05  5511.7  278.31
  5553.7  281.32  5716.5  287.47  5744.8   284.3  5758.9  288.21  5812.1  291.33
#Mann= 7 ,-1 , 0
  4309.3     .11       0  4678.1     .17       0  4847.5     .15       0
  4884.9     .17       0  4976.5     .09       0  5037.2     .17       0
  5716.5     .11       0
Bank Sta=4976.5,5037.2
XS Rating Curve= 0 ,0
Exp/Cntr=0.3,0.1

Type RM Length L Ch R = 1 ,3996    ,499,499,499
BEGIN DESCRIPTION:
Conroe Lake 032 5.0
END DESCRIPTION:
XS GIS Cut Line= 3
      3817390.63      10169660.1      3816739.17     10169892.87
      3816328.12     10170580.24
#Sta/Elev= 30
  4308.2  295.15  4491.9  284.95  4672.2  270.78  4735.9  267.37  4757.2  262.71
  4767.1  261.99  4772.4  264.49  4778.4  265.17  4803.2  264.94  4969.5  256.91
  4977.3  254.14  4982.6  255.27 4984.86  253.97  4990.8  250.71  5006.3  248.74
  5009.8  248.74  5013.8  253.97  5029.4  251.57  5035.2  255.27  5050.8  254.32
  5056.6  258.35  5130.6  263.58  5393.3  272.96  5455.5  275.44    5492  276.59
  5603.8  280.49  5634.4  277.78  5655.8  281.83  5692.7  284.99  5800.9  289.25
#Mann= 7 ,-1 , 0
  4308.2     .11       0  4491.9     .17       0 4984.86     .09       0
  5013.8     .17       0  5393.3     .11       0  5455.5     .17       0
    5492     .11       0
Bank Sta=4984.86,5013.8
XS Rating Curve= 0 ,0
Exp/Cntr=0.3,0.1

Type RM Length L Ch R = 1 ,3497    ,499,499,499
BEGIN DESCRIPTION:
Conroe Lake 032 4.0
END DESCRIPTION:
XS GIS Cut Line= 3
      3816970.51     10169274.66      3816448.34     10169606.33
       3816251.9     10170426.74
#Sta/Elev= 30
  4381.4  294.74  4406.4  293.44  4475.3  290.55  4575.3  283.26  4648.1  276.11
    4715  267.83  4772.6  262.91  4903.1  256.83  4945.4  251.59  4953.2  252.19
  4960.7  250.44  4966.6  251.63  4975.9  249.71  4981.8  252.08  4997.1  248.82
  4999.8  246.16  5013.4  245.09  5016.9  245.09  5021.9  247.73  5027.1  253.48
    5046  255.95  5138.6  257.93  5261.9     262  5333.9  265.92  5620.6  274.48
  5652.7  275.45  5673.3  278.15  5724.7  278.65  5820.9  282.96  5843.6  283.81
#Mann= 6 ,-1 , 0
  4381.4     .11       0  4406.4     .17       0  4981.8     .09       0
  5027.1     .17       0  5620.6     .11       0  5820.9     .17       0
Bank Sta=4981.8,5027.1
XS Rating Curve= 0 ,0
Exp/Cntr=0.3,0.1

Type RM Length L Ch R = 1 ,2998    ,499,499,499
BEGIN DESCRIPTION:
Conroe Lake 032 3.0
END DESCRIPTION:
XS GIS Cut Line= 3
      3816672.22     10169025.18      3816202.24     10169321.87
      3815928.87     10170236.28
#Sta/Elev= 30
  4444.2  287.95  4622.9  271.52  4705.9  263.79  4815.3  256.51  4967.1  252.43
    4973  248.42  4988.3  248.29  4997.9  245.46  5009.6  249.07    5029  252.09
  5034.2  250.76  5040.9  253.01  5238.1  257.43  5314.8  259.99  5342.7   263.1
  5419.3  263.77  5490.8  266.86  5573.2  267.78  5590.1  266.37  5595.3  264.31
  5606.2  264.86  5656.4  265.95  5661.6  268.81    5688  266.37  5699.9  269.31
  5740.2  270.74  5771.5  275.59  5799.2  274.16  5804.5  277.34  5954.4  283.24
#Mann= 5 ,-1 , 0
  4444.2     .11       0  4622.9     .17       0  4967.1     .09       0
  5040.9     .17       0  5606.2     .11       0
Bank Sta=4967.1,5040.9
XS Rating Curve= 0 ,0
Exp/Cntr=0.3,0.1

Type RM Length L Ch R = 1 ,2499    ,946,946,946
BEGIN DESCRIPTION:
Conroe Lake 032 2.0
END DESCRIPTION:
XS GIS Cut Line= 3
      3816525.71     10168872.44       3815960.3      10168975.9
      3815740.33     10169841.07
#Sta/Elev= 30
  4425.2  281.88    4484   276.4  4514.5  272.46  4565.4  269.73  4626.3   263.6
  4669.9  261.93  4677.2  260.63  4728.1  257.14  4759.4  257.06  4781.3  255.38
    4911  252.49    4946  250.59  4961.8  251.13  4982.2  249.62  4998.7  244.63
  5005.3  245.08  5013.9  243.26  5025.5  244.54  5030.7  248.79  5036.3   249.6
  5066.5  252.26  5189.2  254.41  5201.4  253.37  5235.3  255.98  5325.2  256.59
  5376.8  258.18  5407.7  257.51    5440  261.89  5475.7  263.12  5892.7  273.24
#Mann= 5 ,-1 , 0
  4425.2     .11       0  4759.4     .17       0  4982.2     .09       0
  5036.3     .17       0  5189.2     .11       0
#XS Ineff= 2 , 0
       0  4961.8  251.13               0
Permanent Ineff=
       F       F
Bank Sta=4982.2,5036.3
XS Rating Curve= 0 ,0
Exp/Cntr=0.3,0.1

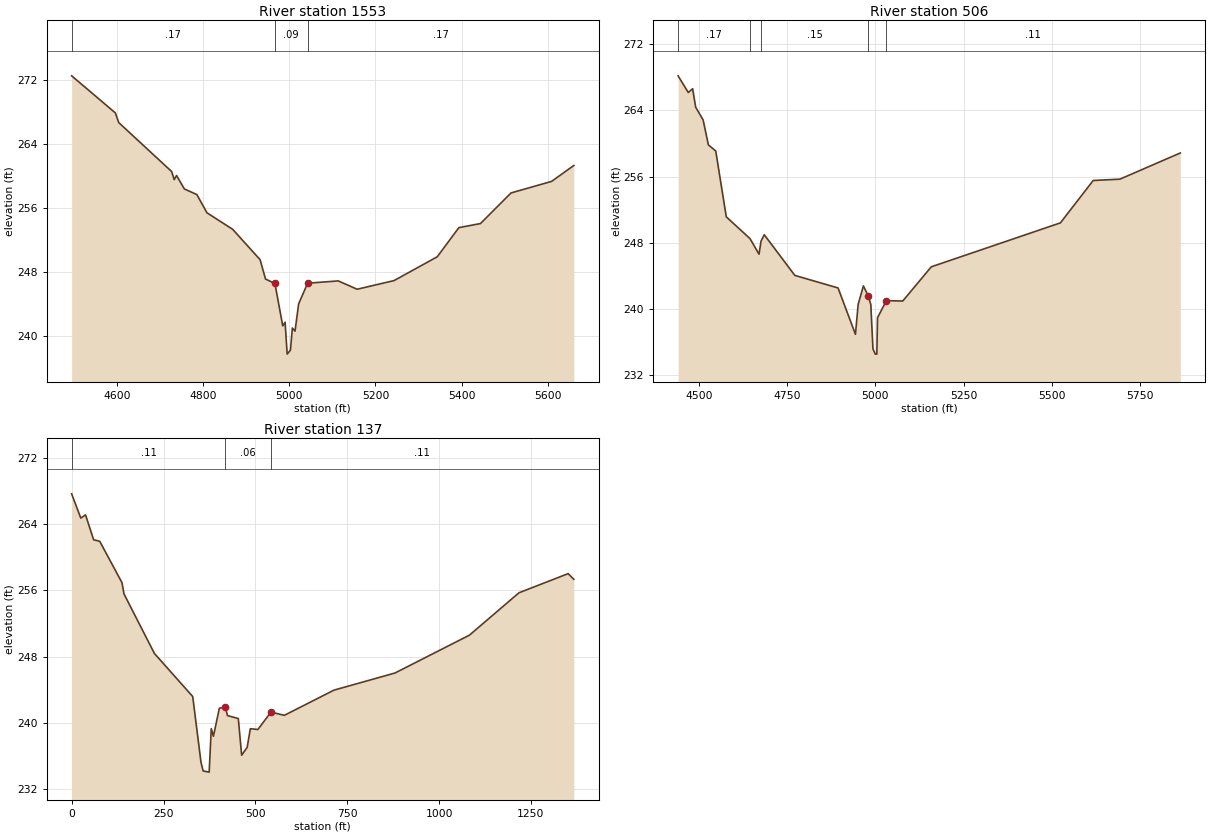
Type RM Length L Ch R = 1 ,1553    ,1047,1047,1047
BEGIN DESCRIPTION:
Conroe Lake 032 1.0
END DESCRIPTION:
XS GIS Cut Line= 3
      3816391.01     10168620.22      3815927.46     10168420.85
      3815396.55     10168813.28
#Sta/Elev= 30
  4495.4  272.48  4596.8  267.85  4604.7  266.64  4727.4  260.53  4733.3  259.52
  4738.7  260.04  4756.8  258.36  4785.8  257.66  4809.3  255.38  4868.9  253.32
  4932.5  249.53  4945.1  247.11  4966.9  246.56    4985  241.27  4990.5  241.72
  4995.3  237.74  5002.9  238.24  5007.3     241  5013.5  240.61  5021.9  244.01
  5042.7  246.59  5113.7  246.88  5157.6  245.84  5243.2  246.92  5343.4  249.89
  5393.5  253.53  5443.6  254.04  5514.5  257.86  5608.5   259.3  5660.2  261.29
#Mann= 3 , 0 , 0
  4495.4     .17       0  4966.9     .09       0  5042.7     .17       0
Bank Sta=4966.9,5042.7
XS Rating Curve= 0 ,0
Exp/Cntr=0.3,0.1

Type RM Length L Ch R = 1 ,506     ,369,369,369
BEGIN DESCRIPTION:
Conroe Lake 032 1.5
END DESCRIPTION:
XS GIS Cut Line= 3
      3815872.57     10167367.21      3815552.61     10167832.74
      3815205.38      10168616.6
#Sta/Elev= 30
  4441.7  268.19  4470.5  266.17  4482.8  266.63  4491.5  264.39  4512.5  262.85
  4527.4  259.83  4548.3  259.09  4578.1  251.12  4645.4  248.48  4670.8   246.6
  4676.6  248.19  4685.7  248.95  4772.3  244.03  4894.7  242.51  4943.9   236.9
  4951.6  240.53  4966.5  242.76  4980.3  241.51  4987.4  240.51  4993.5  235.13
  5000.1   234.5  5004.5   234.5  5006.4   238.9  5031.4  240.97  5077.9  240.93
  5158.7  245.07  5524.4  250.39  5617.2  255.52  5692.8  255.68  5863.9  258.85
#Mann= 5 ,-1 , 0
  4441.7     .17       0  4645.4     .11       0  4676.6     .15       0
  4980.3     .09       0  5031.4     .11       0
Bank Sta=4980.3,5031.4
XS Rating Curve= 0 ,0
Exp/Cntr=0.3,0.1

Type RM Length L Ch R = 1 ,137     ,0,0,0
XS GIS Cut Line= 3
      3815558.51     10167198.97      3815339.05     10167619.49
      3815126.02     10168486.16
#Sta/Elev= 30
       0  267.66    24.9  264.73    37.8  265.12    59.9  262.11    76.4  261.93
     137  256.93   142.6  255.56   225.3  248.38   329.5  243.18     352  235.25
   357.9  234.19   374.3  234.05     380   239.3   385.9  238.38     402  241.77
   418.5  241.89   424.1  240.88   453.6  240.52   462.7  236.09   477.7  237.04
   486.3  239.29   506.9   239.2   542.5   241.3   578.9  240.91   713.9  243.95
     880  246.02  1082.6  250.59  1217.5  255.71  1351.3  258.02  1366.8  257.34
#Mann= 3 , 0 , 0
       0     .11       0   418.5     .06       0   542.5     .11       0
Bank Sta=418.5,542.5
XS Rating Curve= 0 ,0
Exp/Cntr=0.3,0.1

Chan Stop Cuts=-1
Use User Specified Reach Order=0
Composite Channel Slope=5