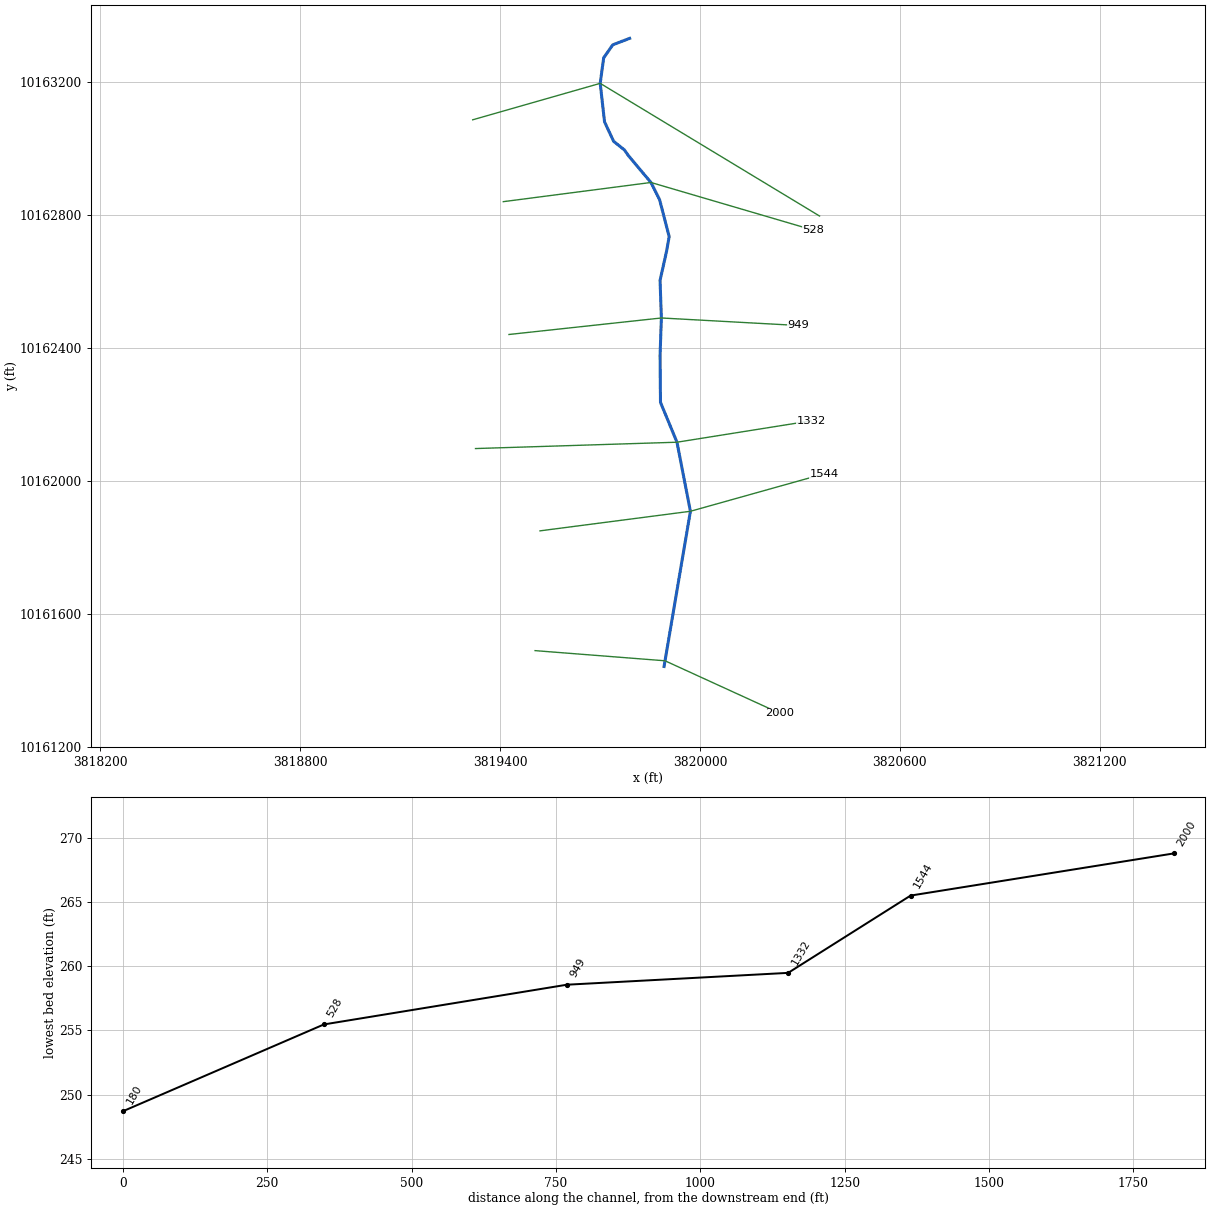
--- Conroe Lake 034.prj (project) ---

Proj Title=Conroe Lake 034 Base Level Engineering
Current Plan=p01
Default Exp/Contr=0.3,0.1
English Units
Geom File=g01
Flow File=f01
Flow File=f02
Plan File=p01
Y Axis Title=Elevation
X Axis Title(PF)=Main Channel Distance
X Axis Title(XS)=Station
BEGIN DESCRIPTION:
Conroe Lake 034
END DESCRIPTION:
DSS Export Rating Curves= 0
DSS Export Rating Curve Sorted= 0
DSS Export Volume Flow Curves= 0
DXF OffsetX= 0
DXF OffsetY= 0
DXF ScaleX= 1
DXF ScaleY= 10

--- Conroe Lake 034.p01 (plan) ---

Plan Title=Multiple Run
Short Identifier=Multiple
Geom File=g01
Flow File=f01
Subcritical Flow
K Sum by GR= 0
Std Step Tol= 0.01
Critical Tol= 0.01
Num of Std Step Trials= 20
Max Error Tol= 0.3
Flow Tol Ratio= 0.001
Split Flow NTrial= 30
Split Flow Tol= 0.02
Split Flow Ratio= 0.02
Log Output Level= 0
Friction Slope Method= 1
Unsteady Friction Slope Method= 2
Unsteady Bridges Friction Slope Method= 1
Parabolic Critical Depth
Global Vel Dist=  1 , 1 , 1
Global Log Level= 0
CheckData=True
Encroach Param= -1, 0, 0, 0
BEGIN DESCRIPTION:
Multiple Run
END DESCRIPTION:

--- Conroe Lake 034.f01 (steady flow) ---

Flow Title=Multiple
Program Version=4.10
Number of Profiles= 7
Profile Names=10-year,25-year,50-year,1pct_min,100-year,1pct_plu,500-year
River Rch & RM=Conroe Lake 034,Reach-1         ,2000
     357     470     624     275     829    2504    1505
River Rch & RM=Conroe Lake 034,Reach-1         ,1544
     572     775    1050     469    1417    4279    2663
Boundary for River Rch & Prof#=Conroe Lake 034,Reach-1         , 1
Up Type= 0
Dn Type= 3
Dn Slope=0.005
Boundary for River Rch & Prof#=Conroe Lake 034,Reach-1         , 2
Up Type= 0
Dn Type= 3
Dn Slope=0.005
Boundary for River Rch & Prof#=Conroe Lake 034,Reach-1         , 3
Up Type= 0
Dn Type= 3
Dn Slope=0.005
Boundary for River Rch & Prof#=Conroe Lake 034,Reach-1         , 4
Up Type= 0
Dn Type= 3
Dn Slope=0.005
Boundary for River Rch & Prof#=Conroe Lake 034,Reach-1         , 5
Up Type= 0
Dn Type= 3
Dn Slope=0.005
Boundary for River Rch & Prof#=Conroe Lake 034,Reach-1         , 6
Up Type= 0
Dn Type= 3
Dn Slope=0.005
Boundary for River Rch & Prof#=Conroe Lake 034,Reach-1         , 7
Up Type= 0
Dn Type= 3
Dn Slope=0.005
DSS Import GetInterval= 0
DSS Import GetPeak= 0
DSS Import FillOption= 0

--- Conroe Lake 034.f02 (steady flow) ---

Flow Title=Orig_BLE_Flow
Program Version=4.10
Number of Profiles= 7
Profile Names=10-year,25-year,50-year,1pct_min,100-year,1pct_plu,500-year
River Rch & RM=Conroe Lake 034,Reach-1         ,2000
     357     461     543     211     638    1926     875
River Rch & RM=Conroe Lake 034,Reach-1         ,1544
     572     760     913     361    1090    3292    1548
Boundary for River Rch & Prof#=Conroe Lake 034,Reach-1         , 1
Up Type= 0
Dn Type= 3
Dn Slope=0.005
Boundary for River Rch & Prof#=Conroe Lake 034,Reach-1         , 2
Up Type= 0
Dn Type= 3
Dn Slope=0.005
Boundary for River Rch & Prof#=Conroe Lake 034,Reach-1         , 3
Up Type= 0
Dn Type= 3
Dn Slope=0.005
Boundary for River Rch & Prof#=Conroe Lake 034,Reach-1         , 4
Up Type= 0
Dn Type= 3
Dn Slope=0.005
Boundary for River Rch & Prof#=Conroe Lake 034,Reach-1         , 5
Up Type= 0
Dn Type= 3
Dn Slope=0.005
Boundary for River Rch & Prof#=Conroe Lake 034,Reach-1         , 6
Up Type= 0
Dn Type= 3
Dn Slope=0.005
Boundary for River Rch & Prof#=Conroe Lake 034,Reach-1         , 7
Up Type= 0
Dn Type= 3
Dn Slope=0.005
DSS Import GetInterval= 0
DSS Import GetPeak= 0
DSS Import FillOption= 0

--- Conroe Lake 034.g01 (geometry) ---

Geom Title=Existing Conditions
Program Version=4.10

River Reach=Conroe Lake 034 ,Reach-1
Reach XY= 19
      3819892.08     10161440.77      3819971.17     10161907.59
      3819930.86     10162115.33      3819881.38     10162235.12
      3819880.08     10162375.75      3819883.98     10162489.03
      3819880.08     10162602.31      3819899.61     10162689.55
      3819907.42     10162733.82      3819878.77      10162844.5
      3819852.73     10162896.58      3819785.02     10162977.31
      3819773.31     10162994.24      3819740.75     10163020.28
      3819713.41     10163078.87      3819700.39     10163194.76
       3819710.8     10163271.58      3819738.15     10163310.64
      3819788.85     10163330.15

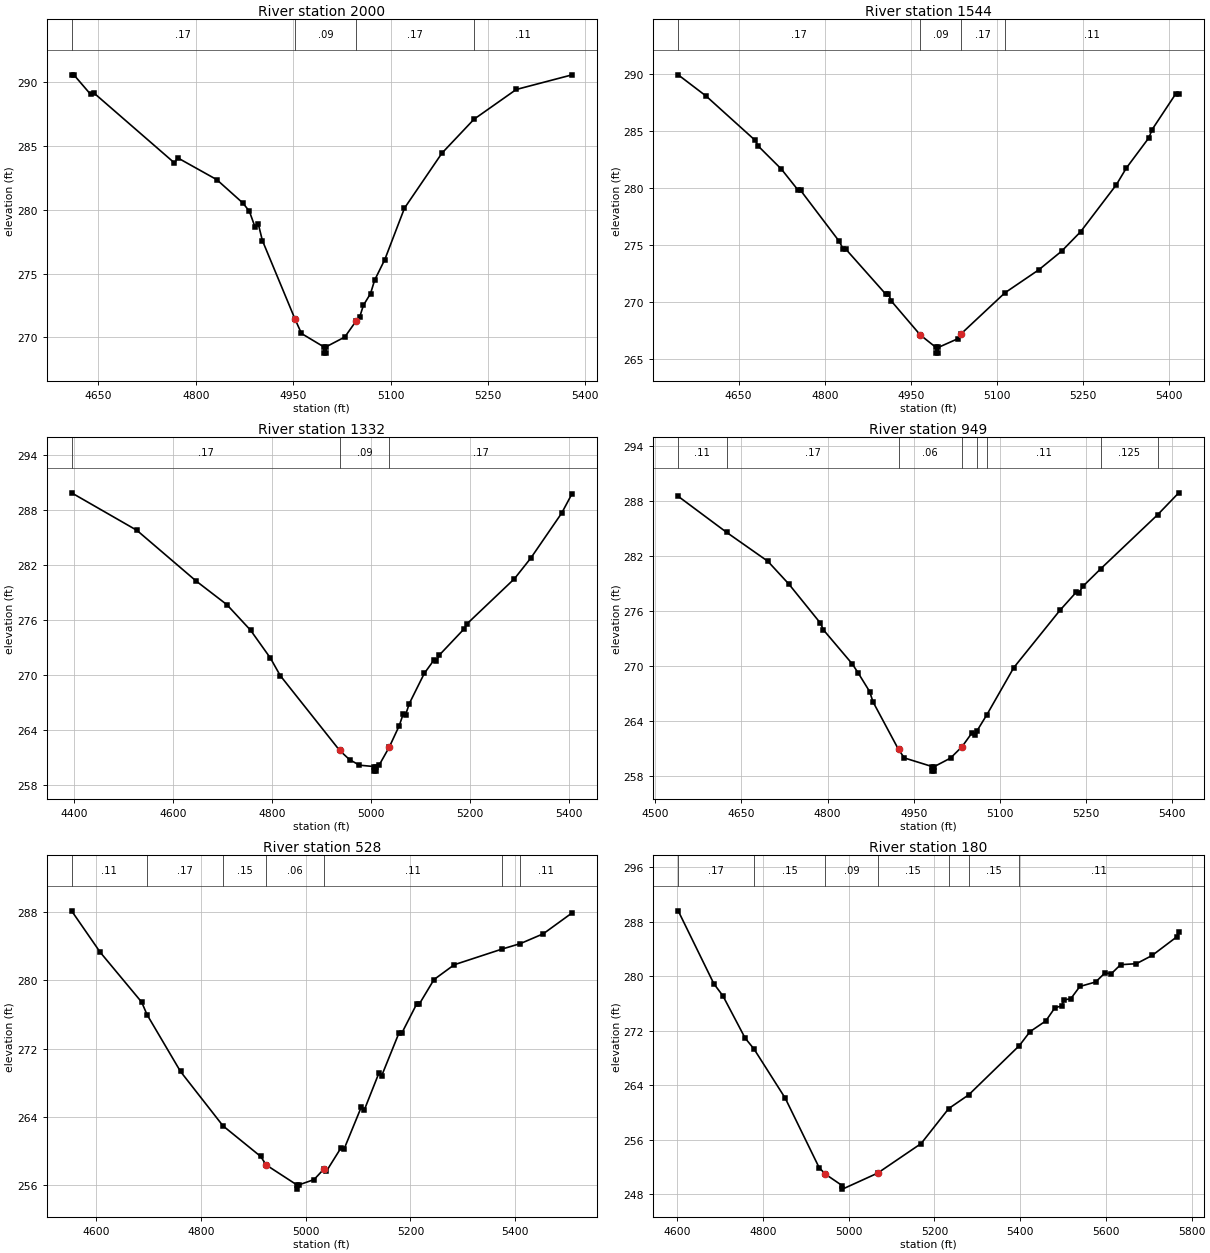
Type RM Length L Ch R = 1 ,2000    ,456,456,456
BEGIN DESCRIPTION:
Conroe Lake 034 4.5
END DESCRIPTION:
XS GIS Cut Line= 3
      3819504.88     10161488.45      3819894.99      10161457.9
      3820240.17     10161299.73
#Sta/Elev= 30
  4608.7  290.56  4612.7  290.56    4638  289.06    4643  289.17  4767.2  283.68
  4772.2  284.08  4832.4  282.37  4872.5  280.54  4882.5   279.9  4891.4  278.64
  4896.4  278.88  4902.6   277.6  4952.7  271.46  4962.8  270.31  4996.9  269.27
  4997.2  268.77  5000.7  268.77  5000.9  269.27  5029.5  270.03    5047  271.29
  5052.5   271.6  5058.2  272.52  5069.2  273.44  5075.5  274.49  5091.2  276.11
  5121.5  280.14  5179.2  284.45  5228.6  287.11  5293.6  289.44  5379.7  290.59
#Mann= 4 ,-1 , 0
  4608.7     .17       0  4952.7     .09       0    5047     .17       0
  5228.6     .11       0
Bank Sta=4952.7,5047
XS Rating Curve= 0 ,0
Exp/Cntr=0.3,0.1

Type RM Length L Ch R = 1 ,1544    ,212,212,212
BEGIN DESCRIPTION:
Conroe Lake 034 4.0
END DESCRIPTION:
XS GIS Cut Line= 3
      3819519.59     10161848.72      3819971.17     10161907.59
      3820372.55     10162020.29
#Sta/Elev= 30
  4544.6  289.96  4593.3  288.09  4678.9  284.19    4684   283.7  4724.4  281.67
  4752.9  279.86  4757.9   279.8  4825.2  275.32  4831.9  274.67  4836.9  274.62
  4905.9   270.7  4910.9   270.7    4916  270.07  4966.4  267.09  4993.8  265.99
  4994.1  265.49  4997.6  265.49  4997.8  265.99  5032.1  266.76  5038.1  267.21
  5113.9  270.79  5173.1  272.82  5212.9  274.46  5245.8  276.16  5308.2   280.3
  5325.5  281.76  5364.8  284.42  5370.5  285.15  5411.8   288.3  5416.9   288.3
#Mann= 4 ,-1 , 0
  4544.6     .17       0  4966.4     .09       0  5038.1     .17       0
  5113.9     .11       0
Bank Sta=4966.4,5038.1
XS Rating Curve= 0 ,0
Exp/Cntr=0.3,0.1

Type RM Length L Ch R = 1 ,1332    ,383,383,383
BEGIN DESCRIPTION:
Conroe Lake 034 3.0
END DESCRIPTION:
XS GIS Cut Line= 3
      3819325.96     10162096.26      3819930.86     10162115.33
      3820333.06     10162179.55
#Sta/Elev= 30
  4394.8  289.86  4526.8  285.77  4646.8  280.23    4709  277.65  4756.9  274.86
  4796.9  271.83  4816.9  269.91    4937  261.74    4957  260.74    4977  260.13
  5006.4  259.98  5006.7  259.48  5010.2  259.48  5010.4  259.98  5017.2  260.16
  5037.5  262.11  5057.7  264.45  5065.5  265.71  5070.5  265.64    5078  266.86
  5108.4  270.16  5127.5  271.58  5132.6  271.48  5138.7  272.15  5189.4  275.04
  5194.7  275.56  5290.6  280.48  5323.9  282.75    5386  287.63  5407.3  289.78
#Mann= 3 ,-1 , 0
  4394.8     .17       0    4937     .09       0  5037.5     .17       0
Bank Sta=4937,5037.5
XS Rating Curve= 0 ,0
Exp/Cntr=0.3,0.1

Type RM Length L Ch R = 1 ,949     ,421,421,421
BEGIN DESCRIPTION:
Conroe Lake 034 2.0
END DESCRIPTION:
XS GIS Cut Line= 3
      3819426.47     10162439.38      3819883.98     10162489.03
      3820294.66     10162466.44
#Sta/Elev= 30
  4539.8  288.53  4624.1   284.6  4695.8  281.45  4732.3  278.97  4787.4   274.7
  4792.7  273.96    4843  270.24    4853  269.28  4873.1  267.24    4879  266.11
  4923.4  260.92  4933.5     260  4981.8  259.06    4982  258.56  4985.5  258.56
  4985.8  259.06  5013.9  259.98  5033.9  261.22  5051.4  262.74  5056.4  262.52
  5059.8  262.93  5077.4  264.73  5124.1  269.85  5204.2  276.08  5232.6  278.06
  5237.6  278.02  5244.2   278.7  5275.5  280.63  5374.5  286.52  5411.3  288.91
#Mann= 8 ,-1 , 0
  4539.8     .11       0  4624.1     .17       0  4923.4     .06       0
  5033.9     .11       0  5059.8     .17       0  5077.4     .11       0
  5275.5    .125       0  5374.5     .11       0
Bank Sta=4923.4,5033.9
XS Rating Curve= 0 ,0
Exp/Cntr=0.3,0.1

Type RM Length L Ch R = 1 ,528     ,348,348,348
BEGIN DESCRIPTION:
Conroe Lake 034 1.0
END DESCRIPTION:
XS GIS Cut Line= 3
      3819409.37     10162838.87      3819852.73     10162896.58
      3820340.67     10162753.08
#Sta/Elev= 30
  4552.9  288.19  4607.8   283.3  4686.8  277.45    4697  275.98  4760.9   269.3
    4842  262.91    4914  259.31  4924.5  258.31    4983  255.97  4983.2  255.47
    4987  255.97  5015.8  256.59  5034.3  257.81  5039.5  257.58  5067.7  260.36
  5072.9  260.14  5106.2  265.14  5111.5  264.73  5139.6   269.1  5144.8  268.77
  5178.2  273.86  5183.4  273.81  5211.5   277.2  5216.7  277.22  5244.9  280.11
  5283.5  281.85  5374.6  283.69  5409.9  284.34  5453.5  285.49  5508.6  287.95
#Mann= 7 ,-1 , 0
  4552.9     .11       0    4697     .17       0    4842     .15       0
  4924.5     .06       0  5034.3     .11       0  5374.6    .125       0
  5409.9     .11       0
Bank Sta=4924.5,5034.3
XS Rating Curve= 0 ,0
Exp/Cntr=0.3,0.1

Type RM Length L Ch R = 1 ,180     ,0,0,0
BEGIN DESCRIPTION:
Conroe Lake 034 1.5
END DESCRIPTION:
XS GIS Cut Line= 3
      3819317.68     10163085.14      3819700.39     10163194.76
       3820358.9     10162795.67
#Sta/Elev= 30
  4601.9  289.63  4685.3  278.89  4706.1  277.15  4758.1  270.92  4778.8  269.32
  4851.7  262.09  4930.9  251.87  4945.4  250.92    4985  249.22  4985.2  248.72
  5067.2  251.07  5168.8  255.42  5233.3  260.57  5279.8  262.58  5397.9  269.81
  5422.9  271.87  5459.7  273.44  5481.1  275.39  5496.6  275.64  5502.4  276.55
  5517.9   276.7  5539.2  278.51  5576.1  279.17  5597.4  280.48  5612.9   280.4
  5634.2  281.71  5671.1  281.86  5707.9  283.07  5766.1  285.84    5770  286.52
#Mann= 7 ,-1 , 0
  4601.9     .17       0  4778.8     .15       0  4945.4     .09       0
  5067.2     .15       0  5233.3     .11       0  5279.8     .15       0
  5397.9     .11       0
Bank Sta=4945.4,5067.2
XS Rating Curve= 0 ,0
Exp/Cntr=0.3,0.1

Chan Stop Cuts=-1
Use User Specified Reach Order=0
Composite Channel Slope=5