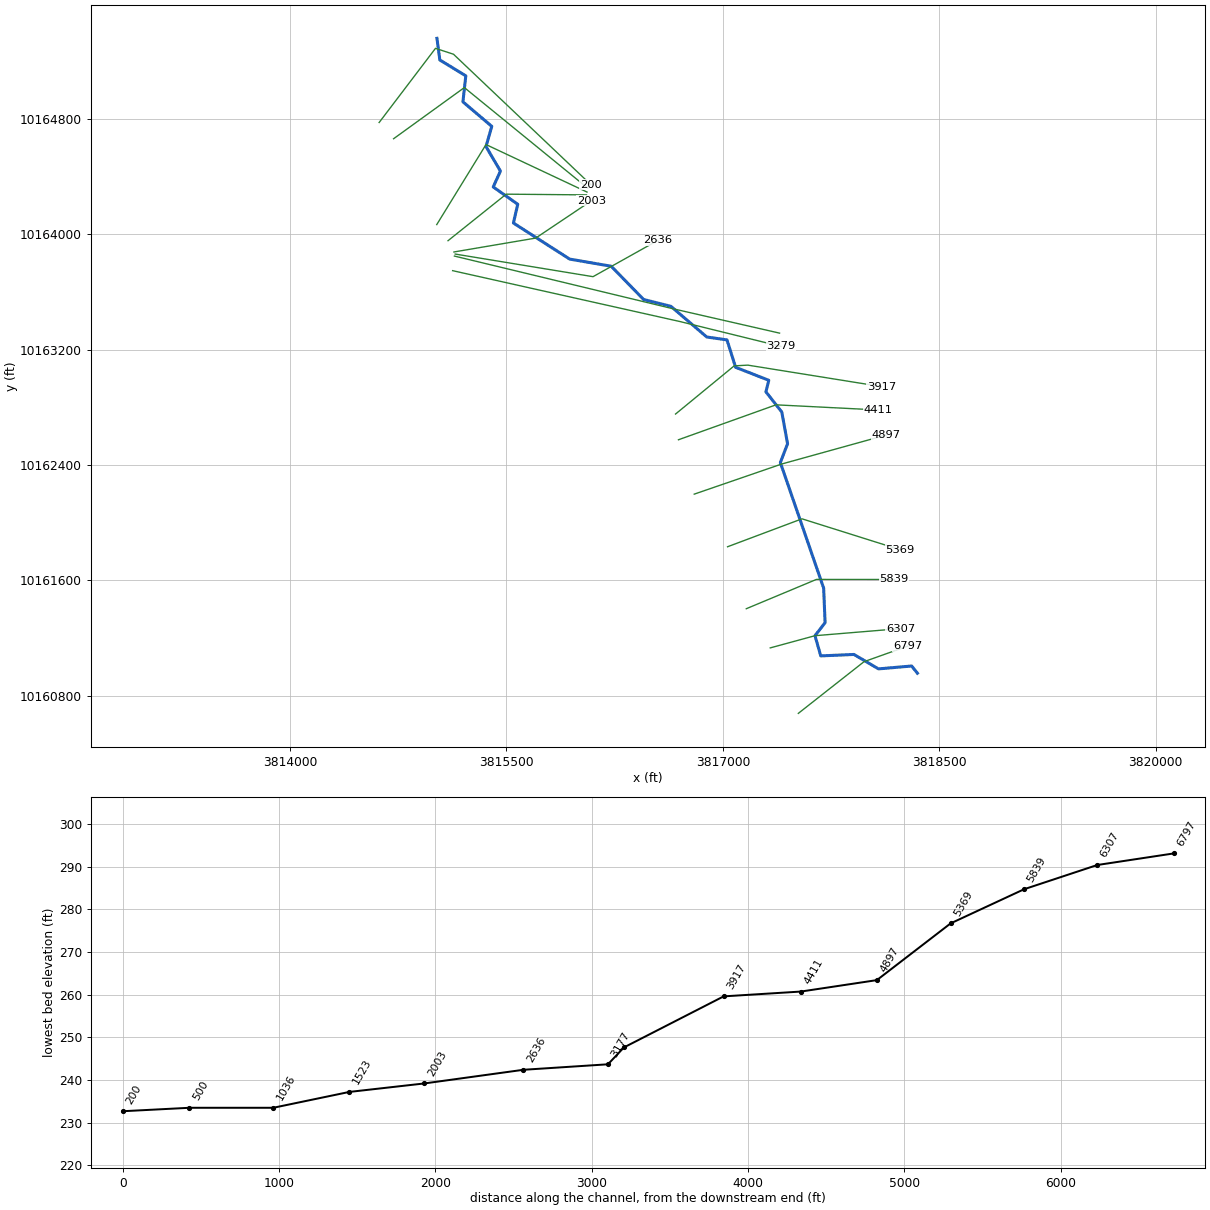
--- Conroe Lake 035.prj (project) ---

Proj Title=Conroe Lake 035 Base Level Engineering
Current Plan=p01
Default Exp/Contr=0.3,0.1
English Units
Geom File=g01
Flow File=f01
Flow File=f02
Plan File=p01
Y Axis Title=Elevation
X Axis Title(PF)=Main Channel Distance
X Axis Title(XS)=Station
BEGIN DESCRIPTION:
Conroe Lake 035
END DESCRIPTION:
DSS File=dss
DSS Export Rating Curves= 0
DSS Export Rating Curve Sorted= 0
DSS Export Volume Flow Curves= 0
DXF OffsetX= 0
DXF OffsetY= 0
DXF ScaleX= 1
DXF ScaleY= 10

--- Conroe Lake 035.p01 (plan) ---

Plan Title=Multiple Run
Short Identifier=Multiple
Geom File=g01
Flow File=f01
Subcritical Flow
K Sum by GR= 0
Std Step Tol= 0.01
Critical Tol= 0.01
Num of Std Step Trials= 20
Max Error Tol= 0.3
Flow Tol Ratio= 0.001
Split Flow NTrial= 30
Split Flow Tol= 0.02
Split Flow Ratio= 0.02
Log Output Level= 0
Friction Slope Method= 1
Unsteady Friction Slope Method= 2
Unsteady Bridges Friction Slope Method= 1
Parabolic Critical Depth
Global Vel Dist=  1 , 1 , 1
Global Log Level= 0
CheckData=True
Encroach Param= -1, 0, 0, 0
BEGIN DESCRIPTION:
Multiple Run
END DESCRIPTION:

--- Conroe Lake 035.f01 (steady flow) ---

Flow Title=Multiple
Program Version=4.10
Number of Profiles= 7
Profile Names=10-year,25-year,50-year,1pct_min,100-year,1pct_plu,500-year
River Rch & RM=Conroe Lake 035,Reach-1         ,6797
     238     305     398     172     520    1570     913
River Rch & RM=Conroe Lake 035,Reach-1         ,6307
     508     678     910     403    1216    3672    2236
Boundary for River Rch & Prof#=Conroe Lake 035,Reach-1         , 1
Up Type= 0
Dn Type= 3
Dn Slope=0.005
Boundary for River Rch & Prof#=Conroe Lake 035,Reach-1         , 2
Up Type= 0
Dn Type= 3
Dn Slope=0.005
Boundary for River Rch & Prof#=Conroe Lake 035,Reach-1         , 3
Up Type= 0
Dn Type= 3
Dn Slope=0.005
Boundary for River Rch & Prof#=Conroe Lake 035,Reach-1         , 4
Up Type= 0
Dn Type= 3
Dn Slope=0.005
Boundary for River Rch & Prof#=Conroe Lake 035,Reach-1         , 5
Up Type= 0
Dn Type= 3
Dn Slope=0.005
Boundary for River Rch & Prof#=Conroe Lake 035,Reach-1         , 6
Up Type= 0
Dn Type= 3
Dn Slope=0.005
Boundary for River Rch & Prof#=Conroe Lake 035,Reach-1         , 7
Up Type= 0
Dn Type= 3
Dn Slope=0.005
DSS Import GetInterval= 0
DSS Import GetPeak= 0
DSS Import FillOption= 0

--- Conroe Lake 035.f02 (steady flow) ---

Flow Title=Orig_BLE_Flow
Program Version=4.10
Number of Profiles= 7
Profile Names=10-year,25-year,50-year,1pct_min,100-year,1pct_plu,500-year
River Rch & RM=Conroe Lake 035,Reach-1         ,6797
     238     299     346     133     400    1209     531
River Rch & RM=Conroe Lake 035,Reach-1         ,6307
     508     665     791     310     935    2823    1300
Boundary for River Rch & Prof#=Conroe Lake 035,Reach-1         , 1
Up Type= 0
Dn Type= 3
Dn Slope=0.005
Boundary for River Rch & Prof#=Conroe Lake 035,Reach-1         , 2
Up Type= 0
Dn Type= 3
Dn Slope=0.005
Boundary for River Rch & Prof#=Conroe Lake 035,Reach-1         , 3
Up Type= 0
Dn Type= 3
Dn Slope=0.005
Boundary for River Rch & Prof#=Conroe Lake 035,Reach-1         , 4
Up Type= 0
Dn Type= 3
Dn Slope=0.005
Boundary for River Rch & Prof#=Conroe Lake 035,Reach-1         , 5
Up Type= 0
Dn Type= 3
Dn Slope=0.005
Boundary for River Rch & Prof#=Conroe Lake 035,Reach-1         , 6
Up Type= 0
Dn Type= 3
Dn Slope=0.005
Boundary for River Rch & Prof#=Conroe Lake 035,Reach-1         , 7
Up Type= 0
Dn Type= 3
Dn Slope=0.005
DSS Import GetInterval= 0
DSS Import GetPeak= 0
DSS Import FillOption= 0

--- Conroe Lake 035.g01 (geometry) ---

Geom Title=Existing Conditions
Program Version=4.10

River Reach=Conroe Lake 035 ,Reach-1
Reach XY= 30
      3818348.23     10160956.84      3818308.23     10161006.84
      3818078.23     10160986.84      3817908.23     10161086.84
      3817678.23     10161076.84      3817638.23     10161216.84
      3817708.23     10161306.84      3817698.23     10161546.84
      3817398.23     10162416.84      3817448.23     10162546.84
      3817408.23     10162766.84      3817298.23     10162906.84
      3817318.23     10162986.84      3817088.23     10163076.84
      3817028.23     10163266.84      3816888.23     10163286.84
      3816639.78     10163499.56      3816450.78     10163546.81
      3816225.86      10163777.4      3815938.23     10163826.84
      3815548.23     10164076.84      3815578.23     10164206.84
      3815408.23     10164326.84      3815458.23     10164436.84
      3815358.23     10164606.84      3815398.23     10164746.84
      3815198.23     10164916.84      3815218.23     10165096.84
      3815038.23     10165206.84      3815018.23     10165356.84

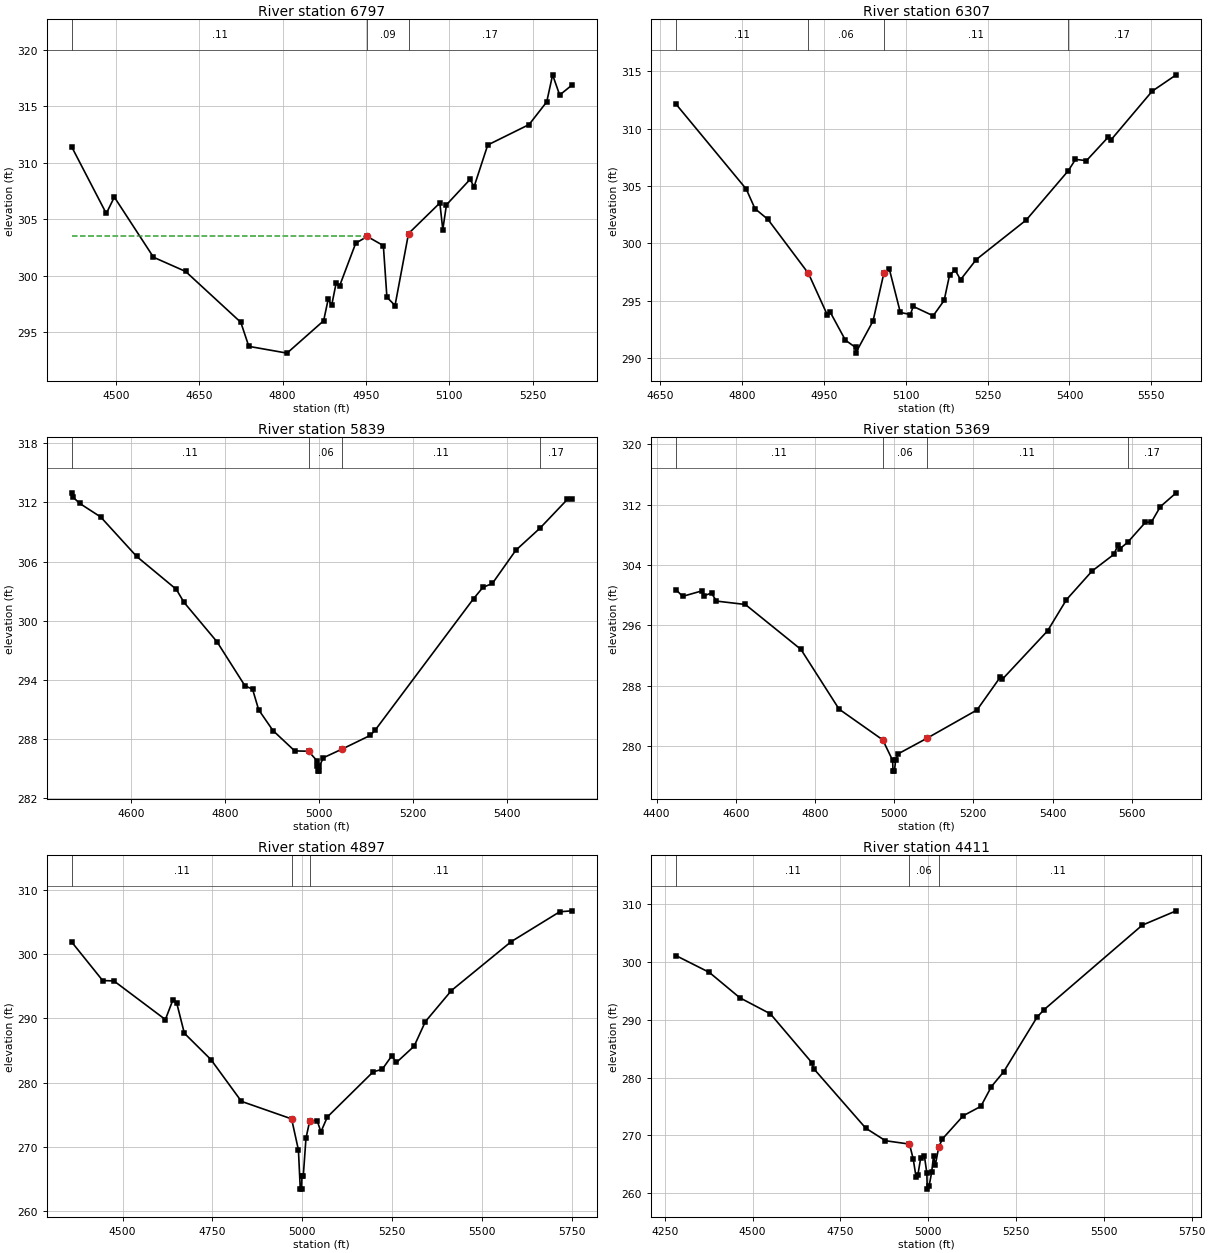
Type RM Length L Ch R = 1 ,6797    ,490,490,490
BEGIN DESCRIPTION:
Conroe Lake 035 14.0
END DESCRIPTION:
XS GIS Cut Line= 3
      3817522.69     10160678.49      3817978.23     10161036.84
      3818280.44     10161144.48
#Sta/Elev= 30
  4420.4  311.42  4482.7  305.51  4497.2  306.96  4567.7  301.63  4625.5  300.37
  4724.9  295.86  4739.3  293.73  4808.1  293.13    4874     296  4882.1  297.89
  4888.5  297.38  4896.5  299.34  4902.9  299.11  4931.8  302.88  4952.6  303.47
  4981.5  302.66  4987.9  298.09  5002.5  297.35  5026.8  303.73  5083.2  306.44
  5088.5  304.08  5095.1  306.28  5137.6  308.53  5144.8  307.88  5169.4  311.58
  5243.8  313.39  5275.6   315.4  5286.2   317.8  5298.9  316.01  5320.8  316.88
#Mann= 3 , 0 , 0
  4420.4     .11       0  4952.6     .09       0  5026.8     .17       0
#XS Ineff= 2 , 0
       0  4946.2  303.48               0
Permanent Ineff=
       T       F
Bank Sta=4952.6,5026.8
XS Rating Curve= 0 ,0
Exp/Cntr=0.3,0.1

Type RM Length L Ch R = 1 ,6307    ,468,468,468
BEGIN DESCRIPTION:
Conroe Lake 035 13.0
END DESCRIPTION:
XS GIS Cut Line= 3
      3817328.25     10161132.32      3817638.23     10161216.84
       3818231.8     10161266.02
#Sta/Elev= 30
  4678.7  312.14  4807.4  304.73  4823.4  303.02  4847.2  302.08  4921.5  297.36
    4956  293.75  4961.2     294  4989.2  291.54  5007.7  290.91  5007.9  290.41
  5039.8  293.21  5059.8  297.41  5069.9  297.71  5089.9  293.96  5108.4  293.78
  5113.4  294.49  5150.1  293.67  5170.2  295.01  5180.2  297.24  5190.3  297.66
  5200.3  296.82  5229.1  298.58  5320.7  302.03  5397.8  306.33    5411  307.32
  5431.1  307.21  5470.7  309.25  5475.7     309  5551.5  313.27  5595.6   314.7
#Mann= 4 ,-1 , 0
  4678.7     .11       0  4921.5     .06       0  5059.8     .11       0
  5397.8     .17       0
#XS Ineff= 2 , 0
       0                  5069.9       0  297.71
Permanent Ineff=
       F       F
Bank Sta=4921.5,5059.8
XS Rating Curve= 0 ,0
Exp/Cntr=0.3,0.1

Type RM Length L Ch R = 1 ,5839    ,470,470,470
BEGIN DESCRIPTION:
Conroe Lake 035 12.0
END DESCRIPTION:
XS GIS Cut Line= 3
      3817162.13      10161403.8      3817648.23     10161606.84
      3818187.23     10161606.37
#Sta/Elev= 30
  4473.2  312.97  4476.5  312.51  4490.2   311.9    4535  310.52  4611.8  306.51
  4696.1  303.18  4712.5  301.86  4782.8  297.86  4842.4  293.39  4858.7  293.04
  4871.6  290.96  4902.1  288.85  4948.5  286.78  4977.9  286.75  4996.1  285.77
    4997  285.23  4997.2  284.73  5000.7  284.73    5001  285.23  5009.6  286.09
  5049.6  286.97  5109.6  288.36  5119.6  288.87  5329.6  302.23  5349.6  303.38
  5369.6  303.77  5419.6  307.14  5471.5   309.4  5529.6  312.31    5539  312.34
#Mann= 4 ,-1 , 0
  4473.2     .11       0  4977.9     .06       0  5049.6     .11       0
  5471.5     .17       0
Bank Sta=4977.9,5049.6
XS Rating Curve= 0 ,0
Exp/Cntr=0.3,0.1

Type RM Length L Ch R = 1 ,5369    ,472,472,472
BEGIN DESCRIPTION:
Conroe Lake 035 11.0
END DESCRIPTION:
XS GIS Cut Line= 3
      3817032.46     10161833.28      3817548.23     10162026.84
      3818227.68     10161813.03
#Sta/Elev= 30
  4449.1  300.75  4465.5  299.85  4513.8  300.57  4519.1  299.93  4538.7  300.29
    4551  299.23  4624.1  298.78  4764.6  292.83  4860.8  284.93  4971.1  280.86
    4996  278.16  4997.2  276.72  5000.7  276.72  5003.7  278.16  5010.1  279.01
  5083.5  281.09  5209.3  284.82    5268  289.16  5273.2  288.88  5387.5  295.29
  5435.2  299.42  5499.9  303.21  5555.2  305.42  5564.7  306.61  5569.9  306.15
  5589.4  306.99  5634.7  309.66  5649.6  309.68  5672.3  311.73  5712.3  313.56
#Mann= 4 ,-1 , 0
  4449.1     .11       0  4971.1     .06       0  5083.5     .11       0
  5589.4     .17       0
Bank Sta=4971.1,5083.5
XS Rating Curve= 0 ,0
Exp/Cntr=0.3,0.1

Type RM Length L Ch R = 1 ,4897    ,486,486,486
BEGIN DESCRIPTION:
Conroe Lake 035 10.0
END DESCRIPTION:
XS GIS Cut Line= 3
      3816801.49     10162197.94      3817408.23     10162406.84
      3818130.46     10162607.17
#Sta/Elev= 30
  4358.3  301.87  4444.5  295.87  4475.8  295.81  4618.9   289.8    4640  292.87
  4650.6  292.35  4671.7  287.67  4745.8  283.56  4830.4  277.07    4970  274.34
    4989  269.51  4994.2  263.41  4997.7  263.41  4998.8  265.38  5002.4  265.38
    5010  271.32  5020.4  274.04  5041.1  274.07  5051.5  272.32  5069.5  274.64
  5196.8  281.66  5222.2  282.06  5248.7  284.16  5261.6  283.12  5310.9  285.66
  5342.1  289.48  5414.7  294.32  5580.7  301.92  5715.7  306.57  5749.5  306.72
#Mann= 3 , 0 , 0
  4358.3     .11       0    4970     .06       0  5020.4     .11       0
Bank Sta=4970,5020.4
XS Rating Curve= 0 ,0
Exp/Cntr=0.3,0.1

Type RM Length L Ch R = 1 ,4411    ,494,494,494
BEGIN DESCRIPTION:
Conroe Lake 035 9.0
END DESCRIPTION:
XS GIS Cut Line= 3
      3816692.06     10162574.75      3817368.23     10162816.84
      3818073.34     10162781.42
#Sta/Elev= 30
  4281.8  301.06  4376.5  298.17  4463.5  293.78  4550.4  291.01  4668.2   282.6
  4673.5  281.56    4822  271.26  4878.2  269.09  4946.5  268.51  4957.1  265.96
  4965.2  262.86  4970.5  263.22  4978.4  266.07    4989  266.46    4996  263.49
  4997.1  260.73  5002.3  261.23  5009.6  263.62    5015  266.42    5020  264.86
  5029.7  267.93  5039.7  269.36  5099.7  273.41  5149.8  275.03  5179.8  278.44
  5214.8     281    5310  290.45    5330  291.74  5609.3  306.32    5706   308.8
#Mann= 3 , 0 , 0
  4281.8     .11       0  4946.5     .06       0  5029.7     .11       0
Bank Sta=4946.5,5029.7
XS Rating Curve= 0 ,0
Exp/Cntr=0.3,0.1

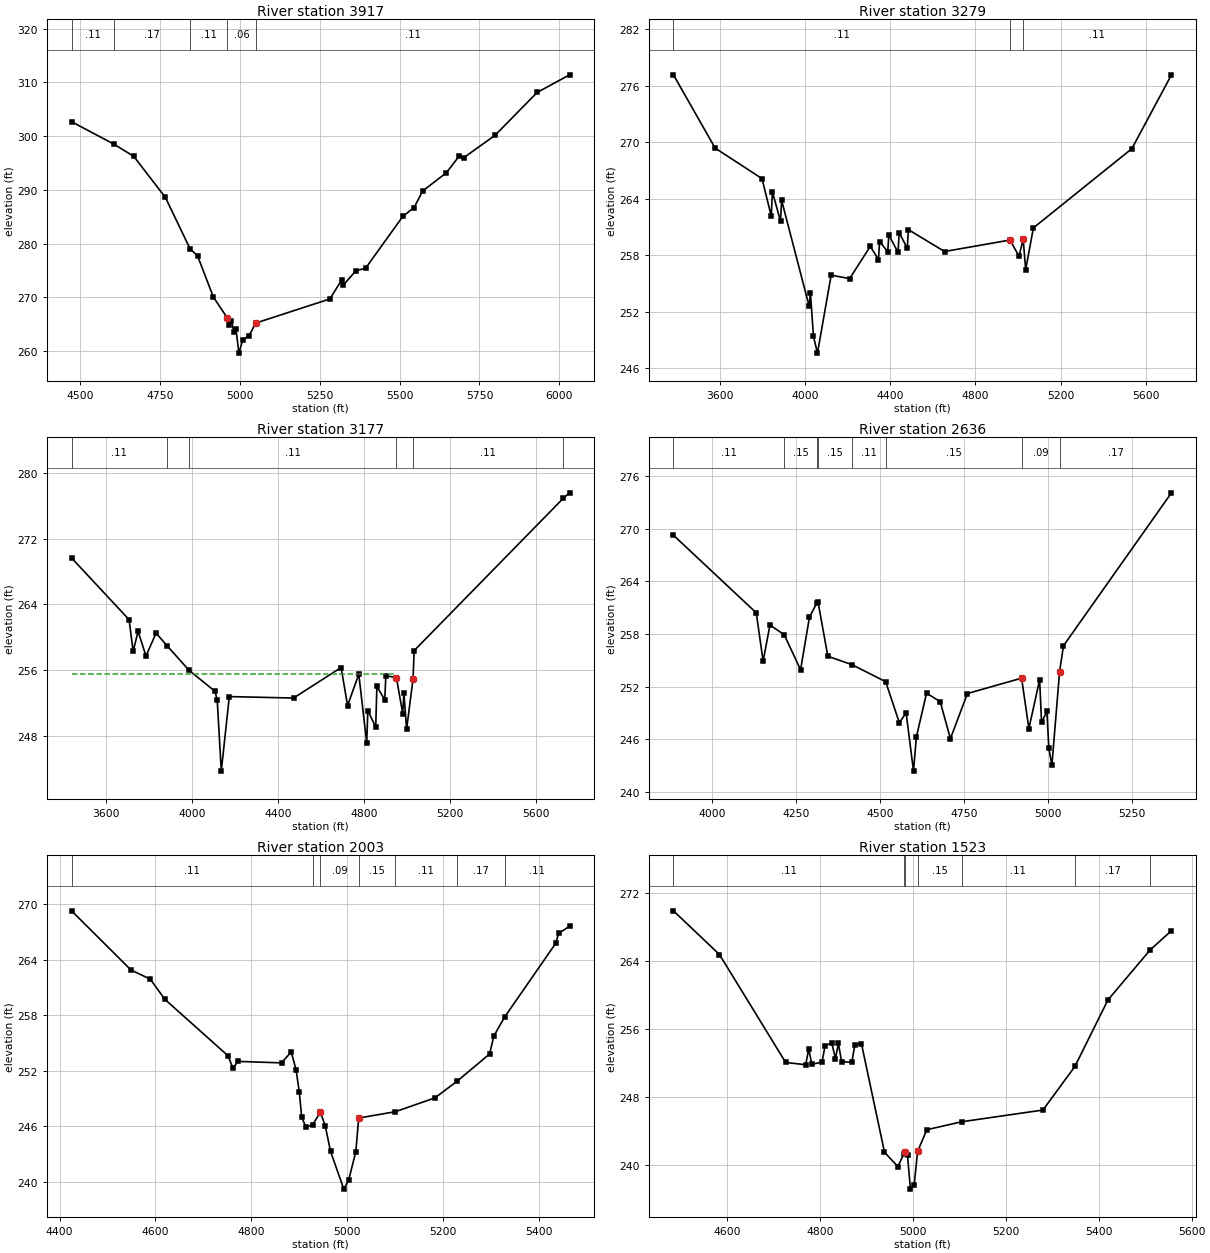
Type RM Length L Ch R = 1 ,3917    ,638,638,638
BEGIN DESCRIPTION:
Conroe Lake 035 8.0
END DESCRIPTION:
XS GIS Cut Line= 4
      3816671.84     10162753.05      3817078.23     10163086.84
      3817172.67     10163092.02      3818098.04     10162943.47
#Sta/Elev= 30
  4474.1  302.69  4606.9   298.5  4668.7  296.23  4767.7  288.58  4844.6  279.04
  4868.2  277.71  4917.7  270.03  4960.7  266.21  4967.2   264.8  4973.7  265.66
  4981.6  263.62    4988  264.18  4997.6   259.6  5009.6  262.09  5029.7  262.87
  5049.7  265.19  5282.1  269.69  5319.5  273.27  5324.5  272.29  5363.2  274.94
  5393.5  275.39  5510.3  285.07  5545.5  286.71  5572.3  289.79  5646.7   293.2
  5687.3  296.35  5701.2  296.01  5798.7  300.16  5930.3  308.14  6031.8  311.42
#Mann= 5 ,-1 , 0
  4474.1     .11       0  4606.9     .17       0  4844.6     .11       0
  4960.7     .06       0  5049.7     .11       0
Bank Sta=4960.7,5049.7
XS Rating Curve= 0 ,0
Exp/Cntr=0.3,0.1

Type RM Length L Ch R = 1 ,3279    ,102,102,102
BEGIN DESCRIPTION:
Conroe Lake 035 7.5
END DESCRIPTION:
XS GIS Cut Line= 3
      3815126.96     10163746.72      3816704.04     10163393.72
      3817403.06      10163221.6
#Sta/Elev= 30
  3383.9  277.17  3579.5  269.39  3799.4  266.15  3842.7  262.17  3847.9  264.77
  3886.1  261.61  3891.3  263.84  4020.2  252.62  4026.5  254.04  4040.6  249.41
  4059.4  247.62  4123.6   255.9  4210.3  255.53  4307.3  258.96  4345.6  257.55
  4350.7  259.47    4389  258.39  4394.1  260.15  4437.5  258.33  4442.6  260.42
  4480.9  258.75    4486  260.73  4655.5  258.41  4962.9  259.63  5004.5  257.91
  5024.5   259.7    5036  256.49  5072.3  260.92  5534.1  269.33  5719.9  277.17
#Mann= 3 , 0 , 0
  3383.9     .11       0  4962.9     .06       0  5024.5     .11       0
#XS Ineff= 2 , 0
       0    4486  260.73               0
Permanent Ineff=
       F       F
Bank Sta=4962.9,5024.5
XS Rating Curve= 0 ,0
Exp/Cntr=0.3,0.1

Type RM Length L Ch R = 1 ,3177    ,541,541,541
BEGIN DESCRIPTION:
Conroe Lake 035 7.0
END DESCRIPTION:
XS GIS Cut Line= 3
       3815139.4     10163847.84       3816654.9     10163482.55
      3817392.65     10163313.81
#Sta/Elev= 30
  3441.1  269.66  3708.4  262.14  3727.5  258.27  3750.3  260.71  3787.1  257.71
  3834.1   260.5    3885  258.96  3987.5  255.96  4108.1   253.4  4118.4  252.31
  4137.2  243.67  4174.6  252.76  4473.1  252.58  4694.4   256.3  4724.5  251.66
  4776.7  255.49  4813.5  247.08  4818.6  251.05  4855.4  249.03  4860.6  253.99
  4897.3  252.38  4902.5   255.3  4951.6  255.07  4981.1  250.67  4986.3  253.25
  4998.9  248.77  5028.9  254.92    5034  258.36  5726.9  276.92  5756.8   277.6
#Mann= 6 ,-1 , 0
  3441.1     .11       0    3885     .15       0  3987.5     .11       0
  4951.6     .06       0  5028.9     .11       0  5726.9     .17       0
#XS Ineff= 2 , 0
       0  4944.4  255.53               0
Permanent Ineff=
       T       F
Bank Sta=4951.6,5028.9
XS Rating Curve= 0 ,0
Exp/Cntr=0.3,0.1

Type RM Length L Ch R = 1 ,2636    ,633,633,633
BEGIN DESCRIPTION:
Mapping XS 438194ae
END DESCRIPTION:
XS GIS Cut Line= 3
      3815144.56     10163861.78      3816099.92     10163704.98
       3816548.3     10163955.99
#Sta/Elev= 30
  3885.9  269.25  4132.4  260.41  4152.7   254.9  4173.1  259.02  4215.5  257.92
  4264.2  253.92  4290.6  259.91  4312.2  261.51  4316.1  261.65  4345.3  255.47
  4416.8  254.51  4517.4  252.57  4558.1  247.89  4578.3  249.02  4600.3  242.38
  4608.7  246.26  4639.1  251.26  4679.7  250.29  4710.1  246.08  4760.7  251.22
  4921.9  252.97  4943.6  247.23  4975.6  252.78  4981.3  247.93  4997.3  249.18
    5003  244.96  5012.1  243.05  5034.9   253.7  5046.5  256.66  5367.9  274.08
#Mann= 8 ,-1 , 0
  3885.9     .11       0  4215.5     .15       0  4312.2     .11       0
  4316.1     .15       0  4416.8     .11       0  4517.4     .15       0
  4921.9     .09       0  5034.9     .17       0
#XS Ineff= 2 , 0
       0  4975.6  252.78               0
Permanent Ineff=
       T       F
Bank Sta=4921.9,5034.9
XS Rating Curve= 0 ,0
Exp/Cntr=0.3,0.1

Type RM Length L Ch R = 1 ,2003    ,480,480,480
BEGIN DESCRIPTION:
Conroe Lake 035 4.0
END DESCRIPTION:
XS GIS Cut Line= 3
      3815135.79     10163876.24      3815702.58      10163972.5
      3816088.57     10164231.07
#Sta/Elev= 30
  4425.1  269.29  4548.9   262.9  4589.5  261.89  4619.9  259.71  4751.8   253.6
  4761.9  252.25  4772.1     253  4863.3  252.84  4883.6  254.03  4893.8  252.06
  4900.4   249.7  4905.4  246.98  4914.1   245.9    4928  246.13  4944.5   247.5
  4954.6  246.02  4965.7  243.26  4993.3  239.18  5003.4  240.14  5018.4  243.24
  5024.4  246.87  5101.1  247.56  5183.5  249.05  5229.4  250.84  5297.6   253.8
  5306.6  255.76  5329.2  257.81  5435.6  265.77  5441.7  266.84  5464.6  267.63
#Mann= 7 ,-1 , 0
  4425.1     .11       0    4928     .15       0  4944.5     .09       0
  5024.4     .15       0  5101.1     .11       0  5229.4     .17       0
  5329.2     .11       0
#XS Ineff= 2 , 0
       0  4944.5   247.5               0
Permanent Ineff=
       F       F
Bank Sta=4944.5,5024.4
XS Rating Curve= 0 ,0
Exp/Cntr=0.3,0.1

Type RM Length L Ch R = 1 ,1523    ,487,487,487
BEGIN DESCRIPTION:
Conroe Lake 035 3.0
END DESCRIPTION:
XS GIS Cut Line= 3
      3815095.05     10163954.34      3815498.23     10164276.84
      3816054.71     10164271.92
#Sta/Elev= 30
  4483.7  269.88  4582.9  264.74  4725.4  252.07  4768.6   251.8    4775  253.65
  4781.8  251.86  4803.8   252.1  4810.2  254.02  4824.7  254.37  4832.7  252.52
  4839.1  254.31  4845.8  252.18  4867.9  252.07  4874.3   254.1  4888.7  254.27
  4938.3  241.53  4967.1  239.84  4979.4  241.26  4981.5  241.51  4987.9  241.17
  4994.2  237.19  5002.3   237.7  5009.6  241.61  5029.6  244.17  5104.3   245.1
  5279.6  246.48  5348.5   251.6  5419.6  259.41  5510.8   265.3  5556.5  267.55
#Mann= 7 ,-1 , 0
  4483.7     .11       0  4979.4     .15       0  4981.5     .09       0
  5009.6     .15       0  5104.3     .11       0  5348.5     .17       0
  5510.8     .11       0
Bank Sta=4981.5,5009.6
XS Rating Curve= 0 ,0
Exp/Cntr=0.3,0.1

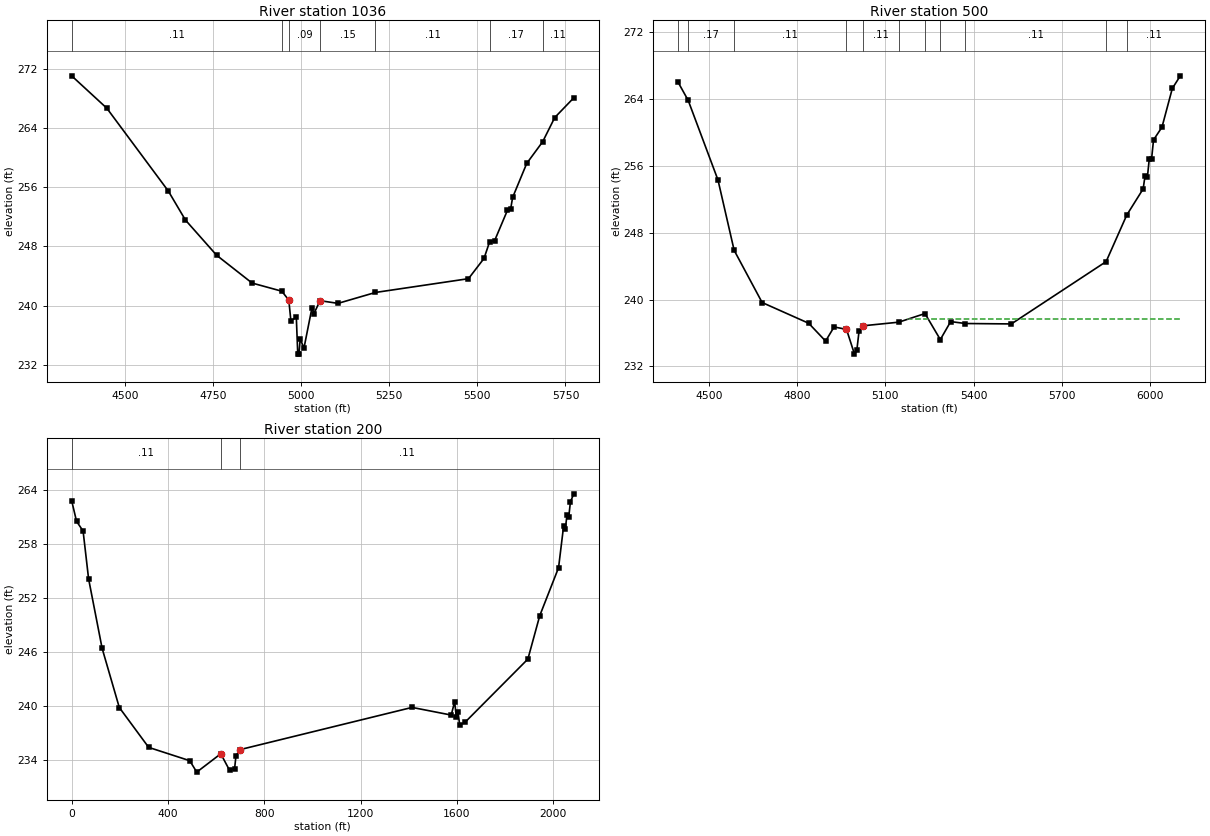
Type RM Length L Ch R = 1 ,1036    ,536,536,536
BEGIN DESCRIPTION:
Conroe Lake 035 2.0
END DESCRIPTION:
XS GIS Cut Line= 3
      3815016.95     10164066.09      3815358.23      10164620.7
      3816058.47      10164291.4
#Sta/Elev= 30
  4348.8  271.02  4448.6  266.65    4623  255.48  4671.7  251.56  4760.2  246.81
  4860.8  243.06  4945.2  241.96    4965  240.75  4970.9  237.96  4986.3  238.46
  4990.4  233.47  4993.9  233.47  4997.3  235.54    5008  234.28  5030.8  239.74
  5036.3  238.93  5053.6  240.68  5104.7  240.32  5210.8  241.79  5474.8  243.65
    5519  246.39  5534.8  248.63    5549  248.78  5585.3  252.87  5594.6  253.08
  5600.1  254.61  5640.2  259.21  5685.4  262.13  5719.6  265.39  5773.8  268.06
#Mann= 7 ,-1 , 0
  4348.8     .11       0  4945.2     .15       0    4965     .09       0
  5053.6     .15       0  5210.8     .11       0  5534.8     .17       0
  5685.4     .11       0
Bank Sta=4965,5053.6
XS Rating Curve= 0 ,0
Exp/Cntr=0.3,0.1

Type RM Length L Ch R = 1 ,500     ,427,427,427
BEGIN DESCRIPTION:
Conroe Lake 035 1.0
END DESCRIPTION:
XS GIS Cut Line= 3
      3814717.84     10164661.06      3815208.23     10165015.55
      3816063.34     10164318.37
#Sta/Elev= 30
  4394.9  265.97  4429.2   263.8  4530.6  254.28  4585.5  245.88  4680.7  239.64
  4839.1  237.16  4896.6  235.03  4925.5  236.72  4967.7  236.43  4994.9  233.47
    5003  233.97  5010.5  236.25  5024.8  236.86  5145.5  237.29  5234.7  238.32
  5286.9  235.21  5322.1  237.36    5372  237.13  5528.5  237.08  5850.9  244.53
  5921.2   250.1    5977  253.23  5983.4  254.81  5991.4  254.65  5997.8  256.84
  6005.7  256.85  6012.2  259.08  6040.9   260.6  6076.1  265.23  6103.3  266.74
#Mann= 11 ,-1 , 0
  4394.9     .11       0  4429.2     .17       0  4585.5     .11       0
  4967.7     .07       0  5024.8     .11       0  5145.5     .11       0
  5234.7     .17       0  5286.9     .15       0    5372     .11       0
  5850.9     .17       0  5921.2     .11       0
#XS Ineff= 2 , 0
       0                  5173.5       0  237.72
Permanent Ineff=
       F       F
Bank Sta=4967.7,5024.8
XS Rating Curve= 0 ,0
Exp/Cntr=0.3,0.1

Type RM Length L Ch R = 1 ,200     ,0,0,0
XS GIS Cut Line= 4
      3814617.69     10164773.48      3815008.23     10165287.58
      3815132.97     10165246.68      3816083.84     10164343.79
#Sta/Elev= 30
       0  262.82    20.4  260.52    47.5  259.45    70.4  254.13   126.5  246.42
   197.9  239.84   319.9  235.41   490.5  233.93   519.6  232.66   619.4   234.7
   655.7  232.87   676.8  233.05   682.3  234.43   697.8  235.15  1413.9  239.85
  1576.5     239  1590.7  240.49  1597.6  238.81  1604.8  239.33  1611.7  237.88
  1633.2  238.18  1894.9  245.22  1944.2  250.04  2022.3  255.37  2043.3  259.99
  2050.6   259.7  2057.5  261.28  2064.7  260.99  2071.6   262.7  2085.8  263.58
#Mann= 3 , 0 , 0
       0     .11       0   619.4     .07       0   697.8     .11       0
Bank Sta=619.4,697.8
XS Rating Curve= 0 ,0
Exp/Cntr=0.3,0.1

Chan Stop Cuts=-1
Use User Specified Reach Order=0
Composite Channel Slope=5