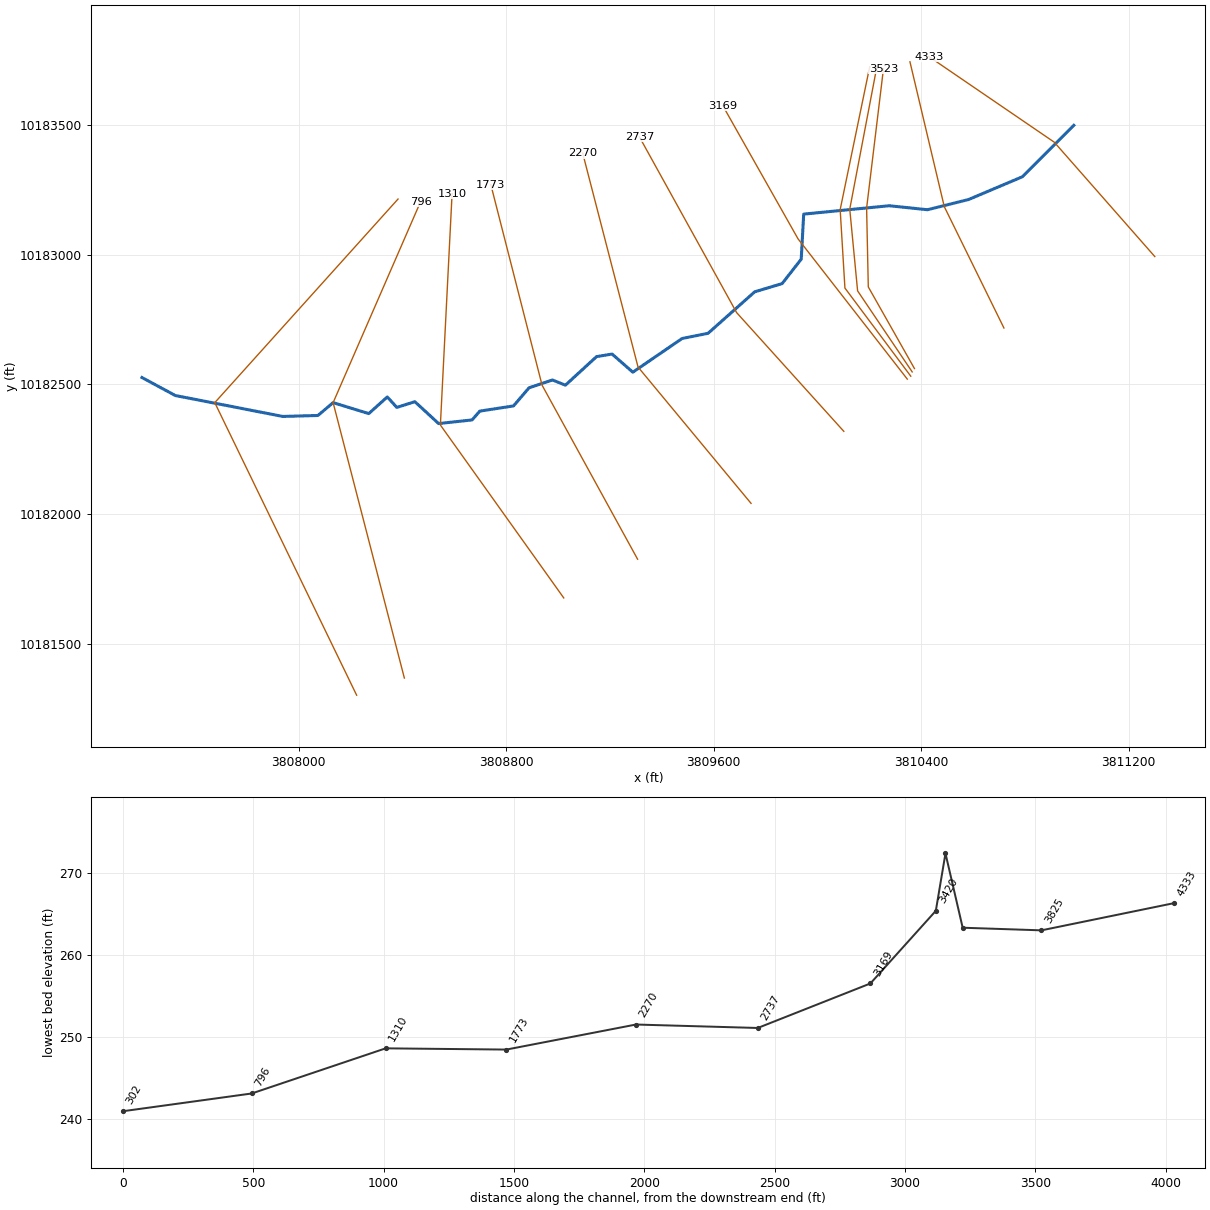
--- Conroe Lake 037.prj (project) ---

Proj Title=Conroe Lake 037 Base Level Engineering
Current Plan=p01
Default Exp/Contr=0.3,0.1
English Units
Geom File=g01
Flow File=f01
Flow File=f02
Plan File=p01
Y Axis Title=Elevation
X Axis Title(PF)=Main Channel Distance
X Axis Title(XS)=Station
BEGIN DESCRIPTION:
Conroe Lake 037
END DESCRIPTION:
DSS Export Rating Curves= 0
DSS Export Rating Curve Sorted= 0
DSS Export Volume Flow Curves= 0
DXF OffsetX= 0
DXF OffsetY= 0
DXF ScaleX= 1
DXF ScaleY= 10

--- Conroe Lake 037.p01 (plan) ---

Plan Title=Multiple Run
Short Identifier=Multiple
Geom File=g01
Flow File=f01
Subcritical Flow
K Sum by GR= 0
Std Step Tol= 0.01
Critical Tol= 0.01
Num of Std Step Trials= 20
Max Error Tol= 0.3
Flow Tol Ratio= 0.001
Split Flow NTrial= 30
Split Flow Tol= 0.02
Split Flow Ratio= 0.02
Log Output Level= 0
Friction Slope Method= 1
Unsteady Friction Slope Method= 2
Unsteady Bridges Friction Slope Method= 1
Parabolic Critical Depth
Global Vel Dist=  1 , 1 , 1
Global Log Level= 0
CheckData=True
Encroach Param= -1, 0, 0, 0
BEGIN DESCRIPTION:
Multiple Run
END DESCRIPTION:

--- Conroe Lake 037.f01 (steady flow) ---

Flow Title=Multiple
Program Version=4.10
Number of Profiles= 7
Profile Names=10-year,25-year,50-year,1pct_min,100-year,1pct_plu,500-year
River Rch & RM=Conroe Lake 037,Reach-1         ,4333
     487     648     865     381    1151    3476    2104
River Rch & RM=Conroe Lake 037,Reach-1         ,3523
     565     757    1017     449    1357    4098    2503
Boundary for River Rch & Prof#=Conroe Lake 037,Reach-1         , 1
Up Type= 0
Dn Type= 3
Dn Slope=0.01
Boundary for River Rch & Prof#=Conroe Lake 037,Reach-1         , 2
Up Type= 0
Dn Type= 3
Dn Slope=0.01
Boundary for River Rch & Prof#=Conroe Lake 037,Reach-1         , 3
Up Type= 0
Dn Type= 3
Dn Slope=0.01
Boundary for River Rch & Prof#=Conroe Lake 037,Reach-1         , 4
Up Type= 0
Dn Type= 3
Dn Slope=0.01
Boundary for River Rch & Prof#=Conroe Lake 037,Reach-1         , 5
Up Type= 0
Dn Type= 3
Dn Slope=0.01
Boundary for River Rch & Prof#=Conroe Lake 037,Reach-1         , 6
Up Type= 0
Dn Type= 3
Dn Slope=0.01
Boundary for River Rch & Prof#=Conroe Lake 037,Reach-1         , 7
Up Type= 0
Dn Type= 3
Dn Slope=0.01
DSS Import GetInterval= 0
DSS Import GetPeak= 0
DSS Import FillOption= 0

--- Conroe Lake 037.f02 (steady flow) ---

Flow Title=Orig_BLE_Flow
Program Version=4.10
Number of Profiles= 7
Profile Names=10-year,25-year,50-year,1pct_min,100-year,1pct_plu,500-year
River Rch & RM=Conroe Lake 037,Reach-1         ,4333
     487     635     752     293     885    2674    1223
River Rch & RM=Conroe Lake 037,Reach-1         ,3523
     565     742     884     346    1044    3154    1455
Boundary for River Rch & Prof#=Conroe Lake 037,Reach-1         , 1
Up Type= 0
Dn Type= 3
Dn Slope=0.005
Boundary for River Rch & Prof#=Conroe Lake 037,Reach-1         , 2
Up Type= 0
Dn Type= 3
Dn Slope=0.005
Boundary for River Rch & Prof#=Conroe Lake 037,Reach-1         , 3
Up Type= 0
Dn Type= 3
Dn Slope=0.005
Boundary for River Rch & Prof#=Conroe Lake 037,Reach-1         , 4
Up Type= 0
Dn Type= 3
Dn Slope=0.005
Boundary for River Rch & Prof#=Conroe Lake 037,Reach-1         , 5
Up Type= 0
Dn Type= 3
Dn Slope=0.005
Boundary for River Rch & Prof#=Conroe Lake 037,Reach-1         , 6
Up Type= 0
Dn Type= 3
Dn Slope=0.005
Boundary for River Rch & Prof#=Conroe Lake 037,Reach-1         , 7
Up Type= 0
Dn Type= 3
Dn Slope=0.005
DSS Import GetInterval= 0
DSS Import GetPeak= 0
DSS Import FillOption= 0

--- Conroe Lake 037.g01 (geometry) ---

Geom Title=Existing Conditions
Program Version=4.10

River Reach=Conroe Lake 037 ,Reach-1
Reach XY= 30
      3810988.42     10183498.71      3810790.09     10183300.39
      3810582.65     10183212.63      3810424.19     10183173.32
      3810276.78     10183188.72      3809947.02     10183156.45
      3809937.46     10182982.68       3809863.8     10182888.45
      3809758.23     10182856.84      3809578.23     10182696.84
      3809478.23     10182676.84      3809288.23     10182546.84
      3809208.23     10182616.84      3809148.23     10182606.84
      3809028.23     10182496.84      3808978.23     10182516.84
      3808888.23     10182486.84      3808828.23     10182416.84
      3808698.23     10182396.84      3808668.23     10182362.75
      3808539.36     10182348.82      3808447.74     10182433.12
       3808378.1     10182411.13      3808341.45     10182451.44
      3808269.98     10182387.31      3808132.55     10182429.45
      3808073.91     10182379.98       3807938.3     10182376.31
      3807524.15     10182456.94      3807395.36     10182526.35

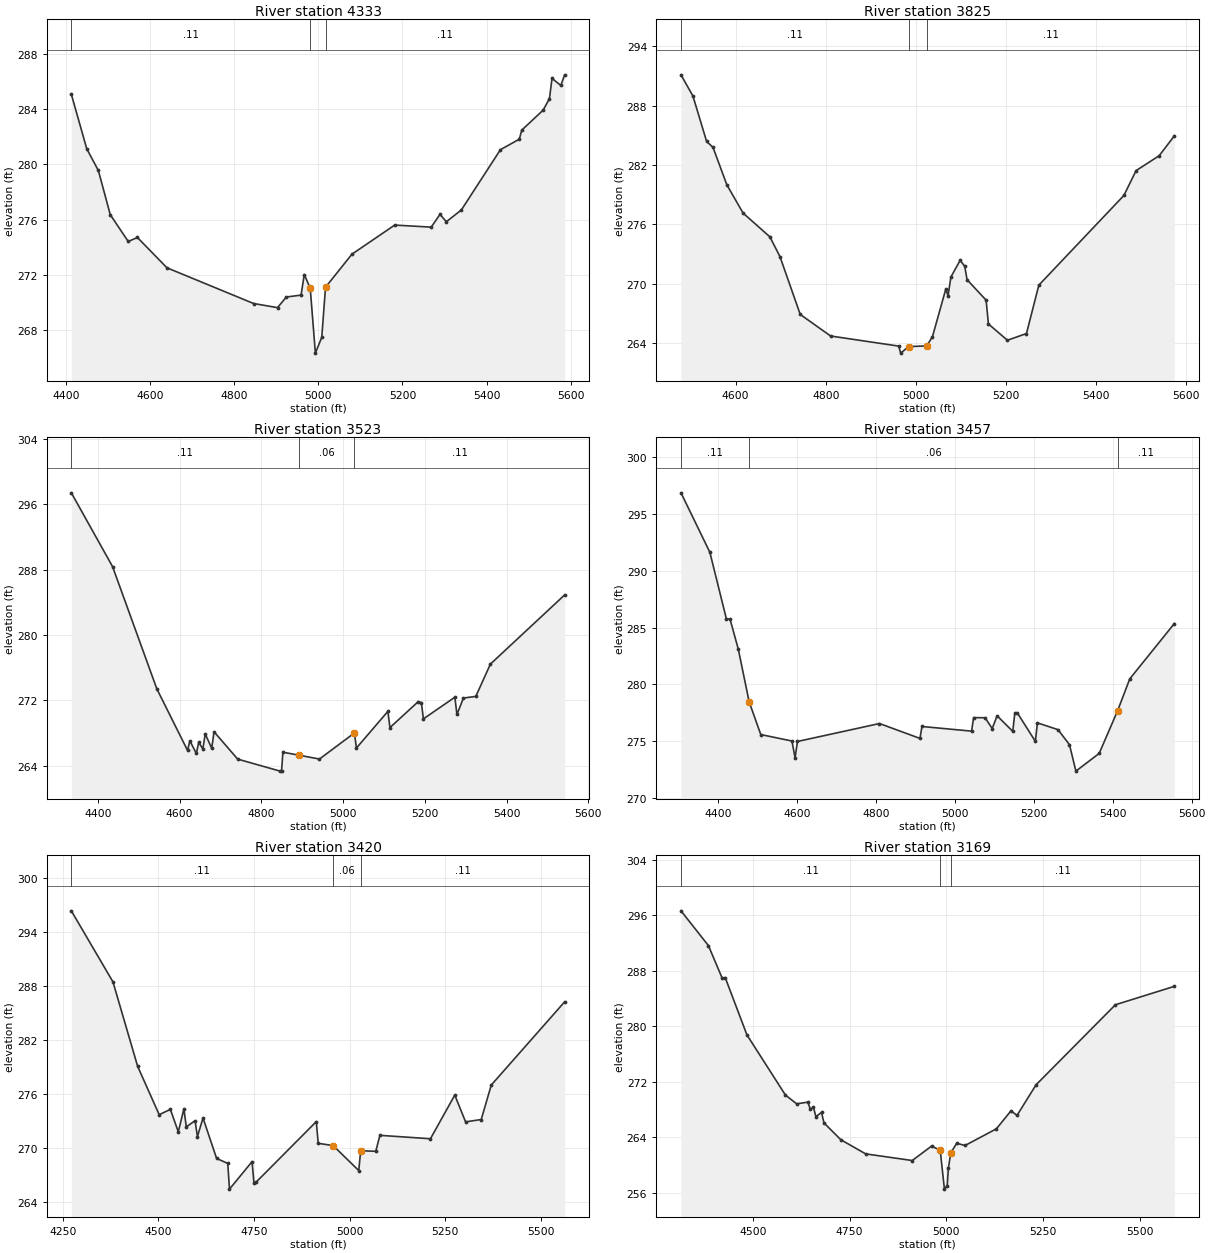
Type RM Length L Ch R = 1 ,4333    ,508,508,508
BEGIN DESCRIPTION:
Conroe Lake 037 8.5
END DESCRIPTION:
XS GIS Cut Line= 3
      3811300.72     10182992.85      3810913.19     10183433.75
      3810429.53     10183764.07
#Sta/Elev= 30
    4413  285.09  4449.6  281.14  4477.2  279.56  4505.6  276.35  4548.3  274.41
  4570.1   274.7  4640.3   272.5  4846.2  269.91  4903.1  269.61    4924  270.38
  4959.1  270.52  4966.7  272.01  4980.9  271.02  4993.1  266.31  5008.3  267.46
  5017.2  271.09  5080.1  273.49  5181.7   275.6  5268.5  275.45  5289.4  276.38
  5304.4  275.84  5340.2   276.7    5433  281.07  5477.8  281.83  5483.8  282.49
  5534.6  283.94  5549.6  284.78  5555.6  286.24  5576.6  285.73  5585.7   286.5
#Mann= 3 , 0 , 0
    4413     .11       0  4980.9     .06       0  5017.2     .11       0
#XS Ineff= 2 , 0
       0                  5289.4       0  276.38
Permanent Ineff=
       F       F
Bank Sta=4980.9,5017.2
XS Rating Curve= 0 ,0
Exp/Cntr=0.3,0.1

Type RM Length L Ch R = 1 ,3825    ,302,302,302
BEGIN DESCRIPTION:
Conroe Lake 037 8.0
END DESCRIPTION:
XS GIS Cut Line= 3
      3810719.09     10182717.28      3810489.09      10183185.2
      3810356.69     10183743.73
#Sta/Elev= 30
  4478.6  291.12  4505.1  288.98  4535.5  284.39  4549.7  283.79  4580.5     280
  4616.5  277.15    4676  274.75  4698.4  272.75  4743.4  266.91  4810.8  264.73
    4962  263.71  4966.4     263  4984.3  263.66  5024.2  263.73  5036.9  264.65
  5066.5  269.46  5071.6  268.81    5078   270.7  5098.5  272.38  5108.7  271.77
  5113.8  270.42  5156.1  268.35  5161.2  265.95  5203.4   264.3  5245.7  264.98
  5273.2  269.87    5462  278.93  5489.1  281.44  5540.4  282.95    5574  284.95
#Mann= 3 , 0 , 0
  4478.6     .11       0  4984.3     .06       0  5024.2     .11       0
Bank Sta=4984.3,5024.2
XS Rating Curve= 0 ,0
Exp/Cntr=0.3,0.1

Type RM Length L Ch R = 1 ,3523    ,66,66,66
BEGIN DESCRIPTION:
Mapping XS 7884ccec
END DESCRIPTION:
XS GIS Cut Line= 4
      3810374.04     10182561.03       3810196.1     10182875.68
      3810189.59      10183179.5       3810254.6     10183716.91
#Sta/Elev= 30
  4335.3   297.4  4436.1  288.37  4544.4   273.4  4619.5  265.86  4625.2  267.03
  4641.1  265.48  4646.9  266.84    4657  266.04  4662.8  267.87  4678.7  266.12
  4684.4  268.14  4742.2  264.79    4846  263.32  4849.5  263.32  4852.8  265.64
  4892.2  265.27  4942.2   264.8  5027.6  267.99  5032.7  266.15  5109.6  270.64
  5114.6  268.65  5183.6  271.82  5191.5   271.7  5196.5  269.72  5273.4  272.37
  5278.5  270.26  5294.4  272.27  5324.6  272.47  5360.4  276.43    5542   284.9
#Mann= 3 , 0 , 0
  4335.3     .11       0  4892.2     .06       0  5027.6     .11       0
Bank Sta=4892.2,5027.6
XS Rating Curve= 0 ,0
Exp/Cntr=0.3,0.1

Type RM Length L Ch R = 1 ,3457    ,37,37,37
BEGIN DESCRIPTION:
Mapping XS a55639db
END DESCRIPTION:
XS GIS Cut Line= 4
      3810365.39     10182547.96      3810154.87     10182860.49
      3810124.61     10183175.71      3810228.64     10183721.99
#Sta/Elev= 30
  4306.5  296.87  4379.6  291.64  4421.6  285.76  4430.6  285.77  4451.6  283.12
  4479.1  278.48  4508.6  275.59  4587.6  275.02  4595.5  273.53  4601.5  274.98
  4809.3  276.56  4911.8  275.25  4916.9   276.3  5042.6  275.89  5047.7  277.08
  5076.7  277.07  5094.8  276.12  5107.3  277.24  5146.9  275.87    5152  277.46
  5158.2  277.51  5204.2  274.99  5209.3  276.62  5261.5  276.02  5290.5   274.7
  5306.8  272.37  5365.8  273.93  5412.6   277.7  5443.2  280.49  5556.1  285.36
#Mann= 3 , 0 , 0
  4306.5     .11       0  4479.1     .06       0  5412.6     .11       0
Bank Sta=4479.1,5412.6
XS Rating Curve= 0 ,0
Exp/Cntr=0.3,0.1

Type RM Length L Ch R = 1 ,3420    ,251,251,251
BEGIN DESCRIPTION:
Mapping XS 92b52ea3
END DESCRIPTION:
XS GIS Cut Line= 4
      3810359.89     10182531.47      3810105.98     10182871.31
      3810087.68     10183173.94      3810201.55     10183724.79
#Sta/Elev= 30
  4272.6  296.37  4381.4  288.46    4446  279.05  4502.3  273.67  4531.5  274.26
  4552.3  271.76  4566.9  274.32  4573.2  272.31  4596.1     273  4602.3  271.23
  4616.9   273.3  4652.4   268.8  4681.6  268.24  4686.1  265.38  4745.1  268.44
  4750.2  266.04  4756.7   266.2  4913.1   272.9  4918.1  270.48  4957.1  270.23
  5024.1  267.45  5029.2  269.66  5068.6  269.59  5079.4  271.37  5211.5  270.99
  5275.2  275.85  5303.4  272.87  5344.3  273.13  5370.6  276.97  5562.5  286.24
#Mann= 3 , 0 , 0
  4272.6     .11       0  4957.1     .06       0  5029.2     .11       0
#XS Ineff= 2 , 0
       0  4913.1   272.9               0
Permanent Ineff=
       F       F
Bank Sta=4957.1,5029.2
XS Rating Curve= 0 ,0
Exp/Cntr=0.3,0.1

Type RM Length L Ch R = 1 ,3169    ,432,432,432
BEGIN DESCRIPTION:
Conroe Lake 037 7.0
END DESCRIPTION:
XS GIS Cut Line= 3
      3810346.49     10182520.23      3809925.16      10183061.1
       3809635.4       10183574.
#Sta/Elev= 30
  4314.4  296.62  4385.3  291.61  4420.6  286.95  4428.7     287  4484.8  278.75
  4584.3  270.08  4613.3  268.82  4642.2  269.06  4648.6  268.04  4656.7  268.32
    4663  266.97  4677.5  267.58  4683.9  266.07  4727.3  263.65  4791.5  261.61
  4911.9  260.65  4961.9  262.73  4984.2  262.12  4995.1  256.53  5002.3  257.03
  5005.2  259.51  5011.5  261.77  5026.9  263.13  5048.5  262.82  5129.4  265.22
  5166.9   267.8  5182.8  267.16  5231.9  271.56  5436.9  283.09  5589.1  285.74
#Mann= 3 , 0 , 0
  4314.4     .11       0  4984.2     .06       0  5011.5     .11       0
#XS Ineff= 2 , 0
       0  4961.9  262.73               0
Permanent Ineff=
       T       F
Bank Sta=4984.2,5011.5
XS Rating Curve= 0 ,0
Exp/Cntr=0.3,0.1

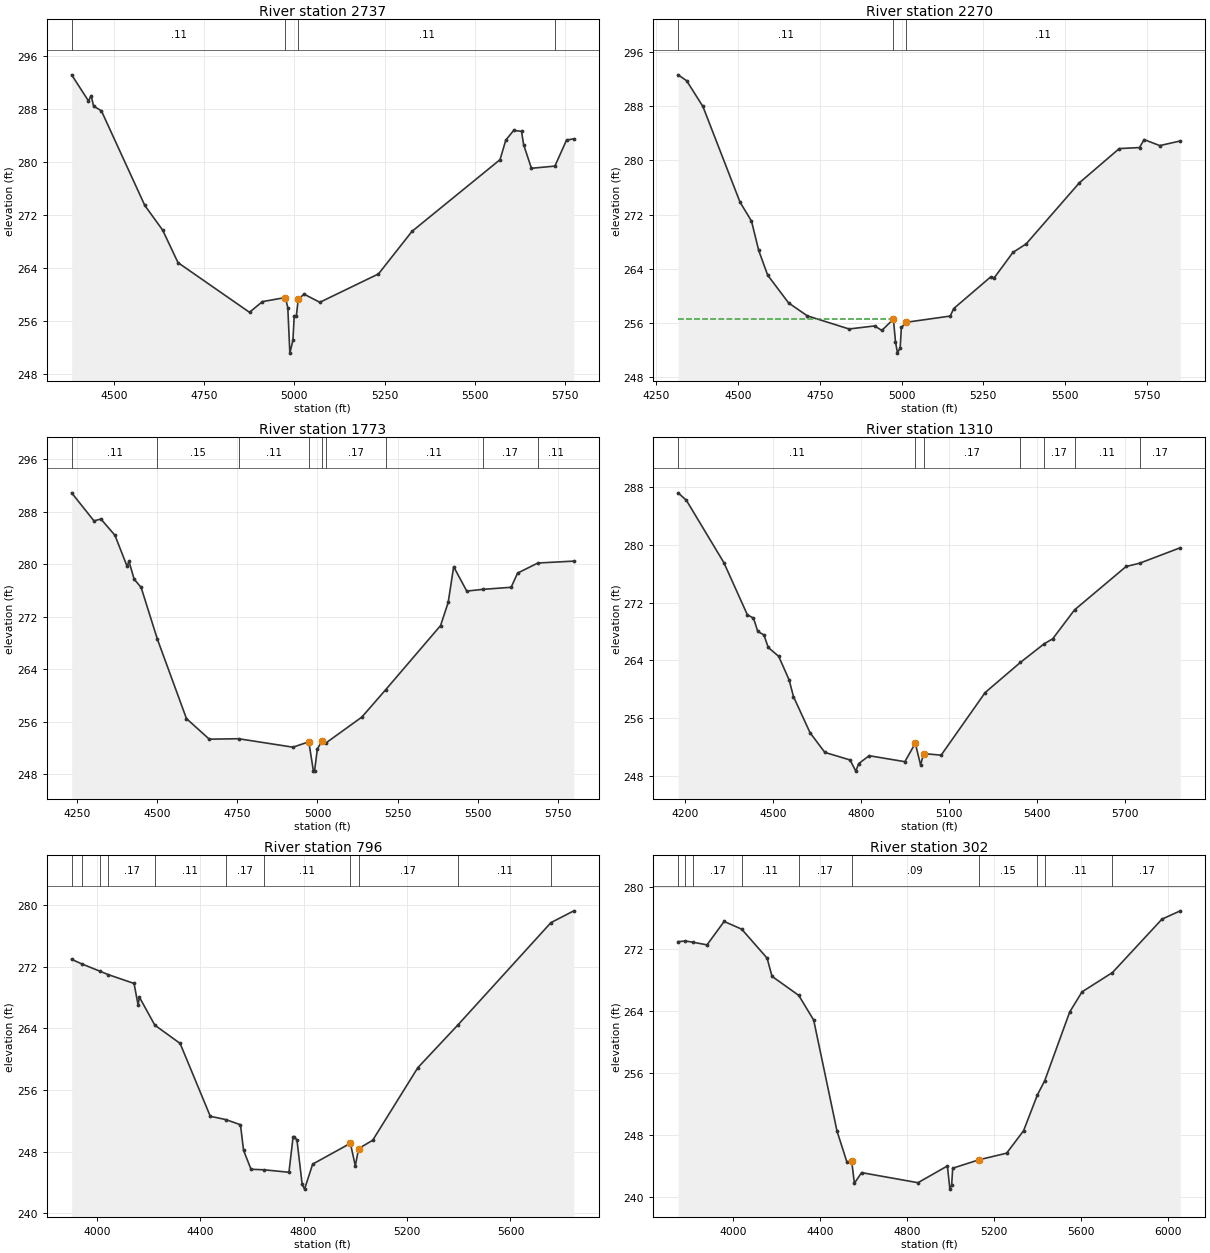
Type RM Length L Ch R = 1 ,2737    ,467,467,467
BEGIN DESCRIPTION:
Conroe Lake 037 6.0
END DESCRIPTION:
XS GIS Cut Line= 3
      3810101.68     10182318.86      3809688.23     10182776.84
      3809313.48      10183454.3
#Sta/Elev= 30
    4383   293.1  4429.6  289.16    4437  289.96  4443.8  288.38  4465.4  287.67
  4585.7  273.39  4635.1  269.67  4677.7  264.76  4875.7  257.27  4911.4  258.88
  4975.1   259.5  4981.8  257.97  4987.5  251.11    4996  253.05  4999.5  256.66
  5005.3  256.66  5010.8  259.24  5026.9  260.01  5070.4  258.78    5233  263.06
  5325.8  269.48  5569.7   280.3  5585.8  283.26  5607.5  284.71  5629.3  284.58
    5635  282.58  5656.7     279  5721.7  279.33  5754.1  283.27  5774.2  283.44
#Mann= 4 ,-1 , 0
    4383     .11       0  4975.1     .06       0  5010.8     .11       0
  5721.7     .17       0
#XS Ineff= 2 , 0
       0                  5026.9       0  260.01
Permanent Ineff=
       F       T
Bank Sta=4975.1,5010.8
XS Rating Curve= 0 ,0
Exp/Cntr=0.3,0.1

Type RM Length L Ch R = 1 ,2270    ,497,497,497
BEGIN DESCRIPTION:
Conroe Lake 037 5.0
END DESCRIPTION:
XS GIS Cut Line= 3
      3809744.04     10182041.09      3809308.23     10182566.84
      3809094.75     10183391.77
#Sta/Elev= 30
  4317.1  292.66  4343.1  291.79  4392.9  287.98  4506.2  273.86  4541.4  271.04
  4563.5   266.7  4590.8  263.06  4654.8  258.95    4712  257.04  4839.6   255.1
  4917.7  255.55  4939.9  254.88  4975.1  256.56  4981.5  253.23  4987.6  251.53
  4995.9  252.35  4999.5  255.32  5014.7  256.09    5149  257.01  5159.3  258.11
  5272.9  262.81  5283.3  262.66  5340.4  266.41    5381  267.68  5543.5   276.7
  5665.5  281.76  5727.4  281.91  5741.4  283.09  5789.4   282.2  5852.1  282.89
#Mann= 3 , 0 , 0
  4317.1     .11       0  4975.1     .07       0  5014.7     .11       0
#XS Ineff= 2 , 0
       0  4967.2  256.58               0
Permanent Ineff=
       T       F
Bank Sta=4975.1,5014.7
XS Rating Curve= 0 ,0
Exp/Cntr=0.3,0.1

Type RM Length L Ch R = 1 ,1773    ,463,463,463
BEGIN DESCRIPTION:
Conroe Lake 037 4.0
END DESCRIPTION:
XS GIS Cut Line= 3
      3809306.56     10181825.78      3808938.23     10182496.84
      3808740.59     10183270.19
#Sta/Elev= 30
  4234.5  290.91  4303.9  286.64  4325.7  286.91  4369.3  284.44  4407.2  279.69
  4412.9  280.49    4429  277.75  4450.8  276.49  4501.3  268.62    4592  256.49
  4663.1  253.35  4754.2  253.42  4923.7  252.13    4973  252.95  4987.3  248.48
  4990.8  248.48  4999.6  251.87  5014.7  253.11  5026.1  252.77  5138.1  256.72
  5212.8  260.92  5383.2  270.67  5406.9  274.19    5424  279.64  5464.8  275.93
  5514.2  276.19    5603  276.51    5623  278.67  5686.2  280.21  5798.2   280.5
#Mann= 9 ,-1 , 0
  4234.5     .11       0  4501.3     .15       0  4754.2     .11       0
    4973     .07       0  5014.7     .11       0  5026.1     .17       0
  5212.8     .11       0  5514.2     .17       0  5686.2     .11       0
Bank Sta=4973,5014.7
XS Rating Curve= 0 ,0
Exp/Cntr=0.3,0.1

Type RM Length L Ch R = 1 ,1310    ,514,514,514
BEGIN DESCRIPTION:
Conroe Lake 037 3.0
END DESCRIPTION:
XS GIS Cut Line= 3
      3809021.82      10181676.5      3808546.14     10182343.15
      3808591.28     10183235.55
#Sta/Elev= 30
  4177.1  287.25  4205.5   286.2  4333.3  277.55  4413.2  270.33  4434.1  269.86
  4448.8  268.02  4469.7  267.53  4484.5  265.79  4520.1  264.56  4555.7  261.28
  4570.5  258.97    4627  253.96  4677.4  251.23  4763.5  250.18  4782.9  248.63
    4793  249.68  4828.6  250.77  4950.3  249.94  4985.9   252.5    5004  249.47
    5014  251.06  5074.1  250.85  5224.3  259.54  5344.1  263.71  5424.7  266.28
  5454.6     267    5529  271.01  5704.9  277.03  5750.8  277.48  5889.6  279.63
#Mann= 7 ,-1 , 0
  4177.1     .11       0  4985.9     .09       0    5014     .17       0
  5344.1     .11       0  5424.7     .17       0    5529     .11       0
  5750.8     .17       0
#XS Ineff= 2 , 0
       0  4985.9   252.5               0
Permanent Ineff=
       T       F
Bank Sta=4985.9,5014
XS Rating Curve= 0 ,0
Exp/Cntr=0.3,0.1

Type RM Length L Ch R = 1 ,796     ,494,494,494
BEGIN DESCRIPTION:
Conroe Lake 037 2.0
END DESCRIPTION:
XS GIS Cut Line= 3
      3808407.24     10181367.51      3808132.55     10182429.45
      3808469.74     10183204.26
#Sta/Elev= 30
  3903.1  272.97  3943.6  272.36  4013.2  271.42  4044.1  270.99  4144.4  269.84
    4160  267.05  4165.2  268.05  4224.6  264.43  4322.5  262.05  4439.2  252.59
  4499.3  252.16  4555.9  251.49  4567.8  248.17  4596.6  245.71  4647.2  245.64
  4743.4  245.32  4759.1  249.84  4764.2  249.91  4774.4   249.5  4794.5  243.74
  4803.7  243.13  4835.1  246.38    4981  249.08    5000  246.15  5012.7  248.39
  5067.2  249.48  5241.7   258.9  5397.2  264.47  5756.5  277.74    5845  279.27
#Mann= 11 ,-1 , 0
  3903.1     .11       0  3943.6     .17       0  4013.2     .11       0
  4044.1     .17       0  4224.6     .11       0  4499.3     .17       0
  4647.2     .11       0    4981     .09       0  5012.7     .17       0
  5397.2     .11       0  5756.5     .17       0
#XS Ineff= 2 , 0
       0    4981  249.08               0
Permanent Ineff=
       T       F
Bank Sta=4981,5012.7
XS Rating Curve= 0 ,0
Exp/Cntr=0.3,0.1

Type RM Length L Ch R = 1 ,302     ,0,0,0
BEGIN DESCRIPTION:
Conroe Lake 037 1.0
END DESCRIPTION:
XS GIS Cut Line= 3
      3808223.22     10181301.48      3807676.25     10182429.45
      3808382.87      10183214.6
#Sta/Elev= 30
  3746.4  272.89  3779.7  272.98    3815  272.82  3879.3  272.48  3958.1   275.5
  4039.1   274.5  4155.7  270.77  4178.3  268.42  4301.4  265.96    4370  262.77
  4477.3  248.45  4522.4   244.5    4545  244.55  4557.2  241.72  4590.1   243.1
  4849.6   241.8    4985  243.96  4996.4  240.97  5004.5  241.47  5009.4  243.67
  5129.7  244.75  5257.5  245.61  5335.3   248.5  5399.1  253.13    5433  254.98
  5547.5  263.82  5604.3  266.42  5744.3  268.91  5972.1   275.8  6056.3  276.87
#Mann= 10 ,-1 , 0
  3746.4     .17       0  3779.7     .11       0    3815     .17       0
  4039.1     .11       0  4301.4     .17       0    4545     .09       0
  5129.7     .15       0  5399.1     .17       0    5433     .11       0
  5744.3     .17       0
Bank Sta=4545,5129.7
XS Rating Curve= 0 ,0
Exp/Cntr=0.3,0.1

Chan Stop Cuts=-1
Use User Specified Reach Order=0
Composite Channel Slope=5