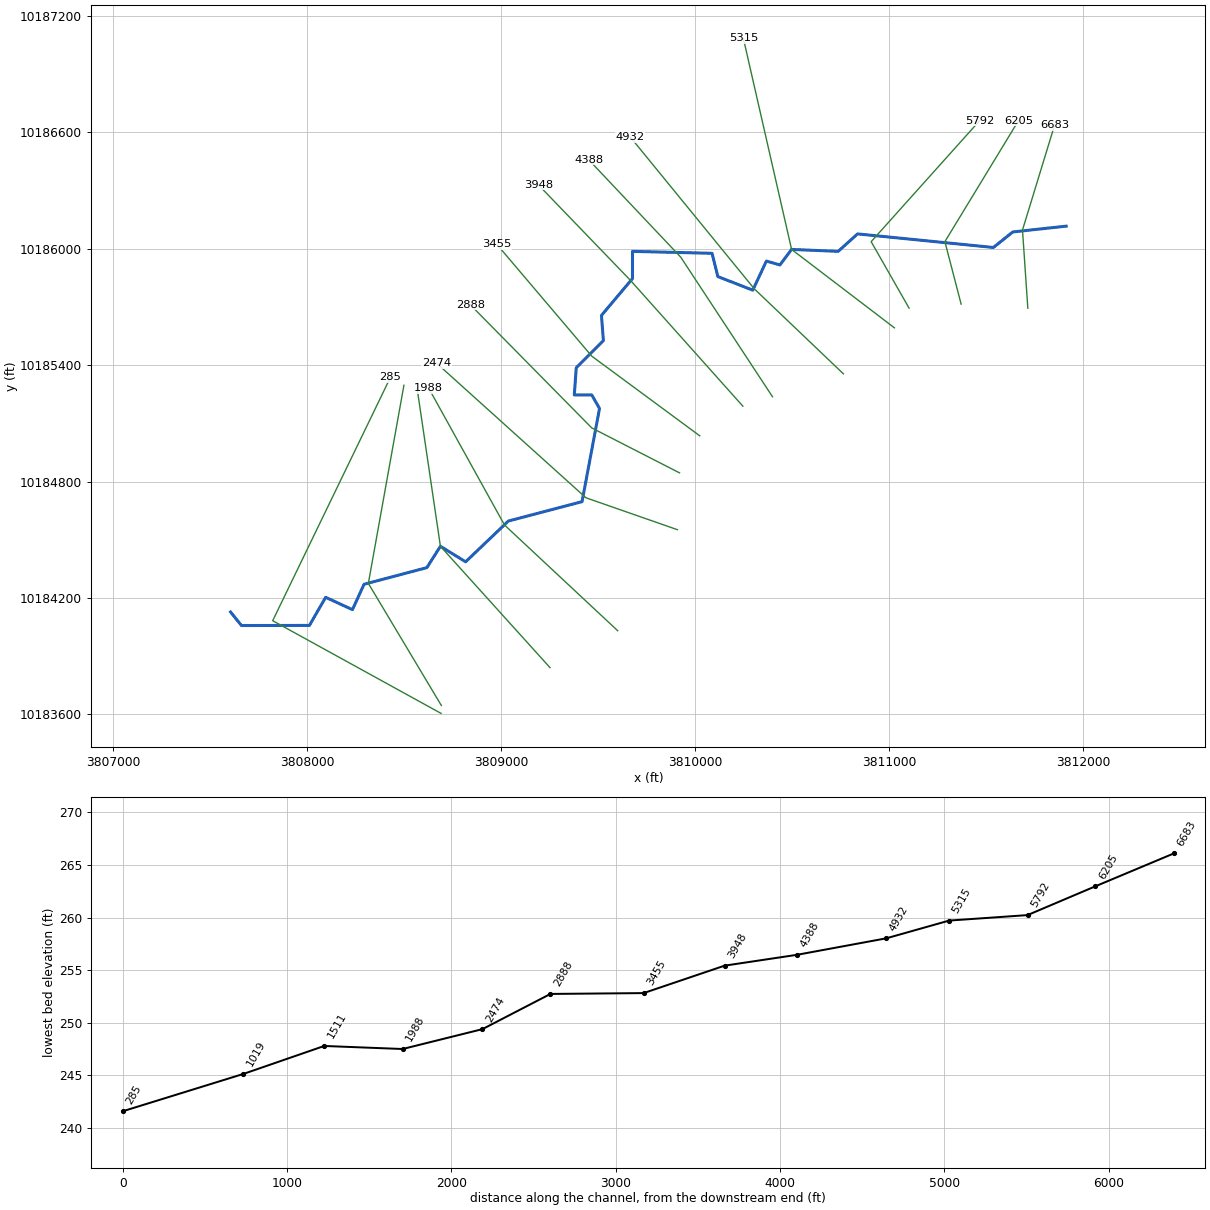
--- Conroe Lake 038.prj (project) ---

Proj Title=Conroe Lake 038 Base Level Engineering
Current Plan=p01
Default Exp/Contr=0.3,0.1
English Units
Geom File=g01
Flow File=f01
Flow File=f02
Plan File=p01
Y Axis Title=Elevation
X Axis Title(PF)=Main Channel Distance
X Axis Title(XS)=Station
BEGIN DESCRIPTION:
Conroe Lake 038
END DESCRIPTION:
DSS File=dss
DSS Export Rating Curves= 0
DSS Export Rating Curve Sorted= 0
DSS Export Volume Flow Curves= 0
DXF OffsetX= 0
DXF OffsetY= 0
DXF ScaleX= 1
DXF ScaleY= 10

--- Conroe Lake 038.p01 (plan) ---

Plan Title=Multiple Run
Program Version=4.10
Short Identifier=Multiple Run
Geom File=g01
Flow File=f01
Subcritical Flow
K Sum by GR= 0
Std Step Tol= 0.01
Critical Tol= 0.01
Num of Std Step Trials= 20
Max Error Tol= 0.3
Flow Tol Ratio= 0.001
Split Flow NTrial= 30
Split Flow Tol= 0.02
Split Flow Ratio= 0.02
Log Output Level= 0
Friction Slope Method= 1
Unsteady Friction Slope Method= 2
Unsteady Bridges Friction Slope Method= 1
Parabolic Critical Depth
Global Vel Dist= 1 , 1 , 1
Global Log Level= 0
CheckData=True
Encroach Param=-1 ,0,0, 0
BEGIN DESCRIPTION:
Multiple Run
END DESCRIPTION:
Computation Interval=1HOUR
Output Interval=1HOUR
Run HTab= 0
Run UNet= 0
Run PostProcess= 0
Run WQNet= 0
UNET Theta= 1
UNET Theta Warmup= 1
UNET ZTol= 0.02
UNET ZSATol= 0.05
UNET MxIter= 20
UNET MaxInSteps= 0
UNET DtIC= 0
UNET DtMin= 0
UNET MaxCRTS= 20
UNET WFStab= 2
UNET SFStab= 1
UNET WFX= 1
UNET SFX= 1
UNET DSS MLevel= 4
UNET DZMax Abort= 100
UNET Convert EG Bridges= 0
UNET Use Existing IB Tables=-1
UNET Froude Reduction=False
UNET Froude Limit= 1
UNET Froude Power= 10
UNET Time Slicing=0,0, 5
UNET Junction Losses=0
Instantaneous Interval=1HOUR
DSS File=dss
Write IC File= 0
Write IC File at Sim End=0
Echo Input=False
Echo Parameters=False
Echo Output=False
Write Detailed= 0
WQ AD Non Conservative
WQ ULTIMATE=-1
WQ Max Comp Step=1HOUR
WQ Output Interval=15MIN
WQ Output Selected Increments= 0
WQ Output face flow=0
WQ Output face velocity=0
WQ Output face area=0
WQ Output face dispersion=0
WQ Output cell volume=0
WQ Output cell surface area=0
WQ Output cell continuity=0
WQ Output cumulative cell continuity=0
WQ Output face conc=0
WQ Output face dconc_dx=0
WQ Output face courant=0
WQ Output face peclet=0
WQ Output face adv mass=0
WQ Output face disp mass=0
WQ Output cell mass=0
WQ Output cell source sink temp=0
WQ Output cell source sink nsm=0
WQ Output MaxMinRange=-1
WQ Daily Max Min Mean=-1
WQ Daily Range=0
WQ Daily Time=0
WQ Create Restart=0
WQ Fixed Restart=0
WQ System Summary=0
WQ Use Fixed Temperature=0
Sorting and Armoring Iterations= 10
XS Update Threshold= 0.02
Hydraulics Update Threshold= 0.02
Energy Slope Method= 1
Volume Change Method= 0
XS Weighting Method= 0
Number of US Weighted Cross Sections= 1
Number of DS Weighted Cross Sections= 1
Upstream XS Weight=0.25
Main XS Weight=0.5
Downstream XS Weight=0.25
Number of DS XS's Weighted with US Boundary= 1
Upstream Boundary Weight= 1
Weight of XSs Associated with US Boundary= 0
Number of US XS's Weighted with DS Boundary= 1
Downstream Boundary Weight= 0.5
Weight of XSs Associated with DS Boundary= 0.5
Sediment Output Level= 4
Mass or Volume Output= 0
Output Increment Type= 1
Profile and TS Output Increment= 10
XS Output Flag= 0
XS Output Increment= 10
Disregard all LS=0
Disregard all Conn=0
Disregard all Breaches=0
Disregard all Pumps=0

--- Conroe Lake 038.f01 (steady flow) ---

Flow Title=Multiple
Program Version=4.10
Number of Profiles= 7
Profile Names=10-year,25-year,50-year,1pct_min,100-year,1pct_plu,500-year
River Rch & RM=Conroe Lake 038,Reach-1         ,6683
     559     752    1014     450    1360    4107    2528
River Rch & RM=Conroe Lake 038,Reach-1         ,6205
     829    1138    1554     698    2107    6363    4004
River Rch & RM=Conroe Lake 038,Reach-1         ,2474
     816    1115    1516     678    2048    6185    3860
Boundary for River Rch & Prof#=Conroe Lake 038,Reach-1         , 1
Up Type= 0
Dn Type= 3
Dn Slope=0.005
Boundary for River Rch & Prof#=Conroe Lake 038,Reach-1         , 2
Up Type= 0
Dn Type= 3
Dn Slope=0.005
Boundary for River Rch & Prof#=Conroe Lake 038,Reach-1         , 3
Up Type= 0
Dn Type= 3
Dn Slope=0.005
Boundary for River Rch & Prof#=Conroe Lake 038,Reach-1         , 4
Up Type= 0
Dn Type= 3
Dn Slope=0.005
Boundary for River Rch & Prof#=Conroe Lake 038,Reach-1         , 5
Up Type= 0
Dn Type= 3
Dn Slope=0.005
Boundary for River Rch & Prof#=Conroe Lake 038,Reach-1         , 6
Up Type= 0
Dn Type= 3
Dn Slope=0.005
Boundary for River Rch & Prof#=Conroe Lake 038,Reach-1         , 7
Up Type= 0
Dn Type= 3
Dn Slope=0.005
DSS Import GetInterval= 0
DSS Import GetPeak= 0
DSS Import FillOption= 0

--- Conroe Lake 038.f02 (steady flow) ---

Flow Title=Orig_BLE_Flow
Program Version=4.10
Number of Profiles= 7
Profile Names=10-year,25-year,50-year,1pct_min,100-year,1pct_plu,500-year
River Rch & RM=Conroe Lake 038,Reach-1         ,6683
     559     737     882     347    1046    3160    1470
River Rch & RM=Conroe Lake 038,Reach-1         ,6205
     829    1116    1351     537    1621    4894    2328
River Rch & RM=Conroe Lake 038,Reach-1         ,2474
     816    1093    1318     522    1575    4756    2244
Boundary for River Rch & Prof#=Conroe Lake 038,Reach-1         , 1
Up Type= 0
Dn Type= 3
Dn Slope=0.005
Boundary for River Rch & Prof#=Conroe Lake 038,Reach-1         , 2
Up Type= 0
Dn Type= 3
Dn Slope=0.005
Boundary for River Rch & Prof#=Conroe Lake 038,Reach-1         , 3
Up Type= 0
Dn Type= 3
Dn Slope=0.005
Boundary for River Rch & Prof#=Conroe Lake 038,Reach-1         , 4
Up Type= 0
Dn Type= 3
Dn Slope=0.005
Boundary for River Rch & Prof#=Conroe Lake 038,Reach-1         , 5
Up Type= 0
Dn Type= 3
Dn Slope=0.005
Boundary for River Rch & Prof#=Conroe Lake 038,Reach-1         , 6
Up Type= 0
Dn Type= 3
Dn Slope=0.005
Boundary for River Rch & Prof#=Conroe Lake 038,Reach-1         , 7
Up Type= 0
Dn Type= 3
Dn Slope=0.005
DSS Import GetInterval= 0
DSS Import GetPeak= 0
DSS Import FillOption= 0

--- Conroe Lake 038.g01 (geometry) ---

Geom Title=Existing Conditions
Program Version=4.10

River Reach=Conroe Lake 038 ,Reach-1
Reach XY= 30
      3811913.23     10186116.84      3811638.23     10186086.84
      3811538.23     10186006.84      3810838.23     10186076.84
      3810738.23     10185986.84      3810498.23     10185996.84
      3810438.23     10185916.84      3810368.23     10185936.84
      3810298.23     10185786.84      3810118.23     10185856.84
      3810088.23     10185976.84      3809678.23     10185986.84
      3809678.23     10185846.84      3809518.23     10185656.84
      3809528.23     10185526.84      3809388.23     10185386.84
      3809378.23     10185246.84      3809468.23     10185246.84
      3809508.23     10185176.84      3809418.23     10184696.84
      3809038.23     10184596.84      3808818.23     10184386.84
      3808688.23     10184466.84      3808618.23     10184356.84
      3808294.66     10184271.11       3808234.8     10184140.18
       3808096.7     10184203.81      3808013.07     10184058.92
      3807662.71     10184058.43      3807606.62     10184128.36

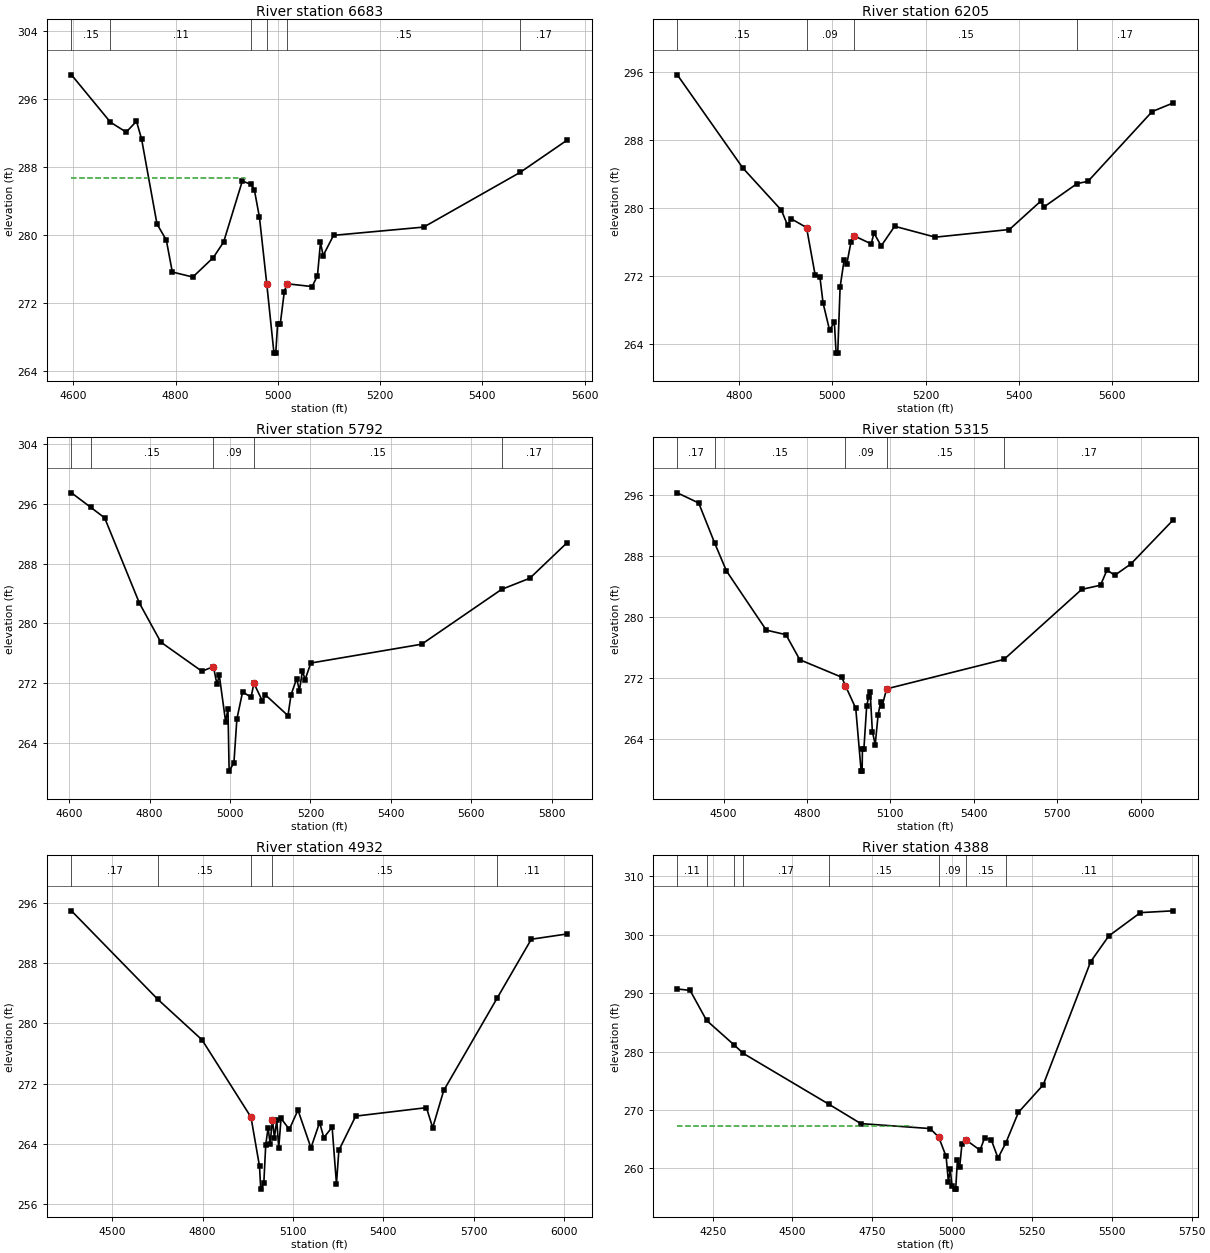
Type RM Length L Ch R = 1 ,6683    ,478,478,478
BEGIN DESCRIPTION:
Conroe Lake 038 14.0
END DESCRIPTION:
XS GIS Cut Line= 3
      3811715.72     10185694.18      3811688.23     10186096.84
      3811853.72      10186637.8
#Sta/Elev= 30
  4596.4   298.8  4672.7  293.23  4703.5  292.07  4723.6  293.34  4733.6  291.25
  4763.7  281.28    4782  279.37  4793.7  275.63  4833.8  275.04  4873.9  277.33
    4894  279.15  4930.6  286.32  4947.6  285.93  4954.1   285.3  4964.1  282.07
 4978.37  274.27  4992.5   266.1    4996   266.1  4999.6   269.5  5004.8   269.5
  5012.7  273.31    5018  274.25  5067.2  273.92  5077.6  275.21  5083.5  279.11
  5088.7  277.56    5109  279.94  5285.4  280.91  5474.1  287.34  5565.7  291.12
#Mann= 6 ,-1 , 0
  4596.4     .15       0  4672.7     .11       0  4947.6     .15       0
 4978.37     .09       0    5018     .15       0  5474.1     .17       0
#XS Ineff= 2 , 0
       0  4935.6  286.62               0
Permanent Ineff=
       F       F
Bank Sta=4978.37,5018
XS Rating Curve= 0 ,0
Exp/Cntr=0.3,0.1

Type RM Length L Ch R = 1 ,6205    ,413,413,413
BEGIN DESCRIPTION:
Conroe Lake 038 13.0
END DESCRIPTION:
XS GIS Cut Line= 3
      3811371.98     10185714.96      3811288.23     10186036.84
      3811667.85     10186661.07
#Sta/Elev= 30
  4667.4  295.68    4808  284.73  4890.7  279.77  4904.2  277.98  4911.4  278.77
  4944.7  277.73    4963  272.19  4973.4  271.91  4980.1  268.87    4994  265.69
  5004.4  266.58  5008.1  262.97  5011.6  262.97  5016.7  270.73  5025.3   273.9
  5031.2  273.49  5040.1  276.04  5046.6  276.76  5083.4  275.81  5089.3  277.09
  5104.8  275.57  5133.7  277.88    5221   276.6  5379.9   277.5  5447.7  280.86
  5453.5  280.13  5525.2   282.9  5548.5  283.16  5686.1  291.36  5730.6  292.36
#Mann= 4 ,-1 , 0
  4667.4     .15       0  4944.7     .09       0  5046.6     .15       0
  5525.2     .17       0
Bank Sta=4944.7,5046.6
XS Rating Curve= 0 ,0
Exp/Cntr=0.3,0.1

Type RM Length L Ch R = 1 ,5792    ,477,477,477
BEGIN DESCRIPTION:
Conroe Lake 038 12.0
END DESCRIPTION:
XS GIS Cut Line= 3
      3811103.72     10185694.19      3810908.23     10186036.84
      3811467.88     10186661.11
#Sta/Elev= 30
  4605.5  297.46    4653  295.54  4688.1  294.11  4774.6   282.7  4827.8  277.49
  4930.1  273.59  4958.8  274.21  4967.5  271.83  4973.3  273.06  4989.1  266.83
  4994.9  268.57  4997.8  260.23  5009.7  261.35  5017.1  267.21  5031.4  270.85
  5052.3   270.1  5059.4  271.98  5080.7   269.6  5087.4  270.46  5144.2  267.65
  5151.7  270.42  5165.9  272.62  5172.6  270.98  5180.1  273.64  5186.8  272.47
    5201  274.69  5476.9  277.21  5675.5  284.54    5746  286.04  5838.4  290.78
#Mann= 5 ,-1 , 0
  4605.5     .17       0    4653     .15       0  4958.8     .09       0
  5059.4     .15       0  5675.5     .17       0
#XS Ineff= 2 , 0
       0  4973.3  273.06  5180.1       0  273.64
Permanent Ineff=
       F       F
Bank Sta=4958.8,5059.4
XS Rating Curve= 0 ,0
Exp/Cntr=0.3,0.1

Type RM Length L Ch R = 1 ,5315    ,383,383,383
BEGIN DESCRIPTION:
Conroe Lake 038 11.0
END DESCRIPTION:
XS GIS Cut Line= 3
      3811028.24     10185592.57      3810498.23     10185996.84
      3810249.57     10187084.79
#Sta/Elev= 30
  4333.4  296.34  4410.4     295  4467.4  289.77  4510.2  286.06  4653.5  278.27
  4724.2  277.67  4774.1  274.37    4925  272.07  4938.3  270.94  4975.3  267.98
  4994.7  259.71  4998.2  259.71  4999.4  262.67  5004.7  262.67  5014.6  268.27
  5021.9  269.53  5027.1   270.1  5035.1  264.92  5045.4  263.21  5055.6  267.09
  5064.9  268.84    5070  268.26  5086.4  270.54  5508.4  274.41  5788.1  283.63
  5855.7  284.18  5879.1  286.18    5907  285.49    5965  286.98    6116  292.73
#Mann= 5 ,-1 , 0
  4333.4     .17       0  4467.4     .15       0  4938.3     .09       0
  5086.4     .15       0  5508.4     .17       0
#XS Ineff= 2 , 0
       0                  5027.1       0   270.1
Permanent Ineff=
       F       F
Bank Sta=4938.3,5086.4
XS Rating Curve= 0 ,0
Exp/Cntr=0.3,0.1

Type RM Length L Ch R = 1 ,4932    ,544,544,544
BEGIN DESCRIPTION:
Conroe Lake 038 10.0
END DESCRIPTION:
XS GIS Cut Line= 3
       3810765.2     10185355.61      3810305.53     10185794.15
      3809666.61      10186576.5
#Sta/Elev= 30
  4364.7  294.95  4651.3  283.21  4798.2  277.83  4960.8  267.57  4989.1  261.05
  4993.2  258.02  5003.4  258.82  5009.8  263.93  5017.7  266.16  5024.2  264.05
  5032.1  267.23  5038.5  264.86  5046.4  267.19  5052.9  263.47  5060.6   267.4
  5088.1  265.95  5116.8  268.51  5159.9   263.5  5188.6  266.86  5202.6  264.85
  5230.2  266.24  5244.6  258.72  5252.5  263.16  5308.5  267.71  5543.3  268.83
  5564.1  266.17  5600.7  271.11  5777.9  283.35  5891.5  291.18  6010.1  291.88
#Mann= 5 ,-1 , 0
  4364.7     .17       0  4651.3     .15       0  4960.8     .09       0
  5032.1     .15       0  5777.9     .11       0
Bank Sta=4960.8,5032.1
XS Rating Curve= 0 ,0
Exp/Cntr=0.3,0.1

Type RM Length L Ch R = 1 ,4388    ,440,440,440
BEGIN DESCRIPTION:
Conroe Lake 038 9.0
END DESCRIPTION:
XS GIS Cut Line= 3
      3810399.73     10185237.62      3809926.96     10185956.84
      3809452.32     10186459.31
#Sta/Elev= 30
  4139.3  290.72  4179.3  290.48  4231.1  285.33  4315.8  281.21  4345.9  279.69
  4614.5  270.97    4714  267.67    4931  266.82    4958  265.35  4981.1  262.04
  4988.2  257.74  4994.2  259.82  4999.5  257.03  5007.6  256.45  5011.1  256.45
  5016.6  261.45  5023.5  260.19  5030.8  264.25  5044.9   264.8  5087.4  263.12
  5101.6  265.21  5122.6  264.89  5143.6  261.77  5168.2  264.37  5207.6   269.6
  5285.2   274.3  5433.7  295.39  5490.4  299.79  5589.5  303.79  5691.2   304.1
#Mann= 8 ,-1 , 0
  4139.3     .11       0  4231.1     .17       0  4315.8     .11       0
  4345.9     .17       0  4614.5     .15       0    4958     .09       0
  5044.9     .15       0  5168.2     .11       0
#XS Ineff= 2 , 0
       0  4873.4  267.21               0
Permanent Ineff=
       F       F
Bank Sta=4958,5044.9
XS Rating Curve= 0 ,0
Exp/Cntr=0.3,0.1

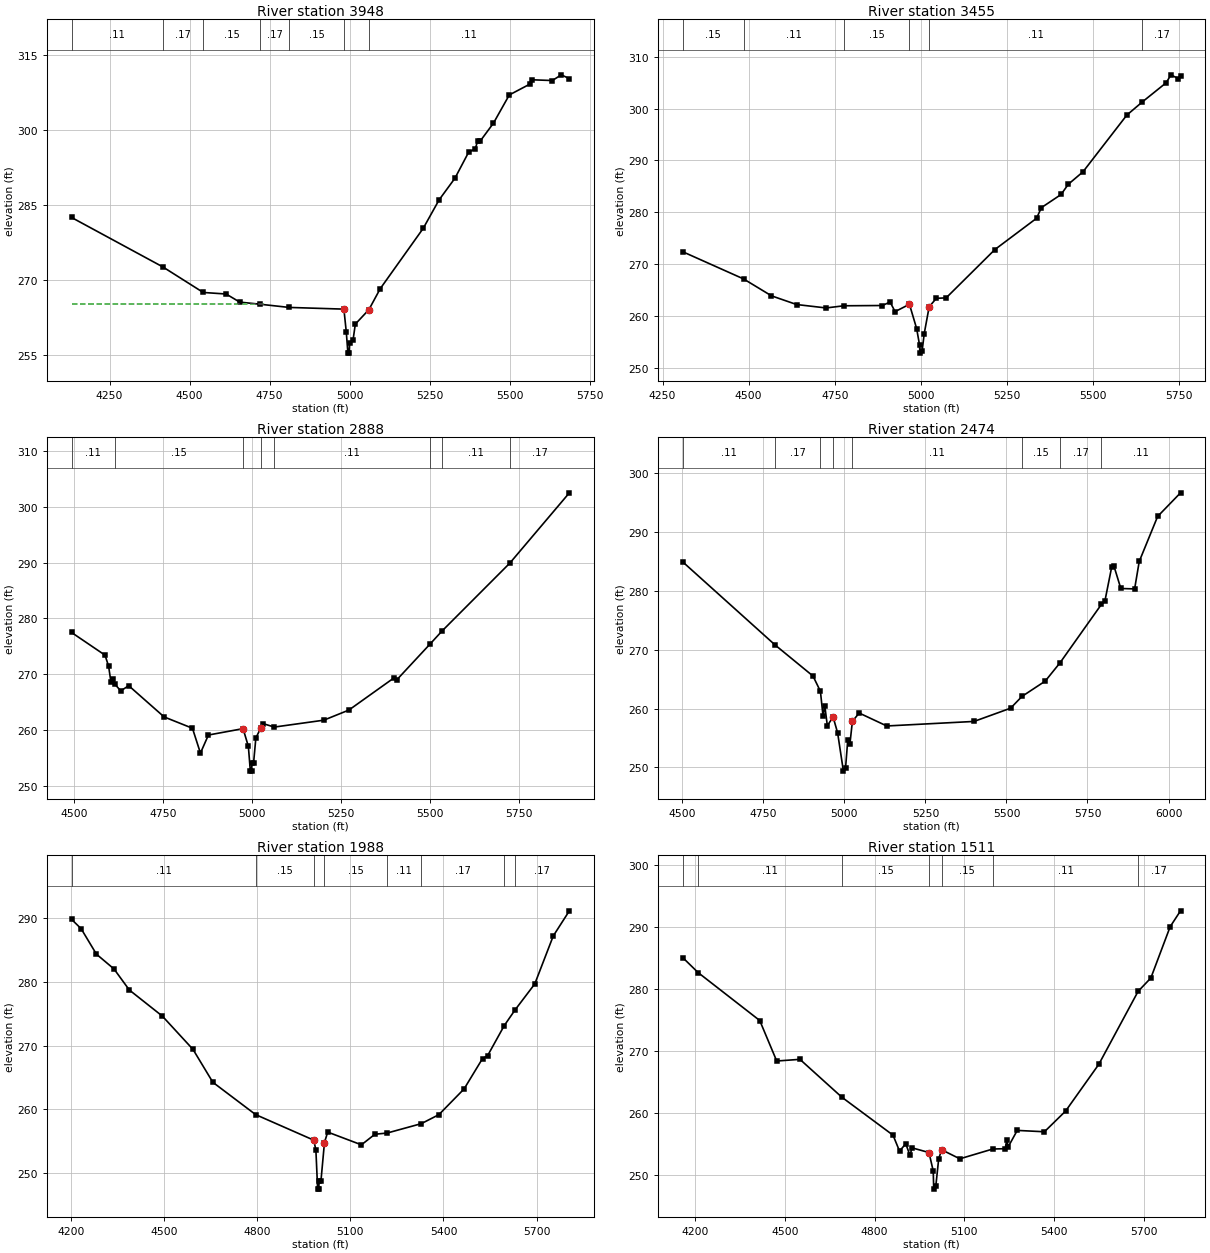
Type RM Length L Ch R = 1 ,3948    ,493,493,493
BEGIN DESCRIPTION:
Conroe Lake 038 8.0
END DESCRIPTION:
XS GIS Cut Line= 3
      3810246.96       10185189.      3809668.23     10185836.84
      3809192.14      10186330.6
#Sta/Elev= 30
  4131.3  282.52  4416.2  272.65  4542.5  267.54    4614  267.23  4656.6  265.61
  4719.8  265.19  4810.9  264.55  4981.8  264.21  4989.3  259.61  4994.3  255.42
  4997.8  255.42  4999.5  257.38  5010.3  258.01  5017.5  261.22  5059.9  264.11
  5095.2  268.29  5229.5  280.35  5279.1  286.04  5328.5  290.36    5371  295.52
  5392.3  296.28  5399.3  297.77  5406.5   297.7  5448.9  301.37  5498.3     307
  5561.8  309.14    5569  310.03  5632.6  309.88  5660.9  311.02  5685.9  310.25
#Mann= 7 ,-1 , 0
  4131.3     .11       0  4416.2     .17       0  4542.5     .15       0
  4719.8     .17       0  4810.9     .15       0  4981.8     .09       0
  5059.9     .11       0
#XS Ineff= 2 , 0
       0  4734.3  265.28               0
Permanent Ineff=
       F       F
Bank Sta=4981.8,5059.9
XS Rating Curve= 0 ,0
Exp/Cntr=0.3,0.1

Type RM Length L Ch R = 1 ,3455    ,567,567,567
BEGIN DESCRIPTION:
Conroe Lake 038 7.0
END DESCRIPTION:
XS GIS Cut Line= 3
      3810024.74     10185036.22      3809468.23     10185446.84
      3808979.63      10186022.3
#Sta/Elev= 30
  4308.4  272.38  4485.3  267.13  4566.3  263.87  4639.4  262.19    4725  261.53
  4776.8  261.95  4888.6     262  4910.9  262.68  4925.5  260.82  4967.2  262.24
  4988.1  257.55  4996.5  254.41  4997.6  252.81  5004.2  253.31  5010.2  256.59
  5024.5  261.75  5045.3  263.39  5073.9  263.48  5215.6  272.81  5336.4  278.83
  5350.7   280.9  5407.8  283.43  5428.7   285.4  5471.5  287.81  5598.9  298.76
  5644.3  301.32  5713.2     305  5727.1  306.53  5748.3  305.79  5754.9   306.4
#Mann= 6 ,-1 , 0
  4308.4     .15       0  4485.3     .11       0  4776.8     .15       0
  4967.2     .09       0  5024.5     .11       0  5644.3     .17       0
Bank Sta=4967.2,5024.5
XS Rating Curve= 0 ,0
Exp/Cntr=0.3,0.1

Type RM Length L Ch R = 1 ,2888    ,414,414,414
BEGIN DESCRIPTION:
Conroe Lake 038 6.0
END DESCRIPTION:
XS GIS Cut Line= 3
      3809920.59     10184845.24      3809468.23     10185076.84
      3808841.76     10185712.24
#Sta/Elev= 30
  4491.8   277.5  4585.9  273.45    4596  271.49  4602.5  268.69  4608.1  269.27
  4613.5  268.27  4630.3  267.06  4652.5     268  4752.3  262.41  4831.9  260.39
  4854.4  255.95  4876.8  259.18  4974.3  260.32  4989.2  257.16  4994.8  252.73
  4998.3  252.73  4999.2  254.14  5003.8  254.14  5010.3  258.65  5024.5  260.48
  5031.6   261.2  5062.1   260.6  5201.3  261.83    5272  263.64  5399.2   269.4
  5406.3  269.01  5500.9  275.47  5533.9  277.75  5724.9   289.9  5892.3  302.45
#Mann= 8 ,-1 , 0
  4491.8     .11       0  4613.5     .15       0  4974.3     .09       0
  5024.5     .15       0  5062.1     .11       0  5500.9     .17       0
  5533.9     .11       0  5724.9     .17       0
#XS Ineff= 2 , 0
       0                  5031.6       0   261.2
Permanent Ineff=
       F       F
Bank Sta=4974.3,5024.5
XS Rating Curve= 0 ,0
Exp/Cntr=0.3,0.1

Type RM Length L Ch R = 1 ,2474    ,486,486,486
BEGIN DESCRIPTION:
Conroe Lake 038 5.0
END DESCRIPTION:
XS GIS Cut Line= 3
       3809909.1     10184552.57      3809438.23     10184716.84
      3808667.87     10185411.05
#Sta/Elev= 30
  4501.3  284.92  4786.2  270.81  4903.2  265.53  4926.1  262.94  4934.2  258.71
  4939.5  260.51  4947.4  257.11  4965.3  258.56  4979.2  255.87    4997  249.38
  5003.6  249.88  5010.5  254.71  5017.2  254.05  5024.7  257.83  5045.6  259.25
  5130.8  257.05  5399.9  257.82  5512.8  260.07  5547.9  262.07  5619.6  264.67
  5665.4  267.79  5793.2  277.72  5803.5  278.22  5824.4  283.98  5831.9  284.16
  5852.8   280.4  5895.4  280.33  5909.6  284.99  5966.4  292.64    6037  296.65
#Mann= 8 ,-1 , 0
  4501.3     .11       0  4786.2     .17       0  4926.1     .11       0
  4965.3     .06       0  5024.7     .11       0  5547.9     .15       0
  5665.4     .17       0  5793.2     .11       0
#XS Ineff= 2 , 0
       0  4939.5  260.51  5045.6       0  259.25
Permanent Ineff=
       T       T
Bank Sta=4965.3,5024.7
XS Rating Curve= 0 ,0
Exp/Cntr=0.3,0.1

Type RM Length L Ch R = 1 ,1988    ,477,477,477
BEGIN DESCRIPTION:
Conroe Lake 038 4.0
END DESCRIPTION:
XS GIS Cut Line= 3
      3809601.84     10184031.72      3809018.23     10184576.84
      3808627.85     10185281.77
#Sta/Elev= 30
  4201.4  289.81  4232.2  288.35  4281.6  284.35  4338.2  282.03  4387.6  278.73
  4494.1  274.63  4592.8  269.41  4656.8  264.25  4794.7  259.18  4982.1  255.17
  4988.9   253.6  4994.5  247.49  4998.1  247.49  4999.4  248.84  5005.3  248.84
  5016.5   254.8  5026.9  256.44  5135.6  254.44  5179.1   256.1  5218.5  256.29
  5328.5  257.76  5385.2  259.17  5466.5  263.21    5526  267.98  5542.1  268.41
    5596  273.15    5631  275.62  5694.3  279.68  5753.9  287.21  5805.8  291.15
#Mann= 8 ,-1 , 0
  4201.4     .11       0  4794.7     .15       0  4982.1     .09       0
  5016.5     .15       0  5218.5     .11       0  5328.5     .17       0
    5596     .11       0    5631     .17       0
#XS Ineff= 2 , 0
       0  4854.6  257.75               0
Permanent Ineff=
       F       F
Bank Sta=4982.1,5016.5
XS Rating Curve= 0 ,0
Exp/Cntr=0.3,0.1

Type RM Length L Ch R = 1 ,1511    ,492,492,492
BEGIN DESCRIPTION:
Conroe Lake 038 3.0
END DESCRIPTION:
XS GIS Cut Line= 3
      3809252.84     10183841.66      3808688.23     10184466.84
      3808567.97     10185281.72
#Sta/Elev= 30
  4157.6  285.12  4209.4  282.69  4415.4  274.97  4472.2  268.44  4549.9  268.71
  4690.3   262.6  4861.5  256.48  4883.2  253.92  4904.1  255.09  4918.3  253.22
    4925  254.44  4981.8  253.68    4996  250.72  4997.7  247.78  5004.7  248.28
  5014.4  252.71  5024.5  254.12  5085.1  252.67  5195.3  254.25  5236.8   254.3
  5242.1  255.67  5247.1  254.61  5277.2  257.25  5368.2  257.03  5438.9  260.36
  5550.1   267.9  5681.8  279.68  5724.4  281.83    5789   290.1  5823.7  292.66
#Mann= 7 ,-1 , 0
  4157.6     .17       0  4209.4     .11       0  4690.3     .15       0
  4981.8     .09       0  5024.5     .15       0  5195.3     .11       0
  5681.8     .17       0
Bank Sta=4981.8,5024.5
XS Rating Curve= 0 ,0
Exp/Cntr=0.3,0.1

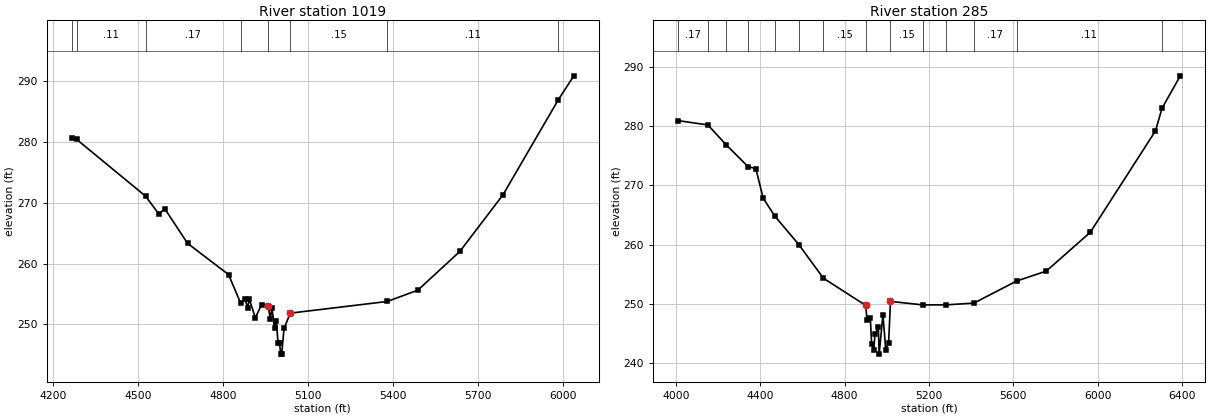
Type RM Length L Ch R = 1 ,1019    ,734,734,734
BEGIN DESCRIPTION:
Conroe Lake 038 2.0
END DESCRIPTION:
XS GIS Cut Line= 3
      3808692.95     10183646.35      3808316.77     10184275.69
      3808500.15     10185296.75
#Sta/Elev= 30
  4266.8  280.69  4284.4  280.39  4527.3  271.07  4574.1  268.15  4595.5  268.98
  4675.3  263.32  4819.9  258.19  4863.1  253.45  4878.1  254.15  4887.3  252.75
  4893.1  254.14  4914.5  251.09  4936.4  253.27  4959.7  253.04  4967.1  250.92
  4972.9  252.65  4982.6  249.33  4988.5  250.61  4994.4  246.92    5000  246.92
  5003.6  245.12  5007.3  245.12  5015.6  249.34  5037.7  251.85  5379.8  253.77
  5487.5  255.63  5635.4  261.98  5787.8   271.3    5983  286.93  6037.4  290.83
#Mann= 8 ,-1 , 0
  4266.8     .17       0  4284.4     .11       0  4527.3     .17       0
  4863.1     .11       0  4959.7     .09       0  5037.7     .15       0
  5379.8     .11       0    5983     .17       0
#XS Ineff= 2 , 0
       0  4893.1  254.14               0
Permanent Ineff=
       F       F
Bank Sta=4959.7,5037.7
XS Rating Curve= 0 ,0
Exp/Cntr=0.3,0.1

Type RM Length L Ch R = 1 ,285     ,0,0,0
BEGIN DESCRIPTION:
Conroe Lake 038 1.0
END DESCRIPTION:
XS GIS Cut Line= 3
      3808691.41     10183605.66      3807823.79     10184083.29
      3808430.43     10185337.15
#Sta/Elev= 30
  4009.6   280.9  4150.7  280.18    4238  276.82  4341.2  273.16  4378.5  272.82
  4413.2  267.85  4468.2  264.83  4583.2  259.99  4698.9  254.36  4900.2  249.77
  4905.9  247.27    4922  247.58  4927.7  243.34  4938.1  242.32  4943.8  244.94
  4959.9  246.06  4963.7  241.57  4981.6  248.21  4994.8  242.34  5008.6  243.49
  5017.5  250.45  5171.6  249.86  5282.8  249.87  5413.7  250.17  5616.6  253.89
    5757  255.56  5965.9   262.1  6275.1  279.18  6306.2     283  6392.9  288.45
#Mann= 14 ,-1 , 0
  4009.6     .17       0  4150.7     .11       0    4238     .17       0
  4341.2     .11       0  4468.2     .17       0  4583.2     .11       0
  4698.9     .15       0  4900.2     .09       0  5017.5     .15       0
  5171.6     .11       0  5282.8     .15       0  5413.7     .17       0
  5616.6     .11       0  6306.2     .17       0
#XS Ineff= 2 , 0
       0                  5017.5       0  250.45
Permanent Ineff=
       F       F
Bank Sta=4900.2,5017.5
XS Rating Curve= 0 ,0
Exp/Cntr=0.3,0.1

Chan Stop Cuts=-1
Use User Specified Reach Order=0
Composite Channel Slope=5