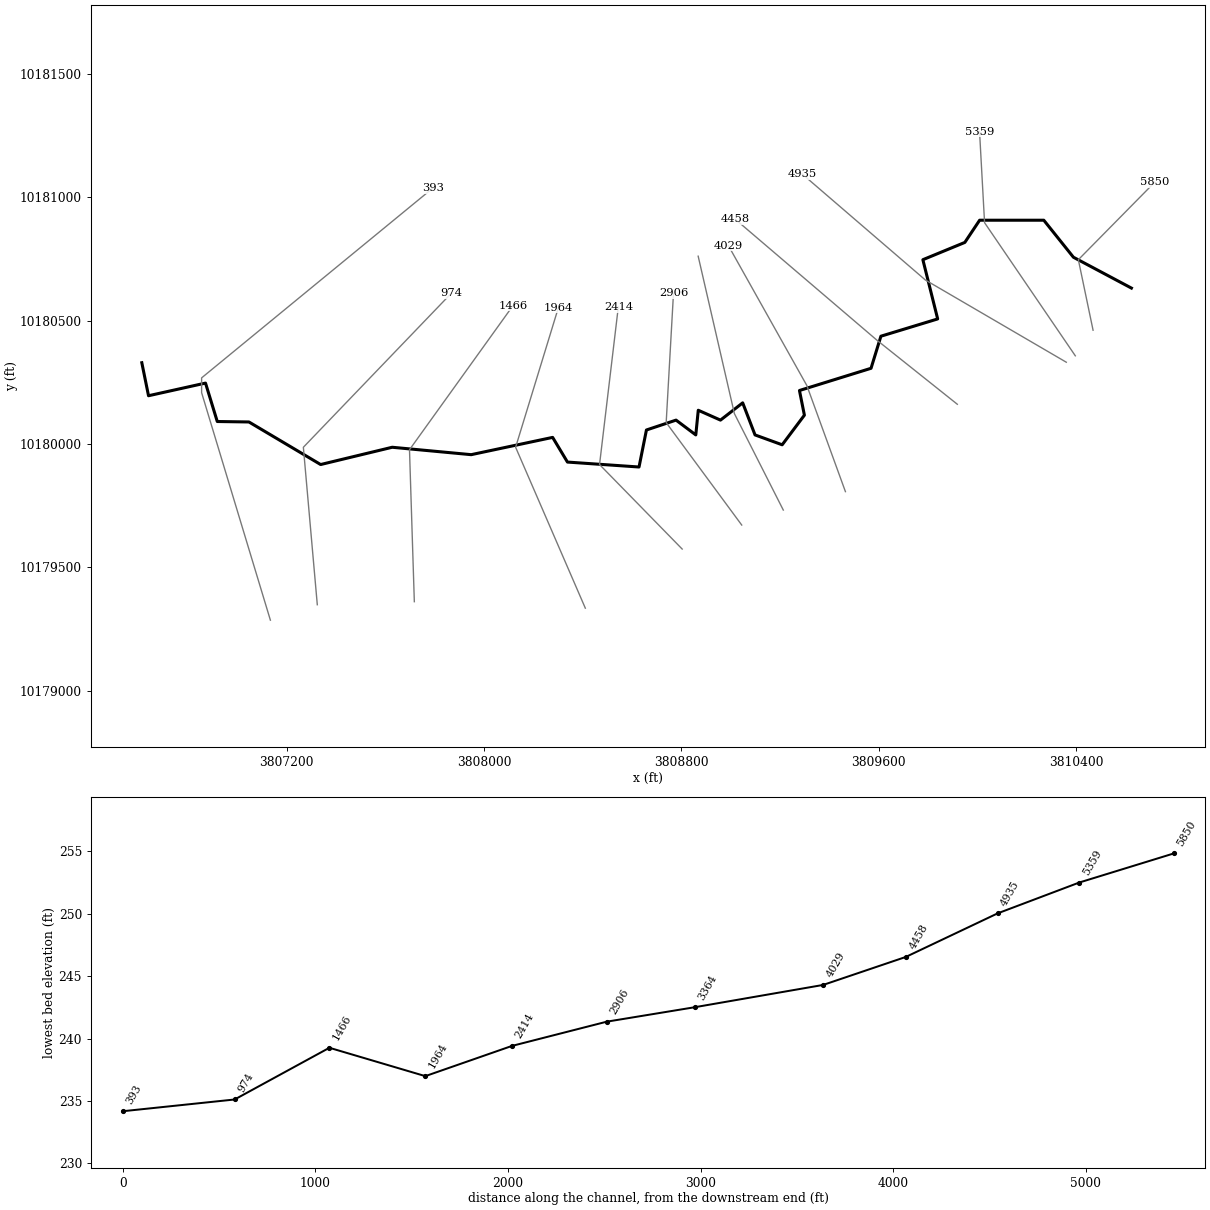
--- Conroe Lake 040.prj (project) ---

Proj Title=Conroe Lake 040 Base Level Engineering
Current Plan=p01
Default Exp/Contr=0.3,0.1
English Units
Geom File=g01
Flow File=f01
Flow File=f02
Plan File=p01
Y Axis Title=Elevation
X Axis Title(PF)=Main Channel Distance
X Axis Title(XS)=Station
BEGIN DESCRIPTION:
Conroe Lake 040
END DESCRIPTION:
DSS File=dss
DSS Export Rating Curves= 0
DSS Export Rating Curve Sorted= 0
DSS Export Volume Flow Curves= 0
DXF OffsetX= 0
DXF OffsetY= 0
DXF ScaleX= 1
DXF ScaleY= 10

--- Conroe Lake 040.p01 (plan) ---

Plan Title=Multiple Run
Short Identifier=Multiple
Geom File=g01
Flow File=f01
Subcritical Flow
K Sum by GR= 0
Std Step Tol= 0.01
Critical Tol= 0.01
Num of Std Step Trials= 20
Max Error Tol= 0.3
Flow Tol Ratio= 0.001
Split Flow NTrial= 30
Split Flow Tol= 0.02
Split Flow Ratio= 0.02
Log Output Level= 0
Friction Slope Method= 1
Unsteady Friction Slope Method= 2
Unsteady Bridges Friction Slope Method= 1
Parabolic Critical Depth
Global Vel Dist=  1 , 1 , 1
Global Log Level= 0
CheckData=True
Encroach Param= -1, 0, 0, 0
BEGIN DESCRIPTION:
Multiple Run
END DESCRIPTION:

--- Conroe Lake 040.f01 (steady flow) ---

Flow Title=Multiple
Program Version=4.10
Number of Profiles= 7
Profile Names=10-year,25-year,50-year,1pct_min,100-year,1pct_plu,500-year
River Rch & RM=Conroe Lake 040,Reach-1         ,5850
     573     774    1047     467    1409    4255    2633
River Rch & RM=Conroe Lake 040,Reach-1         ,5359
     719     978    1327     592    1789    5403    3356
Boundary for River Rch & Prof#=Conroe Lake 040,Reach-1         , 1
Up Type= 0
Dn Type= 3
Dn Slope=0.005
Boundary for River Rch & Prof#=Conroe Lake 040,Reach-1         , 2
Up Type= 0
Dn Type= 3
Dn Slope=0.005
Boundary for River Rch & Prof#=Conroe Lake 040,Reach-1         , 3
Up Type= 0
Dn Type= 3
Dn Slope=0.005
Boundary for River Rch & Prof#=Conroe Lake 040,Reach-1         , 4
Up Type= 0
Dn Type= 3
Dn Slope=0.005
Boundary for River Rch & Prof#=Conroe Lake 040,Reach-1         , 5
Up Type= 0
Dn Type= 3
Dn Slope=0.005
Boundary for River Rch & Prof#=Conroe Lake 040,Reach-1         , 6
Up Type= 0
Dn Type= 3
Dn Slope=0.005
Boundary for River Rch & Prof#=Conroe Lake 040,Reach-1         , 7
Up Type= 0
Dn Type= 3
Dn Slope=0.005
DSS Import GetInterval= 0
DSS Import GetPeak= 0
DSS Import FillOption= 0

--- Conroe Lake 040.f02 (steady flow) ---

Flow Title=Orig_BLE_Flow
Program Version=4.10
Number of Profiles= 7
Profile Names=10-year,25-year,50-year,1pct_min,100-year,1pct_plu,500-year
River Rch & RM=Conroe Lake 040,Reach-1         ,5850
     573     759     910     359    1084    3273    1531
River Rch & RM=Conroe Lake 040,Reach-1         ,5359
     719     959    1154     455    1376    4154    1951
Boundary for River Rch & Prof#=Conroe Lake 040,Reach-1         , 1
Up Type= 0
Dn Type= 3
Dn Slope=0.005
Boundary for River Rch & Prof#=Conroe Lake 040,Reach-1         , 2
Up Type= 0
Dn Type= 3
Dn Slope=0.005
Boundary for River Rch & Prof#=Conroe Lake 040,Reach-1         , 3
Up Type= 0
Dn Type= 3
Dn Slope=0.005
Boundary for River Rch & Prof#=Conroe Lake 040,Reach-1         , 4
Up Type= 0
Dn Type= 3
Dn Slope=0.005
Boundary for River Rch & Prof#=Conroe Lake 040,Reach-1         , 5
Up Type= 0
Dn Type= 3
Dn Slope=0.005
Boundary for River Rch & Prof#=Conroe Lake 040,Reach-1         , 6
Up Type= 0
Dn Type= 3
Dn Slope=0.005
Boundary for River Rch & Prof#=Conroe Lake 040,Reach-1         , 7
Up Type= 0
Dn Type= 3
Dn Slope=0.005
DSS Import GetInterval= 0
DSS Import GetPeak= 0
DSS Import FillOption= 0

--- Conroe Lake 040.g01 (geometry) ---

Geom Title=Existing Conditions
Program Version=4.10

River Reach=Conroe Lake 040 ,Reach-1
Reach XY= 30
      3810623.23     10180631.84      3810388.23     10180756.84
      3810268.23     10180906.84      3810008.23     10180906.84
      3809948.23     10180816.84      3809778.23     10180746.84
      3809838.23     10180506.84      3809608.23     10180436.84
      3809568.23     10180306.84      3809278.23     10180216.84
      3809298.23     10180116.84      3809208.23     10179996.84
      3809098.23     10180036.84      3809048.23     10180166.84
      3808958.23     10180096.84      3808868.23     10180136.84
      3808858.23     10180036.84      3808778.23     10180096.84
      3808658.23     10180056.84      3808628.23     10179906.84
      3808338.23     10179926.84      3808278.23     10180026.84
      3807948.23     10179956.84      3807628.23     10179986.84
      3807338.23     10179916.84       3807047.7     10180089.34
      3806919.42     10180091.17      3806871.78     10180246.93
      3806640.88     10180195.62       3806613.7     10180329.41

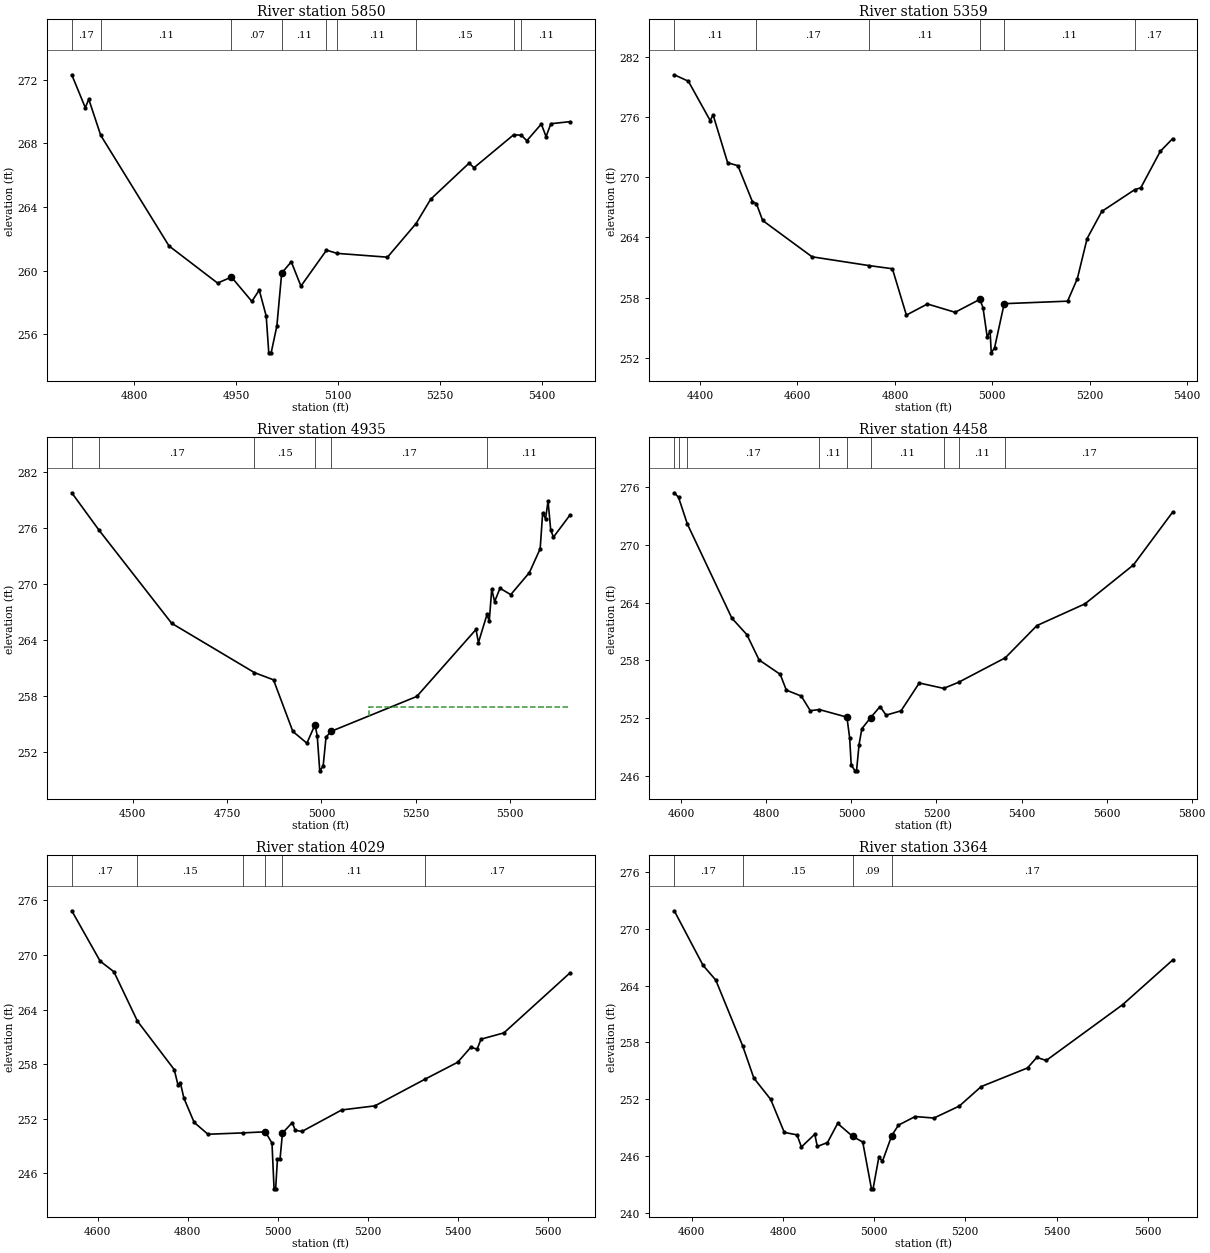
Type RM Length L Ch R = 1 ,5850    ,491,491,491
BEGIN DESCRIPTION:
Conroe Lake 040 11.0
END DESCRIPTION:
XS GIS Cut Line= 3
      3810467.85      10180461.1      3810408.23     10180746.84
      3810717.82     10181061.04
#Sta/Elev= 30
  4708.1  272.32    4728  270.25  4733.1  270.78  4750.7  268.51  4851.1  261.55
  4922.6  259.21    4943  259.59    4973  258.06  4983.9  258.77  4994.1  257.14
  4997.9  254.82  5001.4  254.82  5009.8  256.51  5016.9  259.84    5031  260.55
  5045.2  259.02  5082.8  261.28  5098.6  261.08  5172.5  260.84  5214.6  262.96
  5236.1  264.49  5292.6  266.76  5299.8  266.47    5358  268.54  5369.3  268.52
  5377.5  268.17  5398.8  269.22  5405.8  268.43  5412.9  269.24  5441.1  269.37
#Mann= 9 ,-1 , 0
  4708.1     .17       0  4750.7     .11       0    4943     .07       0
  5016.9     .11       0  5082.8     .15       0  5098.6     .11       0
  5214.6     .15       0    5358     .17       0  5369.3     .11       0
#XS Ineff= 2 , 0
       0                    5031       0  260.55
Permanent Ineff=
       F       F
Bank Sta=4943,5016.9
XS Rating Curve= 0 ,0
Exp/Cntr=0.3,0.1

Type RM Length L Ch R = 1 ,5359    ,424,424,424
BEGIN DESCRIPTION:
Conroe Lake 040 10.0
END DESCRIPTION:
XS GIS Cut Line= 3
      3810395.89     10180357.42      3810028.23     10180896.84
      3810007.87     10181266.18
#Sta/Elev= 30
  4347.2   280.2  4376.1  279.56  4420.9  275.64  4426.9   276.2  4456.8  271.43
  4477.8  271.14  4507.6  267.55  4515.8  267.36  4528.6  265.68    4630  262.06
  4747.6  261.18  4794.9  260.87  4823.6  256.25  4866.7  257.36  4923.6  256.53
  4974.4  257.82  4980.9  256.98  4989.4   254.1  4995.4  254.63  4997.8  252.49
  5004.6  252.99  5024.3  257.39  5154.5  257.64  5174.5  259.89  5194.5  263.88
  5224.6  266.58  5292.2  268.75  5304.7  268.94  5344.7  272.57  5369.9  273.83
#Mann= 6 ,-1 , 0
  4347.2     .11       0  4515.8     .17       0  4747.6     .11       0
  4974.4     .07       0  5024.3     .11       0  5292.2     .17       0
Bank Sta=4974.4,5024.3
XS Rating Curve= 0 ,0
Exp/Cntr=0.3,0.1

Type RM Length L Ch R = 1 ,4935    ,477,477,477
BEGIN DESCRIPTION:
Conroe Lake 040 9.0
END DESCRIPTION:
XS GIS Cut Line= 3
      3810359.39     10180331.41      3809788.23     10180664.72
      3809288.93     10181094.35
#Sta/Elev= 30
  4338.7  279.78  4410.7  275.79  4603.4  265.81  4822.7  260.53  4873.1  259.76
  4924.3  254.24  4961.5  252.98    4983  254.95  4988.9  253.79  4995.6  250.02
  5004.6  250.52  5012.3  253.65  5026.5  254.26  5252.6  257.98  5409.5  265.15
    5416  263.75  5438.7  266.76  5444.6  266.03  5451.2  269.47  5458.8  268.13
  5473.1  269.56  5501.6  268.88    5551  271.24  5579.5  273.79  5586.1  277.63
  5593.8     277  5600.4   278.9  5607.4  275.81  5614.6  275.03  5658.7  277.41
#Mann= 6 ,-1 , 0
  4338.7     .11       0  4410.7     .17       0  4822.7     .15       0
    4983     .09       0  5026.5     .17       0  5438.7     .11       0
#XS Ineff= 2 , 0
       0                 5124.79       0  256.81
Permanent Ineff=
       F       F
Bank Sta=4983,5026.5
XS Rating Curve= 0 ,0
Exp/Cntr=0.3,0.1

Type RM Length L Ch R = 1 ,4458    ,429,429,429
BEGIN DESCRIPTION:
Conroe Lake 040 8.0
END DESCRIPTION:
XS GIS Cut Line= 3
      3809917.88     10180161.05      3809592.12     10180420.74
      3809017.87     10180911.05
#Sta/Elev= 30
  4583.4  275.43  4593.4  274.96  4614.1  272.19  4718.8   262.4    4754  260.69
  4782.8  258.06  4832.5  256.56  4846.9  254.92  4882.1   254.3  4903.2  252.78
  4924.4   252.9  4989.4  252.11  4995.8  249.95  4999.5  247.14  5008.5  246.53
    5012  246.53  5017.9  249.26  5024.5  250.91  5045.3  252.07  5067.3  253.21
  5081.6  252.32  5116.7  252.77  5159.5  255.66  5216.9   255.1  5251.8  255.73
  5361.8  258.28  5436.2  261.63  5549.3  263.89  5663.1  267.93  5755.1  273.41
#Mann= 9 ,-1 , 0
  4583.4     .17       0  4593.4     .11       0  4614.1     .17       0
  4924.4     .11       0  4989.4     .07       0  5045.3     .11       0
  5216.9     .17       0  5251.8     .11       0  5361.8     .17       0
#XS Ineff= 2 , 0
       0  4882.1   254.3               0
Permanent Ineff=
       F       F
Bank Sta=4989.4,5045.3
XS Rating Curve= 0 ,0
Exp/Cntr=0.3,0.1

Type RM Length L Ch R = 1 ,4029    ,665,665,665
BEGIN DESCRIPTION:
Conroe Lake 040 7.0
END DESCRIPTION:
XS GIS Cut Line= 3
      3809464.47     10179807.06      3809308.23     10180236.84
      3808990.53     10180803.57
#Sta/Elev= 30
  4542.7  274.85  4605.7  269.32  4636.3  268.15  4688.6  262.72  4770.4  257.39
  4778.7  255.69    4784  255.95  4791.7  254.27  4814.6  251.59  4845.2  250.29
  4923.5  250.44  4972.6  250.56  4987.5  249.32  4992.1  244.29  4995.6  244.29
  4999.6  247.52  5005.3  247.52  5010.8  250.42  5032.5  251.57  5039.2  250.72
  5054.2   250.6  5142.4  252.96  5216.2  253.41    5327  256.33    5400   258.2
    5429  259.84  5443.3  259.65  5451.9  260.74  5502.7  261.43  5649.7  268.03
#Mann= 6 ,-1 , 0
  4542.7     .17       0  4688.6     .15       0  4923.5     .11       0
  4972.6     .06       0  5010.8     .11       0    5327     .17       0
Bank Sta=4972.6,5010.8
XS Rating Curve= 0 ,0
Exp/Cntr=0.3,0.1

Type RM Length L Ch R = 1 ,3364    ,458,458,458
BEGIN DESCRIPTION:
Conroe Lake 040 6.0
END DESCRIPTION:
XS GIS Cut Line= 3
      3809212.75     10179732.39      3809014.62     10180123.24
      3808867.85     10180761.07
#Sta/Elev= 30
  4561.8  271.93    4625  266.15  4652.8   264.6  4711.6  257.66  4736.3  254.23
  4773.3  251.97  4803.1  248.48    4831  248.22  4840.6  246.94  4869.9  248.29
  4875.5  246.99  4897.8  247.41  4920.1  249.43  4952.7  248.07  4975.1  247.46
  4994.2  242.51  4997.7  242.51  5010.5  245.87  5018.3  245.42  5038.8  248.15
  5053.4  249.25  5090.1  250.16  5131.2     250  5186.9  251.27  5234.9  253.33
  5336.4   255.3  5356.9  256.42  5377.4  256.09  5544.9  261.99  5654.5  266.71
#Mann= 4 ,-1 , 0
  4561.8     .17       0  4711.6     .15       0  4952.7     .09       0
  5038.8     .17       0
Bank Sta=4952.7,5038.8
XS Rating Curve= 0 ,0
Exp/Cntr=0.3,0.1

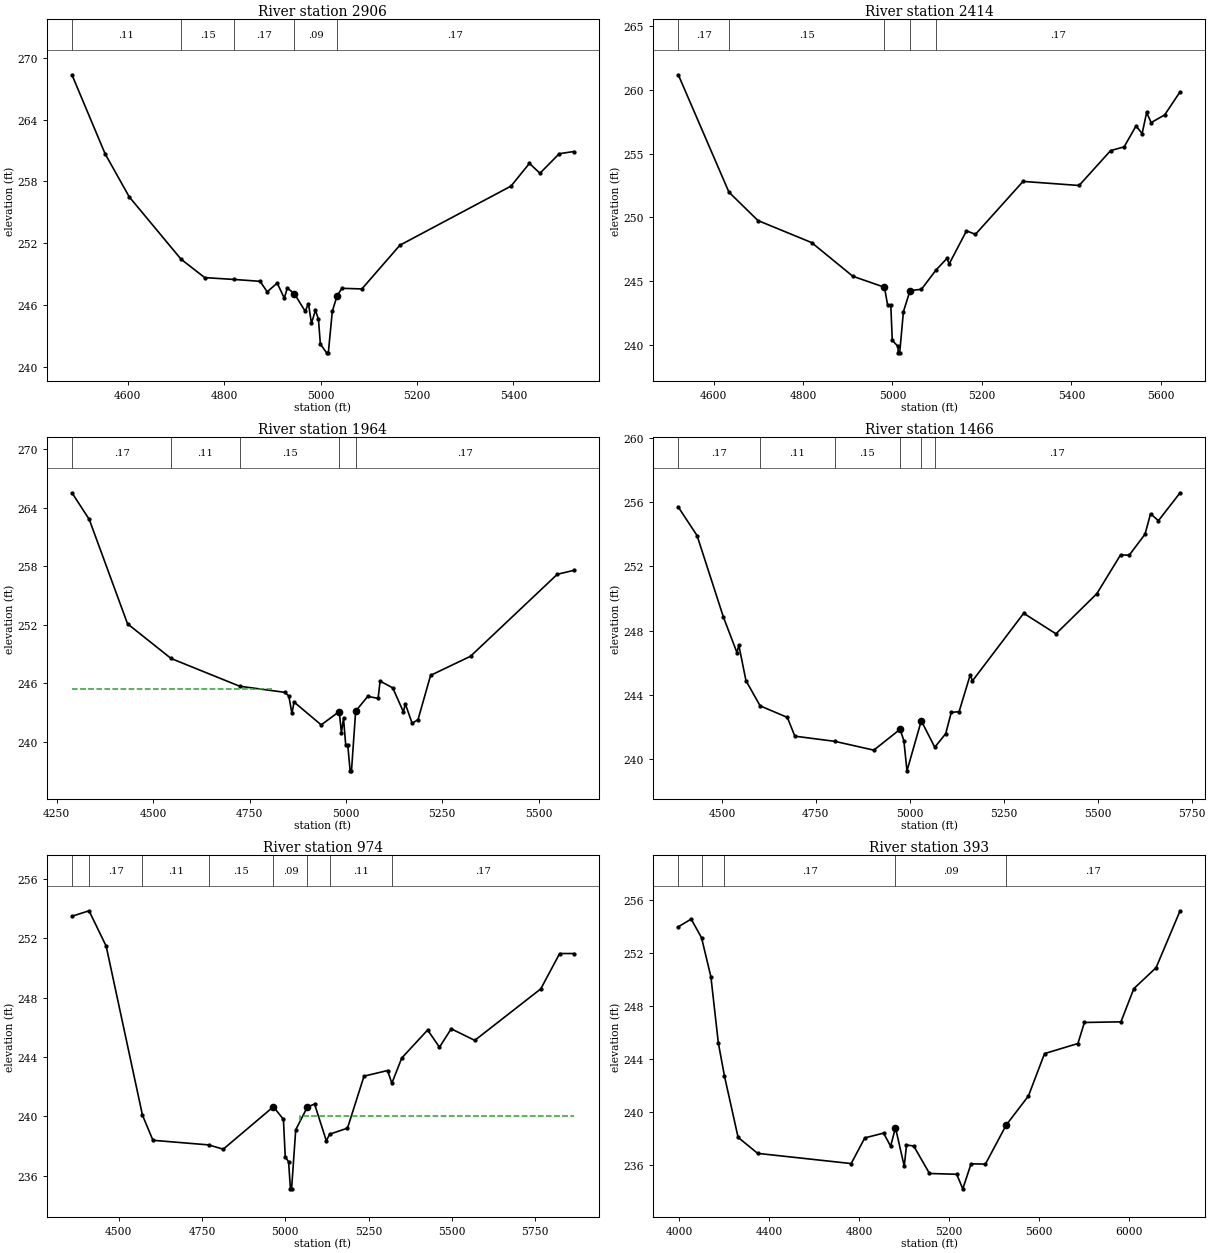
Type RM Length L Ch R = 1 ,2906    ,492,492,492
BEGIN DESCRIPTION:
Conroe Lake 040 5.0
END DESCRIPTION:
XS GIS Cut Line= 3
      3809044.31     10179671.68      3808738.23     10180086.84
      3808767.85     10180611.11
#Sta/Elev= 30
  4484.2  268.37  4552.9   260.7    4603  256.51  4710.5  250.45  4759.6  248.66
  4820.8  248.48  4874.5   248.3  4889.2  247.28    4910  248.13  4924.7  246.66
  4930.9  247.65  4945.5   247.1    4968  245.39  4974.8  246.13    4981  244.22
  4989.4  245.49  4995.6  244.59  4999.5   242.2  5012.5  241.35    5016  241.35
  5024.3  245.39  5034.3  246.91  5044.3  247.62  5085.6  247.56  5164.5  251.81
  5394.9  257.55  5433.2  259.76    5455   258.8    5495   260.7  5525.1  260.91
#Mann= 5 ,-1 , 0
  4484.2     .11       0  4710.5     .15       0  4820.8     .17       0
  4945.5     .09       0  5034.3     .17       0
Bank Sta=4945.5,5034.3
XS Rating Curve= 0 ,0
Exp/Cntr=0.3,0.1

Type RM Length L Ch R = 1 ,2414    ,450,450,450
BEGIN DESCRIPTION:
Conroe Lake 040 4.0
END DESCRIPTION:
XS GIS Cut Line= 3
      3808803.03     10179574.42      3808468.23     10179916.84
      3808544.32     10180555.33
#Sta/Elev= 30
  4521.1  261.16  4634.3  251.98  4699.1  249.76  4819.4  248.03  4911.3   245.4
    4982  244.54  4989.2  243.13  4996.2  243.14  4999.5  240.39  5012.3  239.91
  5012.6  239.41  5016.1  239.41  5024.4  242.63  5039.3  244.28  5064.7  244.38
  5096.9  245.87  5121.8   246.8  5126.8  246.37  5165.4  248.95  5185.5  248.68
  5291.9  252.82  5417.2   252.5  5487.7  255.23  5517.9  255.52  5544.5  257.16
  5558.1  256.56  5568.2  258.21  5578.3  257.42  5608.5  258.02    5643  259.83
#Mann= 5 ,-1 , 0
  4521.1     .17       0  4634.3     .15       0    4982     .09       0
  5039.3     .15       0  5096.9     .17       0
Bank Sta=4982,5039.3
XS Rating Curve= 0 ,0
Exp/Cntr=0.3,0.1

Type RM Length L Ch R = 1 ,1964    ,498,498,498
BEGIN DESCRIPTION:
Conroe Lake 040 3.0
END DESCRIPTION:
XS GIS Cut Line= 3
      3808410.63     10179334.88      3808128.23     10179986.84
      3808301.26     10180551.84
#Sta/Elev= 30
  4289.5  265.55  4334.3  262.82  4433.7  252.09  4546.6  248.53  4724.5  245.68
    4842  245.05    4852  244.67    4860  242.88  4865.5  244.06  4935.9  241.71
  4982.8  243.08  4988.3   240.9  4993.8  242.37  4999.6  239.62  5004.8  239.62
    5011  236.99  5014.5  236.99  5025.3  243.12  5056.7  244.64  5083.5  244.43
  5088.7  246.21  5121.5  245.51    5149  243.06  5154.2  243.86  5171.8  241.87
    5187  242.25  5219.7   246.8  5323.3  248.76  5548.3  257.18  5590.9  257.58
#Mann= 5 ,-1 , 0
  4289.5     .17       0  4546.6     .11       0  4724.5     .15       0
  4982.8     .09       0  5025.3     .17       0
#XS Ineff= 2 , 0
       0  4807.6  245.38  5088.7       0  246.21
Permanent Ineff=
       F       F
Bank Sta=4982.8,5025.3
XS Rating Curve= 0 ,0
Exp/Cntr=0.3,0.1

Type RM Length L Ch R = 1 ,1466    ,492,492,492
BEGIN DESCRIPTION:
Conroe Lake 040 2.0
END DESCRIPTION:
XS GIS Cut Line= 3
      3807717.85     10179361.06      3807698.23     10179976.84
      3808117.85     10180561.07
#Sta/Elev= 30
  4383.9   255.7  4433.9  253.92    4504  248.84    4540  246.63    4545  247.09
    4564  244.88  4601.7  243.31  4674.1  242.59  4694.1  241.42    4800   241.1
  4904.2  240.55  4974.2  241.85  4984.2  241.14  4992.5  239.26  5030.5  242.38
  5066.5  240.73  5095.6  241.58  5110.3   242.9  5131.2  242.95  5160.7  245.23
  5166.8  244.87  5303.1  249.08    5389   247.8  5497.7   250.3  5560.9  252.72
  5583.9   252.7    5626  254.01  5640.7  255.28  5661.6  254.85  5719.3  256.59
#Mann= 6 ,-1 , 0
  4383.9     .17       0  4601.7     .11       0    4800     .15       0
  4974.2     .09       0  5030.5     .15       0  5066.5     .17       0
Bank Sta=4974.2,5030.5
XS Rating Curve= 0 ,0
Exp/Cntr=0.3,0.1

Type RM Length L Ch R = 1 ,974     ,581,581,581
BEGIN DESCRIPTION:
Conroe Lake 040 1.0
END DESCRIPTION:
XS GIS Cut Line= 3
      3807324.71     10179348.74      3807268.23     10179986.84
      3807867.87      10180611.1
#Sta/Elev= 30
  4359.4  253.48  4410.7  253.85  4462.1  251.47  4571.1  240.08  4602.5  238.39
  4769.7  238.08  4813.5  237.79  4964.1  240.65  4994.2   239.8  4999.6  237.29
  5009.7  236.94  5015.2  235.12  5018.7  235.12  5031.1   239.1  5066.3  240.64
  5087.7  240.83  5122.9  238.36  5133.1   238.8  5186.5  239.21  5236.1  242.71
  5306.9  243.09  5319.6  242.23  5349.3  243.93    5427  245.82  5462.6  244.66
  5497.8   245.9  5568.5  245.12  5766.7  248.59  5823.3  250.97  5865.6  250.97
#Mann= 8 ,-1 , 0
  4359.4     .11       0  4410.7     .17       0  4571.1     .11       0
  4769.7     .15       0  4964.1     .09       0  5066.3     .15       0
  5133.1     .11       0  5319.6     .17       0
#XS Ineff= 2 , 0
       0  4964.1  240.65  5045.3       0     240
Permanent Ineff=
       T       F
Bank Sta=4964.1,5066.3
XS Rating Curve= 0 ,0
Exp/Cntr=0.3,0.1

Type RM Length L Ch R = 1 ,393     ,0,0,0
BEGIN DESCRIPTION:
Conroe Lake 040 1.5
END DESCRIPTION:
XS GIS Cut Line= 4
      3807134.62      10179286.2      3806855.96     10180208.12
      3806855.96     10180268.01       3807792.2     10181036.58
#Sta/Elev= 30
  3995.2  253.98  4052.5  254.56  4098.6  253.16  4140.4   250.2  4173.4  245.21
  4200.8   242.7  4261.5  238.07  4348.6  236.86  4764.9  236.09  4825.6  238.03
  4909.2  238.39  4940.5   237.4  4962.3   238.8  5001.3  235.88  5011.3  237.49
  5043.4  237.42  5113.7  235.34    5235  235.28  5261.9  234.18  5298.8  236.07
  5362.7  236.05  5455.3     239  5554.3   241.2    5626   244.4  5774.6  245.16
  5803.3  246.75  5966.2   246.8  6023.6  249.31  6122.6  250.89  6229.5  255.19
#Mann= 5 ,-1 , 0
  3995.2     .17       0  4098.6     .11       0  4200.8     .17       0
  4962.3     .09       0  5455.3     .17       0
Bank Sta=4962.3,5455.3
XS Rating Curve= 0 ,0
Exp/Cntr=0.3,0.1

Chan Stop Cuts=-1
Use User Specified Reach Order=0
Composite Channel Slope=5