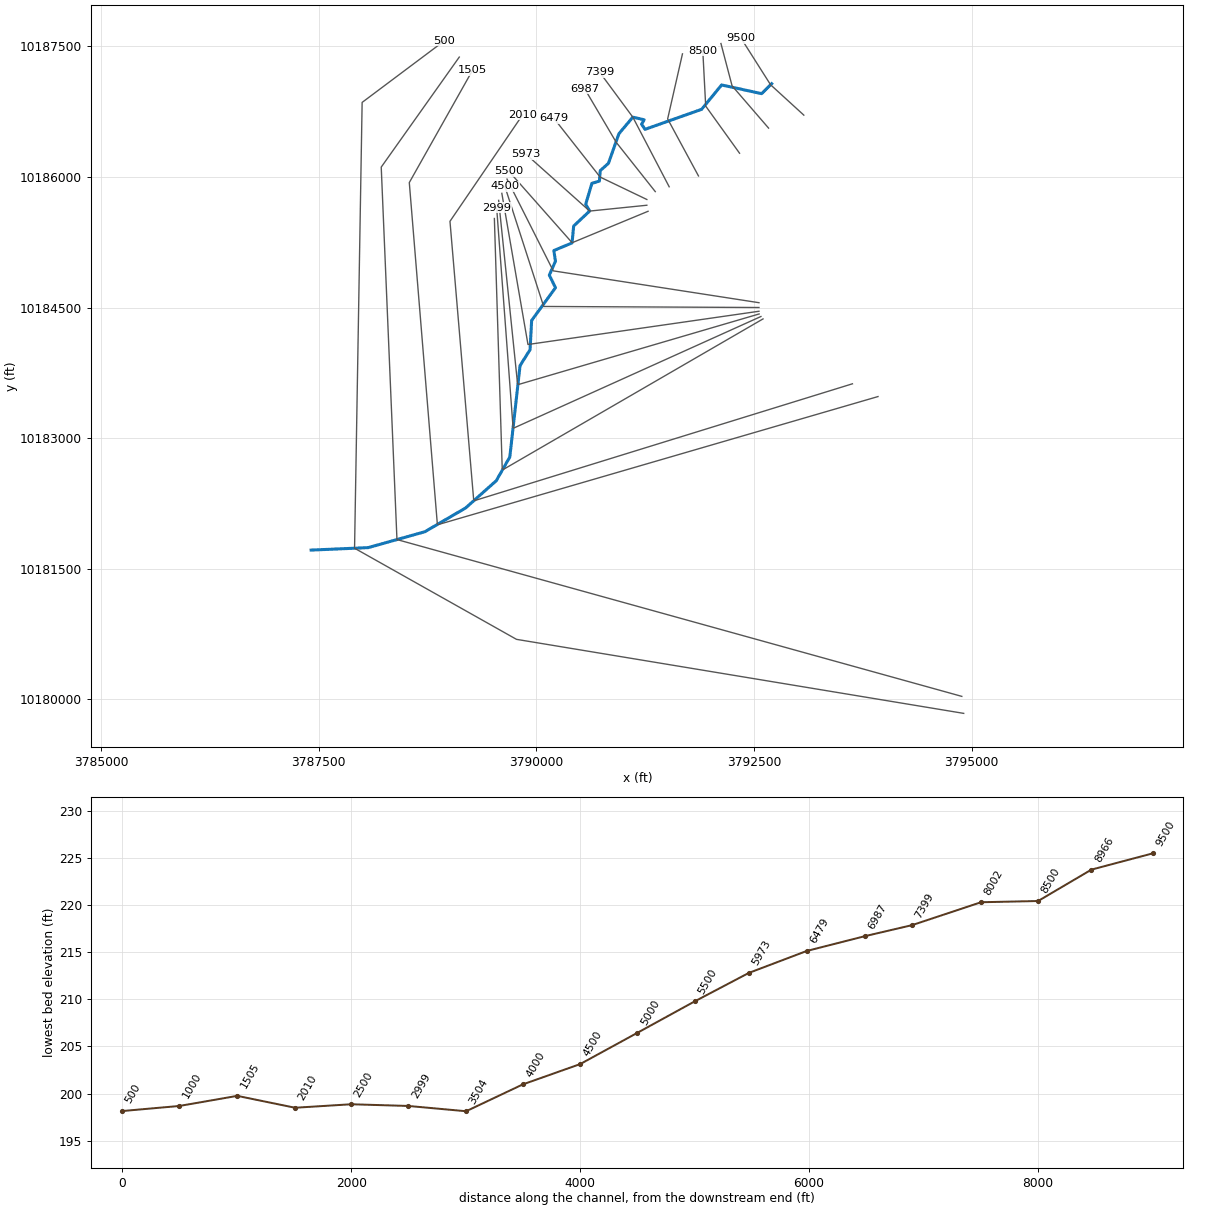
--- Conroe Lake 042.prj (project) ---

Proj Title=Conroe Lake 042 Base Level Engineering
Current Plan=p01
Default Exp/Contr=0.3,0.1
English Units
Geom File=g01
Flow File=f01
Flow File=f02
Plan File=p01
Y Axis Title=Elevation
X Axis Title(PF)=Main Channel Distance
X Axis Title(XS)=Station
BEGIN DESCRIPTION:
Conroe Lake 042
END DESCRIPTION:
DSS Export Rating Curves= 0
DSS Export Rating Curve Sorted= 0
DSS Export Volume Flow Curves= 0
DXF OffsetX= 0
DXF OffsetY= 0
DXF ScaleX= 1
DXF ScaleY= 10

--- Conroe Lake 042.p01 (plan) ---

Plan Title=Multiple Run
Short Identifier=Multiple
Geom File=g01
Flow File=f01
Subcritical Flow
K Sum by GR= 0
Std Step Tol= 0.01
Critical Tol= 0.01
Num of Std Step Trials= 20
Max Error Tol= 0.3
Flow Tol Ratio= 0.001
Split Flow NTrial= 30
Split Flow Tol= 0.02
Split Flow Ratio= 0.02
Log Output Level= 0
Friction Slope Method= 1
Unsteady Friction Slope Method= 2
Unsteady Bridges Friction Slope Method= 1
Parabolic Critical Depth
Global Vel Dist=  1 , 1 , 1
Global Log Level= 0
CheckData=True
Encroach Param= -1, 0, 0, 0
BEGIN DESCRIPTION:
Multiple Run
END DESCRIPTION:

--- Conroe Lake 042.f01 (steady flow) ---

Flow Title=Multiple
Program Version=4.10
Number of Profiles= 7
Profile Names=10-year,25-year,50-year,1pct_min,100-year,1pct_plu,500-year
River Rch & RM=Conroe Lake 042,Reach-1         ,9500
     671     922    1259     567    1713    5173    3275
River Rch & RM=Conroe Lake 042,Reach-1         ,8002
     871    1203    1648     742    2241    6768    4290
River Rch & RM=Conroe Lake 042,Reach-1         ,3504
     934    1280    1745     780    2357    7118    4451
Boundary for River Rch & Prof#=Conroe Lake 042,Reach-1         , 1
Up Type= 0
Dn Type= 3
Dn Slope=0.005
Boundary for River Rch & Prof#=Conroe Lake 042,Reach-1         , 2
Up Type= 0
Dn Type= 3
Dn Slope=0.005
Boundary for River Rch & Prof#=Conroe Lake 042,Reach-1         , 3
Up Type= 0
Dn Type= 3
Dn Slope=0.005
Boundary for River Rch & Prof#=Conroe Lake 042,Reach-1         , 4
Up Type= 0
Dn Type= 3
Dn Slope=0.005
Boundary for River Rch & Prof#=Conroe Lake 042,Reach-1         , 5
Up Type= 0
Dn Type= 3
Dn Slope=0.005
Boundary for River Rch & Prof#=Conroe Lake 042,Reach-1         , 6
Up Type= 0
Dn Type= 3
Dn Slope=0.005
Boundary for River Rch & Prof#=Conroe Lake 042,Reach-1         , 7
Up Type= 0
Dn Type= 3
Dn Slope=0.005
DSS Import GetInterval= 0
DSS Import GetPeak= 0
DSS Import FillOption= 0

--- Conroe Lake 042.f02 (steady flow) ---

Flow Title=Orig_BLE_Flow
Program Version=4.10
Number of Profiles= 7
Profile Names=10-year,25-year,50-year,1pct_min,100-year,1pct_plu,500-year
River Rch & RM=Conroe Lake 042,Reach-1         ,9500
     671     904    1095     436    1318    3981    1904
River Rch & RM=Conroe Lake 042,Reach-1         ,8002
     871    1179    1433     571    1724    5207    2494
River Rch & RM=Conroe Lake 042,Reach-1         ,3504
     934    1255    1517     600    1813    5476    2588
Boundary for River Rch & Prof#=Conroe Lake 042,Reach-1         , 1
Up Type= 0
Dn Type= 3
Dn Slope=0.005
Boundary for River Rch & Prof#=Conroe Lake 042,Reach-1         , 2
Up Type= 0
Dn Type= 3
Dn Slope=0.005
Boundary for River Rch & Prof#=Conroe Lake 042,Reach-1         , 3
Up Type= 0
Dn Type= 3
Dn Slope=0.005
Boundary for River Rch & Prof#=Conroe Lake 042,Reach-1         , 4
Up Type= 0
Dn Type= 3
Dn Slope=0.005
Boundary for River Rch & Prof#=Conroe Lake 042,Reach-1         , 5
Up Type= 0
Dn Type= 3
Dn Slope=0.005
Boundary for River Rch & Prof#=Conroe Lake 042,Reach-1         , 6
Up Type= 0
Dn Type= 3
Dn Slope=0.005
Boundary for River Rch & Prof#=Conroe Lake 042,Reach-1         , 7
Up Type= 0
Dn Type= 3
Dn Slope=0.005
DSS Import GetInterval= 0
DSS Import GetPeak= 0
DSS Import FillOption= 0

--- Conroe Lake 042.g01 (geometry) ---

Geom Title=Existing Conditions
Program Version=4.10

River Reach=Conroe Lake 042 ,Reach-1
Reach XY= 30
      3792703.23     10187071.84      3792588.23     10186956.84
      3792128.23     10187056.84      3791898.23     10186776.84
      3791248.23     10186546.84      3791208.23     10186606.84
      3791238.23     10186656.84      3791108.23     10186686.84
      3790948.23     10186496.84      3790828.23     10186156.84
      3790733.25     10186071.87      3790724.57     10185952.16
      3790638.23     10185926.84      3790566.75     10185686.97
      3790612.31     10185608.06      3790428.46     10185436.42
      3790410.26     10185242.42      3790200.69     10185154.14
       3790219.4     10185032.12      3790148.63     10184871.86
      3790219.76     10184727.51      3789945.88     10184351.43
      3789927.61      10184015.3      3789812.53     10183832.63
      3789694.99     10182783.06      3789538.74     10182509.62
      3789187.17     10182197.12      3788718.42     10181923.68
      3788067.38     10181741.39      3787411.75      10181713.1

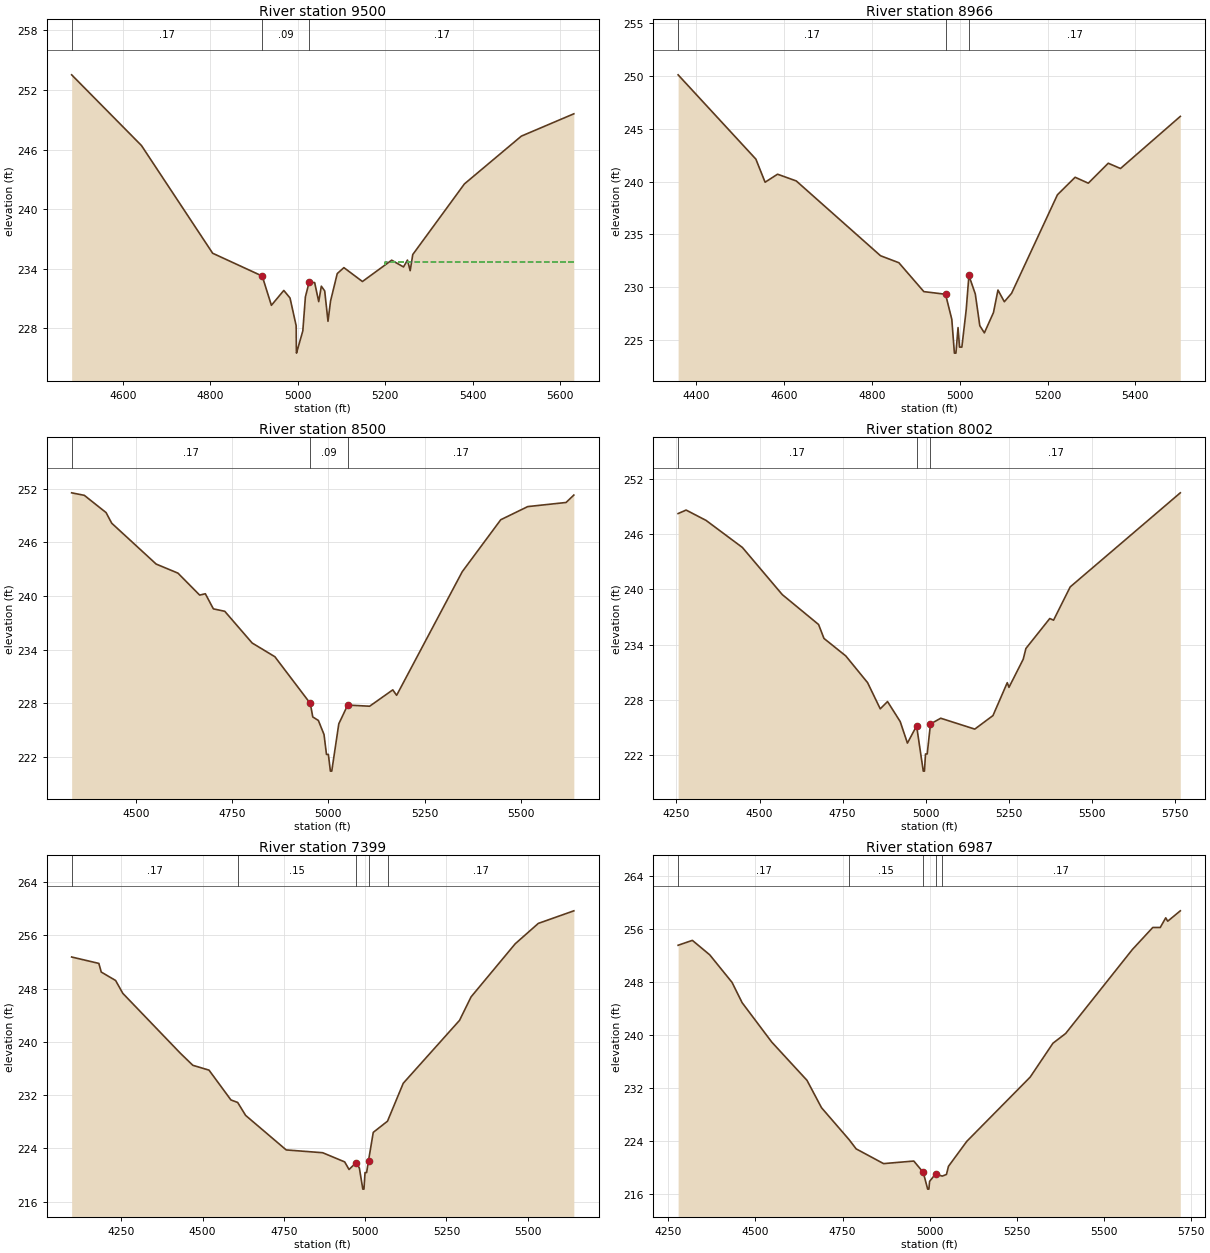
Type RM Length L Ch R = 1 ,9500    ,534,534,534
BEGIN DESCRIPTION:
Conroe Lake 042 19.0
END DESCRIPTION:
XS GIS Cut Line= 3
      3793072.84     10186710.06      3792690.65     10187059.26
      3792352.33     10187592.49
#Sta/Elev= 30
  4482.3  253.53  4642.1   246.4    4805  235.54  4918.4  233.24  4939.4  230.29
  4967.8  231.79    4982  231.03  4996.1  228.23  4996.5  225.97  4996.8  225.47
  5011.3  227.71  5017.2  231.14  5025.8  232.63  5038.4  232.58  5047.7  230.66
  5053.7  232.22  5061.4  231.74  5068.9  228.68  5074.8  230.73  5090.1  233.49
  5105.3  234.09  5147.7  232.69  5214.6  234.84  5241.7  234.16  5250.8  234.85
    5257  233.78  5262.9  235.41  5381.1  242.53  5511.4  247.35  5631.5   249.6
#Mann= 3 , 0 , 0
  4482.3     .17       0  4918.4     .09       0  5025.8     .17       0
#XS Ineff= 2 , 0
       0                  5199.4       0  234.67
Permanent Ineff=
       F       F
Bank Sta=4918.4,5025.8
XS Rating Curve= 0 ,0
Exp/Cntr=0.3,0.1

Type RM Length L Ch R = 1 ,8966    ,466,466,466
BEGIN DESCRIPTION:
Conroe Lake 042 18.0
END DESCRIPTION:
XS GIS Cut Line= 3
      3792667.87     10186561.05      3792248.45     10187046.84
      3792120.55      10187532.9
#Sta/Elev= 30
  4358.2  250.13  4535.4  242.14  4556.4  239.95  4584.8  240.71  4627.5  240.07
  4819.5  232.98  4861.2  232.32  4918.2  229.58  4967.6  229.33  4981.9  226.95
  4987.8  223.75  4991.3  223.75  4996.1  226.17  4999.5  224.32  5004.8  224.32
  5014.7  227.86  5020.9  231.11  5035.4  229.36  5045.7  226.35  5056.1  225.67
  5076.8  227.59  5087.1  229.73  5101.6  228.62  5118.1  229.42  5222.6  238.76
  5262.9  240.42  5292.9  239.86  5338.4  241.75  5366.3  241.25  5502.6  246.19
#Mann= 3 , 0 , 0
  4358.2     .17       0  4967.6     .09       0  5020.9     .17       0
Bank Sta=4967.6,5020.9
XS Rating Curve= 0 ,0
Exp/Cntr=0.3,0.1

Type RM Length L Ch R = 1 ,8500    ,498,498,498
BEGIN DESCRIPTION:
Conroe Lake 042 17.0
END DESCRIPTION:
XS GIS Cut Line= 3
      3792334.35     10186272.52      3791945.38     10186813.99
      3791912.02     10187450.62
#Sta/Elev= 30
  4333.3  251.55  4366.2  251.27  4422.7  249.34  4437.4  248.15  4552.8  243.58
  4609.3  242.57  4665.8  240.11  4680.5  240.26  4701.4  238.57  4730.9   238.3
  4802.1  234.75    4861  233.22  4953.1  227.99  4959.5  226.48    4974  226.09
  4988.7  224.52  4995.1  222.29    5000  222.29  5005.3  220.42  5008.8  220.42
  5027.1  225.71  5050.2  227.81  5107.2  227.68  5167.3  229.51  5177.3   228.9
  5347.6  242.72  5447.7  248.54  5517.8  250.01  5617.3  250.47  5637.5   251.3
#Mann= 3 , 0 , 0
  4333.3     .17       0  4953.1     .09       0  5050.2     .17       0
Bank Sta=4953.1,5050.2
XS Rating Curve= 0 ,0
Exp/Cntr=0.3,0.1

Type RM Length L Ch R = 1 ,8002    ,603,603,603
BEGIN DESCRIPTION:
Conroe Lake 042 16.0
END DESCRIPTION:
XS GIS Cut Line= 3
      3791862.43     10186011.43      3791508.23     10186666.84
      3791678.41     10187414.21
#Sta/Elev= 30
    4255  248.24  4279.1  248.62    4339   247.5  4448.5  244.56  4568.4  239.45
  4677.8   236.2    4694  234.69  4759.7  232.79  4825.3  229.89  4863.4  227.05
  4885.3  227.84  4923.4  225.67  4945.2  223.33  4972.8   225.2  4992.9  220.29
  4996.4  220.29  4999.6  222.15  5004.7  222.15  5014.6  225.41  5045.4  226.03
  5147.9  224.85  5202.7  226.32  5245.7  229.89  5250.8  229.38  5293.8  232.44
  5301.8   233.6  5373.6  236.85    5385  236.67  5435.1  240.28  5766.5  250.49
#Mann= 3 , 0 , 0
    4255     .17       0  4972.8     .09       0  5014.6     .17       0
Bank Sta=4972.8,5014.6
XS Rating Curve= 0 ,0
Exp/Cntr=0.3,0.1

Type RM Length L Ch R = 1 ,7399    ,412,412,412
BEGIN DESCRIPTION:
Conroe Lake 042 15.0
END DESCRIPTION:
XS GIS Cut Line= 3
      3791525.84       10185887.      3791108.23     10186686.84
      3790727.25     10187202.96
#Sta/Elev= 30
  4097.7  252.74  4181.3  251.78  4188.7  250.48  4232.9  249.21    4255  247.28
  4431.7  238.29  4470.2  236.47    4520  235.74  4587.4  231.26  4608.2  230.88
  4632.5  228.94  4757.3  223.75  4869.4  223.33  4937.1  221.95  4950.4  220.81
  4972.5  221.85  4982.2  221.03  4992.8  217.86  4996.3  217.86  4999.6  220.35
  5004.5  220.35  5010.3  222.13  5024.9  226.39  5068.7  228.07  5117.1  233.77
  5290.1  243.22  5325.6  246.75  5461.3  254.73  5532.3  257.79  5641.5  259.68
#Mann= 5 ,-1 , 0
  4097.7     .17       0  4608.2     .15       0  4972.5     .09       0
  5010.3     .15       0  5068.7     .17       0
Bank Sta=4972.5,5010.3
XS Rating Curve= 0 ,0
Exp/Cntr=0.3,0.1

Type RM Length L Ch R = 1 ,6987    ,508,508,508
BEGIN DESCRIPTION:
Conroe Lake 042 14.0
END DESCRIPTION:
XS GIS Cut Line= 3
      3791366.12     10185831.45      3790918.23     10186396.84
      3790553.61     10187015.49
#Sta/Elev= 30
  4278.7  253.59  4319.5  254.33  4369.2  252.15  4433.3  247.97  4462.2   244.9
  4547.1  238.94  4648.1  233.15  4689.7  229.01  4768.9  224.17    4789  222.78
  4867.6  220.55  4954.2  220.94  4981.4  219.22    4994  216.69  4997.5  216.69
  4999.5  217.86  5016.5  218.99  5035.7  218.66  5047.8  218.91  5053.6  220.14
  5106.3  223.93  5287.8  233.64  5353.1  238.77  5389.3  240.23  5580.6  252.94
  5639.2  256.28  5660.6  256.28  5676.3  257.74  5682.1  257.23  5718.1   258.8
#Mann= 5 ,-1 , 0
  4278.7     .17       0  4768.9     .15       0  4981.4     .09       0
  5016.5     .15       0  5035.7     .17       0
Bank Sta=4981.4,5016.5
XS Rating Curve= 0 ,0
Exp/Cntr=0.3,0.1

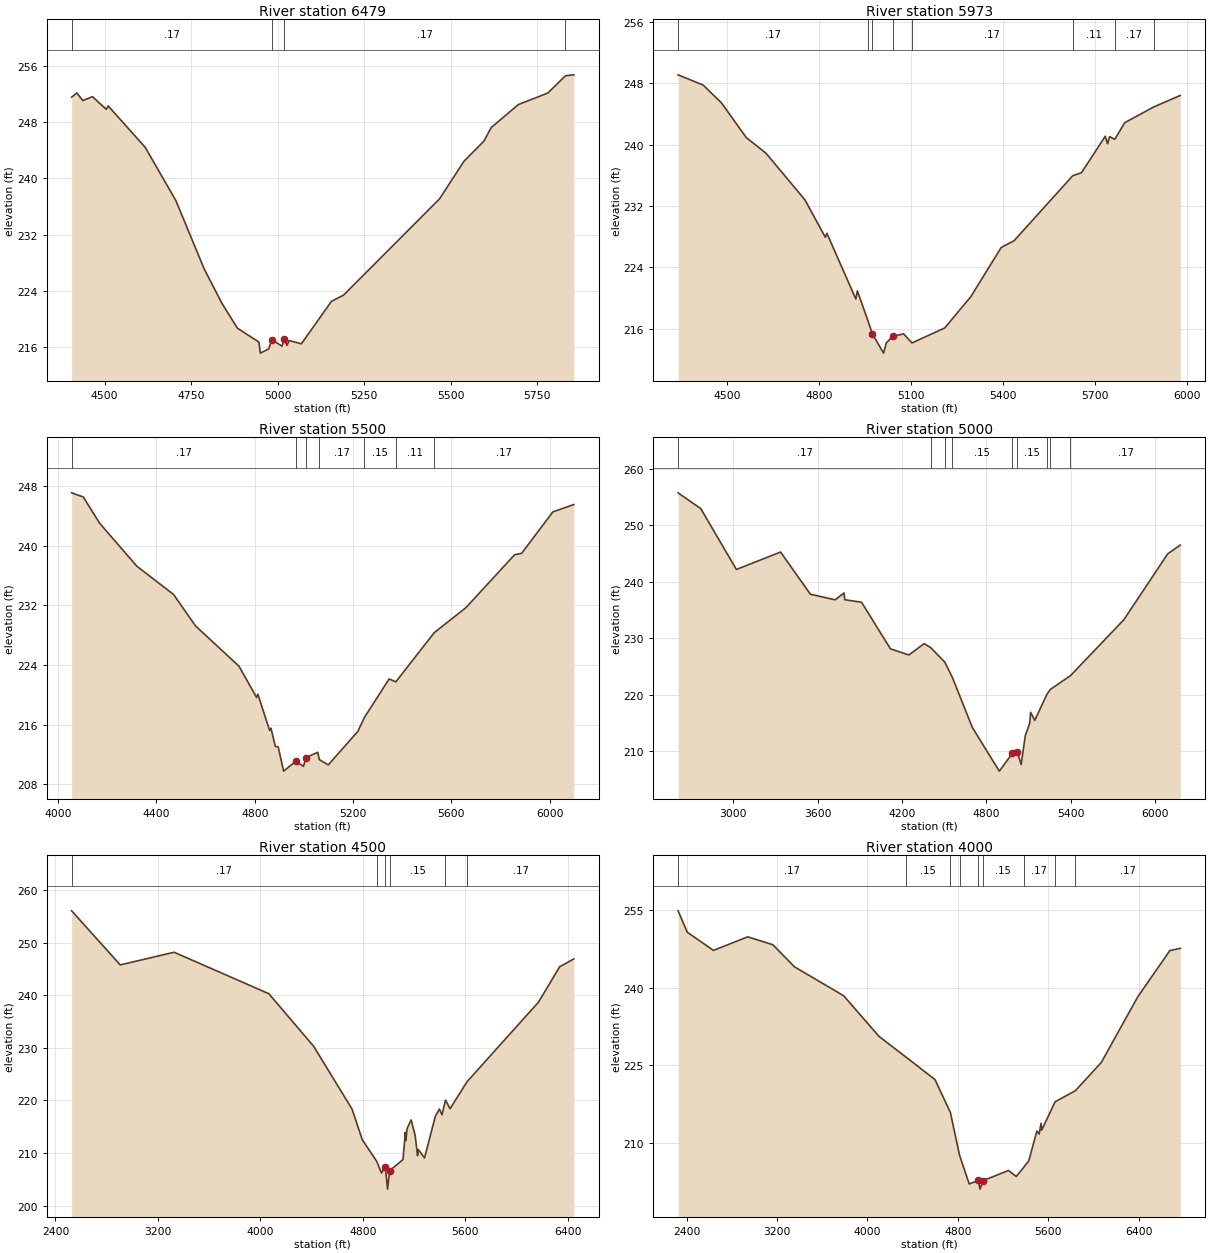
Type RM Length L Ch R = 1 ,6479    ,506,506,506
BEGIN DESCRIPTION:
Conroe Lake 042 13.0
END DESCRIPTION:
XS GIS Cut Line= 3
      3791269.31     10185741.01       3790732.7     10185998.53
       3790203.4     10186671.52
#Sta/Elev= 30
  4404.8  251.58  4419.8  252.18  4436.9  251.09  4465.1  251.65  4504.8  249.85
  4510.4  250.33  4617.2  244.45  4705.9  236.86  4787.7  227.13    4839  222.23
  4883.8  218.68  4946.2  216.69    4950  215.12  4974.4  215.72  4983.2  217.04
  5012.8  216.11  5019.1  217.15  5027.2  216.23  5033.6  216.91  5068.8  216.45
  5155.5  222.49  5190.8  223.39  5468.2   237.1  5538.7  242.45  5596.5  245.33
  5617.4  247.25    5696  250.53  5780.9  252.16    5832  254.63  5856.2  254.76
#Mann= 4 ,-1 , 0
  4404.8     .17       0  4983.2     .09       0  5019.1     .17       0
    5832     .11       0
Bank Sta=4983.2,5019.1
XS Rating Curve= 0 ,0
Exp/Cntr=0.3,0.1

Type RM Length L Ch R = 1 ,5973    ,473,473,473
BEGIN DESCRIPTION:
Conroe Lake 042 12.0
END DESCRIPTION:
XS GIS Cut Line= 3
       3791269.3     10185675.02      3790612.31     10185608.06
      3789881.68     10186260.74
#Sta/Elev= 30
  4339.6  249.12  4421.5  247.78  4481.8  245.43  4562.2  240.93  4626.3   238.9
  4753.2  232.83  4820.4  227.92  4825.5  228.43    4920  219.86    4925  220.92
    4960  216.97  4974.3  215.29  5010.6  212.79  5019.4  214.12  5040.8  214.97
  5075.9  215.31  5103.4  214.12  5210.5  216.08  5295.7  220.17  5394.8  226.58
    5437  227.47  5628.4  235.95  5656.9  236.34  5734.6   241.1  5742.1  240.12
  5748.9  241.06  5765.5  240.69  5798.2  242.87  5893.6  244.94  5979.7  246.43
#Mann= 8 ,-1 , 0
  4339.6     .17       0    4960     .15       0  4974.3     .09       0
  5040.8     .15       0  5103.4     .17       0  5628.4     .11       0
  5765.5     .17       0  5893.6     .11       0
Bank Sta=4974.3,5040.8
XS Rating Curve= 0 ,0
Exp/Cntr=0.3,0.1

Type RM Length L Ch R = 1 ,5500    ,500,500,500
BEGIN DESCRIPTION:
Conroe Lake 042 11.0
END DESCRIPTION:
XS GIS Cut Line= 3
      3791283.27      10185605.6      3790410.76     10185244.21
      3789683.24     10186066.46
#Sta/Elev= 30
  4055.6  247.11    4103  246.55  4169.7  243.02  4321.2  237.25  4469.9  233.48
  4559.4  229.25  4735.9  223.86  4807.6  219.66    4813   220.1  4860.7  215.22
  4866.2  215.53  4884.1  213.07  4895.5  213.03  4917.6  209.77  4967.1  211.09
  4998.9   210.4  5007.2  211.57  5056.5  212.29  5062.7  211.32  5099.2  210.61
  5219.7  215.11  5246.4  216.98  5346.8  222.14    5374  221.75  5529.7  228.33
  5658.8   231.7    5857   238.8  5885.5  238.99  6012.6  244.55  6097.9  245.54
#Mann= 7 ,-1 , 0
  4055.6     .17       0  4967.1     .09       0  5007.2     .15       0
  5062.7     .17       0  5246.4     .15       0    5374     .11       0
  5529.7     .17       0
Bank Sta=4967.1,5007.2
XS Rating Curve= 0 ,0
Exp/Cntr=0.3,0.1

Type RM Length L Ch R = 1 ,5000    ,500,500,500
BEGIN DESCRIPTION:
Conroe Lake 042 10.0
END DESCRIPTION:
XS GIS Cut Line= 3
      3792557.55      10184555.3      3790193.99     10184921.11
      3789662.56     10185975.56
#Sta/Elev= 30
  2608.3  255.74  2769.9  252.93  3022.9  242.16  3337.1  245.25  3549.1  237.78
  3725.5  236.79  3788.5     238  3793.6  236.81  3913.4  236.35  4118.9   228.1
  4250.1  227.02  4358.6  229.02  4405.3  228.32  4505.8  225.74  4559.3  223.04
  4701.5  214.17  4893.2  206.44    4986  209.58  5020.8  209.86  5048.7  207.61
  5078.3  212.75    5110  214.92  5115.6  216.86  5145.5  215.43  5231.5  220.03
  5256.5  220.92  5399.4  223.35  5779.2  233.26  6091.5  244.94  6180.8  246.49
#Mann= 9 ,-1 , 0
  2608.3     .17       0  4405.3     .15       0  4505.8     .17       0
  4559.3     .15       0    4986     .09       0  5020.8     .15       0
  5231.5     .17       0  5256.5     .11       0  5399.4     .17       0
Bank Sta=4986,5020.8
XS Rating Curve= 0 ,0
Exp/Cntr=0.3,0.1

Type RM Length L Ch R = 1 ,4500    ,500,500,500
BEGIN DESCRIPTION:
Conroe Lake 042 9.0
END DESCRIPTION:
XS GIS Cut Line= 3
      3792557.51     10184500.13      3790084.03     10184512.14
      3789638.47     10185890.52
#Sta/Elev= 30
  2526.5  256.07  2906.2  245.78  3326.2  248.19  4066.2  240.31  4416.2  230.31
  4716.2  218.36  4796.2  212.53  4909.3  208.39  4946.2  206.19  4976.2  207.34
  4993.8  203.12  5009.4  206.62  5114.5  208.75  5132.1  213.92  5137.3  212.36
    5146  214.64  5177.5  216.28  5209.1  213.38  5228.1  209.49  5233.4  210.67
  5282.6  209.06  5366.7  216.96  5398.7  218.36  5419.3  217.24  5446.1  220.06
  5482.3  218.43  5615.3  223.58  6172.5  238.69  6337.8  245.42  6448.6  246.92
#Mann= 6 ,-1 , 0
  2526.5     .17       0  4909.3     .15       0  4976.2     .09       0
  5009.4     .15       0  5446.1     .11       0  5615.3     .17       0
#XS Ineff= 2 , 0
       0                  5177.5       0  216.28
Permanent Ineff=
       F       F
Bank Sta=4976.2,5009.4
XS Rating Curve= 0 ,0
Exp/Cntr=0.3,0.1

Type RM Length L Ch R = 1 ,4000    ,496,496,496
BEGIN DESCRIPTION:
Conroe Lake 042 8.0
END DESCRIPTION:
XS GIS Cut Line= 3
      3792557.55     10184457.02       3789903.5     10184075.13
      3789603.41     10185811.71
#Sta/Elev= 30
  2325.8  254.91    2407  250.76  2638.7  247.24  2941.8  249.87    3164  248.34
    3356  244.05  3790.4  238.46  4103.6  230.57  4339.9   226.6  4598.7  222.21
  4735.3  215.82  4815.7  207.57  4901.8  201.97  4982.6  202.65  4997.3  200.97
  5023.4  202.61  5248.8  204.58  5317.7  203.43    5383  205.17  5429.3  206.49
  5500.3  212.24  5520.6  211.64  5537.7  213.74  5542.8  212.39  5661.5   217.9
    5841  220.04  6070.9  225.54  6393.4  238.25  6677.5  247.21  6769.5  247.64
#Mann= 9 ,-1 , 0
  2325.8     .17       0  4339.9     .15       0  4735.3     .17       0
  4815.7     .15       0  4982.6     .09       0  5023.4     .15       0
    5383     .17       0  5661.5     .11       0    5841     .17       0
Bank Sta=4982.6,5023.4
XS Rating Curve= 0 ,0
Exp/Cntr=0.3,0.1

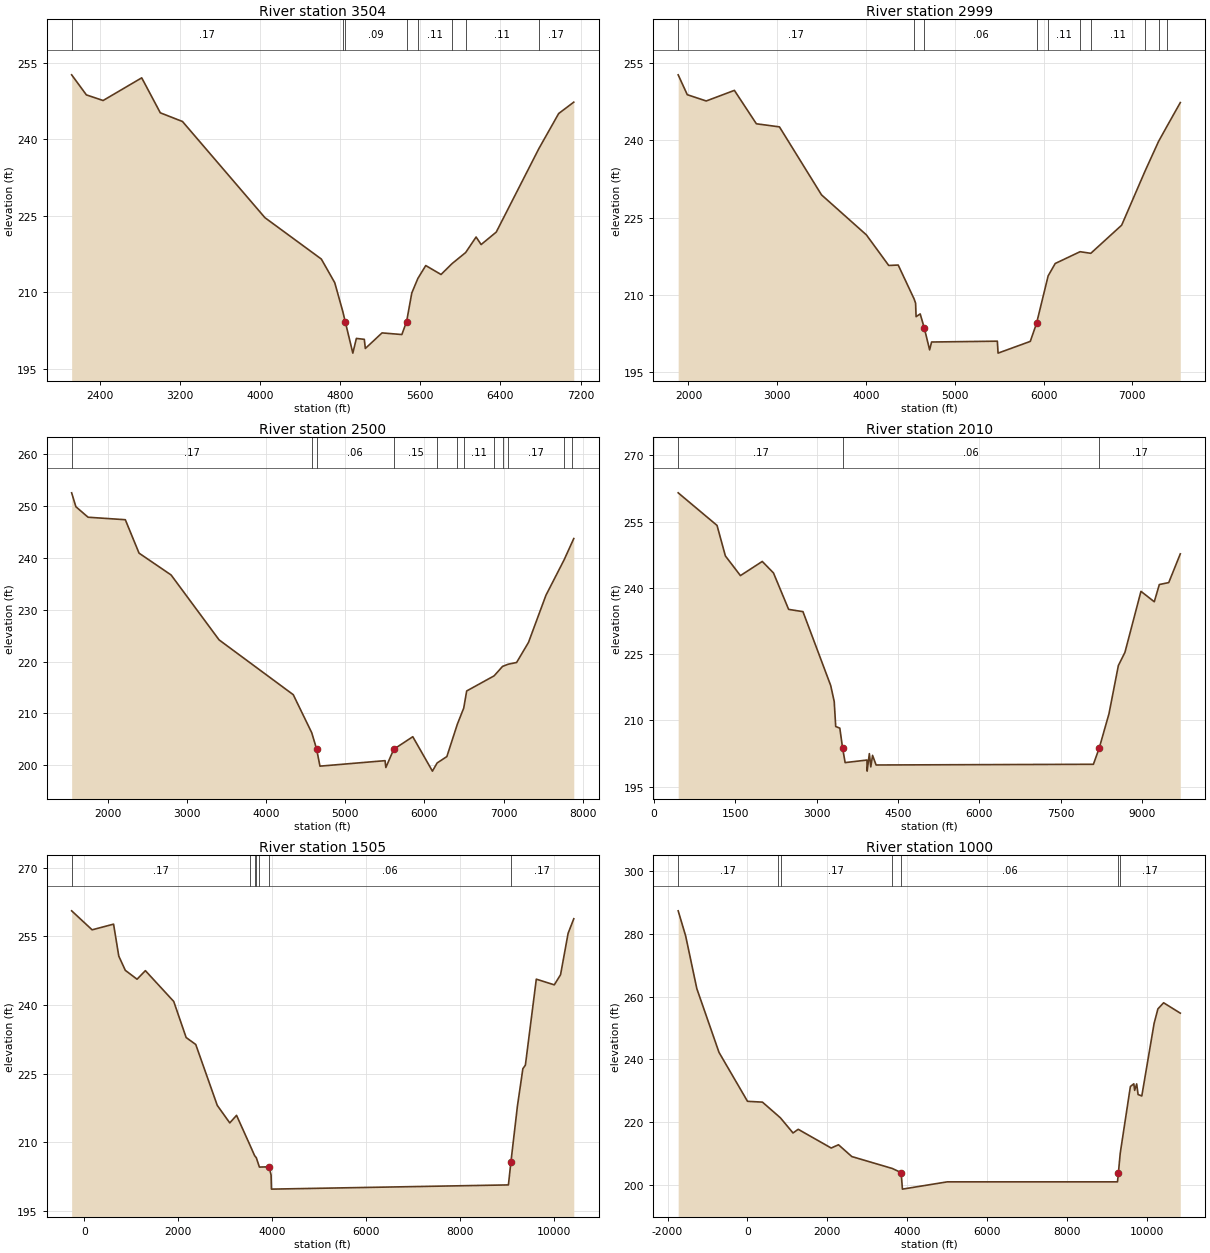
Type RM Length L Ch R = 1 ,3504    ,505,505,505
BEGIN DESCRIPTION:
Conroe Lake 042 7.0
END DESCRIPTION:
XS GIS Cut Line= 4
      3792559.24     10184425.98      3789804.07     10183618.41
      3789784.24     10183620.39      3789566.61     10185731.09
#Sta/Elev= 30
  2119.2  252.62  2266.5  248.69  2433.3  247.59  2818.8  252.03  3004.4  245.18
  3225.7  243.48  4048.5  224.65    4612  216.54  4745.6  211.92    4826  206.29
  4850.9  204.26  4926.4  198.12  4961.7     201    5041  200.82  5051.1  199.03
  5217.9  202.08  5415.9  201.76  5463.3  204.31  5514.9   209.9  5575.7  212.75
  5654.3  215.27  5806.9  213.52  5917.5  215.66  6052.8  217.82  6156.9  220.86
  6207.2  219.38    6358  221.82  6784.4   238.2  6981.3  245.04  7132.1  247.27
#Mann= 8 ,-1 , 0
  2119.2     .17       0    4826     .15       0  4850.9     .09       0
  5463.3     .15       0  5575.7     .11       0  5917.5     .17       0
  6052.8     .11       0  6784.4     .17       0
Bank Sta=4850.9,5463.3
XS Rating Curve= 0 ,0
Exp/Cntr=0.3,0.1

Type RM Length L Ch R = 1 ,2999    ,499,499,499
BEGIN DESCRIPTION:
Conroe Lake 042 6.0
END DESCRIPTION:
XS GIS Cut Line= 4
      3792579.91     10184396.65      3789746.82     10183118.14
      3789732.39     10183119.43      3789543.86      10185646.5
#Sta/Elev= 30
  1884.1  252.74  1986.7  248.88  2200.3  247.66  2517.4  249.72  2765.1  243.23
    3025  242.63  3499.1  229.42  4004.9  221.64  4256.1  215.71  4362.8  215.79
  4542.5  209.19  4558.8  208.37  4564.3  205.76  4610.5   206.3  4656.8  203.56
  4716.9  199.31  4738.8  200.84  5479.8     201  5487.9  198.68  5850.8  200.96
    5921  204.44  6051.9  213.68  6131.6  216.09  6411.7  218.38  6532.7  218.07
  6880.5  223.54  7142.9  234.01  7296.1  239.81  7394.4  242.86  7540.9  247.35
#Mann= 10 ,-1 , 0
  1884.1     .17       0  4542.5     .11       0  4656.8     .06       0
    5921     .15       0  6051.9     .11       0  6411.7     .17       0
  6532.7     .11       0  7142.9     .17       0  7296.1     .11       0
  7394.4     .17       0
Bank Sta=4656.8,5921
XS Rating Curve= 0 ,0
Exp/Cntr=0.3,0.1

Type RM Length L Ch R = 1 ,2500    ,490,490,490
BEGIN DESCRIPTION:
Conroe Lake 042 5.0
END DESCRIPTION:
XS GIS Cut Line= 4
      3792604.06     10184369.06       3789623.3     10182641.15
      3789607.74     10182646.34      3789517.54     10185522.55
#Sta/Elev= 30
  1546.3  252.57  1599.7  249.89  1753.7  247.86  2223.9  247.38  2397.3  240.93
  2801.8  236.72  3407.6  224.19  4344.3  213.61  4577.5  206.27  4638.4  203.15
  4681.4  199.82  5503.1  200.88  5513.1  199.56  5613.1  203.08  5853.2   205.5
  6101.3  198.86  6160.2  200.43  6283.4  201.67  6416.7  207.96  6496.4  211.03
  6533.6  214.33  6880.1  217.25  6986.2  219.07  7057.8  219.49  7163.9  219.83
  7313.9   223.7    7534  232.79    7764  239.65  7862.2  242.96  7885.7  243.75
#Mann= 12 ,-1 , 0
  1546.3     .17       0  4577.5     .11       0  4638.4     .06       0
  5613.1     .15       0  6160.2     .17       0  6416.7     .15       0
  6496.4     .11       0  6880.1     .17       0  6986.2     .11       0
  7057.8     .17       0    7764     .11       0  7862.2     .17       0
#XS Ineff= 2 , 0
       0                  5853.2       0   205.5
Permanent Ineff=
       F       F
Bank Sta=4638.4,5613.1
XS Rating Curve= 0 ,0
Exp/Cntr=0.3,0.1

Type RM Length L Ch R = 1 ,2010    ,505,505,505
BEGIN DESCRIPTION:
Conroe Lake 042 4.0
END DESCRIPTION:
XS GIS Cut Line= 5
       3793631.4     10183623.72      3789292.23     10182282.41
      3789279.16      10182297.1      3789007.45     10185490.41
      3789841.96     10186713.35
#Sta/Elev= 30
   452.2  261.52  1167.7  254.14    1322  247.22  1598.8  242.77  2000.8  245.98
  2207.1  243.38  2486.5  235.12  2750.1  234.61    3261  217.88  3325.7  214.26
  3353.1   208.6  3428.9  208.22  3480.8  203.66  3526.7  200.42  3928.8     201
    3932  198.49  3972.8  202.45  3999.3  199.45  4031.9  202.06  4097.2  199.88
  8098.7  200.04  8205.3  203.69  8385.2  211.47  8558.2   222.4  8679.3  225.39
  8974.6  239.21  9219.8  236.85  9312.6  240.75    9486  241.19    9699   247.7
#Mann= 3 ,-1 , 0
   452.2     .17       0  3480.8     .06       0  8205.3     .17       0
Bank Sta=3480.8,8205.3
XS Rating Curve= 0 ,0
Exp/Cntr=0.3,0.1

Type RM Length L Ch R = 1 ,1505    ,505,505,505
BEGIN DESCRIPTION:
Conroe Lake 042 3.0
END DESCRIPTION:
XS GIS Cut Line= 5
      3793924.98       10183477.      3788870.39     10182005.79
      3788861.74     10182018.76      3788540.17     10185935.34
      3789267.02      10187226.3
#Sta/Elev= 30
    -270  260.55   166.2   256.4   622.7  257.64   733.6  250.66   872.7  247.55
  1122.6  245.61  1299.7  247.48  1903.7  240.75  2167.9  232.87  2372.4  231.35
  2830.7  218.04  3096.6  214.22    3241  215.87  3524.2  209.42  3625.8  207.06
  3661.4  206.62  3727.5  204.57  3934.7  204.62  3976.3  202.82  3984.3  199.75
  9029.5  200.67    9083  205.69  9221.7  217.92  9337.3  226.06  9390.8  226.83
  9623.4  245.62 10006.4  244.38 10139.8   246.6 10300.4  255.63 10421.2  258.82
#Mann= 7 ,-1 , 0
    -270     .17       0  3524.2     .15       0  3625.8     .11       0
  3661.4     .17       0  3727.5     .11       0  3934.7     .06       0
    9083     .17       0
Bank Sta=3934.7,9083
XS Rating Curve= 0 ,0
Exp/Cntr=0.3,0.1

Type RM Length L Ch R = 1 ,1000    ,500,500,500
BEGIN DESCRIPTION:
Conroe Lake 042 2.0
END DESCRIPTION:
XS GIS Cut Line= 4
      3794887.79     10180032.57      3788398.41     10181834.08
      3788217.71     10186113.16      3789114.38     10187377.23
#Sta/Elev= 30
 -1734.8  287.39 -1548.1  279.42 -1267.8  262.58  -712.5  242.26      .7  226.67
   374.5  226.41   756.2  222.17   826.6  221.37  1139.9  216.58  1269.3  217.75
  2095.7  211.78  2277.4  212.82  2611.6  209.06  3622.1  205.27    3846  203.95
  3877.6  198.68    5000     201  9260.8     201  9282.9  203.78  9329.6  210.17
  9583.2  231.39  9669.3  232.25  9690.2  230.16  9740.6  232.22  9776.3  228.84
  9868.8  228.37 10177.4  251.53 10272.1  256.13 10414.8  258.08 10832.7  254.77
#Mann= 7 ,-1 , 0
 -1734.8     .17       0   756.2     .11       0   826.6     .17       0
  3622.1     .11       0    3846     .06       0  9282.9     .11       0
  9329.6     .17       0
Bank Sta=3846,9282.9
XS Rating Curve= 0 ,0
Exp/Cntr=0.3,0.1

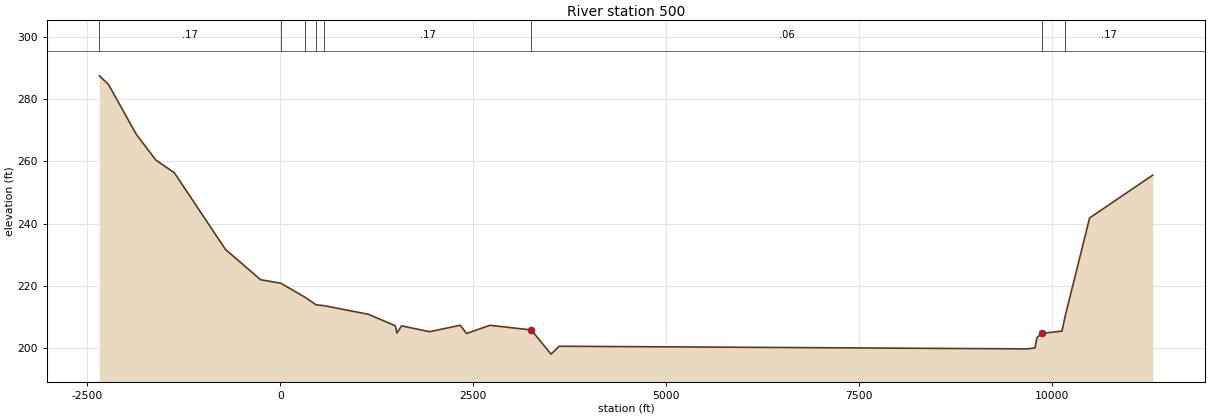
Type RM Length L Ch R = 1 ,500     ,0,0,0
BEGIN DESCRIPTION:
Conroe Lake 042 1.0
END DESCRIPTION:
XS GIS Cut Line= 5
      3794909.53     10179837.25      3789771.77     10180687.71
      3787911.28     10181734.65      3787998.33     10186856.47
      3788941.66     10187562.94
#Sta/Elev= 30
 -2342.5  287.42 -2225.7  284.72 -1864.7  268.69 -1610.4  260.39 -1371.4  256.34
  -708.9  231.72  -252.8     222     7.1   220.9   319.2  216.43   464.9  213.95
   565.6   213.7  1140.8  210.93  1490.6  207.25    1512  204.91    1573  207.22
  1934.1  205.33  2331.9   207.4    2413  204.75  2717.1  207.39  3251.7   205.9
  3508.2  198.14    3613  200.67  9677.1  199.82  9777.1  200.12  9801.1  203.46
  9867.1   204.8 10125.4  205.53 10169.2  210.57 10483.5  241.82 11301.1  255.57
#Mann= 8 ,-1 , 0
 -2342.5     .17       0     7.1     .11       0   319.2     .17       0
   464.9     .11       0   565.6     .17       0  3251.7     .06       0
  9867.1     .11       0 10169.2     .17       0
Bank Sta=3251.7,9867.1
XS Rating Curve= 0 ,0
Exp/Cntr=0.3,0.1

Chan Stop Cuts=-1
Use User Specified Reach Order=0
Composite Channel Slope=5