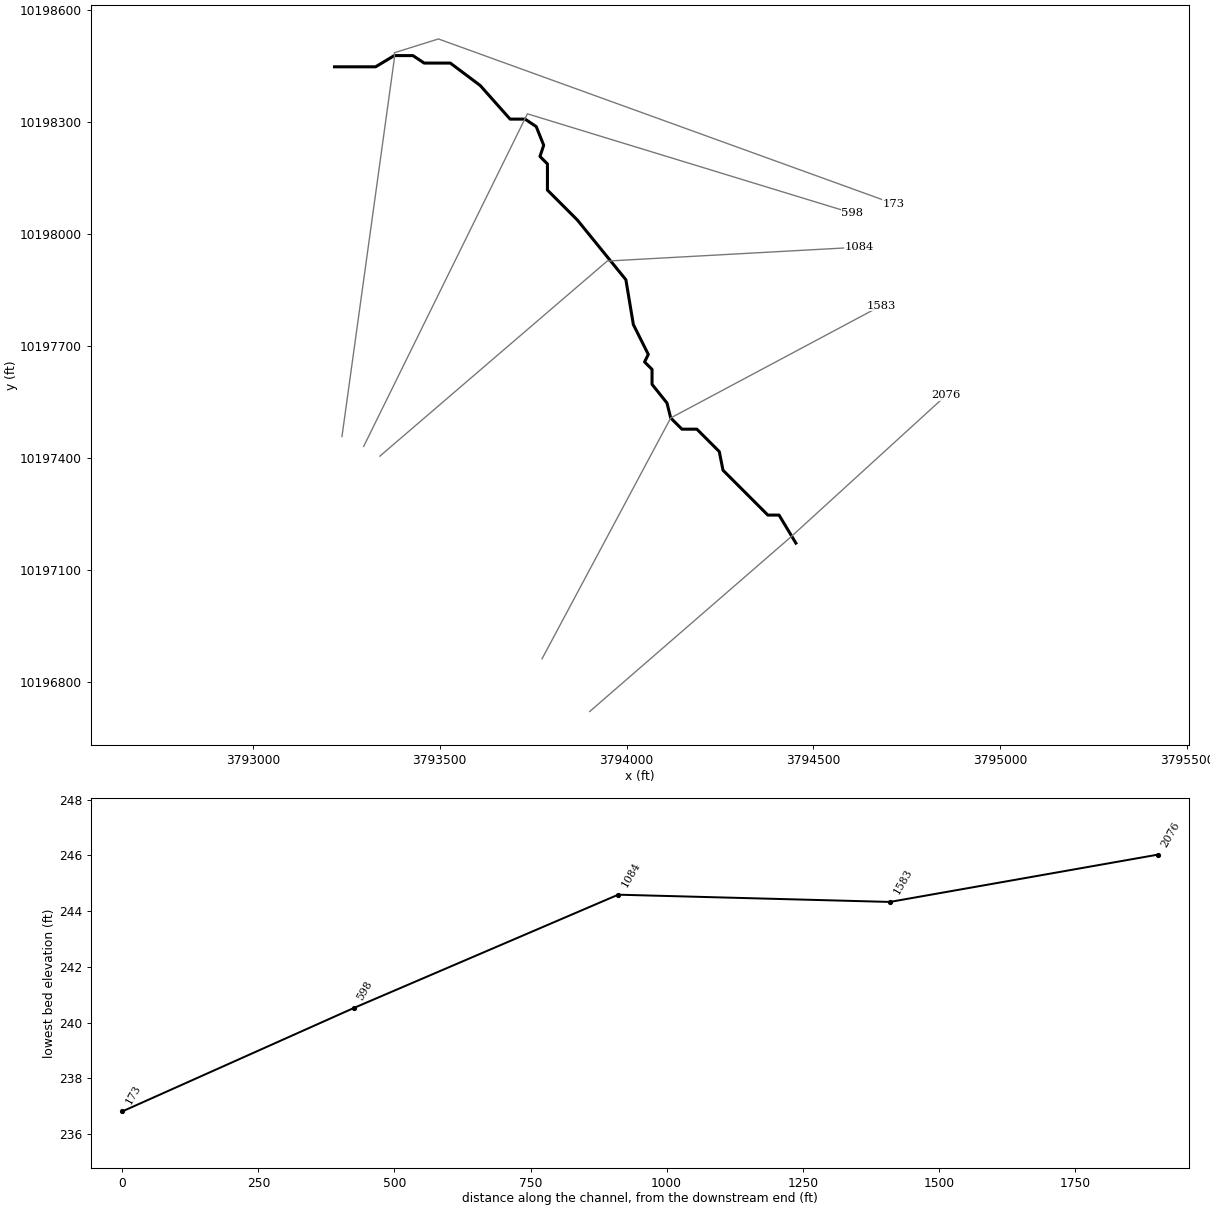
--- Conroe Lake 045.prj (project) ---

Proj Title=Conroe Lake 045 Base Level Engineering
Current Plan=p01
Default Exp/Contr=0.3,0.1
English Units
Geom File=g01
Flow File=f01
Flow File=f02
Plan File=p01
Y Axis Title=Elevation
X Axis Title(PF)=Main Channel Distance
X Axis Title(XS)=Station
BEGIN DESCRIPTION:
Conroe Lake 045
END DESCRIPTION:
DSS File=dss
DSS Export Rating Curves= 0
DSS Export Rating Curve Sorted= 0
DSS Export Volume Flow Curves= 0
DXF OffsetX= 0
DXF OffsetY= 0
DXF ScaleX= 1
DXF ScaleY= 10

--- Conroe Lake 045.p01 (plan) ---

Plan Title=Multiple Run
Short Identifier=Multiple
Geom File=g01
Flow File=f01
Subcritical Flow
K Sum by GR= 0
Std Step Tol= 0.01
Critical Tol= 0.01
Num of Std Step Trials= 20
Max Error Tol= 0.3
Flow Tol Ratio= 0.001
Split Flow NTrial= 30
Split Flow Tol= 0.02
Split Flow Ratio= 0.02
Log Output Level= 0
Friction Slope Method= 1
Unsteady Friction Slope Method= 2
Unsteady Bridges Friction Slope Method= 1
Parabolic Critical Depth
Global Vel Dist=  1 , 1 , 1
Global Log Level= 0
CheckData=True
Encroach Param= -1, 0, 0, 0
BEGIN DESCRIPTION:
Multiple Run
END DESCRIPTION:

--- Conroe Lake 045.f01 (steady flow) ---

Flow Title=Multiple
Program Version=4.10
Number of Profiles= 7
Profile Names=10-year,25-year,50-year,1pct_min,100-year,1pct_plu,500-year
River Rch & RM=Conroe Lake 045,Reach-1         ,2076
     590     799    1079     481    1452    4385    2714
Boundary for River Rch & Prof#=Conroe Lake 045,Reach-1         , 1
Up Type= 0
Dn Type= 3
Dn Slope=0.005
Boundary for River Rch & Prof#=Conroe Lake 045,Reach-1         , 2
Up Type= 0
Dn Type= 3
Dn Slope=0.005
Boundary for River Rch & Prof#=Conroe Lake 045,Reach-1         , 3
Up Type= 0
Dn Type= 3
Dn Slope=0.005
Boundary for River Rch & Prof#=Conroe Lake 045,Reach-1         , 4
Up Type= 0
Dn Type= 3
Dn Slope=0.005
Boundary for River Rch & Prof#=Conroe Lake 045,Reach-1         , 5
Up Type= 0
Dn Type= 3
Dn Slope=0.005
Boundary for River Rch & Prof#=Conroe Lake 045,Reach-1         , 6
Up Type= 0
Dn Type= 3
Dn Slope=0.005
Boundary for River Rch & Prof#=Conroe Lake 045,Reach-1         , 7
Up Type= 0
Dn Type= 3
Dn Slope=0.005
DSS Import GetInterval= 0
DSS Import GetPeak= 0
DSS Import FillOption= 0

--- Conroe Lake 045.f02 (steady flow) ---

Flow Title=Orig_BLE_Flow
Program Version=4.10
Number of Profiles= 7
Profile Names=10-year,25-year,50-year,1pct_min,100-year,1pct_plu,500-year
River Rch & RM=Conroe Lake 045,Reach-1         ,2076
     590     783     938     370    1117    3373    1578
Boundary for River Rch & Prof#=Conroe Lake 045,Reach-1         , 1
Up Type= 0
Dn Type= 3
Dn Slope=0.005
Boundary for River Rch & Prof#=Conroe Lake 045,Reach-1         , 2
Up Type= 0
Dn Type= 3
Dn Slope=0.005
Boundary for River Rch & Prof#=Conroe Lake 045,Reach-1         , 3
Up Type= 0
Dn Type= 3
Dn Slope=0.005
Boundary for River Rch & Prof#=Conroe Lake 045,Reach-1         , 4
Up Type= 0
Dn Type= 3
Dn Slope=0.005
Boundary for River Rch & Prof#=Conroe Lake 045,Reach-1         , 5
Up Type= 0
Dn Type= 3
Dn Slope=0.005
Boundary for River Rch & Prof#=Conroe Lake 045,Reach-1         , 6
Up Type= 0
Dn Type= 3
Dn Slope=0.005
Boundary for River Rch & Prof#=Conroe Lake 045,Reach-1         , 7
Up Type= 0
Dn Type= 3
Dn Slope=0.005
DSS Import GetInterval= 0
DSS Import GetPeak= 0
DSS Import FillOption= 0

--- Conroe Lake 045.g01 (geometry) ---

Geom Title=Existing Conditions
Program Version=4.10

River Reach=Conroe Lake 045 ,Reach-1
Reach XY= 30
      3794453.23     10197171.84      3794408.23     10197246.84
      3794378.23     10197246.84      3794258.23     10197366.84
      3794248.23     10197416.84      3794188.23     10197476.84
      3794148.23     10197476.84      3794118.23     10197506.84
      3794108.23     10197546.84      3794068.23     10197596.84
      3794068.23     10197636.84      3794048.23     10197656.84
      3794058.23     10197676.84      3794018.23     10197756.84
      3793998.23     10197876.84      3793868.23     10198036.84
      3793788.23     10198116.84      3793788.23     10198186.84
      3793768.23     10198206.84      3793778.23     10198236.84
      3793758.23     10198286.84      3793728.23     10198306.84
      3793688.23     10198306.84      3793608.23     10198396.84
      3793528.23     10198456.84      3793458.23     10198456.84
      3793428.23     10198476.84      3793378.23     10198476.84
      3793328.23     10198446.84      3793218.23     10198446.84

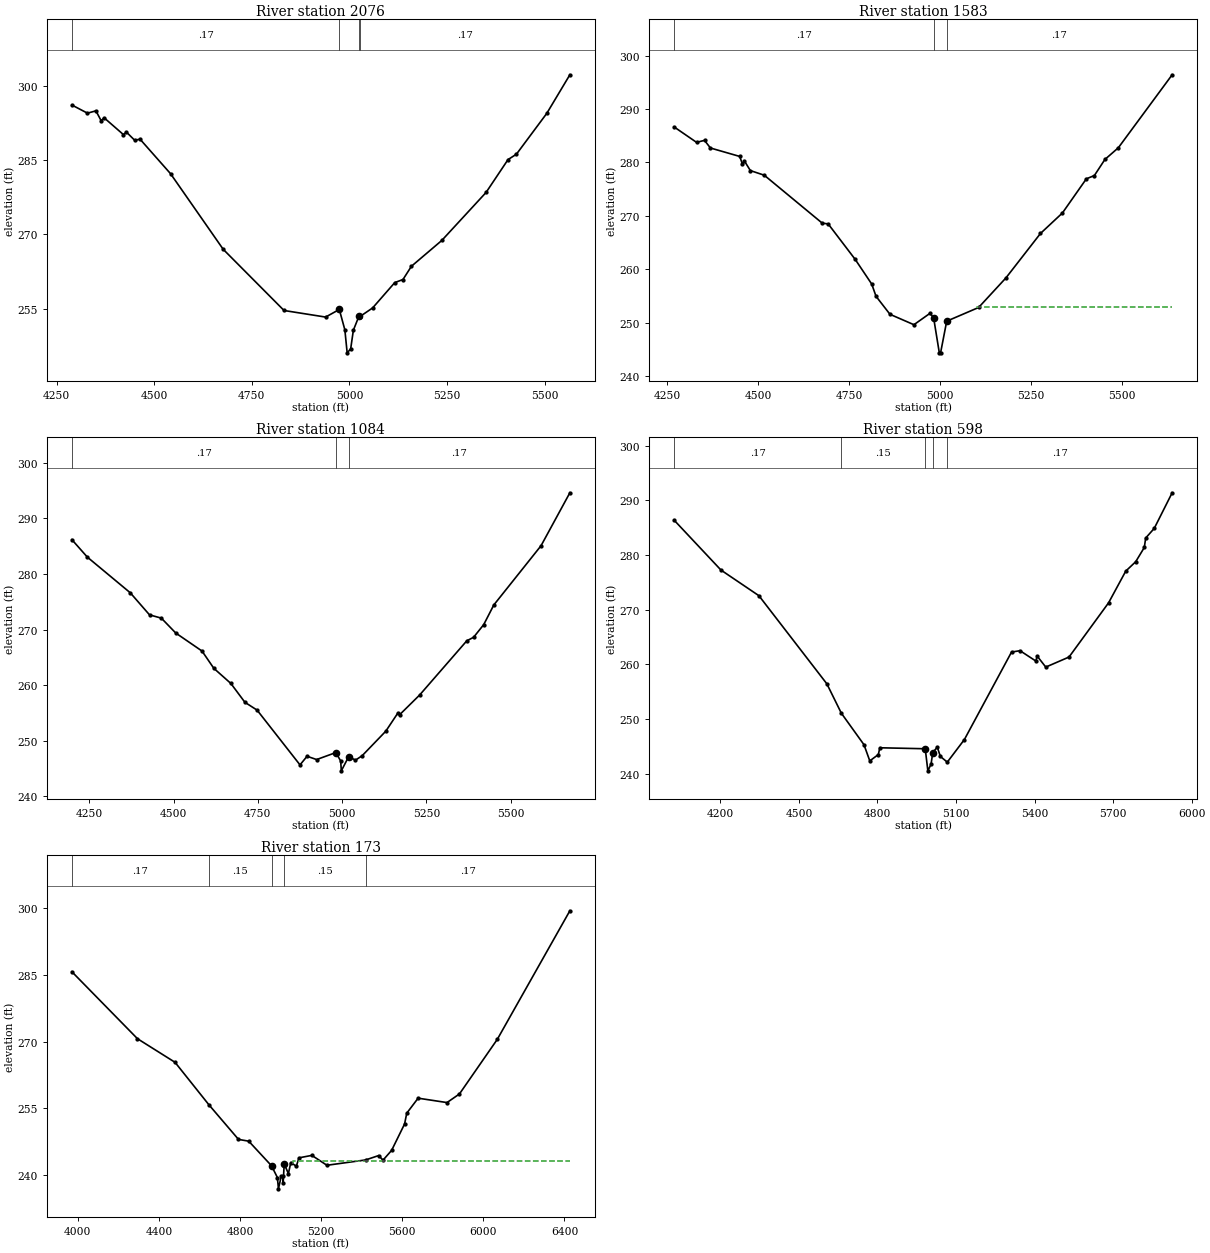
Type RM Length L Ch R = 1 ,2076    ,493,493,493
BEGIN DESCRIPTION:
Conroe Lake 045 4.0
END DESCRIPTION:
XS GIS Cut Line= 3
      3793901.43     10196721.07      3794438.23     10197186.84
      3794855.09     10197567.19
#Sta/Elev= 30
  4289.3  296.19  4329.2  294.54  4350.8  295.01  4364.3  293.01  4371.9   293.6
  4421.3   290.2  4428.9  290.71  4449.8  289.08    4464  289.26  4541.9  282.29
  4676.8  266.98  4832.5   254.6  4938.9  253.27    4974  254.81  4988.2  250.69
  4994.1  246.03  5003.1  246.83    5010  250.61  5024.2  253.43  5025.8  253.32
  5059.3  255.12    5116  260.25    5137  260.87  5158.6  263.55  5236.3  268.77
  5349.8   278.5  5405.9  285.14  5427.5  286.24  5505.2   294.5  5564.3  302.31
#Mann= 4 ,-1 , 0
  4289.3     .17       0    4974     .09       0  5024.2     .15       0
  5025.8     .17       0
Bank Sta=4974,5024.2
XS Rating Curve= 0 ,0
Exp/Cntr=0.3,0.1

Type RM Length L Ch R = 1 ,1583    ,499,499,499
BEGIN DESCRIPTION:
Conroe Lake 045 3.0
END DESCRIPTION:
XS GIS Cut Line= 3
      3793773.75      10196862.1      3794118.23     10197506.84
        3794681.     10197806.98
#Sta/Elev= 30
    4269  286.65  4330.5  283.77  4352.4  284.14  4368.7  282.71  4449.2  281.13
  4456.5  279.72  4462.2  280.27  4478.4  278.48  4516.7  277.61    4676  268.63
  4692.3  268.49  4766.7  261.83    4812  257.22  4823.9  254.92  4862.2  251.55
    4928   249.6  4971.9  251.72  4982.1  250.93  4997.8  244.33  5001.3  244.33
  5018.1  250.26  5105.9  252.83  5180.9  258.37  5275.9   266.7  5336.1  270.53
    5402  276.94    5424  277.55  5452.9  280.56  5489.8  282.75  5637.8  296.43
#Mann= 3 , 0 , 0
    4269     .17       0  4982.1     .09       0  5018.1     .17       0
#XS Ineff= 2 , 0
       0                  5100.3       0  252.93
Permanent Ineff=
       F       F
Bank Sta=4982.1,5018.1
XS Rating Curve= 0 ,0
Exp/Cntr=0.3,0.1

Type RM Length L Ch R = 1 ,1084    ,486,486,486
BEGIN DESCRIPTION:
Conroe Lake 045 2.0
END DESCRIPTION:
XS GIS Cut Line= 3
       3793339.7      10197404.6      3793948.23     10197926.84
       3794623.2     10197964.09
#Sta/Elev= 30
  4198.1  286.18  4244.1  283.03  4371.4  276.62  4428.5  272.65  4463.6  272.06
  4506.4  269.38  4584.3  266.14  4619.4  263.03  4669.9  260.31  4711.6  256.92
  4747.8  255.51  4875.1  245.66    4896  247.21  4924.5  246.62  4981.6  247.88
  4995.9  246.35  4997.7  244.59  5019.7  247.16  5039.7  246.51  5059.7  247.32
  5129.8  251.73  5166.2  255.05  5171.2  254.71    5230  258.22  5370.2  267.99
  5390.2  268.61  5420.3  270.89  5450.3  274.43  5590.5  285.09    5676  294.61
#Mann= 3 , 0 , 0
  4198.1     .17       0  4981.6     .09       0  5019.7     .17       0
Bank Sta=4981.6,5019.7
XS Rating Curve= 0 ,0
Exp/Cntr=0.3,0.1

Type RM Length L Ch R = 1 ,598     ,425,425,425
BEGIN DESCRIPTION:
Conroe Lake 045 1.0
END DESCRIPTION:
XS GIS Cut Line= 3
      3793296.31     10197430.65      3793734.58     10198320.98
      3794604.56     10198054.92
#Sta/Elev= 30
  4023.4  286.37  4202.2  277.25  4347.1  272.56  4606.6  256.44    4662  251.06
  4748.4   245.3  4770.6  242.34  4803.3   243.5  4808.9  244.74  4982.4  244.56
  4992.4  240.52  5004.7  241.76  5011.1  243.87  5028.5  244.85  5040.1  243.16
  5066.6  242.11    5132  246.25    5312  262.25  5344.4   262.5  5404.8  260.61
    5410  261.51  5442.8   259.5  5531.6  261.34  5682.7  271.26  5748.3  277.06
  5786.3  278.78  5819.1  281.38  5824.4  283.11  5857.1  284.88  5925.5  291.39
#Mann= 5 ,-1 , 0
  4023.4     .17       0    4662     .15       0  4982.4     .09       0
  5011.1     .15       0  5066.6     .17       0
Bank Sta=4982.4,5011.1
XS Rating Curve= 0 ,0
Exp/Cntr=0.3,0.1

Type RM Length L Ch R = 1 ,173     ,0,0,0
BEGIN DESCRIPTION:
Conroe Lake 045 1.5
END DESCRIPTION:
XS GIS Cut Line= 5
      3793238.22     10197457.13      3793378.58     10198469.82
      3793378.58     10198484.55      3793496.47     10198521.41
      3794714.41     10198080.53
#Sta/Elev= 30
  3970.6  285.73  4294.1  270.64  4479.4  265.32  4646.2  255.76  4792.3  247.95
  4842.8  247.55  4955.1  242.01  4984.1  239.36  4989.3  236.81  5003.5  239.75
  5009.9  239.75  5012.5  238.11  5017.7  242.43  5038.4  240.24  5050.2  242.74
  5077.4  241.91  5090.8   243.8    5154  244.35  5228.4  242.12    5419  243.32
  5483.6  244.31  5504.9  243.27  5547.5  245.48  5611.3  251.42  5622.1  253.86
  5678.1  257.24  5820.6  256.25  5881.9  258.19  6068.6   270.5  6426.5  299.47
#Mann= 5 ,-1 , 0
  3970.6     .17       0  4646.2     .15       0  4955.1     .09       0
  5017.7     .15       0    5419     .17       0
#XS Ineff= 2 , 0
       0                  5059.3       0  243.03
Permanent Ineff=
       F       F
Bank Sta=4955.1,5017.7
XS Rating Curve= 0 ,0
Exp/Cntr=0.3,0.1

Chan Stop Cuts=-1
Use User Specified Reach Order=0
Composite Channel Slope=5