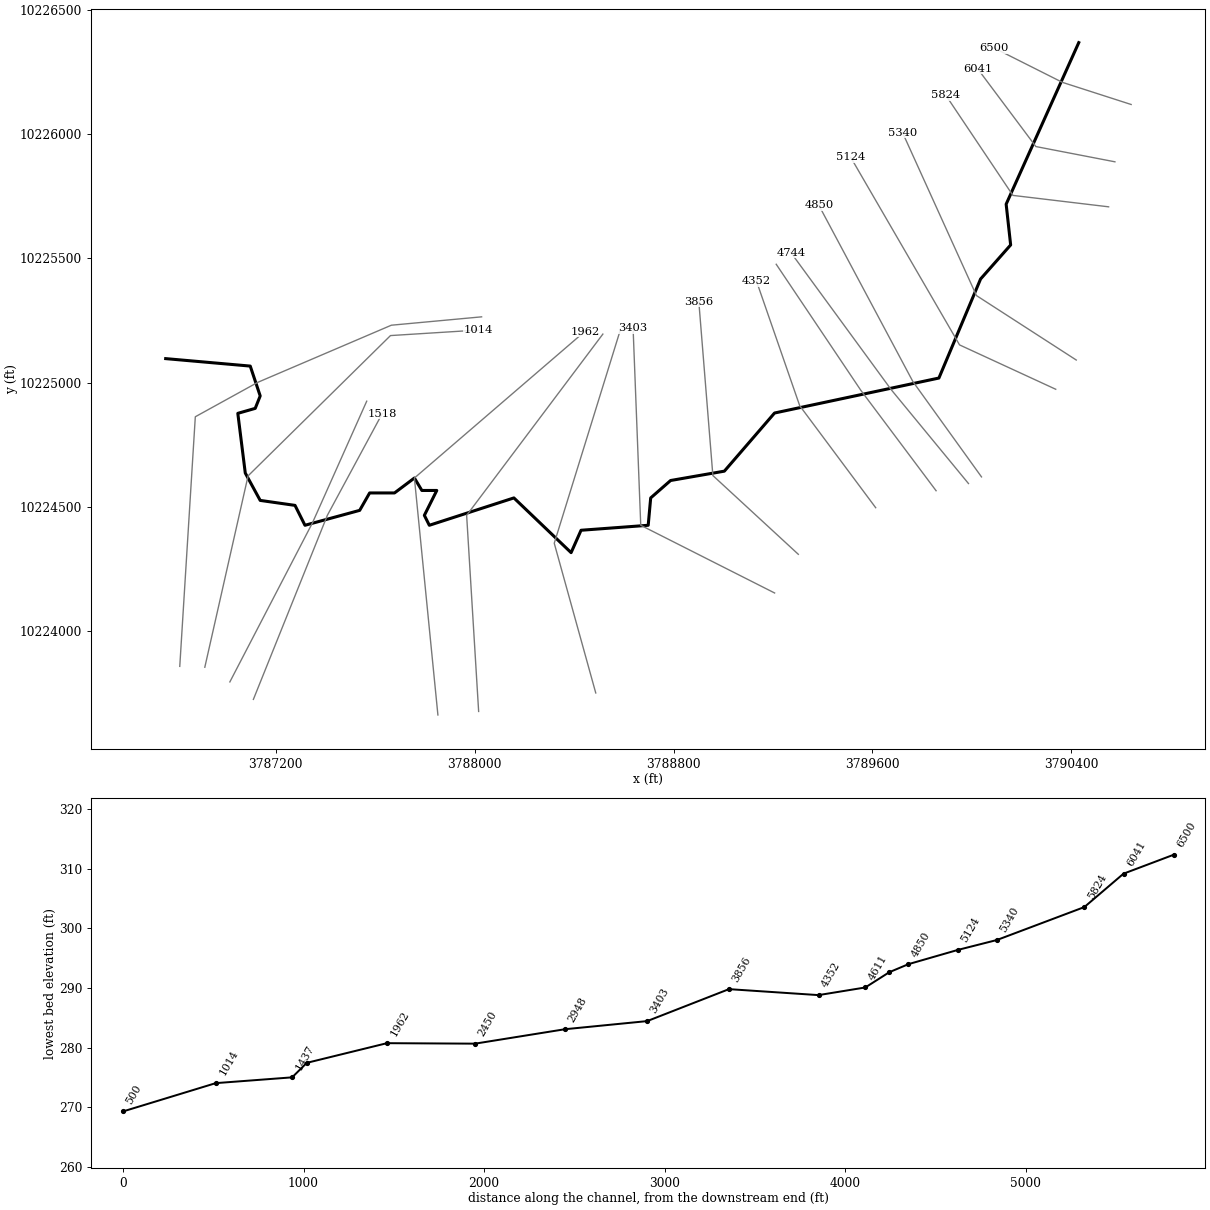
--- Conroe Lake 046.prj (project) ---

Proj Title=Conroe Lake 046 Base Level Engineering
Current Plan=p01
Default Exp/Contr=0.3,0.1
English Units
Geom File=g01
Flow File=f01
Flow File=f02
Plan File=p01
Y Axis Title=Elevation
X Axis Title(PF)=Main Channel Distance
X Axis Title(XS)=Station
BEGIN DESCRIPTION:
Conroe Lake 046
END DESCRIPTION:
DSS File=dss
DSS Export Rating Curves= 0
DSS Export Rating Curve Sorted= 0
DSS Export Volume Flow Curves= 0
DXF OffsetX= 0
DXF OffsetY= 0
DXF ScaleX= 1
DXF ScaleY= 10

--- Conroe Lake 046.p01 (plan) ---

Plan Title=Multiple Run
Short Identifier=Multiple
Geom File=g01
Flow File=f01
Subcritical Flow
K Sum by GR= 0
Std Step Tol= 0.01
Critical Tol= 0.01
Num of Std Step Trials= 20
Max Error Tol= 0.3
Flow Tol Ratio= 0.001
Split Flow NTrial= 30
Split Flow Tol= 0.02
Split Flow Ratio= 0.02
Log Output Level= 0
Friction Slope Method= 1
Unsteady Friction Slope Method= 2
Unsteady Bridges Friction Slope Method= 1
Parabolic Critical Depth
Global Vel Dist=  1 , 1 , 1
Global Log Level= 0
CheckData=True
Encroach Param= -1, 0, 0, 0
BEGIN DESCRIPTION:
Multiple Run
END DESCRIPTION:

--- Conroe Lake 046.f01 (steady flow) ---

Flow Title=Multiple
Program Version=4.10
Number of Profiles= 7
Profile Names=10-year,25-year,50-year,1pct_min,100-year,1pct_plu,500-year
River Rch & RM=Conroe Lake 046,Reach-1         ,6500
     608     819    1103     489    1477    4460    2735
River Rch & RM=Conroe Lake 046,Reach-1         ,6041
     608     819    1103     489    1477    4460    2735
Boundary for River Rch & Prof#=Conroe Lake 046,Reach-1         , 1
Up Type= 0
Dn Type= 3
Dn Slope=0.006
Boundary for River Rch & Prof#=Conroe Lake 046,Reach-1         , 2
Up Type= 0
Dn Type= 3
Dn Slope=0.006
Boundary for River Rch & Prof#=Conroe Lake 046,Reach-1         , 3
Up Type= 0
Dn Type= 3
Dn Slope=0.006
Boundary for River Rch & Prof#=Conroe Lake 046,Reach-1         , 4
Up Type= 0
Dn Type= 3
Dn Slope=0.006
Boundary for River Rch & Prof#=Conroe Lake 046,Reach-1         , 5
Up Type= 0
Dn Type= 3
Dn Slope=0.006
Boundary for River Rch & Prof#=Conroe Lake 046,Reach-1         , 6
Up Type= 0
Dn Type= 3
Dn Slope=0.006
Boundary for River Rch & Prof#=Conroe Lake 046,Reach-1         , 7
Up Type= 0
Dn Type= 3
Dn Slope=0.006
DSS Import GetInterval= 0
DSS Import GetPeak= 0
DSS Import FillOption= 0

--- Conroe Lake 046.f02 (steady flow) ---

Flow Title=Orig_BLE_Flow
Program Version=4.10
Number of Profiles= 7
Profile Names=10-year,25-year,50-year,1pct_min,100-year,1pct_plu,500-year
River Rch & RM=Conroe Lake 046,Reach-1         ,6500
     608     803     959     376    1136    3431    1590
River Rch & RM=Conroe Lake 046,Reach-1         ,6041
     608     803     959     376    1136    3431    1590
Boundary for River Rch & Prof#=Conroe Lake 046,Reach-1         , 1
Up Type= 0
Dn Type= 3
Dn Slope=0.005
Boundary for River Rch & Prof#=Conroe Lake 046,Reach-1         , 2
Up Type= 0
Dn Type= 3
Dn Slope=0.005
Boundary for River Rch & Prof#=Conroe Lake 046,Reach-1         , 3
Up Type= 0
Dn Type= 3
Dn Slope=0.005
Boundary for River Rch & Prof#=Conroe Lake 046,Reach-1         , 4
Up Type= 0
Dn Type= 3
Dn Slope=0.005
Boundary for River Rch & Prof#=Conroe Lake 046,Reach-1         , 5
Up Type= 0
Dn Type= 3
Dn Slope=0.005
Boundary for River Rch & Prof#=Conroe Lake 046,Reach-1         , 6
Up Type= 0
Dn Type= 3
Dn Slope=0.005
Boundary for River Rch & Prof#=Conroe Lake 046,Reach-1         , 7
Up Type= 0
Dn Type= 3
Dn Slope=0.005
DSS Import GetInterval= 0
DSS Import GetPeak= 0
DSS Import FillOption= 0

--- Conroe Lake 046.g01 (geometry) ---

Geom Title=Existing Conditions
Program Version=4.10

River Reach=Conroe Lake 046 ,Reach-1
Reach XY= 30
      3790429.33     10226367.15       3790137.4     10225717.72
      3790155.46     10225553.83      3790034.62     10225417.02
      3789867.03     10225018.76      3789206.17     10224878.13
      3789004.44     10224644.45      3788788.23     10224606.84
      3788708.23     10224536.84      3788698.23     10224426.84
      3788428.23     10224406.84      3788388.23     10224316.84
      3788158.23     10224536.84      3787818.23     10224426.84
      3787798.23     10224466.84      3787848.23     10224566.84
      3787788.23     10224566.84      3787758.23     10224616.84
      3787678.23     10224556.84      3787578.23     10224556.84
      3787538.23     10224486.84      3787318.23     10224426.84
      3787278.23     10224506.84      3787138.23     10224526.84
      3787078.23     10224636.84      3787048.23     10224876.84
      3787118.23     10224896.84      3787138.23     10224946.84
      3787098.23     10225066.84      3786758.23     10225096.84

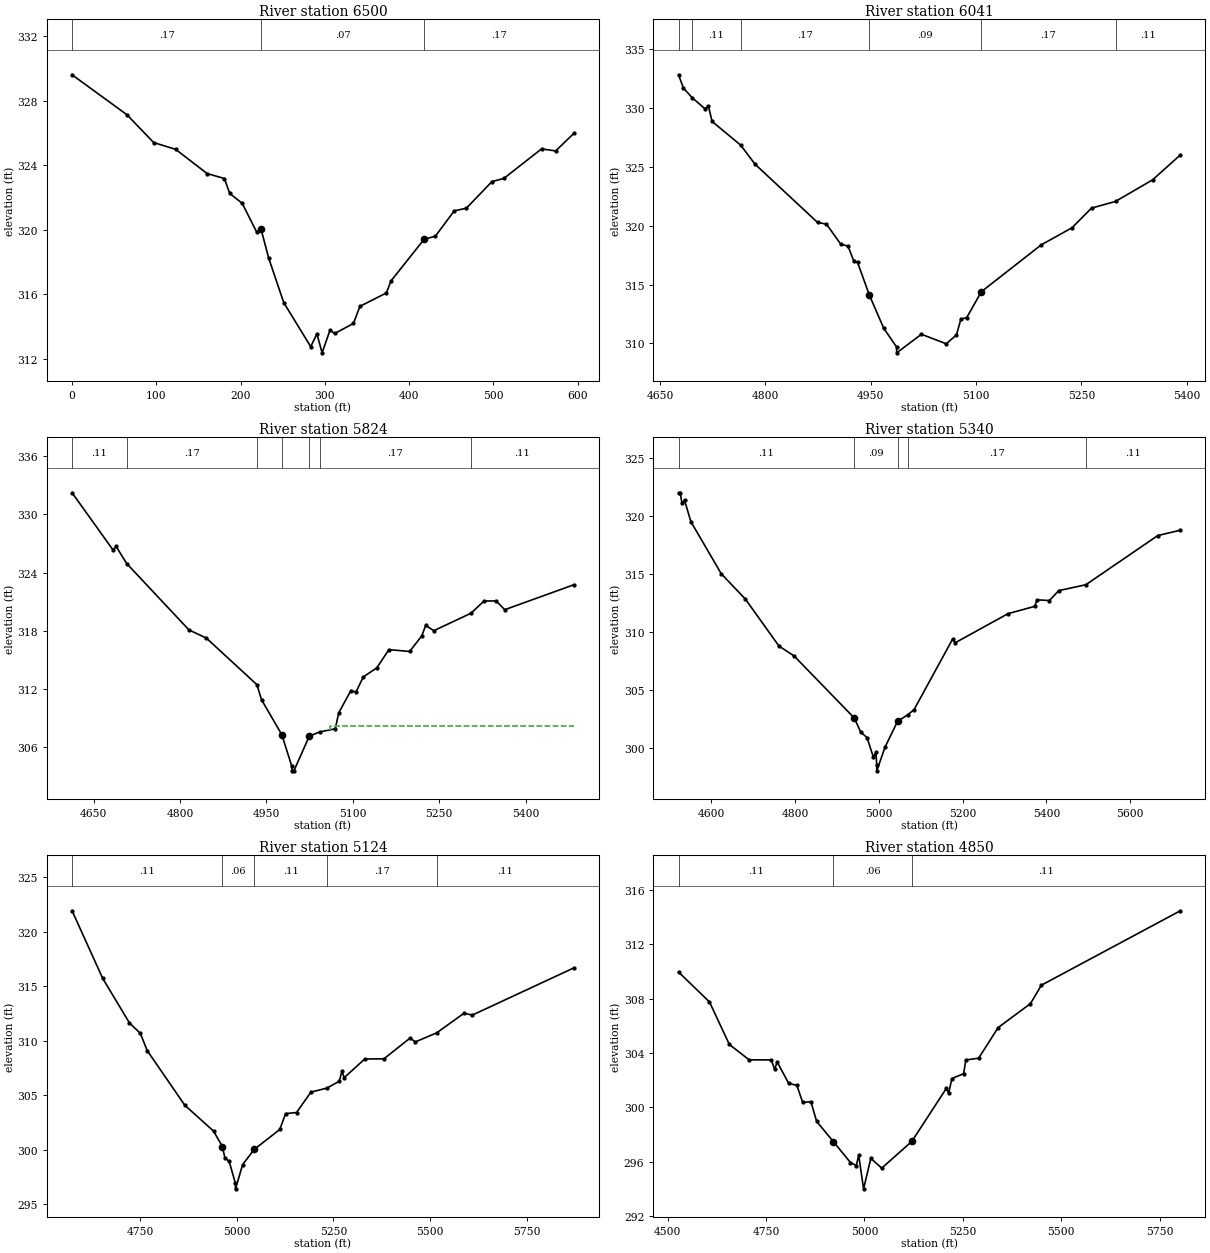
Type RM Length L Ch R = 1 ,6500    ,279,279,279
XS GIS Cut Line= 3
      3790639.95     10226118.47       3790363.4     10226207.51
       3790089.3     10226345.43
#Sta/Elev= 30
       0  329.61    65.2  327.13    96.8  325.41   122.9  324.99   160.2  323.49
   180.8  323.18     187  322.26   201.8  321.65   219.1  319.86   224.3  320.03
   233.3  318.25   251.2  315.49   283.2  312.76   290.5  313.56   296.7  312.38
     306  313.78   311.6  313.58   333.9   314.2   341.5  315.26   372.9  316.09
   378.5  316.84   417.6  319.41   431.1  319.61   453.5  321.18   467.8  321.34
   498.2  322.99   512.4  323.19   557.1  325.02   573.8  324.89   595.4  325.98
#Mann= 3 , 0 , 0
       0     .17       0   224.3     .07       0   417.6     .17       0
Bank Sta=224.3,417.6
XS Rating Curve= 0 ,0
Exp/Cntr=0.3,0.1

Type RM Length L Ch R = 1 ,6041    ,217,217,217
BEGIN DESCRIPTION:
Conroe Lake 046 12.0
END DESCRIPTION:
XS GIS Cut Line= 3
      3790574.74     10225888.05       3790256.8      10225949.4
       3790022.6     10226262.37
#Sta/Elev= 30
  4676.2  332.84  4683.2   331.7  4695.7  330.89  4713.6  329.96  4718.7  330.19
    4724  328.87  4764.8  326.85  4785.1  325.24  4874.2  320.28  4886.9  320.14
  4907.3  318.43  4917.5  318.27  4926.1  316.97  4931.2  316.88    4948   314.1
  4968.4  311.29  4986.7  309.69    4987  309.19  5022.1  310.77  5057.5  309.96
  5072.1  310.72  5078.3  312.05  5086.7  312.19  5107.5  314.39  5192.9  318.38
  5236.7  319.83  5264.4   321.5  5298.6  322.07  5351.3   323.9  5390.9  326.02
#Mann= 6 ,-1 , 0
  4676.2     .17       0  4695.7     .11       0  4764.8     .17       0
    4948     .09       0  5107.5     .17       0  5298.6     .11       0
Bank Sta=4948,5107.5
XS Rating Curve= 0 ,0
Exp/Cntr=0.3,0.1

Type RM Length L Ch R = 1 ,5824    ,484,484,484
BEGIN DESCRIPTION:
Conroe Lake 046 11.0
END DESCRIPTION:
XS GIS Cut Line= 3
      3790549.34     10225707.09      3790164.57       10225753.
      3789895.38     10226154.75
#Sta/Elev= 30
  4612.5  332.22  4683.9  326.31  4688.9   326.7  4707.4  324.93  4815.4   318.1
  4845.6  317.26  4933.4  312.46  4941.4  310.91  4976.6  307.31  4993.8  304.09
  4994.1  303.59  4997.6  303.59  5024.4  307.17  5042.1  307.59  5069.4  307.92
  5075.4  309.56  5096.5  311.85  5105.4   311.7    5118  313.26  5141.5  314.19
  5162.5  316.07  5198.5  315.88  5219.5  317.48  5226.4  318.56  5240.5  318.02
  5305.1  319.82  5327.6  321.07  5348.6  321.09  5363.6  320.18  5483.6  322.75
#Mann= 7 ,-1 , 0
  4612.5     .11       0  4707.4     .17       0  4933.4     .11       0
  4976.6     .07       0  5024.4     .11       0  5042.1     .17       0
  5305.1     .11       0
#XS Ineff= 2 , 0
       0                  5060.4       0  308.19
Permanent Ineff=
       F       F
Bank Sta=4976.6,5024.4
XS Rating Curve= 0 ,0
Exp/Cntr=0.3,0.1

Type RM Length L Ch R = 1 ,5340    ,216,216,216
BEGIN DESCRIPTION:
Conroe Lake 046 10.0
END DESCRIPTION:
XS GIS Cut Line= 3
      3790419.24     10225091.19      3790017.96     10225350.35
      3789720.79     10226005.51
#Sta/Elev= 30
  4522.3  321.99  4526.1  321.99  4530.6  321.09  4536.6  321.35  4551.7  319.51
  4624.3  315.02  4681.7  312.85    4762   308.8  4797.8  307.96  4941.7  302.61
  4956.9   301.4    4972  300.93  4987.2  299.24  4993.1  299.68  4995.1  298.57
  4995.3  298.07  5014.8   300.1  5044.7  302.32  5069.8  302.91  5084.1  303.33
  5176.4  309.42  5181.9  309.08  5308.3  311.59  5372.1  312.22  5377.6  312.78
  5407.1  312.72  5429.2  313.57    5494  314.08  5665.6  318.31  5719.4  318.77
#Mann= 5 ,-1 , 0
  4522.3     .11       0  4941.7     .09       0  5044.7     .11       0
  5069.8     .17       0    5494     .11       0
Bank Sta=4941.7,5044.7
XS Rating Curve= 0 ,0
Exp/Cntr=0.3,0.1

Type RM Length L Ch R = 1 ,5124    ,274,274,274
BEGIN DESCRIPTION:
Mapping XS 90cf7250
END DESCRIPTION:
XS GIS Cut Line= 3
      3790336.65     10224973.68      3789949.99       10225152.
      3789512.67     10225905.72
#Sta/Elev= 30
  4574.2  321.92  4653.5  315.71  4722.4  311.64  4750.8  310.67  4768.3   309.1
  4865.6  304.08  4939.9  301.71  4962.9  300.29  4969.3  299.23  4980.3  298.94
  4996.4  296.91  4996.7  296.41  5015.2  298.64  5045.2  300.03  5111.3  301.86
  5126.1  303.31  5154.4  303.41  5191.6  305.28  5232.8  305.65  5264.8  306.28
  5271.9  307.19  5277.7  306.61  5330.7  308.32  5380.4  308.34  5448.3  310.25
  5461.4  309.89  5516.8  310.72  5587.4  312.52  5608.9  312.35  5871.4  316.68
#Mann= 5 ,-1 , 0
  4574.2     .11       0  4962.9     .06       0  5045.2     .11       0
  5232.8     .17       0  5516.8     .11       0
Bank Sta=4962.9,5045.2
XS Rating Curve= 0 ,0
Exp/Cntr=0.3,0.1

Type RM Length L Ch R = 1 ,4850    ,106,106,106
BEGIN DESCRIPTION:
Conroe Lake 046 9.0
END DESCRIPTION:
XS GIS Cut Line= 3
      3790038.26     10224621.35      3789762.16     10225005.04
      3789384.27     10225713.45
#Sta/Elev= 30
  4527.3  309.95    4606  307.75  4656.4  304.63  4706.7   303.5  4763.2  303.49
  4771.7  302.79  4777.9  303.35  4807.3  301.77  4828.2  301.62  4842.9  300.37
  4863.8  300.42  4878.5  298.97  4921.2  297.48  4964.4  295.95  4979.2  295.73
  4985.3  296.48  4997.7  294.02  5016.1  296.26  5043.8  295.54  5120.2   297.5
  5208.1   301.4  5213.8  301.04  5222.2  302.12    5252  302.48  5257.7  303.49
  5290.2  303.62  5339.8  305.87    5422  307.63  5449.6  308.98  5802.9  314.45
#Mann= 3 , 0 , 0
  4527.3     .11       0  4921.2     .06       0  5120.2     .11       0
Bank Sta=4921.2,5120.2
XS Rating Curve= 0 ,0
Exp/Cntr=0.3,0.1

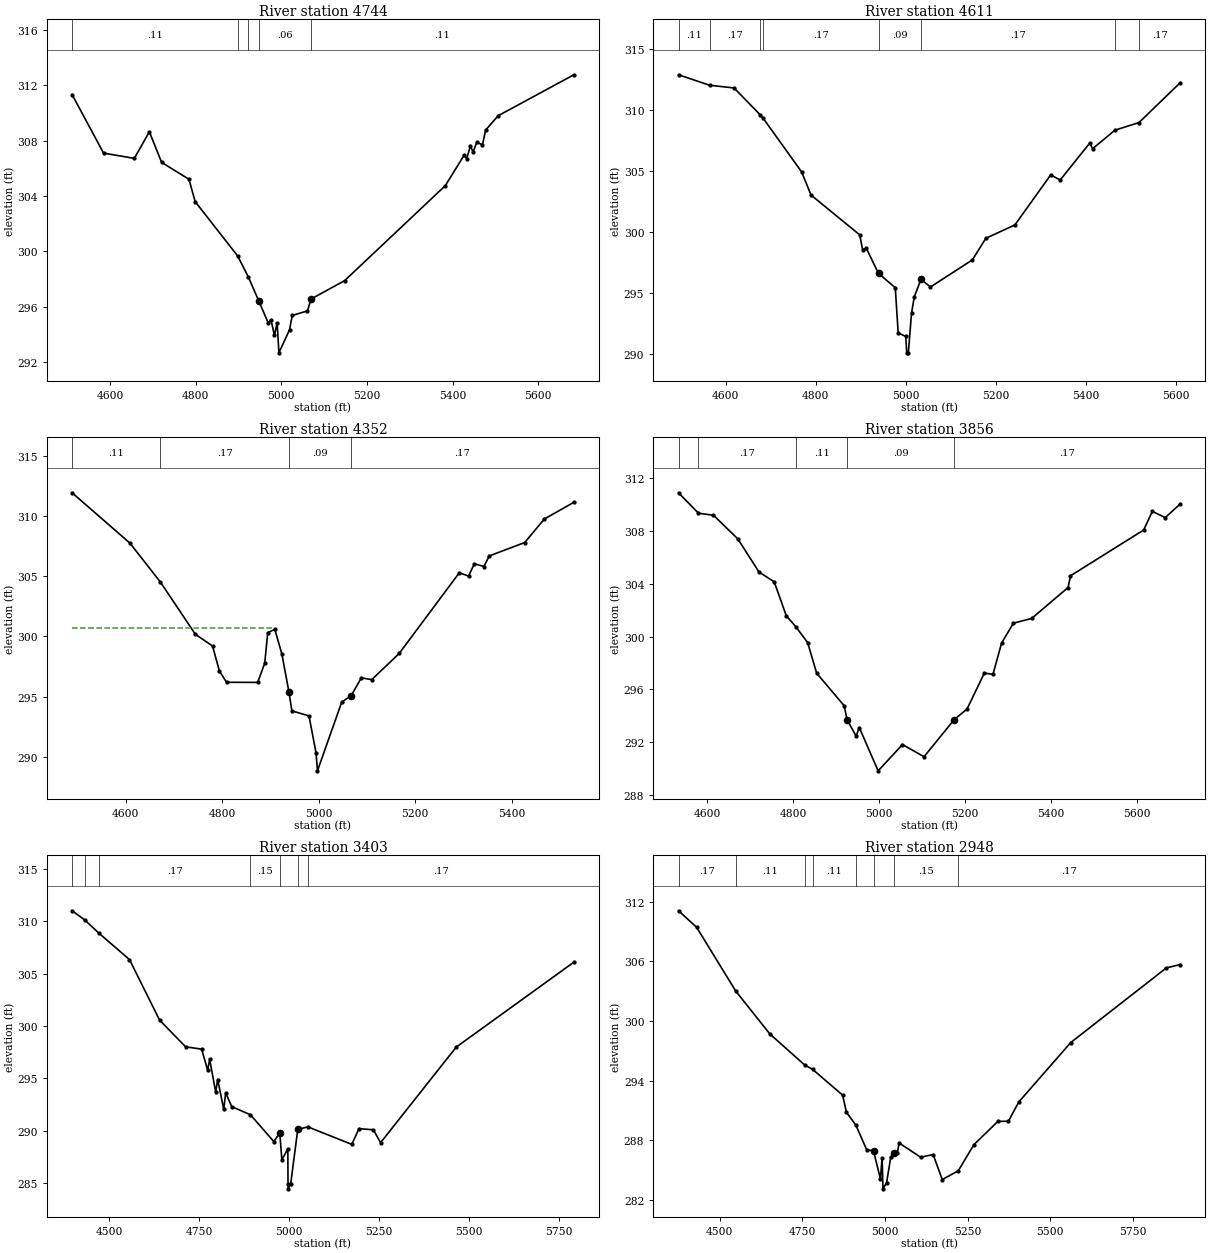
Type RM Length L Ch R = 1 ,4744    ,133,133,133
BEGIN DESCRIPTION:
Mapping XS de0efd5a
END DESCRIPTION:
XS GIS Cut Line= 3
       3789985.9     10224594.66      3789675.36     10224971.88
      3789271.83      10225523.3
#Sta/Elev= 30
  4511.4  311.33    4585   307.1  4656.8  306.72  4691.9  308.64  4720.6  306.43
  4784.4  305.21  4798.8   303.6  4898.1  299.67  4923.1  298.15  4947.3  296.43
  4969.5  294.83    4976  295.06  4983.9  293.93  4990.3  294.82  4994.5  292.67
  5019.4  294.35  5025.6  295.37  5061.1   295.7  5069.6  296.56  5147.7  297.88
  5383.1  304.75    5427  306.95  5433.2   306.7  5441.7  307.64  5447.9  307.16
  5456.4  307.87  5469.9  307.71  5477.2  308.76  5506.5   309.8  5683.3  312.76
#Mann= 5 ,-1 , 0
  4511.4     .11       0  4898.1     .17       0  4923.1     .11       0
  4947.3     .06       0  5069.6     .11       0
Bank Sta=4947.3,5069.6
XS Rating Curve= 0 ,0
Exp/Cntr=0.3,0.1

Type RM Length L Ch R = 1 ,4611    ,259,259,259
BEGIN DESCRIPTION:
Mapping XS 884bc429
END DESCRIPTION:
XS GIS Cut Line= 3
      3789855.69     10224565.76      3789552.96     10224969.71
      3789212.95     10225476.16
#Sta/Elev= 30
  4495.2  312.91  4564.4  312.05  4618.6  311.83  4676.3  309.64  4682.7  309.37
  4768.6  304.95  4789.5  303.05  4897.8  299.78  4904.1  298.57  4912.4  298.68
  4939.5  296.62  4976.7  295.45  4983.2  291.74    5000  291.46  5002.2  290.11
  5005.7  290.11  5012.9  293.38  5018.9   294.7  5033.9  296.14  5054.9  295.51
    5148  297.73  5177.9   299.5  5242.5   300.6    5322   304.7    5343  304.28
    5409  307.32    5415  306.85  5464.9  308.37  5518.1  308.99    5610  312.27
#Mann= 8 ,-1 , 0
  4495.2     .11       0  4564.4     .17       0  4676.3     .11       0
  4682.7     .17       0  4939.5     .09       0  5033.9     .17       0
  5464.9     .11       0  5518.1     .17       0
Bank Sta=4939.5,5033.9
XS Rating Curve= 0 ,0
Exp/Cntr=0.3,0.1

Type RM Length L Ch R = 1 ,4352    ,496,496,496
BEGIN DESCRIPTION:
Conroe Lake 046 8.0
END DESCRIPTION:
XS GIS Cut Line= 3
      3789612.84     10224497.55       3789307.3     10224907.65
      3789133.94     10225407.33
#Sta/Elev= 30
  4488.6  311.91  4608.6  307.73  4671.9  304.49  4744.1  300.17  4779.8  299.19
  4794.2   297.1  4808.8  296.18  4873.4  296.17    4888  297.76  4894.3   300.3
  4908.9  300.57  4923.5  298.54  4938.1   295.4  4944.3  293.81  4979.8  293.39
  4994.4  290.32  4997.3  288.83  5047.7  294.54  5067.1  295.06  5088.3  296.55
  5109.9   296.4  5166.9  298.58  5291.4  305.27  5310.6     305  5322.6  306.02
  5342.3  305.79  5353.7  306.67    5427  307.78  5467.6  309.73  5528.9  311.12
#Mann= 4 ,-1 , 0
  4488.6     .11       0  4671.9     .17       0  4938.1     .09       0
  5067.1     .17       0
#XS Ineff= 2 , 0
       0  4902.6  300.69               0
Permanent Ineff=
       F       F
Bank Sta=4938.1,5067.1
XS Rating Curve= 0 ,0
Exp/Cntr=0.3,0.1

Type RM Length L Ch R = 1 ,3856    ,453,453,453
BEGIN DESCRIPTION:
Conroe Lake 046 7.0
END DESCRIPTION:
XS GIS Cut Line= 3
      3789301.76      10224310.2      3788958.23     10224626.84
      3788901.73     10225326.07
#Sta/Elev= 30
  4532.8   310.9  4579.2  309.35  4614.1   309.2  4670.8  307.41  4720.1   304.9
  4755.7  304.15  4783.6  301.59  4806.2  300.74  4833.5  299.55  4854.5  297.23
  4918.6  294.76  4925.4   293.7  4946.4  292.46  4953.8  293.11  4997.7  289.83
  5054.4  291.82  5104.6   290.9  5174.8  293.71  5204.9  294.52    5245  297.24
  5265.1  297.14  5285.2  299.51  5312.7  301.02  5355.4  301.38    5440  303.72
  5445.7  304.61  5616.2  308.08  5636.3  309.49  5666.4  309.02  5701.5  310.06
#Mann= 5 ,-1 , 0
  4532.8     .11       0  4579.2     .17       0  4806.2     .11       0
  4925.4     .09       0  5174.8     .17       0
Bank Sta=4925.4,5174.8
XS Rating Curve= 0 ,0
Exp/Cntr=0.3,0.1

Type RM Length L Ch R = 1 ,3403    ,455,455,455
BEGIN DESCRIPTION:
Conroe Lake 046 6.0
END DESCRIPTION:
XS GIS Cut Line= 3
      3789206.52     10224154.65      3788668.23     10224426.84
      3788637.52     10225217.95
#Sta/Elev= 30
  4396.8  310.98  4431.6  310.12  4471.9  308.83  4556.4  306.33    4640  300.56
  4712.4  298.01    4757  297.79  4773.7  295.79  4779.3  296.82    4796   293.7
  4801.6  294.89  4818.3  292.06  4823.9  293.61  4840.6  292.31  4892.7  291.53
  4957.6  288.98  4974.3  289.79  4979.9  287.25  4996.6  288.27  4997.1  284.97
  4997.4  284.47  5004.6  284.97  5024.2  290.13  5052.1  290.38  5174.4  288.71
  5194.4  290.21  5234.4   290.1  5254.4  288.87  5464.6  297.98  5791.7  306.08
#Mann= 7 ,-1 , 0
  4396.8     .17       0  4431.6     .11       0  4471.9     .17       0
  4892.7     .15       0  4974.3     .09       0  5024.2     .15       0
  5052.1     .17       0
Bank Sta=4974.3,5024.2
XS Rating Curve= 0 ,0
Exp/Cntr=0.3,0.1

Type RM Length L Ch R = 1 ,2948    ,498,498,498
BEGIN DESCRIPTION:
Conroe Lake 046 5.0
END DESCRIPTION:
XS GIS Cut Line= 3
      3788487.33     10223752.79      3788320.48     10224354.59
      3788584.85     10225207.67
#Sta/Elev= 30
  4375.5  311.07  4430.2  309.41  4548.6  302.99  4651.5  298.69    4757  295.56
  4780.8  295.13  4871.8  292.53  4883.1  290.83  4912.2  289.49  4944.5  287.04
  4965.2  286.93    4986  284.11  4991.2  286.22  4993.8  283.11  5004.8  283.74
  5017.3  286.29  5027.7  286.74  5037.4  286.74  5042.6  287.72  5107.8  286.29
  5145.6  286.56    5173  284.04  5221.7  284.93  5268.5  287.54  5341.2  289.89
  5373.2  289.91  5404.6  291.85  5561.7  297.82  5851.1  305.33  5893.1  305.66
#Mann= 8 ,-1 , 0
  4375.5     .17       0  4548.6     .11       0    4757     .15       0
  4780.8     .11       0  4912.2     .15       0  4965.2     .09       0
  5027.7     .15       0  5221.7     .17       0
Bank Sta=4965.2,5027.7
XS Rating Curve= 0 ,0
Exp/Cntr=0.3,0.1

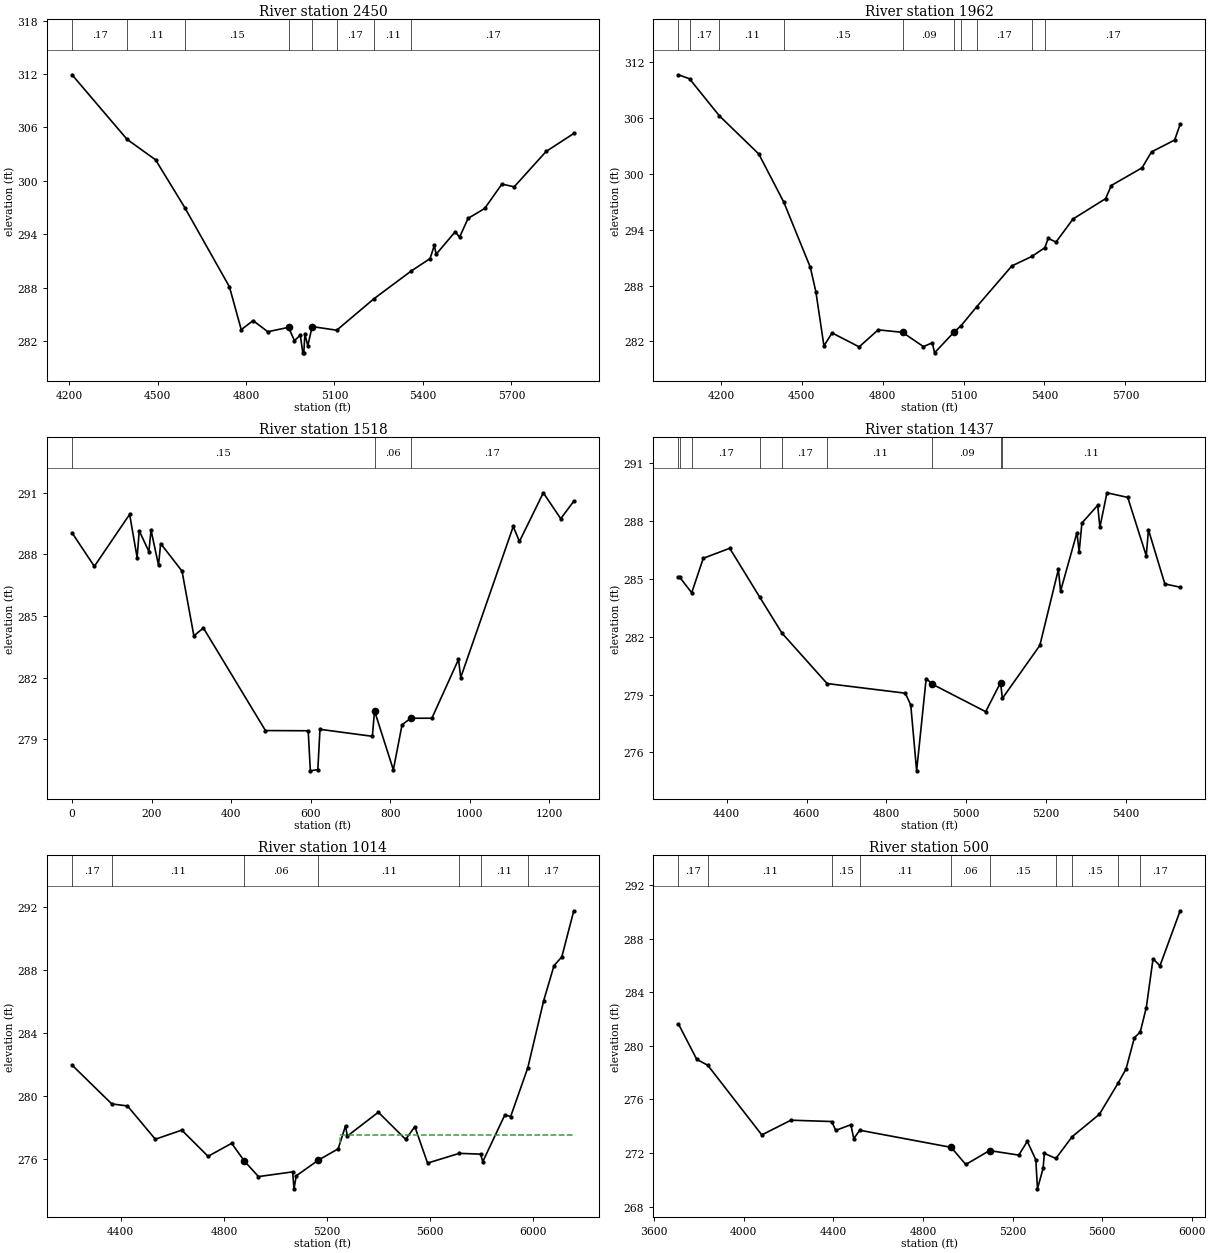
Type RM Length L Ch R = 1 ,2450    ,488,488,488
BEGIN DESCRIPTION:
Conroe Lake 046 4.0
END DESCRIPTION:
XS GIS Cut Line= 3
      3788016.51     10223678.42      3787968.23     10224466.84
      3788515.93     10225195.45
#Sta/Elev= 30
  4210.1  311.91  4396.6  304.66  4493.3  302.36  4592.4  296.99  4743.7  288.11
  4783.8  283.29  4823.9  284.31    4874  283.06  4944.1  283.55  4964.2  282.06
  4984.2  282.68  4992.5  280.69    4996  280.69  4999.6  282.77  5009.6  281.49
  5024.2  283.64  5107.6  283.23  5234.1  286.77  5360.7  289.89  5424.1  291.27
  5438.6  292.75  5444.9  291.76  5509.5  294.29    5524  293.67  5553.2  295.79
  5609.4   296.9  5667.7  299.64  5709.4  299.33  5817.7   303.3  5911.5  305.32
#Mann= 8 ,-1 , 0
  4210.1     .17       0  4396.6     .11       0  4592.4     .15       0
  4944.1     .09       0  5024.2     .15       0  5107.6     .17       0
  5234.1     .11       0  5360.7     .17       0
Bank Sta=4944.1,5024.2
XS Rating Curve= 0 ,0
Exp/Cntr=0.3,0.1

Type RM Length L Ch R = 1 ,1962    ,444,444,444
BEGIN DESCRIPTION:
Conroe Lake 046 3.0
END DESCRIPTION:
XS GIS Cut Line= 3
      3787852.72     10223664.22      3787758.23     10224616.84
       3788442.9     10225205.76
#Sta/Elev= 30
  4042.7  310.63  4083.7   310.2  4194.2  306.23  4340.7  302.12  4433.5  296.94
  4531.9  289.94  4552.5  287.29  4582.2  281.51  4612.3  282.91  4712.8  281.41
  4783.2  283.24  4873.6  282.97  4951.1  281.44  4984.1  281.85  4992.4  280.77
  5066.1  283.04  5090.6  283.68  5149.2  285.74    5279   290.1  5353.5  291.13
  5401.3  292.06  5413.9  293.07  5442.5  292.66  5506.1  295.15  5626.8  297.33
  5647.7  298.74  5761.8  300.64  5796.9  302.35  5882.5  303.62  5903.1  305.31
#Mann= 10 ,-1 , 0
  4042.7     .11       0  4083.7     .17       0  4194.2     .11       0
  4433.5     .15       0  4873.6     .09       0  5066.1     .17       0
  5090.6     .11       0  5149.2     .17       0  5353.5     .11       0
  5401.3     .17       0
Bank Sta=4873.6,5066.1
XS Rating Curve= 0 ,0
Exp/Cntr=0.3,0.1

Type RM Length L Ch R = 1 ,1518    ,81,81,81
XS GIS Cut Line= 3
      3787110.82     10223726.92      3787408.23     10224466.84
       3787628.4     10224875.02
#Sta/Elev= 30
       0  289.05      56  287.42   144.7  289.95   163.5  287.85   168.9  289.15
   193.1  288.14   198.5  289.18   217.3  287.48   222.7  288.53   276.4  287.19
   306.2  284.04   330.2  284.42   486.1  279.43   593.6  279.42     599  277.47
   617.8  277.53   623.2  279.49   754.9  279.15   760.3  280.39   807.6  277.52
   829.5  279.71   851.4  280.03   904.5  280.03   971.4  282.89     977  282.01
    1109  289.36  1124.6  288.63  1184.6     291  1228.4  289.74  1261.2  290.59
#Mann= 3 , 0 , 0
       0     .15       0   760.3     .06       0   851.4     .17       0
Bank Sta=760.3,851.4
XS Rating Curve= 0 ,0
Exp/Cntr=0.3,0.1

Type RM Length L Ch R = 1 ,1437    ,423,423,423
BEGIN DESCRIPTION:
Conroe Lake 046 1.0
END DESCRIPTION:
XS GIS Cut Line= 3
      3787016.25     10223797.15      3787348.44     10224436.84
      3787566.49     10224925.72
#Sta/Elev= 30
  4279.2  285.08  4282.7  285.08  4312.4  284.28  4341.3  286.07  4407.6  286.59
  4482.2  284.07  4538.3  282.19  4651.3  279.57    4847  279.07  4860.8  278.46
  4875.5  275.04  4899.4  279.83  4914.6  279.54  5048.4  278.11  5085.6  279.62
  5090.2   278.8    5184  281.55  5230.4  285.49  5235.9  284.37  5276.9   287.4
  5282.4   286.4  5289.3   287.9  5328.8  288.82  5334.3  287.68    5352  289.47
    5404  289.23  5450.4   286.2  5455.9  287.55  5496.9  284.74  5535.3  284.57
#Mann= 9 ,-1 , 0
  4279.2     .17       0  4282.7     .11       0  4312.4     .17       0
  4482.2     .11       0  4538.3     .17       0  4651.3     .11       0
  4914.6     .09       0  5085.6     .15       0  5090.2     .11       0
Bank Sta=4914.6,5085.6
XS Rating Curve= 0 ,0
Exp/Cntr=0.3,0.1

Type RM Length L Ch R = 1 ,1014    ,514,514,514
BEGIN DESCRIPTION:
Conroe Lake 046 2.5
END DESCRIPTION:
XS GIS Cut Line= 4
      3786915.55     10223856.17      3787089.53     10224625.54
      3787662.08     10225189.49      3788014.24     10225211.61
#Sta/Elev= 30
  4211.2  281.95  4365.1  279.48    4426  279.35  4534.1  277.23  4636.6  277.81
  4738.5  276.14    4830  276.97  4878.3  275.86  4933.9  274.85  5066.4  275.15
  5071.7  274.07  5080.5   274.9  5165.4  275.89  5243.1  276.62  5271.4  278.08
  5278.4  277.43  5398.7  278.95  5504.7  277.22  5540.2  278.03  5589.6  275.71
  5712.7  276.33    5795  276.28  5803.6   275.8  5889.6  278.79  5911.6  278.67
  5978.2  281.78  6039.9  286.06    6080  288.29    6110  288.84  6156.5  291.78
#Mann= 7 ,-1 , 0
  4211.2     .17       0  4365.1     .11       0  4878.3     .06       0
  5165.4     .11       0  5712.7     .15       0    5795     .11       0
  5978.2     .17       0
#XS Ineff= 2 , 0
       0    4830  276.97  5250.3       0  277.53
Permanent Ineff=
       F       F
Bank Sta=4878.3,5165.4
XS Rating Curve= 0 ,0
Exp/Cntr=0.3,0.1

Type RM Length L Ch R = 1 ,500     ,0,0,0
BEGIN DESCRIPTION:
Conroe Lake 046 1.5
END DESCRIPTION:
XS GIS Cut Line= 5
      3786814.85     10223859.62      3786877.35      10224863.1
      3787128.23      10225001.4      3787665.55     10225231.16
      3788028.41     10225264.79
#Sta/Elev= 30
  3708.1  281.64  3789.7     279  3839.3  278.55  4080.3  273.35  4210.5  274.45
  4392.1  274.35  4410.9  273.69  4478.1  274.11  4491.1  273.07  4517.8   273.7
  4926.1  272.42  4991.4  271.14  5097.5  272.18    5228  271.84  5266.1  272.87
  5304.1  271.49  5311.6  269.32  5336.7  270.86  5342.4  271.97  5393.7  271.59
  5466.5  273.22    5588  274.89  5671.7  277.22  5707.2  278.28  5744.2  280.61
  5770.5  281.04  5797.6  282.87  5827.7  286.51  5858.6  285.99  5948.8   290.1
#Mann= 10 ,-1 , 0
  3708.1     .17       0  3839.3     .11       0  4392.1     .15       0
  4517.8     .11       0  4926.1     .06       0  5097.5     .15       0
  5393.7     .11       0  5466.5     .15       0  5671.7     .11       0
  5770.5     .17       0
Bank Sta=4926.1,5097.5
XS Rating Curve= 0 ,0
Exp/Cntr=0.3,0.1

Chan Stop Cuts=-1
Use User Specified Reach Order=0
Composite Channel Slope=5