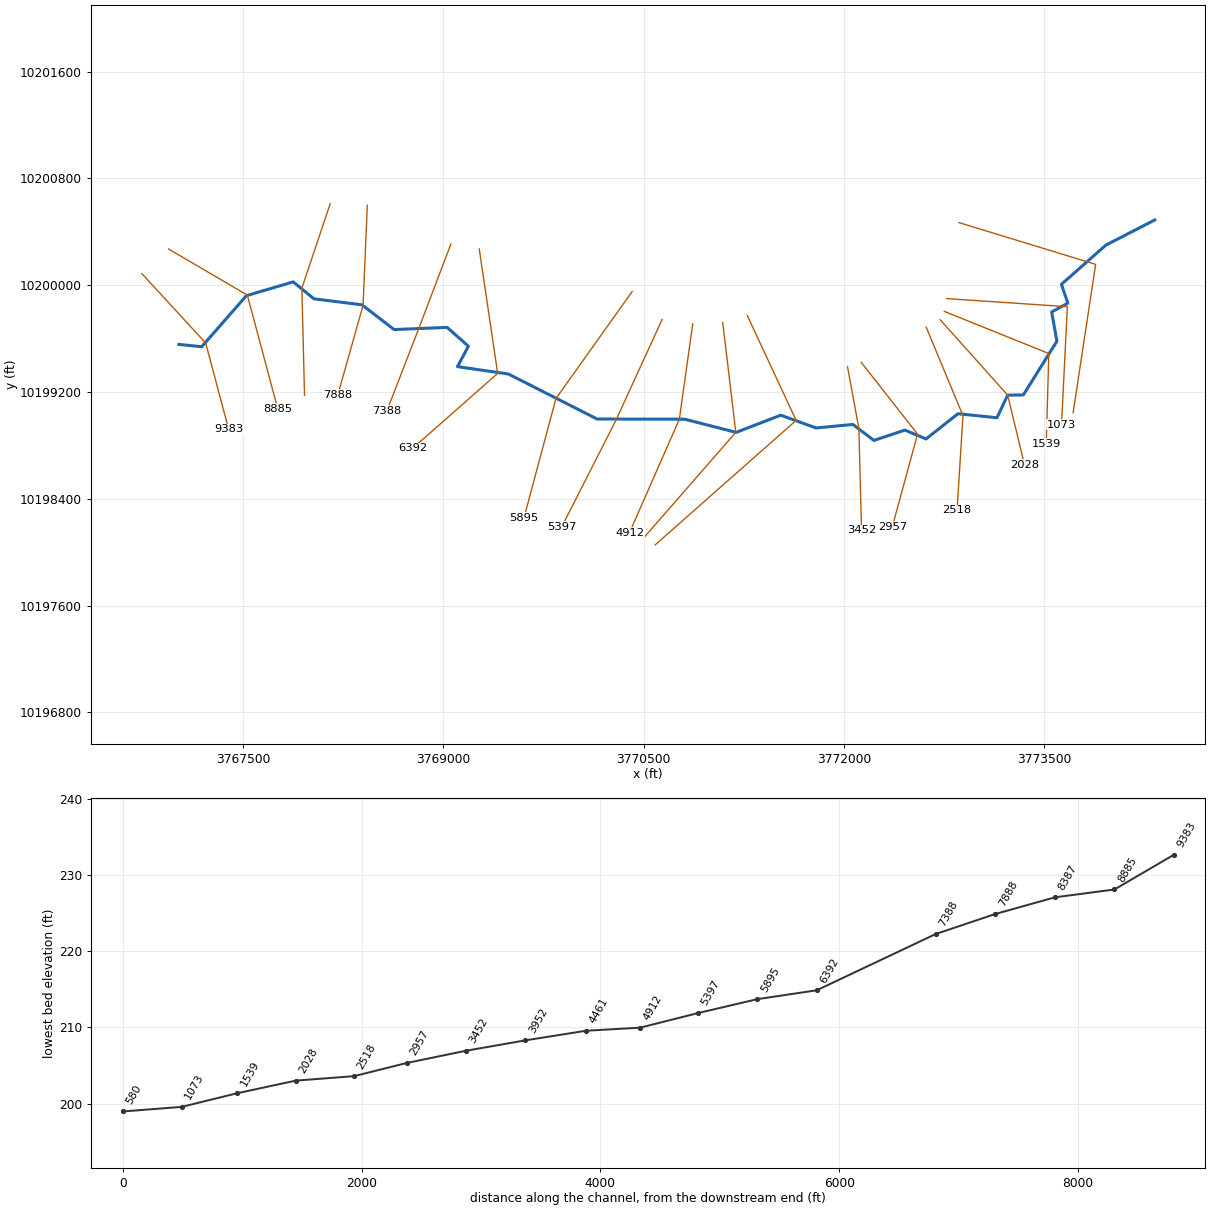
--- Conroe Lake 049.prj (project) ---

Proj Title=Conroe Lake 049 Base Level Engineering
Current Plan=p01
Default Exp/Contr=0.3,0.1
English Units
Geom File=g01
Flow File=f01
Flow File=f02
Plan File=p01
Y Axis Title=Elevation
X Axis Title(PF)=Main Channel Distance
X Axis Title(XS)=Station
BEGIN DESCRIPTION:
Conroe Lake 049
END DESCRIPTION:
DSS Export Rating Curves= 0
DSS Export Rating Curve Sorted= 0
DSS Export Volume Flow Curves= 0
DXF OffsetX= 0
DXF OffsetY= 0
DXF ScaleX= 1
DXF ScaleY= 10

--- Conroe Lake 049.p01 (plan) ---

Plan Title=Multiple Run
Short Identifier=Multiple
Geom File=g01
Flow File=f01
Subcritical Flow
K Sum by GR= 0
Std Step Tol= 0.01
Critical Tol= 0.01
Num of Std Step Trials= 20
Max Error Tol= 0.3
Flow Tol Ratio= 0.001
Split Flow NTrial= 30
Split Flow Tol= 0.02
Split Flow Ratio= 0.02
Log Output Level= 0
Friction Slope Method= 1
Unsteady Friction Slope Method= 2
Unsteady Bridges Friction Slope Method= 1
Parabolic Critical Depth
Global Vel Dist=  1 , 1 , 1
Global Log Level= 0
CheckData=True
Encroach Param= -1, 0, 0, 0
BEGIN DESCRIPTION:
Multiple Run
END DESCRIPTION:

--- Conroe Lake 049.f01 (steady flow) ---

Flow Title=Multiple
Program Version=4.10
Number of Profiles= 7
Profile Names=10-year,25-year,50-year,1pct_min,100-year,1pct_plu,500-year
River Rch & RM=Conroe Lake 049,Reach-1         ,9383
     994    1404    1952     894    2699    8151    5334
River Rch & RM=Conroe Lake 049,Reach-1         ,8387
    1177    1663    2313    1057    3192    9640    6290
River Rch & RM=Conroe Lake 049,Reach-1         ,3452
    1429    2020    2808    1282    3871   11690    7608
River Rch & RM=Conroe Lake 049,Reach-1         ,580
    1706    2436    3411    1567    4731   14287    9420
Boundary for River Rch & Prof#=Conroe Lake 049,Reach-1         , 1
Up Type= 0
Dn Type= 3
Dn Slope=0.005
Boundary for River Rch & Prof#=Conroe Lake 049,Reach-1         , 2
Up Type= 0
Dn Type= 3
Dn Slope=0.005
Boundary for River Rch & Prof#=Conroe Lake 049,Reach-1         , 3
Up Type= 0
Dn Type= 3
Dn Slope=0.005
Boundary for River Rch & Prof#=Conroe Lake 049,Reach-1         , 4
Up Type= 0
Dn Type= 3
Dn Slope=0.005
Boundary for River Rch & Prof#=Conroe Lake 049,Reach-1         , 5
Up Type= 0
Dn Type= 3
Dn Slope=0.005
Boundary for River Rch & Prof#=Conroe Lake 049,Reach-1         , 6
Up Type= 0
Dn Type= 3
Dn Slope=0.005
Boundary for River Rch & Prof#=Conroe Lake 049,Reach-1         , 7
Up Type= 0
Dn Type= 3
Dn Slope=0.005
DSS Import GetInterval= 0
DSS Import GetPeak= 0
DSS Import FillOption= 0

--- Conroe Lake 049.f02 (steady flow) ---

Flow Title=Orig_BLE_Flow
Program Version=4.10
Number of Profiles= 7
Profile Names=10-year,25-year,50-year,1pct_min,100-year,1pct_plu,500-year
River Rch & RM=Conroe Lake 049,Reach-1         ,9383
     994    1376    1697     687    2076    6269    3101
River Rch & RM=Conroe Lake 049,Reach-1         ,8387
    1177    1630    2011     813    2455    7414    3657
River Rch & RM=Conroe Lake 049,Reach-1         ,3452
    1429    1980    2442     986    2978    8992    4423
River Rch & RM=Conroe Lake 049,Reach-1         ,580
    1706    2388    2966    1205    3639   10990    5477
Boundary for River Rch & Prof#=Conroe Lake 049,Reach-1         , 1
Up Type= 0
Dn Type= 3
Dn Slope=0.005
Boundary for River Rch & Prof#=Conroe Lake 049,Reach-1         , 2
Up Type= 0
Dn Type= 3
Dn Slope=0.005
Boundary for River Rch & Prof#=Conroe Lake 049,Reach-1         , 3
Up Type= 0
Dn Type= 3
Dn Slope=0.005
Boundary for River Rch & Prof#=Conroe Lake 049,Reach-1         , 4
Up Type= 0
Dn Type= 3
Dn Slope=0.005
Boundary for River Rch & Prof#=Conroe Lake 049,Reach-1         , 5
Up Type= 0
Dn Type= 3
Dn Slope=0.005
Boundary for River Rch & Prof#=Conroe Lake 049,Reach-1         , 6
Up Type= 0
Dn Type= 3
Dn Slope=0.005
Boundary for River Rch & Prof#=Conroe Lake 049,Reach-1         , 7
Up Type= 0
Dn Type= 3
Dn Slope=0.005
DSS Import GetInterval= 0
DSS Import GetPeak= 0
DSS Import FillOption= 0

--- Conroe Lake 049.g01 (geometry) ---

Geom Title=Existing Conditions
Program Version=4.10

River Reach=Conroe Lake 049 ,Reach-1
Reach XY= 30
      3767018.23     10199556.84       3767189.8     10199539.92
      3767524.42     10199922.04      3767875.01     10200025.38
      3768030.67     10199898.16       3768389.8     10199853.96
      3768630.74     10199668.24      3769028.18     10199684.39
      3769187.18     10199543.49       3769105.8     10199390.54
      3769487.41      10199335.1       3770151.6     10198998.08
      3770807.77     10198996.64      3771193.59     10198898.19
       3771527.2     10199026.77      3771791.85     10198931.29
      3772067.65     10198957.37      3772225.36     10198837.98
      3772457.56     10198915.02      3772615.98     10198848.83
      3772855.03     10199037.92      3773147.15     10199007.64
       3773227.3     10199176.85      3773344.87     10199178.63
      3773596.02     10199581.19      3773556.83     10199800.28
      3773677.96     10199866.19      3773629.86     10200006.91
      3773962.95     10200300.81      3774329.24     10200489.23

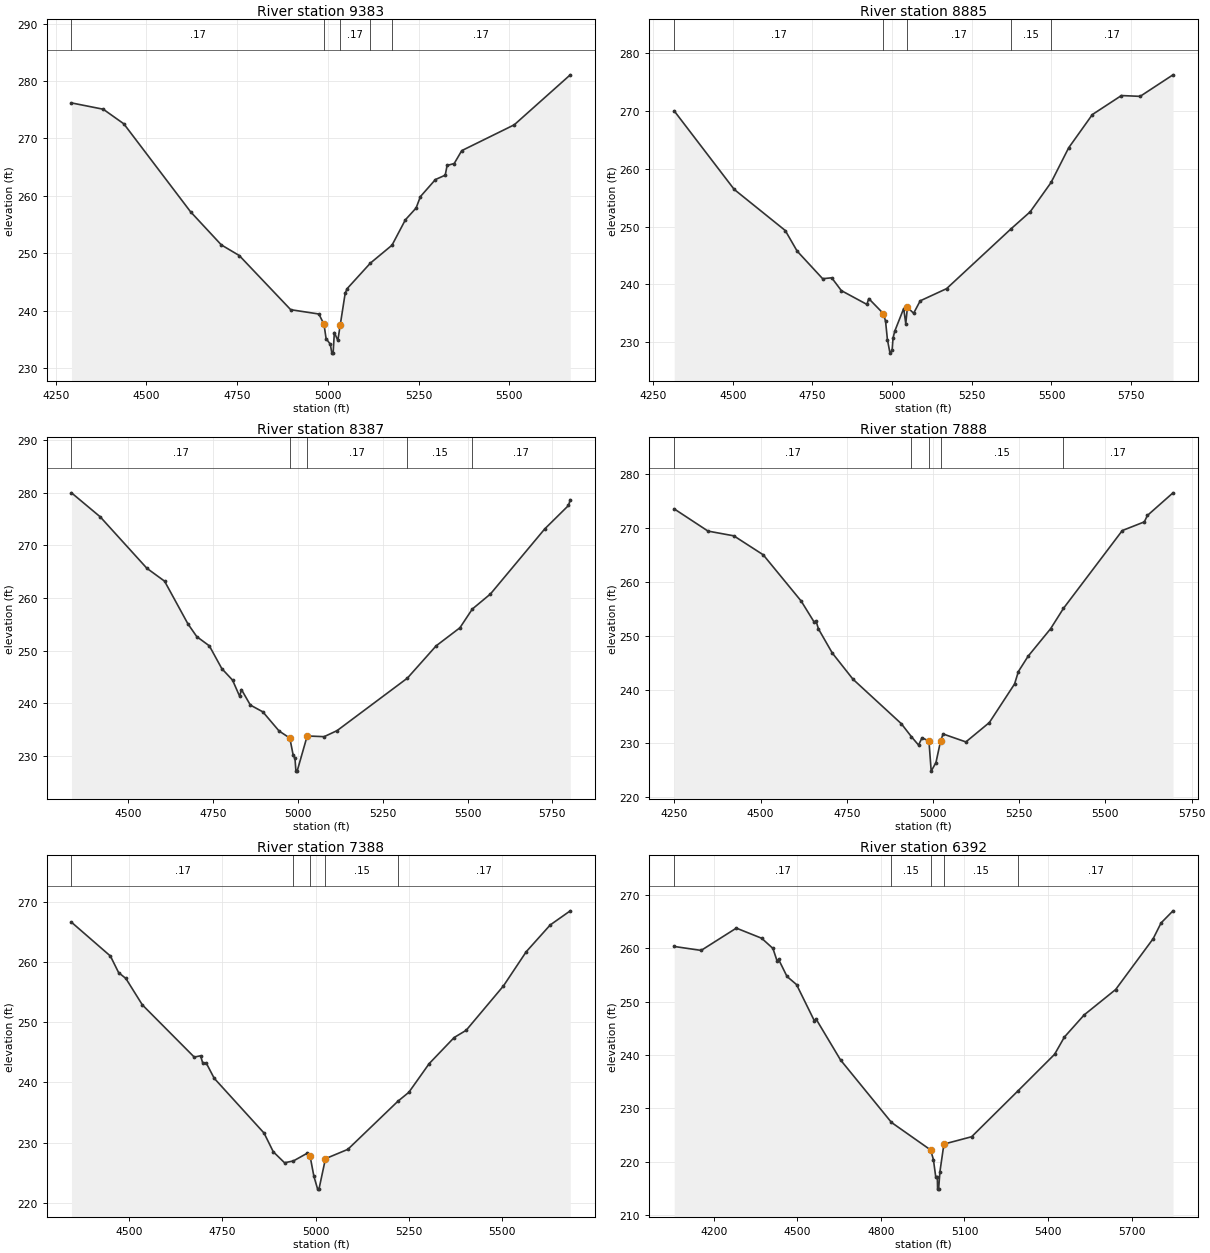
Type RM Length L Ch R = 1 ,9383    ,498,498,498
BEGIN DESCRIPTION:
Conroe Lake 049 18.0
END DESCRIPTION:
XS GIS Cut Line= 3
      3766740.85     10200087.65      3767219.35     10199567.72
      3767391.21     10198921.89
#Sta/Elev= 30
  4293.4  276.19    4381  275.09  4437.7  272.55  4621.5  257.25  4706.5  251.47
  4755.9  249.62  4897.7  240.19  4975.4  239.44  4989.5  237.63  4995.2  235.17
  5006.9  234.17  5011.1  232.63  5014.6  232.63    5018  236.22  5027.6  234.84
 5034.42  237.61  5047.8  243.03    5053  243.84  5117.3   248.3  5176.9  251.42
  5213.8  255.84  5243.3  257.89  5255.2  259.88  5296.6  262.85  5323.6  263.61
  5328.8   265.3  5348.4  265.64  5369.1  267.88  5513.9  272.38  5668.3  281.08
#Mann= 5 ,-1 , 0
  4293.4     .17       0  4989.5     .09       0 5034.42     .17       0
  5117.3     .15       0  5176.9     .17       0
Bank Sta=4989.5,5034.42
XS Rating Curve= 0 ,0
Exp/Cntr=0.3,0.1

Type RM Length L Ch R = 1 ,8885    ,498,498,498
BEGIN DESCRIPTION:
Conroe Lake 049 17.0
END DESCRIPTION:
XS GIS Cut Line= 3
       3766941.3     10200271.73      3767531.48     10199926.18
      3767758.97     10199074.64
#Sta/Elev= 30
  4316.1  270.04  4504.4  256.44  4664.6  249.32  4701.8  245.76    4782  240.97
  4810.4  241.13  4840.6  238.91  4920.8  236.52  4926.6  237.53  4972.6  234.92
  4979.4  233.59  4985.2  230.41  4993.3  228.08    5000  228.58  5002.7  230.64
  5007.9  231.84  5036.3  235.81  5042.8  233.18    5048  236.03  5067.4  234.98
  5088.1  237.14  5170.9  239.25  5372.3  249.57  5433.2  252.56  5498.9  257.65
  5553.9  263.64  5628.4  269.41  5719.5   272.7  5778.3  272.56  5881.4  276.29
#Mann= 5 ,-1 , 0
  4316.1     .17       0  4972.6     .09       0    5048     .17       0
  5372.3     .15       0  5498.9     .17       0
Bank Sta=4972.6,5048
XS Rating Curve= 0 ,0
Exp/Cntr=0.3,0.1

Type RM Length L Ch R = 1 ,8387    ,499,499,499
BEGIN DESCRIPTION:
Conroe Lake 049 16.0
END DESCRIPTION:
XS GIS Cut Line= 3
      3768152.02     10200611.27      3767939.92     10199978.48
      3767959.76     10199175.82
#Sta/Elev= 30
  4332.6  280.01  4417.2  275.45  4554.9  265.65    4607   263.2  4675.8  255.08
    4702  252.64    4739  250.89  4775.8  246.55  4807.4  244.37  4828.3  241.29
  4833.6  242.58  4859.9  239.62  4896.7  238.33  4944.5  234.69  4976.2  233.34
  4986.1  230.09  4991.4  229.46  4994.2  227.05  4997.8  227.05  5027.4  233.74
  5077.4  233.61  5115.6  234.76  5322.8  244.75  5407.5  250.89  5477.6  254.33
  5514.1  257.89  5567.6  260.76  5727.6  273.14  5797.6   277.6  5802.9   278.7
#Mann= 5 ,-1 , 0
  4332.6     .17       0  4976.2     .09       0  5027.4     .17       0
  5322.8     .15       0  5514.1     .17       0
Bank Sta=4976.2,5027.4
XS Rating Curve= 0 ,0
Exp/Cntr=0.3,0.1

Type RM Length L Ch R = 1 ,7888    ,500,500,500
BEGIN DESCRIPTION:
Conroe Lake 049 15.0
END DESCRIPTION:
XS GIS Cut Line= 3
      3768430.16     10200598.96      3768398.38     10199849.34
      3768209.29     10199179.62
#Sta/Elev= 30
  4249.7  273.53  4347.7  269.41  4422.5  268.53  4507.8  265.01  4617.9  256.42
  4655.7   252.5  4660.7  252.77    4668  251.25    4708  246.79  4768.1  241.92
  4908.2  233.67  4937.2  231.28  4958.2   229.7  4968.2  231.06  4988.3  230.46
  4994.8  224.87  5008.6  226.45  5022.3  230.54  5029.4  231.76  5095.4  230.29
  5163.4  233.88  5236.6  241.05  5247.6  243.35  5275.8  246.19  5341.1   251.3
  5378.3  255.07  5548.9  269.51  5612.8  271.12  5621.7  272.31  5695.9  276.51
#Mann= 5 ,-1 , 0
  4249.7     .17       0  4937.2     .15       0  4988.3     .09       0
  5022.3     .15       0  5378.3     .17       0
Bank Sta=4988.3,5022.3
XS Rating Curve= 0 ,0
Exp/Cntr=0.3,0.1

Type RM Length L Ch R = 1 ,7388    ,996,996,996
BEGIN DESCRIPTION:
Conroe Lake 049 14.0
END DESCRIPTION:
XS GIS Cut Line= 3
        3769056.     10200308.57      3768823.63     10199696.93
      3768577.43     10199061.02
#Sta/Elev= 30
  4345.7  266.67    4450  261.04    4472  258.28  4491.4  257.31  4535.6  252.91
  4674.6  244.22  4691.6  244.44  4696.9  243.31  4706.7  243.23  4728.1  240.69
  4861.6  231.57  4886.4  228.45  4916.5  226.63  4940.1  226.93  4976.8   228.2
  4984.9  227.72  4995.1  224.38  5005.1  222.24  5008.7  222.24  5026.1  227.31
    5086  228.86  5220.3  236.88  5249.5  238.36    5304  243.14  5370.9  247.48
    5403  248.68  5502.8  256.06  5563.9  261.76  5628.2  266.22  5681.9  268.57
#Mann= 5 ,-1 , 0
  4345.7     .17       0  4940.1     .15       0  4984.9     .09       0
  5026.1     .15       0  5220.3     .17       0
Bank Sta=4984.9,5026.1
XS Rating Curve= 0 ,0
Exp/Cntr=0.3,0.1

Type RM Length L Ch R = 1 ,6392    ,497,497,497
BEGIN DESCRIPTION:
Conroe Lake 049 13.0
END DESCRIPTION:
XS GIS Cut Line= 3
       3769268.7     10200271.75      3769406.72     10199339.71
      3768769.69     10198778.77
#Sta/Elev= 30
  4057.8  260.35  4154.5  259.61  4280.9  263.79  4371.9  261.89  4412.3  259.98
  4427.5  257.59  4432.5  257.94  4462.8  254.73    4497  253.21  4561.5  246.37
  4566.5  246.81  4654.9  239.09  4837.9  227.37  4978.5  222.21  4988.5  220.42
  4996.8  217.19  5002.6  217.19  5003.5  214.87  5007.2  214.87    5012  218.17
  5026.2  223.31  5125.8  224.69  5293.4  233.35  5423.7  240.14  5458.8  243.37
    5530  247.53  5642.9  252.28  5777.6  261.81    5806  264.76  5848.8  267.03
#Mann= 5 ,-1 , 0
  4057.8     .17       0  4837.9     .15       0  4978.5     .09       0
  5026.2     .15       0  5293.4     .17       0
Bank Sta=4978.5,5026.2
XS Rating Curve= 0 ,0
Exp/Cntr=0.3,0.1

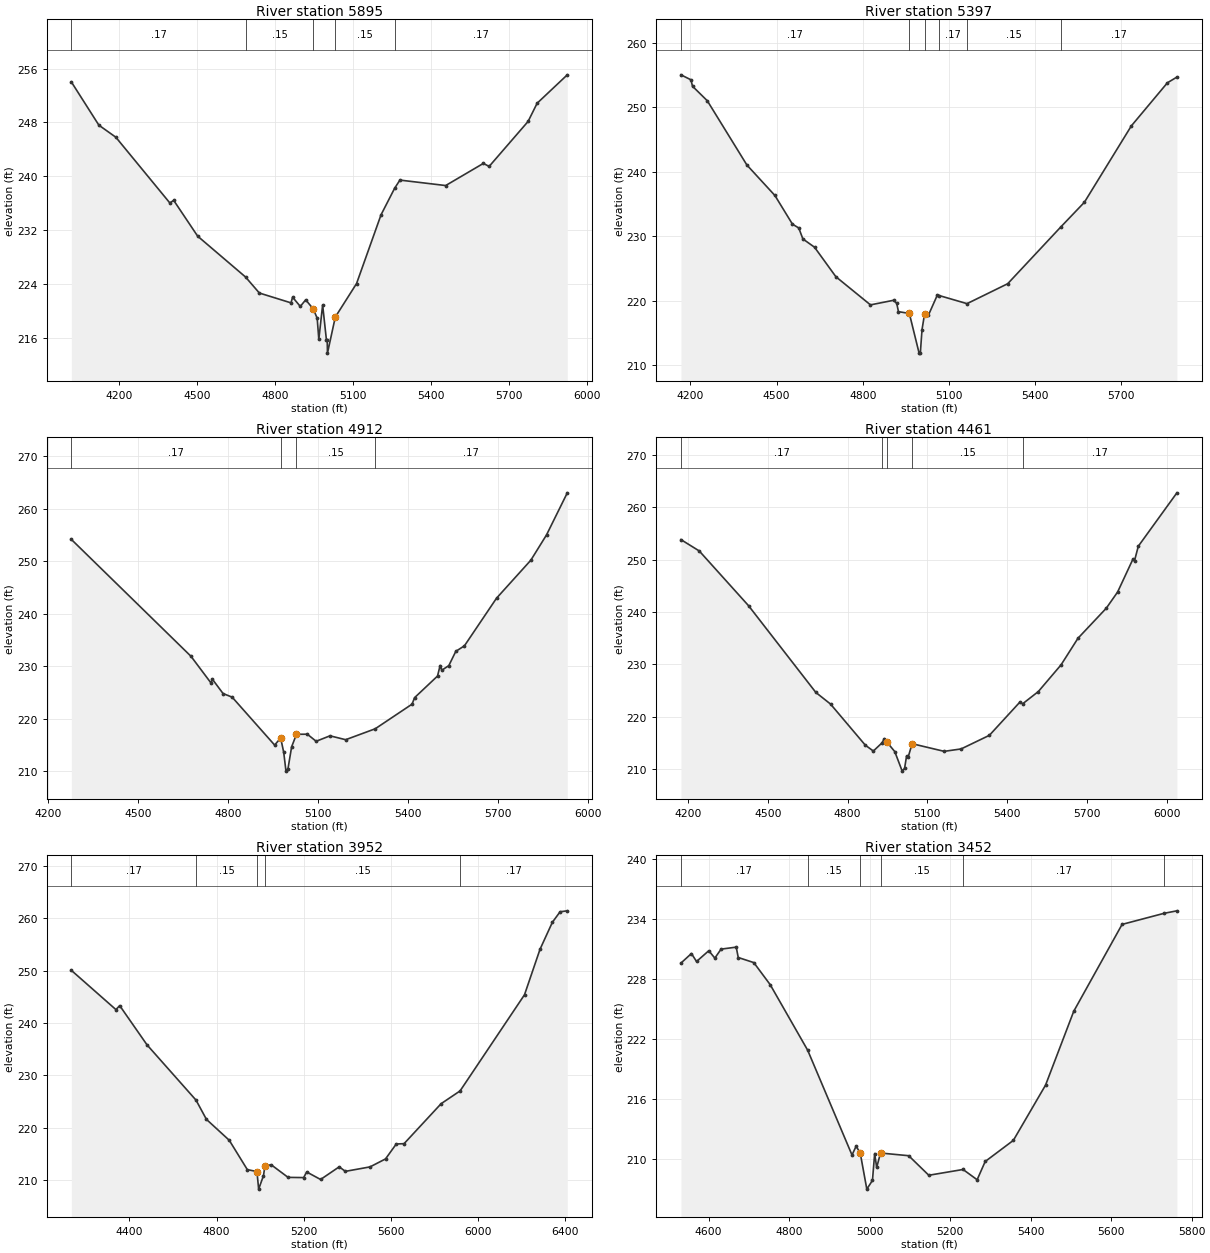
Type RM Length L Ch R = 1 ,5895    ,498,498,498
BEGIN DESCRIPTION:
Conroe Lake 049 12.0
END DESCRIPTION:
XS GIS Cut Line= 3
      3770414.03     10199952.72      3769843.15     10199151.25
       3769604.1     10198259.23
#Sta/Elev= 30
    4016  254.01  4121.9  247.58  4187.1  245.79  4394.9  236.02  4409.6  236.41
  4501.8  231.09    4686  225.02  4739.1  222.64  4860.8  221.18    4867  222.02
  4896.5  220.65  4917.4  221.63  4946.9  220.25  4961.6  218.88  4967.8  215.75
  4982.5  220.87    4997   215.7    5000   215.7  5001.1  213.71  5031.2  219.07
    5113  224.05  5207.2  234.27  5259.6  238.22  5279.7  239.42  5455.7  238.61
  5600.7   241.9  5622.9  241.45  5772.6  248.13  5807.5  250.84  5923.5  255.06
#Mann= 5 ,-1 , 0
    4016     .17       0    4686     .15       0  4946.9     .09       0
  5031.2     .15       0  5259.6     .17       0
Bank Sta=4946.9,5031.2
XS Rating Curve= 0 ,0
Exp/Cntr=0.3,0.1

Type RM Length L Ch R = 1 ,5397    ,485,485,485
BEGIN DESCRIPTION:
Conroe Lake 049 11.0
END DESCRIPTION:
XS GIS Cut Line= 3
        3770639.     10199744.11      3770291.58      10198986.8
      3769886.33      10198189.7
#Sta/Elev= 30
  4166.8  255.02  4201.6  254.25  4207.1  253.25  4258.6     251  4396.5  241.04
    4494  236.32  4555.2  231.87  4577.2  231.28  4591.5  229.58    4632   228.3
  4706.5  223.72  4826.9  219.36  4907.3  220.07  4918.3   219.6  4924.4  218.31
  4962.3  218.03  4996.3  211.88  5000.6  211.88  5006.4  215.51  5015.6  218.02
  5028.9  217.78  5060.1  220.91  5066.7   220.8  5163.2  219.55  5304.9  222.64
  5489.2  231.41  5571.9  235.26  5735.6  247.11  5861.2  253.79  5894.2  254.67
#Mann= 6 ,-1 , 0
  4166.8     .17       0  4962.3     .09       0  5015.6     .15       0
  5066.7     .17       0  5163.2     .15       0  5489.2     .17       0
Bank Sta=4962.3,5015.6
XS Rating Curve= 0 ,0
Exp/Cntr=0.3,0.1

Type RM Length L Ch R = 1 ,4912    ,451,451,451
BEGIN DESCRIPTION:
Conroe Lake 049 10.0
END DESCRIPTION:
XS GIS Cut Line= 3
      3770868.05     10199711.39      3770767.88     10198996.87
      3770393.85      10198145.4
#Sta/Elev= 30
  4278.5  254.14  4676.9  231.86  4743.2   226.8  4748.2  227.49  4783.7  224.76
    4814  224.07  4955.4  214.94  4975.6  216.28  4985.7  213.55  4993.2  209.97
    5000  210.47  5012.1  214.62  5028.2  216.99  5064.3  217.01  5093.7  215.66
  5139.8   216.7    5192  215.96  5290.3  218.04  5413.1  222.74  5421.4  223.97
  5497.8  228.09  5506.5   230.1    5512   229.2  5535.4  230.08  5558.7   232.8
  5587.5  233.86  5694.4  242.94  5808.6  250.18  5860.8     255    5930  263.02
#Mann= 4 ,-1 , 0
  4278.5     .17       0  4975.6     .09       0  5028.2     .15       0
  5290.3     .17       0
Bank Sta=4975.6,5028.2
XS Rating Curve= 0 ,0
Exp/Cntr=0.3,0.1

Type RM Length L Ch R = 1 ,4461    ,509,509,509
BEGIN DESCRIPTION:
Conroe Lake 049 9.0
END DESCRIPTION:
XS GIS Cut Line= 3
      3771093.02     10199719.52      3771190.51     10198898.49
      3770508.08     10198116.09
#Sta/Elev= 30
  4173.2  253.81  4242.1  251.64  4427.3  241.19  4680.4  224.61  4735.6  222.39
  4866.5  214.53  4896.7  213.41  4929.1  214.96  4938.5  215.79    4947  215.16
  4977.3   213.3  5005.2  209.57  5014.1  210.09  5021.7  212.46  5028.3  212.36
  5042.5  214.81  5163.1  213.35  5226.7  213.81    5333  216.41    5447  222.72
  5458.7  222.46  5517.2  224.78  5602.6  229.88  5666.2  234.96  5772.6   240.7
  5815.3   243.8  5872.3  250.02  5878.9   249.8  5893.1  252.55  6038.2  262.75
#Mann= 5 ,-1 , 0
  4173.2     .17       0  4929.1     .15       0    4947     .09       0
  5042.5     .15       0  5458.7     .17       0
Bank Sta=4947,5042.5
XS Rating Curve= 0 ,0
Exp/Cntr=0.3,0.1

Type RM Length L Ch R = 1 ,3952    ,500,500,500
BEGIN DESCRIPTION:
Conroe Lake 049 8.0
END DESCRIPTION:
XS GIS Cut Line= 3
      3771277.11     10199772.68      3771642.66     10198987.84
      3770586.57     10198055.42
#Sta/Elev= 30
  4134.2  250.04  4338.7  242.55    4356  243.31  4481.4  235.82  4706.1  225.28
  4753.7  221.62  4858.4  217.63  4941.3  212.03  4985.4  211.66  4993.3  208.31
  5015.4  210.88  5022.1  212.73  5050.6  212.96  5128.3  210.55  5199.5  210.51
  5213.7  211.58  5277.3  210.15  5362.6  212.56  5391.1   211.7    5504  212.55
  5575.1  214.07  5624.4  216.92  5660.1  216.98  5830.2  224.61    5917  227.04
  6212.5  245.38  6283.7  254.06  6340.4  259.21  6375.7  261.21  6408.8  261.39
#Mann= 5 ,-1 , 0
  4134.2     .17       0  4706.1     .15       0  4985.4     .09       0
  5022.1     .15       0    5917     .17       0
Bank Sta=4985.4,5022.1
XS Rating Curve= 0 ,0
Exp/Cntr=0.3,0.1

Type RM Length L Ch R = 1 ,3452    ,495,495,495
BEGIN DESCRIPTION:
Conroe Lake 049 7.0
END DESCRIPTION:
XS GIS Cut Line= 3
      3772027.63     10199389.09      3772112.51     10198928.04
      3772132.51      10198164.9
#Sta/Elev= 30
  4531.2   229.6  4557.3  230.56  4569.9  229.76  4600.4  230.84  4615.4   230.1
  4630.9     231  4668.5   231.2  4673.6  230.16  4712.2  229.65  4752.9  227.44
    4846  220.87  4956.2  210.36  4966.4  211.24  4976.6  210.57    4993  206.94
    5007  207.81  5012.5  210.51  5017.5  209.11    5027  210.56    5097  210.29
    5147  208.33  5232.1  208.91  5267.1  207.88  5287.1  209.71  5357.1  211.83
  5437.1  217.37  5507.1  224.77  5627.2  233.48  5731.5  234.59  5763.4  234.84
#Mann= 6 ,-1 , 0
  4531.2     .17       0    4846     .15       0  4976.6     .09       0
    5027     .15       0  5232.1     .17       0  5731.5     .11       0
Bank Sta=4976.6,5027
XS Rating Curve= 0 ,0
Exp/Cntr=0.3,0.1

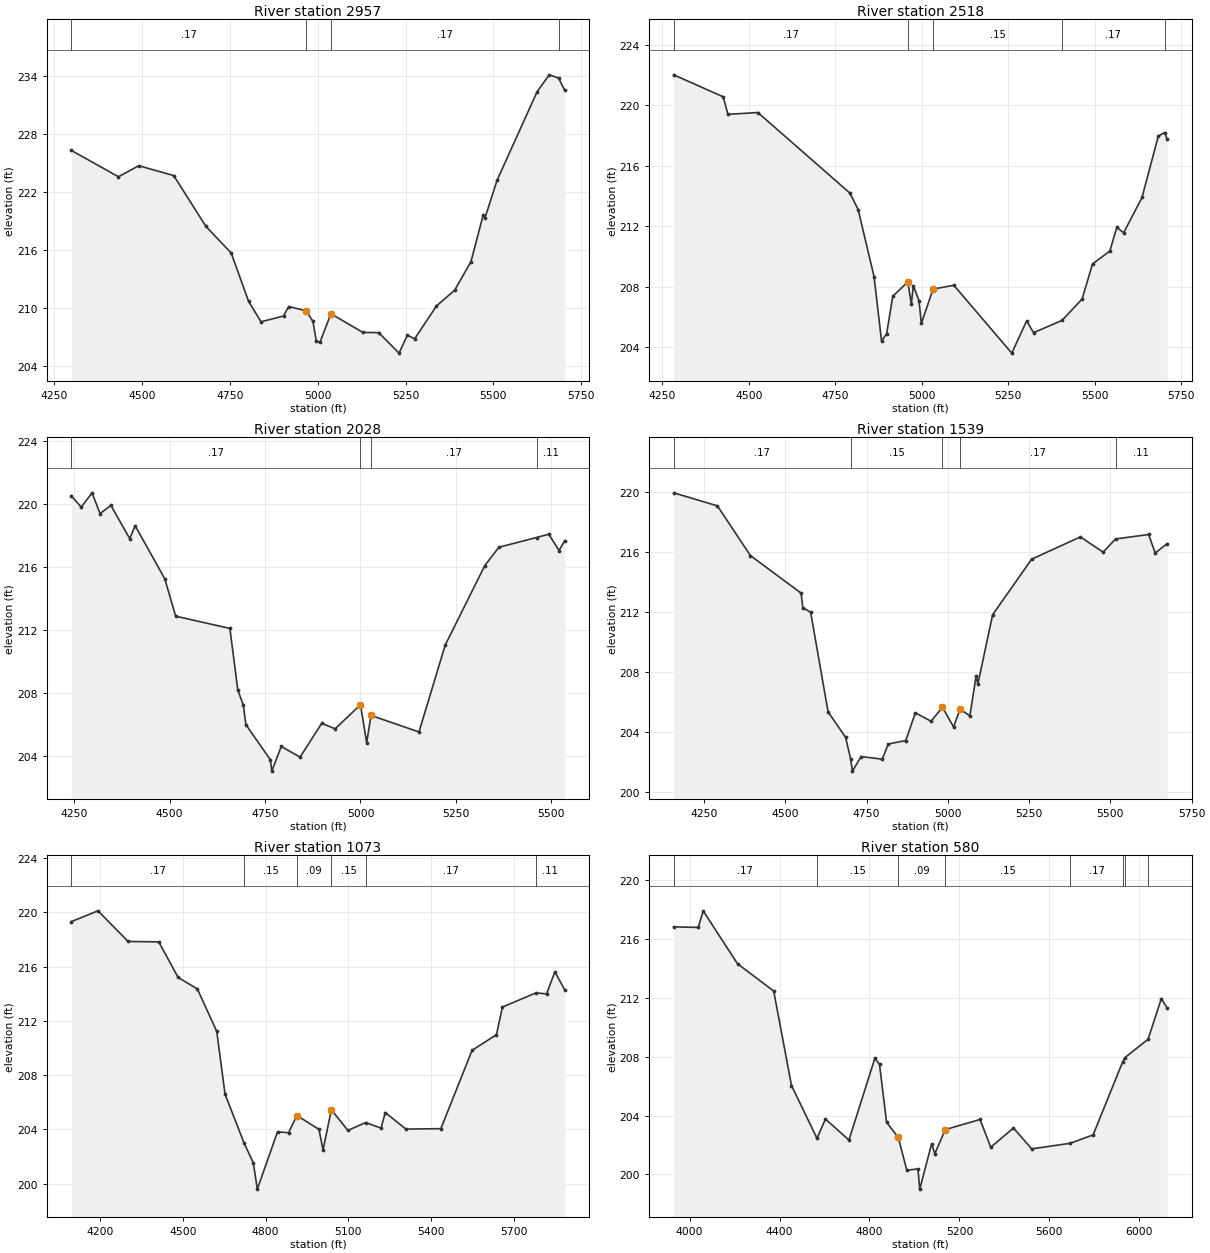
Type RM Length L Ch R = 1 ,2957    ,439,439,439
BEGIN DESCRIPTION:
Conroe Lake 049 6.0
END DESCRIPTION:
XS GIS Cut Line= 3
      3772130.32     10199422.54      3772552.25     10198884.94
      3772362.64     10198189.01
#Sta/Elev= 30
  4298.4  226.31  4432.9  223.58  4490.7  224.72  4590.2   223.7  4681.6  218.46
  4753.8  215.69  4803.5  210.68  4838.8  208.58  4902.9  209.18  4917.4  210.16
  4967.1  209.72  4986.4  208.63  4996.2  206.55  5006.5  206.46  5037.6  209.41
  5128.7  207.48  5173.6  207.46  5231.6  205.34  5255.3   207.2    5276  206.82
  5338.2  210.22    5390  211.85  5436.3   214.8  5470.9  219.59  5476.1  219.31
  5510.7  223.22  5624.7  232.38  5659.3  234.12  5685.6  233.79  5703.1  232.53
#Mann= 4 ,-1 , 0
  4298.4     .17       0  4967.1     .09       0  5037.6     .17       0
  5685.6     .11       0
Bank Sta=4967.1,5037.6
XS Rating Curve= 0 ,0
Exp/Cntr=0.3,0.1

Type RM Length L Ch R = 1 ,2518    ,490,490,490
BEGIN DESCRIPTION:
Conroe Lake 049 5.0
END DESCRIPTION:
XS GIS Cut Line= 3
      3772616.88     10199685.93      3772892.43     10199023.67
      3772848.19     10198315.75
#Sta/Elev= 30
  4282.7     222  4425.9  220.55  4439.6  219.39  4526.2  219.51  4792.2  214.19
  4816.1   213.1    4862  208.68  4883.7  204.42  4898.4   204.9  4916.2  207.38
  4959.5  208.32    4970  206.86  4975.4  208.08    4992  207.09  4998.7  205.58
  5032.7  207.85  5092.8   208.1  5260.2  203.62  5303.2  205.75  5323.2  204.97
  5405.3  205.78  5463.5  207.19  5493.6  209.51  5543.7  210.36  5563.7  211.92
  5583.7  211.57  5636.7   213.9  5683.9  217.96  5702.4  218.19  5709.3  217.74
#Mann= 5 ,-1 , 0
  4282.7     .17       0  4959.5     .09       0  5032.7     .15       0
  5405.3     .17       0  5702.4     .11       0
Bank Sta=4959.5,5032.7
XS Rating Curve= 0 ,0
Exp/Cntr=0.3,0.1

Type RM Length L Ch R = 1 ,2028    ,489,489,489
BEGIN DESCRIPTION:
Conroe Lake 049 4.0
END DESCRIPTION:
XS GIS Cut Line= 3
      3772721.82      10199741.7       3773227.3     10199176.85
      3773352.93     10198656.71
#Sta/Elev= 30
    4242  220.53  4268.3  219.81  4296.5  220.72  4317.6   219.4    4346  219.92
  4395.3  217.81  4409.5  218.63  4487.3  215.25  4515.7  212.88  4657.8   212.1
  4678.7  208.16  4692.9  207.25  4699.6  205.99  4763.9  203.75  4767.6  203.03
  4792.4   204.6  4841.7  203.92  4898.5  206.07  4933.6  205.72    5000  207.25
  5016.2  204.84  5027.6  206.57  5153.3  205.52    5222  211.04  5325.9   216.1
  5362.6  217.26  5461.3  217.88  5493.4  218.09  5520.3  217.05  5535.1  217.68
#Mann= 4 ,-1 , 0
    4242     .17       0    5000     .09       0  5027.6     .17       0
  5461.3     .11       0
Bank Sta=5000,5027.6
XS Rating Curve= 0 ,0
Exp/Cntr=0.3,0.1

Type RM Length L Ch R = 1 ,1539    ,466,466,466
BEGIN DESCRIPTION:
Conroe Lake 049 3.0
END DESCRIPTION:
XS GIS Cut Line= 3
      3772753.03     10199804.23      3773535.46     10199488.57
      3773516.28     10198814.34
#Sta/Elev= 30
  4156.3  219.95  4290.9  219.08  4392.6  215.76  4548.3  213.26  4553.7  212.29
  4577.8  211.98  4631.5  205.33  4685.2  203.64  4700.9  202.19  4706.3  201.38
    4733  202.35    4798  202.18  4816.7  203.19  4870.4  203.42    4900  205.27
  4948.2  204.71  4983.2  205.64  5017.5  204.33  5037.5  205.53  5067.5  205.06
  5087.1  207.76  5092.1  207.18  5137.6  211.81  5257.6  215.52  5407.7  217.01
  5477.7  215.99  5515.7  216.87  5617.7  217.17  5637.8  215.93  5674.5  216.56
#Mann= 5 ,-1 , 0
  4156.3     .17       0  4700.9     .15       0  4983.2     .09       0
  5037.5     .17       0  5515.7     .11       0
#XS Ineff= 2 , 0
       0                  5087.1       0  207.76
Permanent Ineff=
       F       F
Bank Sta=4983.2,5037.5
XS Rating Curve= 0 ,0
Exp/Cntr=0.3,0.1

Type RM Length L Ch R = 1 ,1073    ,493,493,493
BEGIN DESCRIPTION:
Conroe Lake 049 2.0
END DESCRIPTION:
XS GIS Cut Line= 3
      3772770.93      10199900.2      3773674.39     10199839.47
      3773630.84     10198955.44
#Sta/Elev= 30
  4094.5  219.32  4191.6  220.12    4301  217.86  4412.1  217.83  4482.3  215.21
  4552.5  214.35  4622.6  211.22  4652.7   206.6  4722.1  202.97  4755.2  201.53
  4769.9  199.59  4843.1  203.82  4883.2  203.75  4913.3  205.02  4993.4     204
  5008.4  202.48  5038.4  205.45  5098.5  203.92  5162.9   204.5  5218.7  204.09
  5234.1  205.24  5308.8  204.02  5435.8  204.05  5549.1  209.83  5637.5  210.98
  5659.2  213.02  5781.5  214.07  5819.4  213.99  5849.4  215.62  5885.1   214.3
#Mann= 6 ,-1 , 0
  4094.5     .17       0  4722.1     .15       0  4913.3     .09       0
  5038.4     .15       0  5162.9     .17       0  5781.5     .11       0
Bank Sta=4913.3,5038.4
XS Rating Curve= 0 ,0
Exp/Cntr=0.3,0.1

Type RM Length L Ch R = 1 ,580     ,0,0,0
BEGIN DESCRIPTION:
Conroe Lake 049 1.0
END DESCRIPTION:
XS GIS Cut Line= 3
      3772862.38     10200469.37      3773886.36     10200156.53
      3773717.69     10199045.66
#Sta/Elev= 30
  3929.3  216.84  4038.8   216.8  4060.5  217.93  4213.2  214.33  4374.2  212.47
  4453.3  206.04  4566.6  202.45  4604.2  203.76  4708.8  202.33  4823.8  207.89
  4844.7  207.48  4876.1  203.54  4928.1  202.51  4966.2  200.27  5015.6  200.37
  5023.6  198.99  5076.3  202.07  5090.7   201.4    5137  203.04  5291.8  203.73
  5339.3  201.84  5440.4  203.15  5521.4  201.73  5693.1  202.11  5794.5  202.68
  5925.4  207.63  5935.8  207.94  6038.9  209.19  6097.9  211.96  6123.6  211.31
#Mann= 8 ,-1 , 0
  3929.3     .17       0  4566.6     .15       0  4928.1     .09       0
    5137     .15       0  5693.1     .17       0  5925.4     .11       0
  5935.8     .17       0  6038.9     .11       0
#XS Ineff= 2 , 0
       0  4823.8  207.89               0
Permanent Ineff=
       F       F
Bank Sta=4928.1,5137
XS Rating Curve= 0 ,0
Exp/Cntr=0.3,0.1

Chan Stop Cuts=-1
Use User Specified Reach Order=0
Composite Channel Slope=5