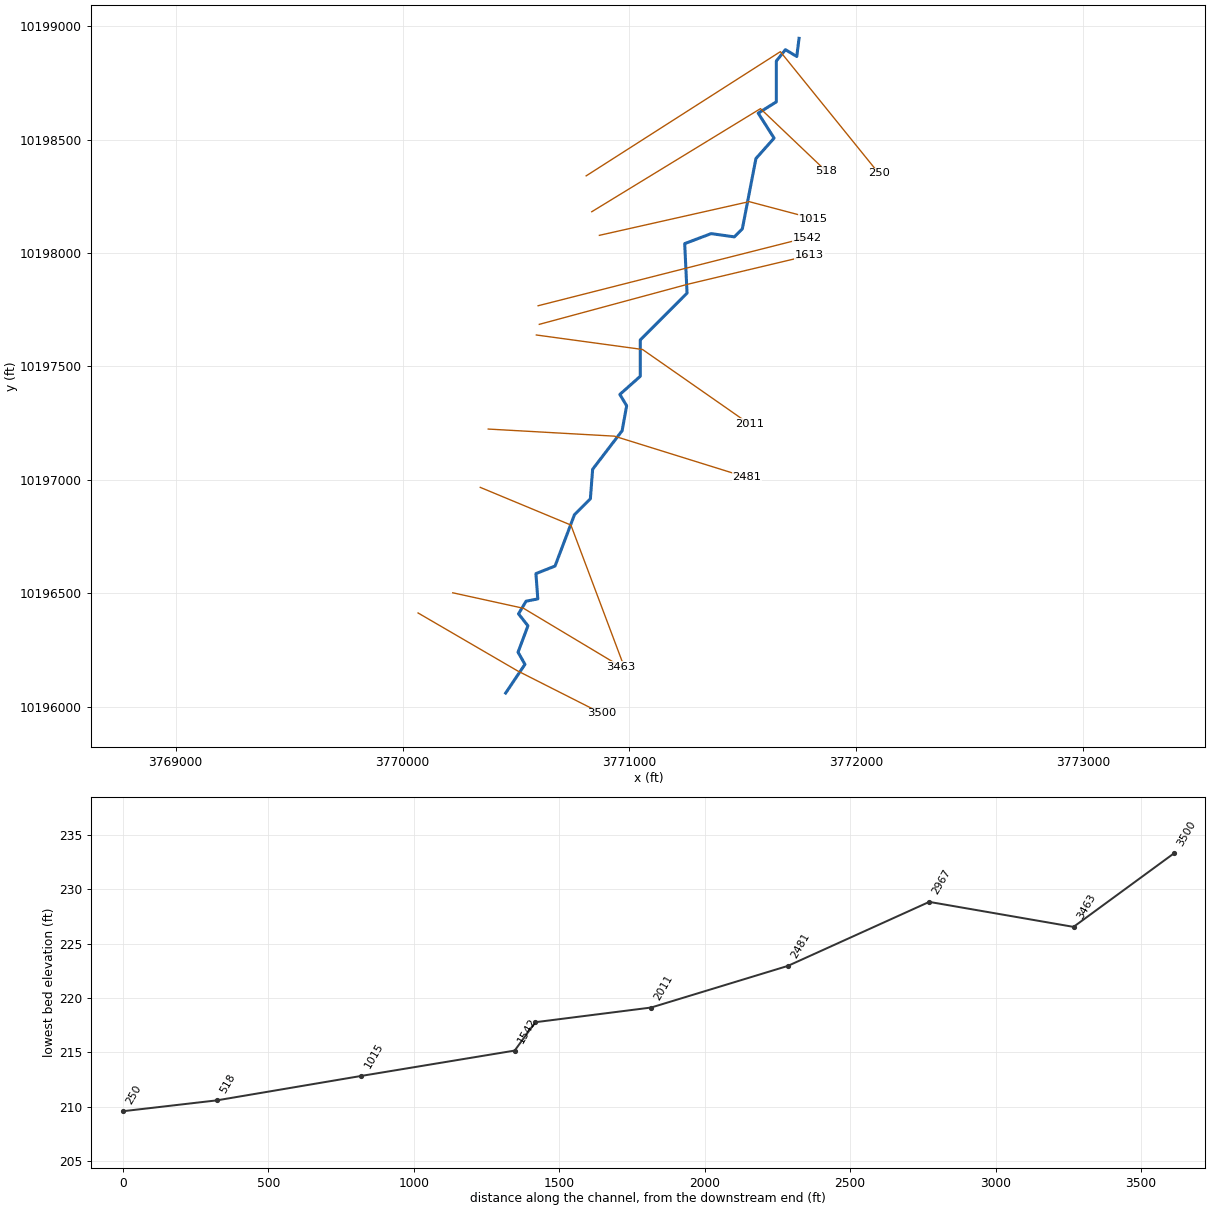
--- Conroe Lake 050.prj (project) ---

Proj Title=Conroe Lake 050 Base Level Engineering
Current Plan=p01
Default Exp/Contr=0.3,0.1
English Units
Geom File=g01
Flow File=f01
Flow File=f02
Plan File=p01
Y Axis Title=Elevation
X Axis Title(PF)=Main Channel Distance
X Axis Title(XS)=Station
BEGIN DESCRIPTION:
Conroe Lake 050
END DESCRIPTION:
DSS Export Rating Curves= 0
DSS Export Rating Curve Sorted= 0
DSS Export Volume Flow Curves= 0
DXF OffsetX= 0
DXF OffsetY= 0
DXF ScaleX= 1
DXF ScaleY= 10

--- Conroe Lake 050.p01 (plan) ---

Plan Title=Multiple Run
Short Identifier=Multiple
Geom File=g01
Flow File=f01
Subcritical Flow
K Sum by GR= 0
Std Step Tol= 0.01
Critical Tol= 0.01
Num of Std Step Trials= 20
Max Error Tol= 0.3
Flow Tol Ratio= 0.001
Split Flow NTrial= 30
Split Flow Tol= 0.02
Split Flow Ratio= 0.02
Log Output Level= 0
Friction Slope Method= 1
Unsteady Friction Slope Method= 2
Unsteady Bridges Friction Slope Method= 1
Parabolic Critical Depth
Global Vel Dist=  1 , 1 , 1
Global Log Level= 0
CheckData=True
Encroach Param= -1, 0, 0, 0
BEGIN DESCRIPTION:
Multiple Run
END DESCRIPTION:

--- Conroe Lake 050.f01 (steady flow) ---

Flow Title=Multiple
Program Version=4.10
Number of Profiles= 7
Profile Names=10-year,25-year,50-year,1pct_min,100-year,1pct_plu,500-year
River Rch & RM=Conroe Lake 050,Reach-1         ,3500
     507     681     917     406    1227    3705    2274
River Rch & RM=Conroe Lake 050,Reach-1         ,3463
     507     681     917     406    1227    3705    2274
River Rch & RM=Conroe Lake 050,Reach-1         ,2967
     580     785    1061     473    1427    4309    2668
Boundary for River Rch & Prof#=Conroe Lake 050,Reach-1         , 1
Up Type= 0
Dn Type= 3
Dn Slope=0.005
Boundary for River Rch & Prof#=Conroe Lake 050,Reach-1         , 2
Up Type= 0
Dn Type= 3
Dn Slope=0.005
Boundary for River Rch & Prof#=Conroe Lake 050,Reach-1         , 3
Up Type= 0
Dn Type= 3
Dn Slope=0.005
Boundary for River Rch & Prof#=Conroe Lake 050,Reach-1         , 4
Up Type= 0
Dn Type= 3
Dn Slope=0.005
Boundary for River Rch & Prof#=Conroe Lake 050,Reach-1         , 5
Up Type= 0
Dn Type= 3
Dn Slope=0.005
Boundary for River Rch & Prof#=Conroe Lake 050,Reach-1         , 6
Up Type= 0
Dn Type= 3
Dn Slope=0.005
Boundary for River Rch & Prof#=Conroe Lake 050,Reach-1         , 7
Up Type= 0
Dn Type= 3
Dn Slope=0.005
DSS Import GetInterval= 0
DSS Import GetPeak= 0
DSS Import FillOption= 0

--- Conroe Lake 050.f02 (steady flow) ---

Flow Title=Orig_BLE_Flow
Program Version=4.10
Number of Profiles= 7
Profile Names=10-year,25-year,50-year,1pct_min,100-year,1pct_plu,500-year
River Rch & RM=Conroe Lake 050,Reach-1         ,3500
     507     668     797     313     944    2852    1322
River Rch & RM=Conroe Lake 050,Reach-1         ,3463
     507     668     797     313     944    2852    1322
River Rch & RM=Conroe Lake 050,Reach-1         ,2967
     580     770     923     364    1098    3317    1551
Boundary for River Rch & Prof#=Conroe Lake 050,Reach-1         , 1
Up Type= 0
Dn Type= 3
Dn Slope=0.005
Boundary for River Rch & Prof#=Conroe Lake 050,Reach-1         , 2
Up Type= 0
Dn Type= 3
Dn Slope=0.005
Boundary for River Rch & Prof#=Conroe Lake 050,Reach-1         , 3
Up Type= 0
Dn Type= 3
Dn Slope=0.005
Boundary for River Rch & Prof#=Conroe Lake 050,Reach-1         , 4
Up Type= 0
Dn Type= 3
Dn Slope=0.005
Boundary for River Rch & Prof#=Conroe Lake 050,Reach-1         , 5
Up Type= 0
Dn Type= 3
Dn Slope=0.005
Boundary for River Rch & Prof#=Conroe Lake 050,Reach-1         , 6
Up Type= 0
Dn Type= 3
Dn Slope=0.005
Boundary for River Rch & Prof#=Conroe Lake 050,Reach-1         , 7
Up Type= 0
Dn Type= 3
Dn Slope=0.005
DSS Import GetInterval= 0
DSS Import GetPeak= 0
DSS Import FillOption= 0

--- Conroe Lake 050.g01 (geometry) ---

Geom Title=Existing Conditions
Program Version=4.10

River Reach=Conroe Lake 050 ,Reach-1
Reach XY= 30
      3770454.74     10196060.23      3770539.79     10196186.79
      3770509.42     10196240.45      3770552.95     10196356.89
      3770511.44     10196409.54      3770544.85     10196465.22
      3770596.49     10196475.35      3770588.23     10196586.84
      3770672.43     10196620.13      3770758.23     10196846.84
      3770828.23     10196916.84      3770838.23     10197046.84
      3770968.23     10197216.84      3770988.23     10197326.84
      3770958.23     10197376.84      3771048.23     10197456.84
      3771048.23     10197616.84      3771254.46     10197823.52
      3771244.12     10198041.67      3771360.71     10198085.86
      3771462.93     10198071.54      3771498.23     10198106.84
      3771558.23     10198416.84      3771638.23     10198506.84
      3771568.23     10198616.84      3771648.23     10198666.84
      3771648.23     10198846.84      3771688.23     10198896.84
      3771738.23     10198866.84      3771748.23     10198946.84

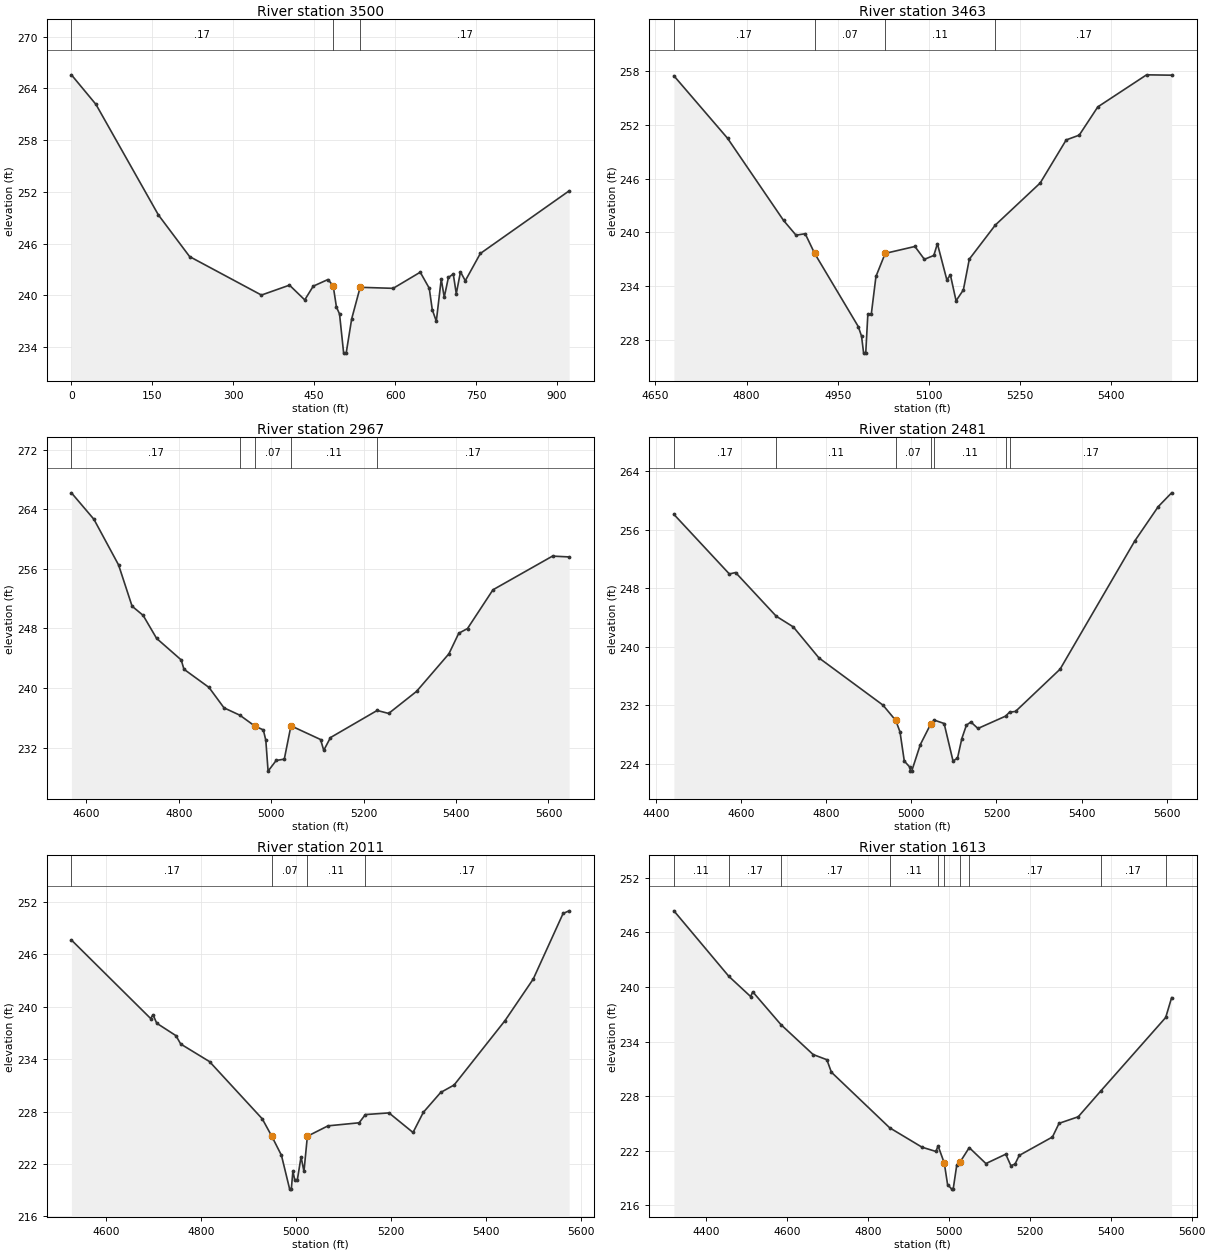
Type RM Length L Ch R = 1 ,3500    ,345,345,345
XS GIS Cut Line= 3
      3770068.55     10196413.35      3770506.38     10196158.44
      3770877.57     10195970.64
#Sta/Elev= 30
       0  265.57    45.5  262.14   161.2  249.33   219.1   244.5   352.2  240.04
   404.2  241.19   432.5  239.48   448.2  241.07   475.5  241.84   485.2  241.12
   491.2  238.67     497  237.84   504.6  233.31   509.3  233.31   519.5  237.28
   535.2  240.94   596.4  240.82   646.6  242.69   663.3  240.83   668.9  238.34
   676.4  237.01   685.5  241.89   691.1  239.79   698.8  242.08   707.8  242.48
   713.4   240.2   721.2  242.73   730.1   241.7     758  244.86   922.6  252.12
#Mann= 3 , 0 , 0
       0     .17       0   485.2     .07       0   535.2     .17       0
Bank Sta=485.2,535.2
XS Rating Curve= 0 ,0
Exp/Cntr=0.3,0.1

Type RM Length L Ch R = 1 ,3463    ,496,496,496
BEGIN DESCRIPTION:
Conroe Lake 050 7.0
END DESCRIPTION:
XS GIS Cut Line= 3
      3770221.64     10196502.29      3770533.72     10196433.84
      3770961.98     10196177.13
#Sta/Elev= 30
  4680.5  257.44  4768.8  250.48  4860.9  241.33  4881.4  239.69  4896.5  239.85
  4912.1  237.65  4983.8  229.51  4989.2  228.44  4992.6  226.55  4996.1  226.55
  4999.6  230.92  5005.3  230.92  5012.9  235.09  5028.1  237.66    5077  238.43
  5092.6     237  5108.1  237.43    5114  238.74  5129.5  234.72  5135.4  235.25
  5144.7  232.38  5156.7  233.59  5166.5  237.02  5209.2  240.81  5283.1   245.5
  5325.9   250.3  5347.3  250.83  5377.9  253.98  5458.1  257.55  5499.3  257.51
#Mann= 4 ,-1 , 0
  4680.5     .17       0  4912.1     .07       0  5028.1     .11       0
  5209.2     .17       0
Bank Sta=4912.1,5028.1
XS Rating Curve= 0 ,0
Exp/Cntr=0.3,0.1

Type RM Length L Ch R = 1 ,2967    ,486,486,486
BEGIN DESCRIPTION:
Conroe Lake 050 6.0
END DESCRIPTION:
XS GIS Cut Line= 3
      3770342.89     10196967.03      3770742.35     10196800.96
      3770969.27     10196197.41
#Sta/Elev= 30
  4567.4  266.19  4616.1  262.64  4669.5  256.51  4698.7  250.98  4722.6  249.75
  4751.8  246.66    4805  243.77    4811  242.52  4865.2  240.08  4897.7  237.34
  4932.1  236.35  4964.3   234.9  4982.8  234.38  4988.2  232.99  4993.1  228.85
  5010.6  230.28  5028.2  230.46  5042.6  234.93  5106.7  233.09  5113.6  231.64
  5128.1  233.35  5229.2  236.99  5254.1  236.59  5314.5  239.55  5384.5  244.59
  5405.9  247.35  5424.8  247.98  5479.9  253.18  5608.8   257.7  5644.8  257.59
#Mann= 5 ,-1 , 0
  4567.4     .17       0  4932.1     .15       0  4964.3     .07       0
  5042.6     .11       0  5229.2     .17       0
Bank Sta=4964.3,5042.6
XS Rating Curve= 0 ,0
Exp/Cntr=0.3,0.1

Type RM Length L Ch R = 1 ,2481    ,470,470,470
BEGIN DESCRIPTION:
Conroe Lake 050 5.0
END DESCRIPTION:
XS GIS Cut Line= 3
      3770377.85     10197224.18      3770934.27     10197192.89
      3771517.81     10197011.09
#Sta/Elev= 30
  4442.7  258.11  4572.9  249.95  4587.5  250.15  4683.1  244.16  4723.1   242.7
  4783.2  238.46  4933.5     232  4963.5   229.9  4973.5  228.34  4983.6  224.34
  4997.3  223.46  4997.5  222.96    5001  222.96  5021.2  226.59  5045.6   229.4
  5053.7  229.95  5077.1  229.48    5098  224.35  5108.5  224.73  5118.7  227.42
  5129.4  229.25  5139.9  229.69  5156.5   228.8  5221.5  230.49  5230.6  231.03
  5244.7  231.13  5349.4  236.92  5524.7  254.47  5579.8  259.17  5611.2  261.06
#Mann= 7 ,-1 , 0
  4442.7     .17       0  4683.1     .11       0  4963.5     .07       0
  5045.6     .11       0  5053.7     .11       0  5221.5     .15       0
  5230.6     .17       0
Bank Sta=4963.5,5045.6
XS Rating Curve= 0 ,0
Exp/Cntr=0.3,0.1

Type RM Length L Ch R = 1 ,2011    ,398,398,398
BEGIN DESCRIPTION:
Conroe Lake 050 4.0
END DESCRIPTION:
XS GIS Cut Line= 3
      3770589.97     10197638.91      3771058.23     10197575.03
      3771529.56     10197246.21
#Sta/Elev= 30
  4527.4  247.63  4694.1  238.65  4699.1  239.08  4706.9  238.11  4747.3  236.69
  4757.4  235.73    4818  233.72    4929  227.17  4949.2  225.16  4969.3     223
  4986.6  219.13  4990.1  219.13  4993.4  221.18  4997.3   220.2  5002.8   220.2
  5010.6  222.83  5016.7  221.15  5023.9  225.18  5067.3  226.37  5132.8  226.72
  5145.9  227.66  5195.6  227.85  5246.2  225.61  5267.8  227.91  5304.4  230.19
  5332.6  231.04  5439.9  238.42  5499.2  243.17    5562  250.67  5574.7  250.97
#Mann= 4 ,-1 , 0
  4527.4     .17       0  4949.2     .07       0  5023.9     .11       0
  5145.9     .17       0
Bank Sta=4949.2,5023.9
XS Rating Curve= 0 ,0
Exp/Cntr=0.3,0.1

Type RM Length L Ch R = 1 ,1613    ,71,71,71
BEGIN DESCRIPTION:
Conroe Lake 050 3.0
END DESCRIPTION:
XS GIS Cut Line= 3
      3770602.98     10197685.77      3771258.68     10197862.89
      3771794.27     10197990.13
#Sta/Elev= 30
  4320.8  248.36  4456.6  241.16  4510.4  238.94  4515.6  239.46  4585.4  235.85
  4664.8  232.57  4698.7     232  4709.9  230.63  4853.9  224.52  4933.7  222.39
  4968.1  221.92  4973.5  222.53  4988.8  220.65    4997  218.28  5007.3  217.78
  5010.8  217.78  5019.7  220.44  5028.6  220.81  5050.5  222.34  5091.7  220.59
  5140.7  221.62  5153.3  220.36  5163.6  220.53  5173.9  221.48  5256.1  223.51
  5272.4  225.01  5319.8  225.73    5375  228.54  5535.9  236.64  5550.5  238.82
#Mann= 10 ,-1 , 0
  4320.8     .11       0  4456.6     .17       0  4585.4     .17       0
  4853.9     .11       0  4973.5     .11       0  4988.8     .07       0
  5028.6     .11       0  5050.5     .17       0    5375     .17       0
  5535.9     .11       0
Bank Sta=4988.8,5028.6
XS Rating Curve= 0 ,0
Exp/Cntr=0.3,0.1

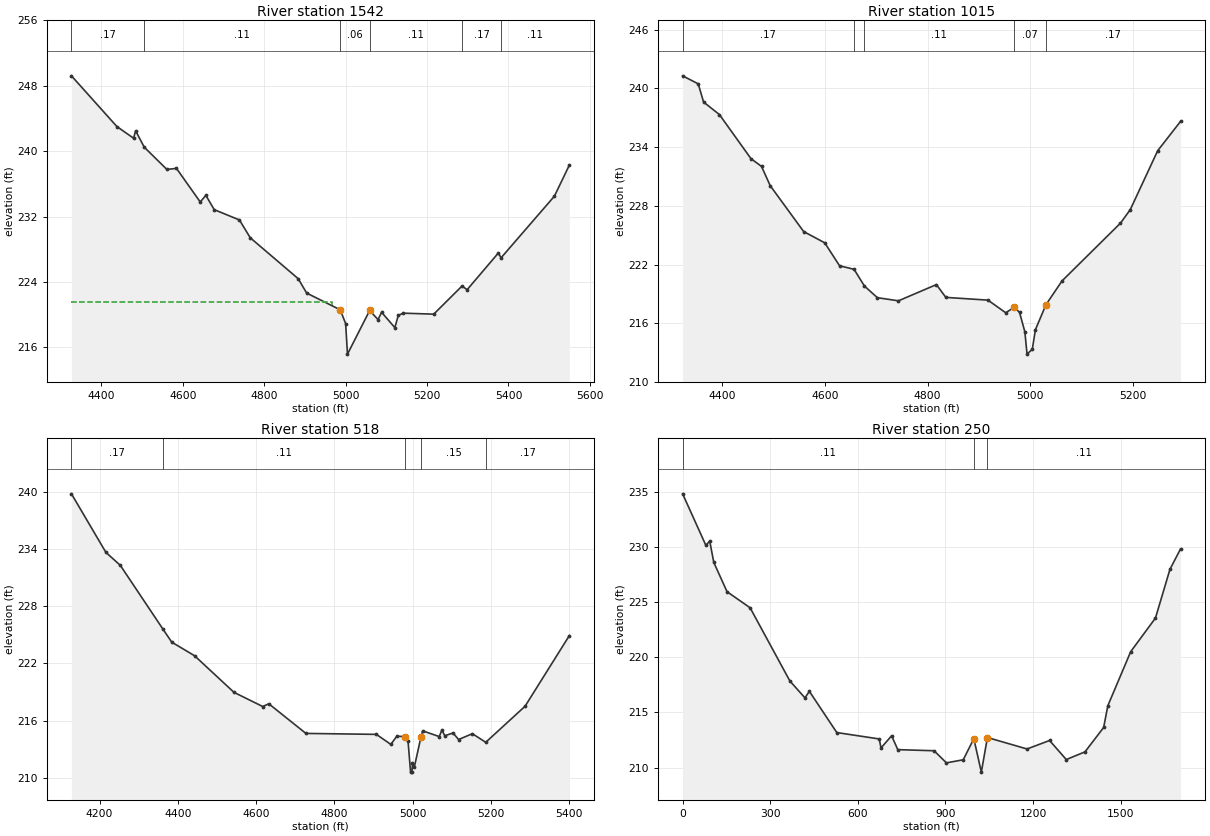
Type RM Length L Ch R = 1 ,1542    ,527,527,527
BEGIN DESCRIPTION:
Mapping XS 9c897df0
END DESCRIPTION:
XS GIS Cut Line= 3
       3770597.8     10197767.81       3771250.7     10197933.53
      3771783.38     10198068.44
#Sta/Elev= 30
  4326.4  249.21    4438  243.01    4479  241.58  4484.1  242.48  4505.3  240.48
  4560.9  237.76  4584.4  237.89  4642.8  233.78  4656.6  234.59  4677.2  232.84
  4739.1  231.58  4765.7   229.4  4883.4   224.4  4904.2  222.64  4986.7  220.59
    5000   218.9  5004.5  215.17    5059  220.51  5079.6  219.39  5088.3  220.29
  5120.9  218.41  5129.3  219.91  5141.5  220.18  5216.4  220.06  5285.9   223.5
  5298.4  223.05  5375.3  227.55  5381.6  226.94  5512.8  234.49  5549.5  238.29
#Mann= 6 ,-1 , 0
  4326.4     .17       0  4505.3     .11       0  4986.7     .06       0
    5059     .11       0  5285.9     .17       0  5381.6     .11       0
#XS Ineff= 2 , 0
       0  4965.3   221.6               0
Permanent Ineff=
       F       F
Bank Sta=4986.7,5059
XS Rating Curve= 0 ,0
Exp/Cntr=0.3,0.1

Type RM Length L Ch R = 1 ,1015    ,497,497,497
BEGIN DESCRIPTION:
Conroe Lake 050 2.0
END DESCRIPTION:
XS GIS Cut Line= 3
      3770868.04     10198078.29      3771528.23     10198226.84
      3771810.87     10198151.94
#Sta/Elev= 30
  4323.3  241.29  4353.7  240.47  4364.1  238.61  4394.9  237.33  4456.4  232.82
  4476.9  232.03  4493.8  230.06  4558.9  225.37  4599.9  224.22  4628.8  221.87
    4657  221.51  4677.2   219.8  4702.4  218.61  4743.4  218.29  4817.3  219.95
  4835.6  218.64  4917.6  218.36  4952.2  217.07  4968.9  217.63  4979.1   217.1
  4989.4  215.13  4993.7  212.84  5003.9  213.34    5010  215.34  5030.6   217.9
  5061.7  220.32  5175.5  226.23  5194.6  227.61  5247.9  233.63  5292.4  236.63
#Mann= 5 ,-1 , 0
  4323.3     .17       0    4657     .15       0  4677.2     .11       0
  4968.9     .07       0  5030.6     .17       0
Bank Sta=4968.9,5030.6
XS Rating Curve= 0 ,0
Exp/Cntr=0.3,0.1

Type RM Length L Ch R = 1 ,518     ,323,323,323
BEGIN DESCRIPTION:
Conroe Lake 050 1.0
END DESCRIPTION:
XS GIS Cut Line= 3
      3770834.31     10198182.29      3771578.23     10198636.84
      3771867.84     10198361.08
#Sta/Elev= 30
  4128.2  239.78  4216.2  233.64    4253  232.28  4361.4  225.62  4384.5  224.22
  4442.6   222.8  4543.3  218.96  4616.8  217.47  4632.3  217.76  4727.1  214.65
  4907.1  214.55  4943.9   213.5  4959.3  214.36  4980.7  214.31  4987.8   213.9
  4994.4  210.59  4997.9  210.59  4999.3  211.53  5003.8  211.09 5021.14  214.31
  5025.2  214.92  5067.6  214.32  5074.5  215.01  5081.8   214.4  5102.8   214.7
    5117  214.01  5152.2  214.62  5186.4  213.72  5286.8   217.5  5399.9  224.91
#Mann= 5 ,-1 , 0
  4128.2     .17       0  4361.4     .11       0  4980.7     .07       0
 5021.14     .15       0  5186.4     .17       0
Bank Sta=4980.7,5021.14
XS Rating Curve= 0 ,0
Exp/Cntr=0.3,0.1

Type RM Length L Ch R = 1 ,250     ,0,0,0
XS GIS Cut Line= 3
      3770809.67     10198340.46       3771665.9     10198888.08
      3772099.23     10198352.43
#Sta/Elev= 30
       0  234.84    79.8  230.16    92.8  230.56   106.9  228.61   152.2  225.96
   231.2   224.5   367.4  217.86     419  216.33   434.2  216.92   528.1  213.18
   673.5   212.6   679.5  211.78   715.8  212.89     737  211.63   861.3  211.53
   903.6  210.43   961.1  210.71   997.5  212.62  1023.2  209.59    1044  212.73
  1179.7  211.69  1256.9  212.46  1314.2  210.73  1378.2  211.43  1442.1  213.64
  1456.5  215.62  1534.8  220.52  1619.6  223.57  1669.2  227.99  1705.4  229.84
#Mann= 3 , 0 , 0
       0     .11       0   997.5     .07       0    1044     .11       0
Bank Sta=997.5,1044
XS Rating Curve= 0 ,0
Exp/Cntr=0.3,0.1

Chan Stop Cuts=-1
Use User Specified Reach Order=0
Composite Channel Slope=5