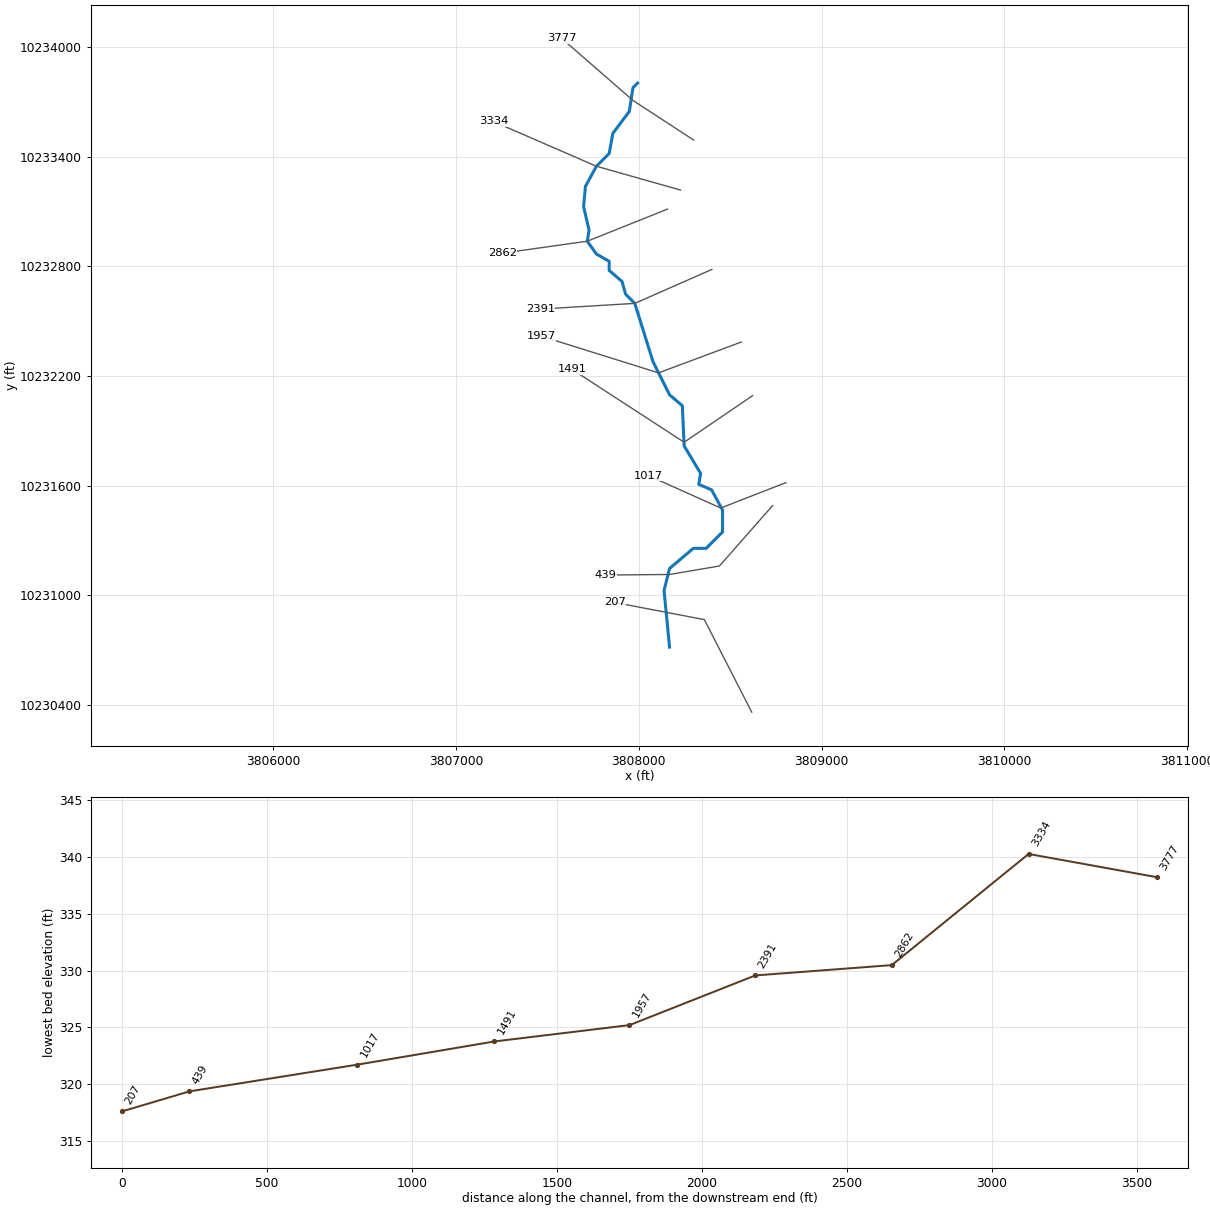
--- Conroe Lake 053.prj (project) ---

Proj Title=Conroe Lake 053 Base Level Engineering
Current Plan=p01
Default Exp/Contr=0.3,0.1
English Units
Geom File=g01
Flow File=f01
Flow File=f02
Plan File=p01
Y Axis Title=Elevation
X Axis Title(PF)=Main Channel Distance
X Axis Title(XS)=Station
BEGIN DESCRIPTION:
Conroe Lake 053
END DESCRIPTION:
DSS File=dss
DSS Export Rating Curves= 0
DSS Export Rating Curve Sorted= 0
DSS Export Volume Flow Curves= 0
DXF OffsetX= 0
DXF OffsetY= 0
DXF ScaleX= 1
DXF ScaleY= 10

--- Conroe Lake 053.p01 (plan) ---

Plan Title=Multiple Run
Program Version=4.10
Short Identifier=Multiple Run
Geom File=g01
Flow File=f01
Subcritical Flow
K Sum by GR= 0
Std Step Tol= 0.01
Critical Tol= 0.01
Num of Std Step Trials= 20
Max Error Tol= 0.3
Flow Tol Ratio= 0.001
Split Flow NTrial= 30
Split Flow Tol= 0.02
Split Flow Ratio= 0.02
Log Output Level= 0
Friction Slope Method= 1
Unsteady Friction Slope Method= 2
Unsteady Bridges Friction Slope Method= 1
Parabolic Critical Depth
Global Vel Dist= 1 , 1 , 1
Global Log Level= 0
CheckData=True
Encroach Param=-1 ,0,0, 0
BEGIN DESCRIPTION:
Multiple Run
END DESCRIPTION:
Computation Interval=1HOUR
Output Interval=1HOUR
Run HTab= 0
Run UNet= 0
Run PostProcess= 0
Run WQNet= 0
UNET Theta= 1
UNET Theta Warmup= 1
UNET ZTol= 0.02
UNET ZSATol= 0.05
UNET MxIter= 20
UNET MaxInSteps= 0
UNET DtIC= 0
UNET DtMin= 0
UNET MaxCRTS= 20
UNET WFStab= 2
UNET SFStab= 1
UNET WFX= 1
UNET SFX= 1
UNET DSS MLevel= 4
UNET DZMax Abort= 100
UNET Convert EG Bridges= 0
UNET Use Existing IB Tables=-1
UNET Froude Reduction=False
UNET Froude Limit= 1
UNET Froude Power= 10
UNET Time Slicing=0,0, 5
UNET Junction Losses=0
Instantaneous Interval=1HOUR
DSS File=dss
Write IC File= 0
Write IC File at Sim End=0
Echo Input=False
Echo Parameters=False
Echo Output=False
Write Detailed= 0
WQ AD Non Conservative
WQ ULTIMATE=-1
WQ Max Comp Step=1HOUR
WQ Output Interval=15MIN
WQ Output Selected Increments= 0
WQ Output face flow=0
WQ Output face velocity=0
WQ Output face area=0
WQ Output face dispersion=0
WQ Output cell volume=0
WQ Output cell surface area=0
WQ Output cell continuity=0
WQ Output cumulative cell continuity=0
WQ Output face conc=0
WQ Output face dconc_dx=0
WQ Output face courant=0
WQ Output face peclet=0
WQ Output face adv mass=0
WQ Output face disp mass=0
WQ Output cell mass=0
WQ Output cell source sink temp=0
WQ Output cell source sink nsm=0
WQ Output MaxMinRange=-1
WQ Daily Max Min Mean=-1
WQ Daily Range=0
WQ Daily Time=0
WQ Create Restart=0
WQ Fixed Restart=0
WQ System Summary=0
WQ Use Fixed Temperature=0
Sorting and Armoring Iterations= 10
XS Update Threshold= 0.02
Hydraulics Update Threshold= 0.02
Energy Slope Method= 1
Volume Change Method= 0
XS Weighting Method= 0
Number of US Weighted Cross Sections= 1
Number of DS Weighted Cross Sections= 1
Upstream XS Weight=0.25
Main XS Weight=0.5
Downstream XS Weight=0.25
Number of DS XS's Weighted with US Boundary= 1
Upstream Boundary Weight= 1
Weight of XSs Associated with US Boundary= 0
Number of US XS's Weighted with DS Boundary= 1
Downstream Boundary Weight= 0.5
Weight of XSs Associated with DS Boundary= 0.5
Sediment Output Level= 4
Mass or Volume Output= 0
Output Increment Type= 1
Profile and TS Output Increment= 10
XS Output Flag= 0
XS Output Increment= 10
Disregard all LS=0
Disregard all Conn=0
Disregard all Breaches=0
Disregard all Pumps=0

--- Conroe Lake 053.f01 (steady flow) ---

Flow Title=Multiple
Program Version=4.10
Number of Profiles= 7
Profile Names=10-year,25-year,50-year,1pct_min,100-year,1pct_plu,500-year
River Rch & RM=Conroe Lake 053,Reach-1         ,3777
     560     755    1017     452    1365    4122    2535
River Rch & RM=Conroe Lake 053,Reach-1         ,3334
     667     905    1224     545    1646    4971    3075
River Rch & RM=Conroe Lake 053,Reach-1         ,207
    1348    1892    2620    1190    3595   10857    7004
Boundary for River Rch & Prof#=Conroe Lake 053,Reach-1         , 1
Up Type= 0
Dn Type= 3
Dn Slope=0.01
Boundary for River Rch & Prof#=Conroe Lake 053,Reach-1         , 2
Up Type= 0
Dn Type= 3
Dn Slope=0.01
Boundary for River Rch & Prof#=Conroe Lake 053,Reach-1         , 3
Up Type= 0
Dn Type= 3
Dn Slope=0.01
Boundary for River Rch & Prof#=Conroe Lake 053,Reach-1         , 4
Up Type= 0
Dn Type= 3
Dn Slope=0.01
Boundary for River Rch & Prof#=Conroe Lake 053,Reach-1         , 5
Up Type= 0
Dn Type= 3
Dn Slope=0.01
Boundary for River Rch & Prof#=Conroe Lake 053,Reach-1         , 6
Up Type= 0
Dn Type= 3
Dn Slope=0.01
Boundary for River Rch & Prof#=Conroe Lake 053,Reach-1         , 7
Up Type= 0
Dn Type= 3
Dn Slope=0.01
DSS Import GetInterval= 0
DSS Import GetPeak= 0
DSS Import FillOption= 0

--- Conroe Lake 053.f02 (steady flow) ---

Flow Title=Orig_BLE_Flow
Program Version=4.10
Number of Profiles= 7
Profile Names=10-year,25-year,50-year,1pct_min,100-year,1pct_plu,500-year
River Rch & RM=Conroe Lake 053,Reach-1         ,3777
     560     740     884     348    1050    3170    1474
River Rch & RM=Conroe Lake 053,Reach-1         ,3334
     667     887    1064     419    1266    3824    1788
River Rch & RM=Conroe Lake 053,Reach-1         ,207
    1348    1855    2278     916    2765    8352    4072
Boundary for River Rch & Prof#=Conroe Lake 053,Reach-1         , 1
Up Type= 0
Dn Type= 3
Dn Slope=0.01
Boundary for River Rch & Prof#=Conroe Lake 053,Reach-1         , 2
Up Type= 0
Dn Type= 3
Dn Slope=0.01
Boundary for River Rch & Prof#=Conroe Lake 053,Reach-1         , 3
Up Type= 0
Dn Type= 3
Dn Slope=0.01
Boundary for River Rch & Prof#=Conroe Lake 053,Reach-1         , 4
Up Type= 0
Dn Type= 3
Dn Slope=0.01
Boundary for River Rch & Prof#=Conroe Lake 053,Reach-1         , 5
Up Type= 0
Dn Type= 3
Dn Slope=0.01
Boundary for River Rch & Prof#=Conroe Lake 053,Reach-1         , 6
Up Type= 0
Dn Type= 3
Dn Slope=0.01
Boundary for River Rch & Prof#=Conroe Lake 053,Reach-1         , 7
Up Type= 0
Dn Type= 3
Dn Slope=0.01
DSS Import GetInterval= 0
DSS Import GetPeak= 0
DSS Import FillOption= 0

--- Conroe Lake 053.g01 (geometry) ---

Geom Title=Existing Conditions
Program Version=4.10

River Reach=Conroe Lake 053 ,Reach-1
Reach XY= 30
      3807993.23     10233801.84      3807968.23     10233776.84
      3807948.23     10233646.84      3807858.23     10233526.84
      3807838.23     10233416.84      3807768.23     10233346.84
      3807708.23     10233236.84      3807698.23     10233126.84
      3807728.23     10232996.84      3807718.23     10232936.84
      3807768.23     10232866.84      3807838.23     10232826.84
      3807838.23     10232776.84      3807908.23     10232716.84
      3807928.23     10232646.84      3807978.23     10232596.84
      3808078.23     10232276.84      3808168.23     10232096.84
      3808238.23     10232036.84      3808248.23     10231816.84
      3808338.23     10231666.84      3808328.23     10231606.84
      3808398.23     10231576.84      3808458.23     10231466.84
      3808458.23     10231346.84      3808368.23     10231256.84
      3808298.23     10231256.84      3808168.23     10231146.84
      3808138.23     10231026.84      3808168.23     10230716.84

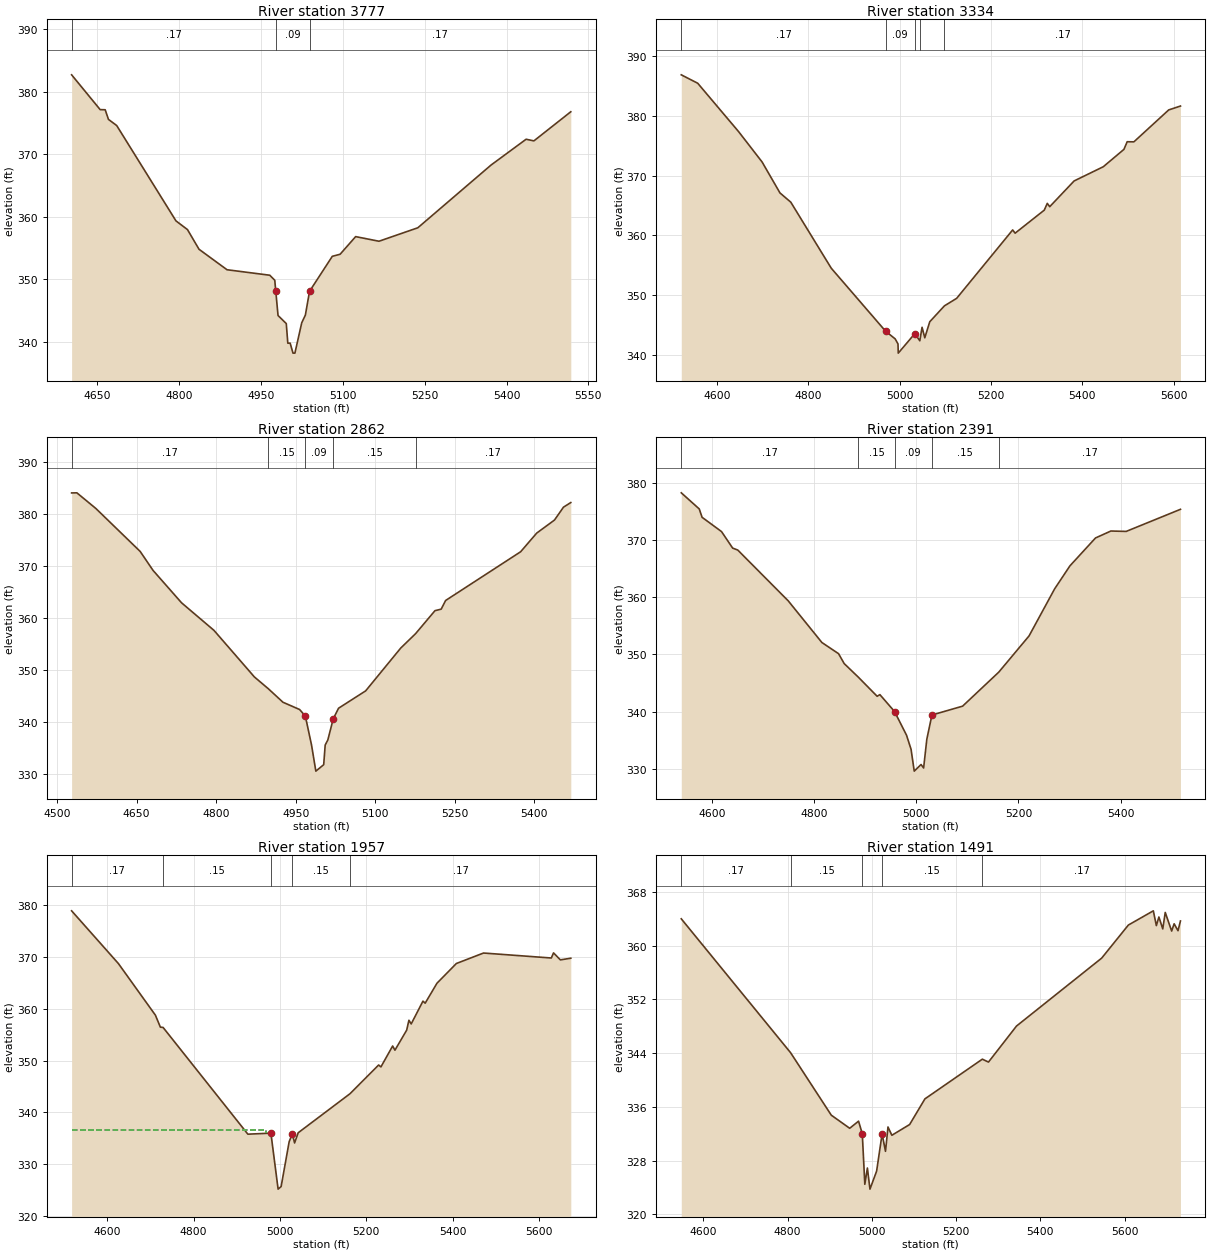
Type RM Length L Ch R = 1 ,3777    ,443,443,443
BEGIN DESCRIPTION:
Conroe Lake 053 7.0
END DESCRIPTION:
XS GIS Cut Line= 3
      3808300.52     10233489.97      3807968.23     10233706.84
      3807577.68     10234046.82
#Sta/Elev= 30
  4603.2  382.68  4655.5  377.12  4664.7   377.1  4670.7  375.56  4685.8  374.58
  4794.4  359.35  4815.5  357.96  4836.6  354.82  4887.9  351.55  4966.3  350.67
  4975.4  349.87 4977.27   348.1  4981.4  344.24  4996.5  342.95  4999.3  339.82
  5003.6  339.82  5008.8  338.23  5012.3  338.23  5024.8  343.07  5031.5  344.31
  5039.1   348.1  5080.8  353.69  5095.1  354.02  5123.6  356.84  5166.3   356.1
  5237.5  358.25  5371.7  368.27  5435.9  372.39  5450.2  372.13  5517.8  376.78
#Mann= 3 , 0 , 0
  4603.2     .17       0 4977.27     .09       0  5039.1     .17       0
Bank Sta=4977.27,5039.1
XS Rating Curve= 0 ,0
Exp/Cntr=0.3,0.1

Type RM Length L Ch R = 1 ,3334    ,472,472,472
BEGIN DESCRIPTION:
Conroe Lake 053 6.0
END DESCRIPTION:
XS GIS Cut Line= 3
      3808228.66      10233216.6      3807768.23     10233346.84
      3807204.27     10233591.89
#Sta/Elev= 30
  4521.5  386.91  4557.5   385.5  4647.1  377.39  4698.5  372.31  4737.7  367.12
  4761.4  365.57    4850  354.51  4969.2  343.94    4990  342.67  4996.2  341.82
  4996.8  340.28  5033.1  343.55    5044  342.35  5048.9  344.61  5054.9  342.85
  5065.8  345.54  5097.9   348.2  5124.7  349.46  5247.4  360.92  5252.8  360.38
  5316.6  364.24  5323.2  365.37  5328.6  364.82    5382  369.13  5445.9  371.51
  5491.1  374.42  5498.2   375.7  5512.9  375.68  5589.2  381.03  5614.9  381.68
#Mann= 5 ,-1 , 0
  4521.5     .17       0  4969.2     .09       0  5033.1     .17       0
    5044     .15       0  5097.9     .17       0
Bank Sta=4969.2,5033.1
XS Rating Curve= 0 ,0
Exp/Cntr=0.3,0.1

Type RM Length L Ch R = 1 ,2862    ,471,471,471
BEGIN DESCRIPTION:
Conroe Lake 053 5.0
END DESCRIPTION:
XS GIS Cut Line= 3
        3808157.     10233112.43      3807718.23     10232936.84
       3807254.2     10232871.55
#Sta/Elev= 30
  4527.4     384  4537.3  384.02  4573.2     381  4656.7  372.74  4680.9   369.1
  4734.7  362.86  4795.8  357.56    4872   348.6  4898.3  346.33  4925.9  343.73
  4957.3  342.33  4968.1  341.06  4979.7  335.53  4987.9  330.48  5002.7  331.72
  5005.5   335.5  5010.5  336.48  5020.6  340.52  5030.7  342.58  5081.8  345.92
  5147.9  354.15  5175.9  356.92  5212.5  361.35  5224.2  361.64  5232.6  363.31
    5374  372.68  5404.3  376.27  5437.9  378.79  5454.8  381.26  5468.6  382.15
#Mann= 5 ,-1 , 0
  4527.4     .17       0  4898.3     .15       0  4968.1     .09       0
  5020.6     .15       0  5175.9     .17       0
Bank Sta=4968.1,5020.6
XS Rating Curve= 0 ,0
Exp/Cntr=0.3,0.1

Type RM Length L Ch R = 1 ,2391    ,434,434,434
BEGIN DESCRIPTION:
Conroe Lake 053 4.0
END DESCRIPTION:
XS GIS Cut Line= 3
      3808400.05     10232782.57      3807978.23     10232596.84
      3807461.67     10232565.64
#Sta/Elev= 30
  4539.1  378.32  4574.3   375.5  4579.9  374.03    4618  371.53  4639.8  368.64
  4649.9  368.29  4748.7   359.4  4814.7   352.1  4847.4  350.14  4858.4  348.41
    4886  346.04    4923  342.68  4928.4  342.97  4957.2     340  4980.6  335.86
  4989.5  333.39  4995.7  329.57  5009.1  330.73  5014.1  330.12  5020.4  335.17
  5030.4   339.4  5090.5  340.95  5161.4  346.91  5220.8  353.26  5270.9   361.5
  5300.9  365.53    5351  370.41  5381.1  371.63  5411.1  371.56  5517.5  375.43
#Mann= 5 ,-1 , 0
  4539.1     .17       0    4886     .15       0  4957.2     .09       0
  5030.4     .15       0  5161.4     .17       0
Bank Sta=4957.2,5030.4
XS Rating Curve= 0 ,0
Exp/Cntr=0.3,0.1

Type RM Length L Ch R = 1 ,1957    ,466,466,466
BEGIN DESCRIPTION:
Conroe Lake 053 3.0
END DESCRIPTION:
XS GIS Cut Line= 3
      3808560.64     10232385.43      3808108.23     10232216.84
      3807464.74       10232418.
#Sta/Elev= 30
  4517.2  378.93  4625.7  368.74  4711.4  358.78  4722.9  356.47  4729.2  356.41
  4925.7   335.8  4979.1     336  4995.8  325.19  5002.8  325.69  5021.4  334.34
  5028.8  335.91    5034   334.1  5042.3  336.07  5162.4  343.61  5228.8  349.16
  5234.1  348.79  5261.3  352.83  5266.6  352.02  5293.8  355.89    5299   357.8
  5304.3  357.09  5331.5  361.49  5336.7   361.1    5364  364.95    5409  368.76
  5471.9  370.78    5629  369.82  5634.2  370.81    5650  369.46  5674.2  369.78
#Mann= 5 ,-1 , 0
  4517.2     .17       0  4729.2     .15       0  4979.1     .09       0
  5028.8     .15       0  5162.4     .17       0
#XS Ineff= 2 , 0
       0  4968.3  336.63               0
Permanent Ineff=
       F       F
Bank Sta=4979.1,5028.8
XS Rating Curve= 0 ,0
Exp/Cntr=0.3,0.1

Type RM Length L Ch R = 1 ,1491    ,474,474,474
BEGIN DESCRIPTION:
Conroe Lake 053 2.0
END DESCRIPTION:
XS GIS Cut Line= 3
      3808622.19     10232092.04      3808248.23     10231837.27
      3807633.88     10232236.55
#Sta/Elev= 30
  4547.5     364  4807.1  344.06  4903.7  334.76  4947.4  332.81  4968.4  333.87
 4977.26     332  4983.3  324.47  4989.4  326.89  4995.5  323.75  5011.3  326.43
  5024.3  331.96  5032.4  329.38  5038.3     333  5047.5  331.77  5089.7  333.37
    5126  337.19  5262.3   343.1  5276.9  342.67  5343.4  348.03  5545.7  358.15
    5609  363.07  5668.3  365.19  5675.5  362.99  5681.5  364.27  5690.7   362.5
  5696.6  364.95  5711.8  362.18  5717.7  363.26  5726.9  362.23  5732.7  363.68
#Mann= 5 ,-1 , 0
  4547.5     .17       0  4807.1     .15       0 4977.26     .09       0
  5024.3     .15       0  5262.3     .17       0
#XS Ineff= 2 , 0
       0  4968.4  333.87               0
Permanent Ineff=
       F       F
Bank Sta=4977.26,5024.3
XS Rating Curve= 0 ,0
Exp/Cntr=0.3,0.1

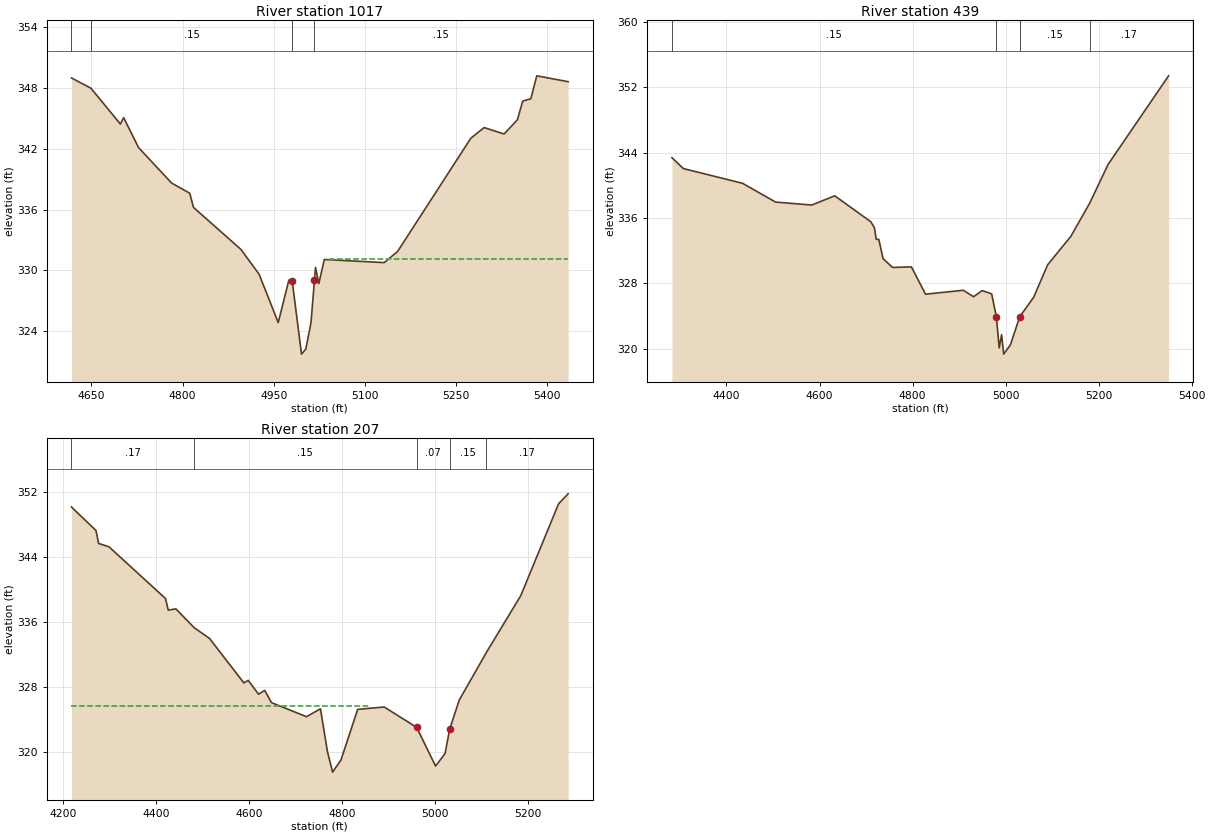
Type RM Length L Ch R = 1 ,1017    ,578,578,578
BEGIN DESCRIPTION:
Conroe Lake 053 1.0
END DESCRIPTION:
XS GIS Cut Line= 3
      3808804.83     10231616.44      3808448.23     10231477.55
       3808051.8     10231655.39
#Sta/Elev= 30
  4617.3  349.01  4649.2     348  4697.8  344.45  4703.1  345.09  4727.6  342.13
    4782  338.62  4811.9  337.61    4818  336.21  4896.2  332.05    4926   329.6
  4957.5  324.82    4975  329.02  4980.4  328.97  4995.8   321.7  5002.9   322.2
  5011.4  324.81  5017.1     329  5018.8  330.27  5024.3  328.68  5033.3  331.06
  5131.9  330.75  5153.9  331.85  5274.4  343.05  5296.3   344.1  5329.2  343.47
  5351.1  344.88  5359.7  346.72  5373.1  346.95  5382.9  349.22  5434.5  348.64
#Mann= 4 ,-1 , 0
  4617.3     .17       0  4649.2     .15       0  4980.4     .09       0
  5017.1     .15       0
#XS Ineff= 2 , 0
       0                    5042       0  331.09
Permanent Ineff=
       F       F
Bank Sta=4980.4,5017.1
XS Rating Curve= 0 ,0
Exp/Cntr=0.3,0.1

Type RM Length L Ch R = 1 ,439     ,232,232,232
BEGIN DESCRIPTION:
Conroe Lake 053 1.5
END DESCRIPTION:
XS GIS Cut Line= 4
      3808732.17     10231490.92      3808441.17     10231160.45
      3808168.23     10231113.98      3807817.84     10231111.07
#Sta/Elev= 30
  4282.8  343.37  4307.3  342.04  4434.5  340.24  4505.6  337.94  4583.4  337.58
  4632.7  338.71  4710.5  335.53  4718.1  334.78  4721.9  333.39  4727.4  333.39
  4736.6  331.03  4756.9  329.95  4797.5  330.02  4827.9  326.68  4909.1  327.16
  4931.2  326.37  4949.7  327.12    4970  326.72  4980.1  323.94  4986.3  320.12
  4991.4  321.73  4995.9  319.35  5010.4  320.49  5030.4  323.92  5060.4  326.31
  5090.4  330.27  5140.4  333.76  5180.7   337.8  5220.4  342.55  5350.4  353.38
#Mann= 4 ,-1 , 0
  4282.8     .15       0  4980.1     .07       0  5030.4     .15       0
  5180.7     .17       0
#XS Ineff= 2 , 0
       0  4949.7  327.12               0
Permanent Ineff=
       F       F
Bank Sta=4980.1,5030.4
XS Rating Curve= 0 ,0
Exp/Cntr=0.3,0.1

Type RM Length L Ch R = 1 ,207     ,0,0,0
BEGIN DESCRIPTION:
Conroe Lake 053 15.0
END DESCRIPTION:
XS GIS Cut Line= 3
      3808617.87     10230361.04      3808358.68     10230867.17
      3807867.82     10230961.08
#Sta/Elev= 30
  4217.6  350.12  4270.3  347.24    4276  345.65  4298.2  345.24  4419.9  338.89
  4425.8  337.47  4442.3  337.62  4481.2  335.33  4514.6  333.99  4588.4  328.54
  4597.8  328.85    4620  327.15  4633.3  327.62  4647.8  326.12  4723.2  324.39
  4753.2  325.36  4768.2  320.12  4779.3  317.59  4797.3  319.08  4833.3  325.29
  4890.4  325.58  4960.2  323.08  5000.9  318.33  5021.3  319.88  5031.4   322.9
  5051.8  326.43  5110.1  332.27  5184.2  339.25  5265.6  350.53    5286  351.74
#Mann= 5 ,-1 , 0
  4217.6     .17       0  4481.2     .15       0  4960.2     .07       0
  5031.4     .15       0  5110.1     .17       0
#XS Ineff= 2 , 0
       0  4858.3  325.74               0
Permanent Ineff=
       F       F
Bank Sta=4960.2,5031.4
XS Rating Curve= 0 ,0
Exp/Cntr=0.3,0.1

Chan Stop Cuts=-1
Use User Specified Reach Order=0
Composite Channel Slope=5