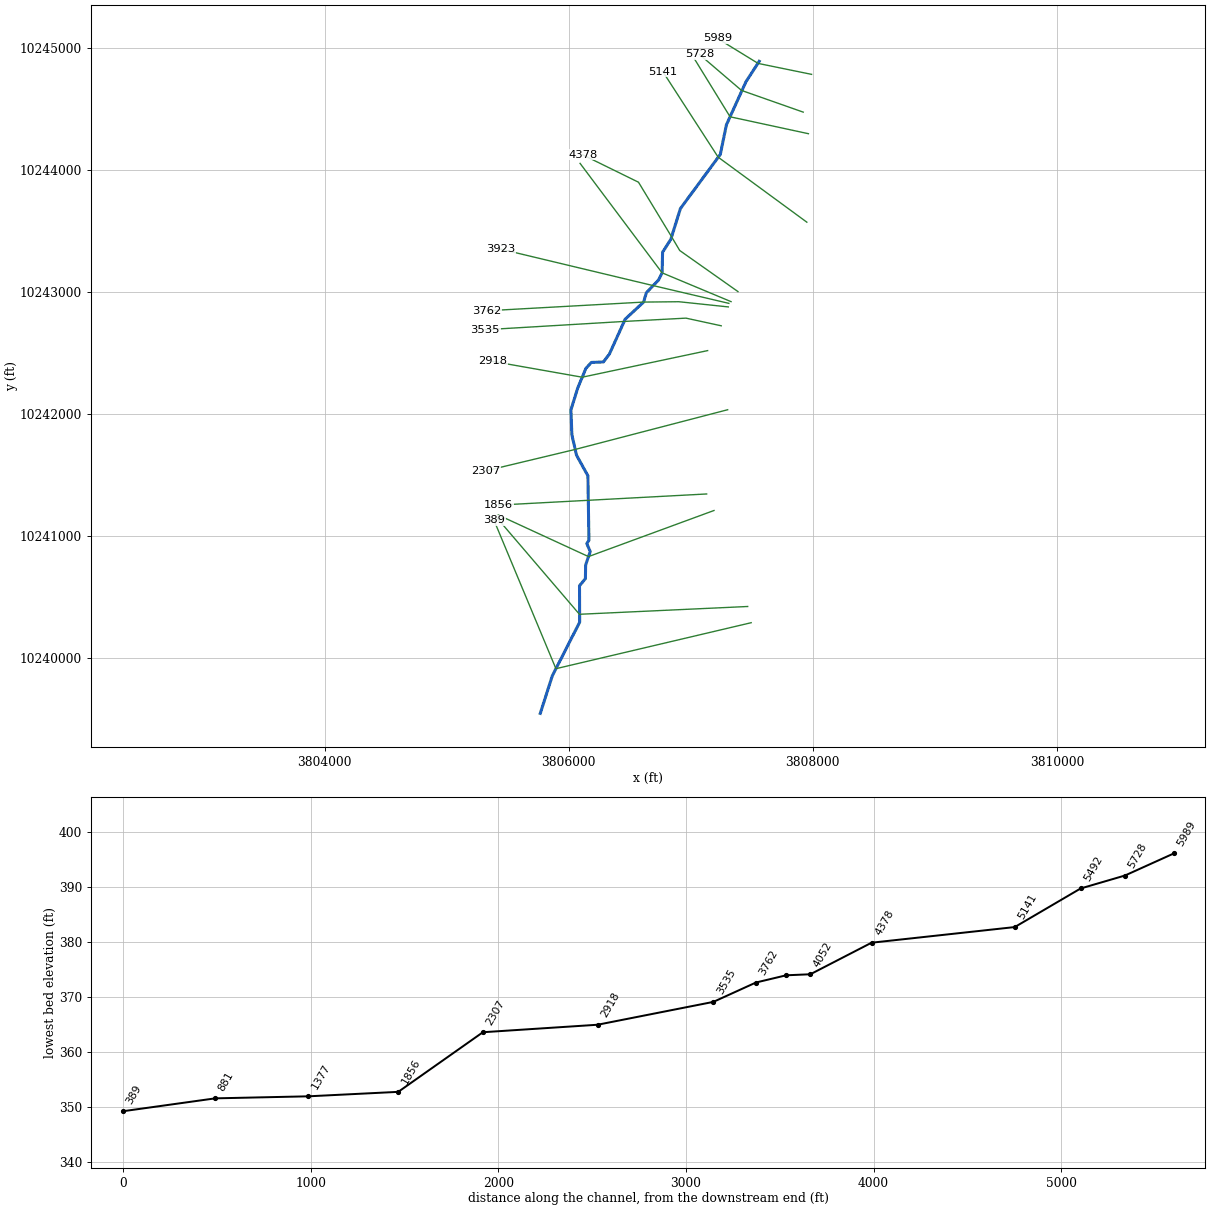
--- Conroe Lake 056.prj (project) ---

Proj Title=Conroe Lake 056 Base Level Engineering
Current Plan=p01
Default Exp/Contr=0.3,0.1
English Units
Geom File=g01
Flow File=f01
Flow File=f02
Plan File=p01
Y Axis Title=Elevation
X Axis Title(PF)=Main Channel Distance
X Axis Title(XS)=Station
BEGIN DESCRIPTION:
Conroe Lake 056
END DESCRIPTION:
DSS File=dss
DSS Export Rating Curves= 0
DSS Export Rating Curve Sorted= 0
DSS Export Volume Flow Curves= 0
DXF OffsetX= 0
DXF OffsetY= 0
DXF ScaleX= 1
DXF ScaleY= 10

--- Conroe Lake 056.p01 (plan) ---

Plan Title=Multiple Run
Program Version=4.10
Short Identifier=Multiple Run
Geom File=g01
Flow File=f01
Subcritical Flow
K Sum by GR= 0
Std Step Tol= 0.01
Critical Tol= 0.01
Num of Std Step Trials= 20
Max Error Tol= 0.3
Flow Tol Ratio= 0.001
Split Flow NTrial= 30
Split Flow Tol= 0.02
Split Flow Ratio= 0.02
Log Output Level= 0
Friction Slope Method= 1
Unsteady Friction Slope Method= 2
Unsteady Bridges Friction Slope Method= 1
Parabolic Critical Depth
Global Vel Dist= 1 , 1 , 1
Global Log Level= 0
CheckData=True
Encroach Param=-1 ,0,0, 0
BEGIN DESCRIPTION:
Multiple Run
END DESCRIPTION:
Computation Interval=1HOUR
Output Interval=1HOUR
Run HTab= 0
Run UNet= 0
Run PostProcess= 0
Run WQNet= 0
UNET Theta= 1
UNET Theta Warmup= 1
UNET ZTol= 0.02
UNET ZSATol= 0.05
UNET MxIter= 20
UNET MaxInSteps= 0
UNET DtIC= 0
UNET DtMin= 0
UNET MaxCRTS= 20
UNET WFStab= 2
UNET SFStab= 1
UNET WFX= 1
UNET SFX= 1
UNET DSS MLevel= 4
UNET DZMax Abort= 100
UNET Convert EG Bridges= 0
UNET Use Existing IB Tables=-1
UNET Froude Reduction=False
UNET Froude Limit= 1
UNET Froude Power= 10
UNET Time Slicing=0,0, 5
UNET Junction Losses=0
Instantaneous Interval=1HOUR
DSS File=dss
Write IC File= 0
Write IC File at Sim End=0
Echo Input=False
Echo Parameters=False
Echo Output=False
Write Detailed= 0
WQ AD Non Conservative
WQ ULTIMATE=-1
WQ Max Comp Step=1HOUR
WQ Output Interval=15MIN
WQ Output Selected Increments= 0
WQ Output face flow=0
WQ Output face velocity=0
WQ Output face area=0
WQ Output face dispersion=0
WQ Output cell volume=0
WQ Output cell surface area=0
WQ Output cell continuity=0
WQ Output cumulative cell continuity=0
WQ Output face conc=0
WQ Output face dconc_dx=0
WQ Output face courant=0
WQ Output face peclet=0
WQ Output face adv mass=0
WQ Output face disp mass=0
WQ Output cell mass=0
WQ Output cell source sink temp=0
WQ Output cell source sink nsm=0
WQ Output MaxMinRange=-1
WQ Daily Max Min Mean=-1
WQ Daily Range=0
WQ Daily Time=0
WQ Create Restart=0
WQ Fixed Restart=0
WQ System Summary=0
WQ Use Fixed Temperature=0
Sorting and Armoring Iterations= 10
XS Update Threshold= 0.02
Hydraulics Update Threshold= 0.02
Energy Slope Method= 1
Volume Change Method= 0
XS Weighting Method= 0
Number of US Weighted Cross Sections= 1
Number of DS Weighted Cross Sections= 1
Upstream XS Weight=0.25
Main XS Weight=0.5
Downstream XS Weight=0.25
Number of DS XS's Weighted with US Boundary= 1
Upstream Boundary Weight= 1
Weight of XSs Associated with US Boundary= 0
Number of US XS's Weighted with DS Boundary= 1
Downstream Boundary Weight= 0.5
Weight of XSs Associated with DS Boundary= 0.5
Sediment Output Level= 4
Mass or Volume Output= 0
Output Increment Type= 1
Profile and TS Output Increment= 10
XS Output Flag= 0
XS Output Increment= 10
Disregard all LS=0
Disregard all Conn=0
Disregard all Breaches=0
Disregard all Pumps=0

--- Conroe Lake 056.f01 (steady flow) ---

Flow Title=Multiple
Program Version=4.10
Number of Profiles= 7
Profile Names=10-year,25-year,50-year,1pct_min,100-year,1pct_plu,500-year
River Rch & RM=Conroe Lake 056,Reach-1         ,5989
     317     414     547     240     724    2186    1304
River Rch & RM=Conroe Lake 056,Reach-1         ,4378
     636     864    1171     523    1580    4772    2967
Boundary for River Rch & Prof#=Conroe Lake 056,Reach-1         , 1
Up Type= 0
Dn Type= 3
Dn Slope=0.005
Boundary for River Rch & Prof#=Conroe Lake 056,Reach-1         , 2
Up Type= 0
Dn Type= 3
Dn Slope=0.005
Boundary for River Rch & Prof#=Conroe Lake 056,Reach-1         , 3
Up Type= 0
Dn Type= 3
Dn Slope=0.005
Boundary for River Rch & Prof#=Conroe Lake 056,Reach-1         , 4
Up Type= 0
Dn Type= 3
Dn Slope=0.005
Boundary for River Rch & Prof#=Conroe Lake 056,Reach-1         , 5
Up Type= 0
Dn Type= 3
Dn Slope=0.005
Boundary for River Rch & Prof#=Conroe Lake 056,Reach-1         , 6
Up Type= 0
Dn Type= 3
Dn Slope=0.005
Boundary for River Rch & Prof#=Conroe Lake 056,Reach-1         , 7
Up Type= 0
Dn Type= 3
Dn Slope=0.005
DSS Import GetInterval= 0
DSS Import GetPeak= 0
DSS Import FillOption= 0

--- Conroe Lake 056.f02 (steady flow) ---

Flow Title=Orig_BLE_Flow
Program Version=4.10
Number of Profiles= 7
Profile Names=10-year,25-year,50-year,1pct_min,100-year,1pct_plu,500-year
River Rch & RM=Conroe Lake 056,Reach-1         ,5989
     317     406     476     184     557    1683     758
River Rch & RM=Conroe Lake 056,Reach-1         ,4378
     636     847    1018     402    1215    3670    1725
Boundary for River Rch & Prof#=Conroe Lake 056,Reach-1         , 1
Up Type= 0
Dn Type= 3
Dn Slope=0.005
Boundary for River Rch & Prof#=Conroe Lake 056,Reach-1         , 2
Up Type= 0
Dn Type= 3
Dn Slope=0.005
Boundary for River Rch & Prof#=Conroe Lake 056,Reach-1         , 3
Up Type= 0
Dn Type= 3
Dn Slope=0.005
Boundary for River Rch & Prof#=Conroe Lake 056,Reach-1         , 4
Up Type= 0
Dn Type= 3
Dn Slope=0.005
Boundary for River Rch & Prof#=Conroe Lake 056,Reach-1         , 5
Up Type= 0
Dn Type= 3
Dn Slope=0.005
Boundary for River Rch & Prof#=Conroe Lake 056,Reach-1         , 6
Up Type= 0
Dn Type= 3
Dn Slope=0.005
Boundary for River Rch & Prof#=Conroe Lake 056,Reach-1         , 7
Up Type= 0
Dn Type= 3
Dn Slope=0.005
DSS Import GetInterval= 0
DSS Import GetPeak= 0
DSS Import FillOption= 0

--- Conroe Lake 056.g01 (geometry) ---

Geom Title=Existing Conditions
Program Version=4.10

River Reach=Conroe Lake 056 ,Reach-1
Reach XY= 30
      3807560.98     10244887.51      3807452.24      10244719.9
      3807291.86     10244366.12      3807242.33     10244124.75
      3806915.61     10243681.55      3806836.45     10243428.57
       3806769.3     10243323.53      3806765.48     10243154.46
      3806736.53     10243096.04       3806636.6      10242991.9
      3806613.71     10242914.99      3806463.03      10242775.1
      3806333.24      10242488.5      3806284.14     10242424.39
      3806185.61     10242420.58      3806140.75      10242371.1
      3806074.09     10242210.95      3806018.54     10242032.12
      3806026.29      10241827.1      3806064.04     10241661.43
      3806157.49      10241491.6      3806165.92     10240963.97
      3806148.45     10240936.46      3806176.59       10240871.
      3806139.05     10240761.62      3806136.91      10240649.3
      3806088.69     10240590.77      3806090.02      10240292.6
      3805865.65     10239852.68      3805767.34     10239545.49

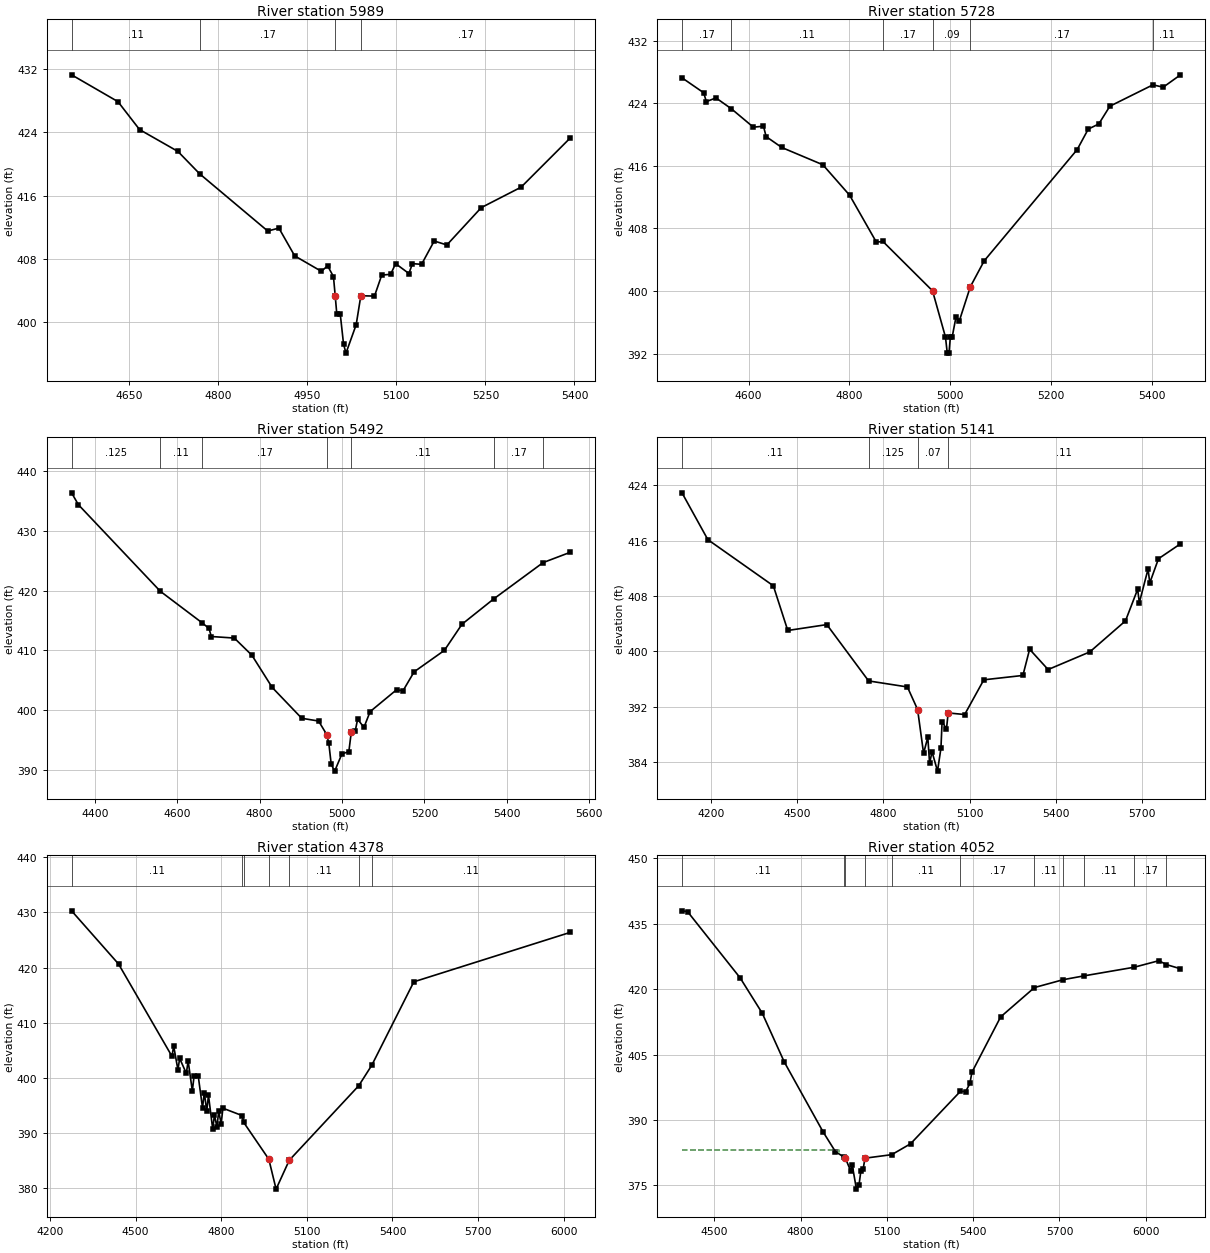
Type RM Length L Ch R = 1 ,5989    ,261,261,261
BEGIN DESCRIPTION:
Conroe Lake 056 14.0
END DESCRIPTION:
XS GIS Cut Line= 3
      3807990.01     10244780.52      3807551.99     10244870.18
      3807217.46     10245075.67
#Sta/Elev= 30
  4552.9  431.27    4631  427.88  4667.4  424.35    4732  421.59  4768.6  418.76
  4883.3  411.53  4902.1   411.9  4928.7  408.39  4973.6  406.44  4984.2  407.13
    4994  405.77 4996.98  403.32  4999.6  401.07  5005.4  401.07    5011  397.23
  5015.1   396.1  5032.3   399.7  5040.1  403.35  5063.1  403.31  5075.3  405.96
  5090.3  406.06  5098.7  407.41  5121.1  406.16    5127  407.41  5142.4  407.32
  5163.7  410.27    5185  409.77    5243  414.49    5310  417.07  5392.6  423.27
#Mann= 4 ,-1 , 0
  4552.9     .11       0  4768.6     .17       0 4996.98     .09       0
  5040.1     .17       0
#XS Ineff= 2 , 0
       0                  5040.1       0  403.35
Permanent Ineff=
       F       F
Bank Sta=4996.98,5040.1
XS Rating Curve= 0 ,0
Exp/Cntr=0.3,0.1

Type RM Length L Ch R = 1 ,5728    ,236,236,236
BEGIN DESCRIPTION:
Mapping XS ab674624
END DESCRIPTION:
XS GIS Cut Line= 3
      3807921.45     10244471.07      3807415.82     10244649.02
      3807071.82     10244943.26
#Sta/Elev= 30
  4467.8  427.25  4510.8  425.34  4516.1  424.21  4535.2  424.68  4565.8  423.29
  4609.4  420.94  4629.4  421.07  4634.7  419.74  4665.7  418.35  4747.2  416.14
  4800.3  412.25  4853.3  406.26  4866.4  406.34  4964.7  400.04  4990.4  394.13
  4993.9  392.08  4997.4  392.08  5000.1  394.18  5003.8  394.18  5011.2  396.68
  5017.8  396.19  5039.7  400.56  5067.2  403.87  5251.6  418.08  5273.6   420.7
  5294.4  421.35  5316.4  423.62  5401.8  426.35  5422.2  426.05  5456.5  427.63
#Mann= 6 ,-1 , 0
  4467.8     .17       0  4565.8     .11       0  4866.4     .17       0
  4964.7     .09       0  5039.7     .17       0  5401.8     .11       0
Bank Sta=4964.7,5039.7
XS Rating Curve= 0 ,0
Exp/Cntr=0.3,0.1

Type RM Length L Ch R = 1 ,5492    ,351,351,351
BEGIN DESCRIPTION:
Conroe Lake 056 13.0
END DESCRIPTION:
XS GIS Cut Line= 3
      3807964.02      10244294.4      3807322.21     10244432.94
      3807031.96     10244904.59
#Sta/Elev= 30
  4343.4  436.39  4359.9   434.4  4558.9  419.88  4660.8  414.57  4677.1  413.65
  4682.6   412.3  4738.5  412.04  4781.2  409.16  4830.5  403.76  4902.2  398.59
  4943.1  398.13  4962.9  395.86    4968  394.37  4973.8  390.87  4982.2  389.73
  4999.7  392.61  5016.6     393  5022.5  396.27    5032  396.44  5037.9  398.43
  5053.3  397.07  5068.3  399.71  5132.6  403.38    5148  403.19  5175.1  406.38
  5248.5  409.97  5291.3  414.36  5368.3   418.6  5488.2  424.69  5553.8  426.41
#Mann= 7 ,-1 , 0
  4343.4    .125       0  4558.9     .11       0  4660.8     .17       0
  4962.9     .07       0  5022.5     .11       0  5368.3     .17       0
  5488.2     .11       0
Bank Sta=4962.9,5022.5
XS Rating Curve= 0 ,0
Exp/Cntr=0.3,0.1

Type RM Length L Ch R = 1 ,5141    ,763,763,763
BEGIN DESCRIPTION:
Conroe Lake 056 12.0
END DESCRIPTION:
XS GIS Cut Line= 3
      3807950.96      10243569.6      3807224.66     10244102.11
      3806772.15      10244801.6
#Sta/Elev= 30
  4099.4  422.89  4189.4  416.13  4417.1  409.47  4467.3  403.02  4603.1  403.87
  4748.4  395.74  4883.3  394.87  4918.8  391.61  4939.6  385.29  4954.3  387.61
  4960.5  383.85    4969  385.52  4988.1  382.72    5000  386.03    5004  389.88
  5019.2  388.78  5025.1  391.12  5082.5  390.89  5149.1   395.9    5285  396.53
  5308.4  400.31  5372.7  397.38  5517.8  399.93  5641.8  404.41  5684.1  408.97
    5690  407.04  5720.3  411.88  5726.3  409.89  5756.6  413.38  5833.1  415.53
#Mann= 4 ,-1 , 0
  4099.4     .11       0  4748.4    .125       0  4918.8     .07       0
  5025.1     .11       0
#XS Ineff= 2 , 0
       0                    5004       0  389.88
Permanent Ineff=
       F       F
Bank Sta=4918.8,5025.1
XS Rating Curve= 0 ,0
Exp/Cntr=0.3,0.1

Type RM Length L Ch R = 1 ,4378    ,326,326,326
BEGIN DESCRIPTION:
Conroe Lake 056 10.0
END DESCRIPTION:
XS GIS Cut Line= 5
      3807386.73     10243001.02      3806909.91     10243337.33
      3806838.06      10243458.2      3806571.95     10243896.91
      3806114.86      10244121.3
#Sta/Elev= 30
  4275.9  430.26  4440.3  420.64  4627.5  403.93  4633.6  405.78  4648.4  401.47
  4654.5  403.54    4678  400.82  4684.1  403.12  4698.9  397.65    4705  400.36
  4719.8  400.28  4734.6  394.56  4740.7  397.37  4749.4  394.05  4755.5  396.86
  4770.3  390.73  4776.4  393.33  4785.1  391.09  4791.2  394.01  4799.9   391.7
    4806  394.53  4873.6  393.19    4879  391.95  4966.8   385.3  4992.3  379.88
  5038.4   385.1  5281.9   398.6  5327.6  402.31  5474.9  417.41  6022.3  426.35
#Mann= 7 ,-1 , 0
  4275.9     .11       0  4873.6     .15       0    4879     .11       0
  4966.8     .07       0  5038.4     .11       0  5281.9     .17       0
  5327.6     .11       0
Bank Sta=4966.8,5038.4
XS Rating Curve= 0 ,0
Exp/Cntr=0.3,0.1

Type RM Length L Ch R = 1 ,4052    ,129,129,129
BEGIN DESCRIPTION:
Conroe Lake 056 9.0
END DESCRIPTION:
XS GIS Cut Line= 3
       3807330.3     10242918.55      3806765.48     10243154.46
      3806093.35     10244051.35
#Sta/Elev= 30
  4387.9  437.93  4407.1  437.76    4590  422.57  4666.9  414.47  4743.7  403.26
    4879   387.2  4921.3  382.74  4949.4  381.56  4955.9  381.24  4974.3  378.32
  4979.7  379.69  4994.3  374.15  5003.2  375.08  5009.5  378.19  5017.8  378.81
    5024  381.24    5117  382.05  5182.4  384.54  5355.7  396.56  5374.1  396.52
  5388.7  398.36  5395.7  400.92  5495.6  413.62  5613.2  420.35  5713.8  422.16
  5786.7  423.04  5960.2  425.01  6045.5   426.5  6071.8  425.61  6120.8  424.65
#Mann= 11 ,-1 , 0
  4387.9     .11       0  4949.4     .15       0  4955.9     .09       0
    5024     .15       0    5117     .11       0  5355.7     .17       0
  5613.2     .11       0  5713.8     .17       0  5786.7     .11       0
  5960.2     .17       0  6071.8     .11       0
#XS Ineff= 2 , 0
       0  4932.4   383.1               0
Permanent Ineff=
       F       F
Bank Sta=4955.9,5024
XS Rating Curve= 0 ,0
Exp/Cntr=0.3,0.1

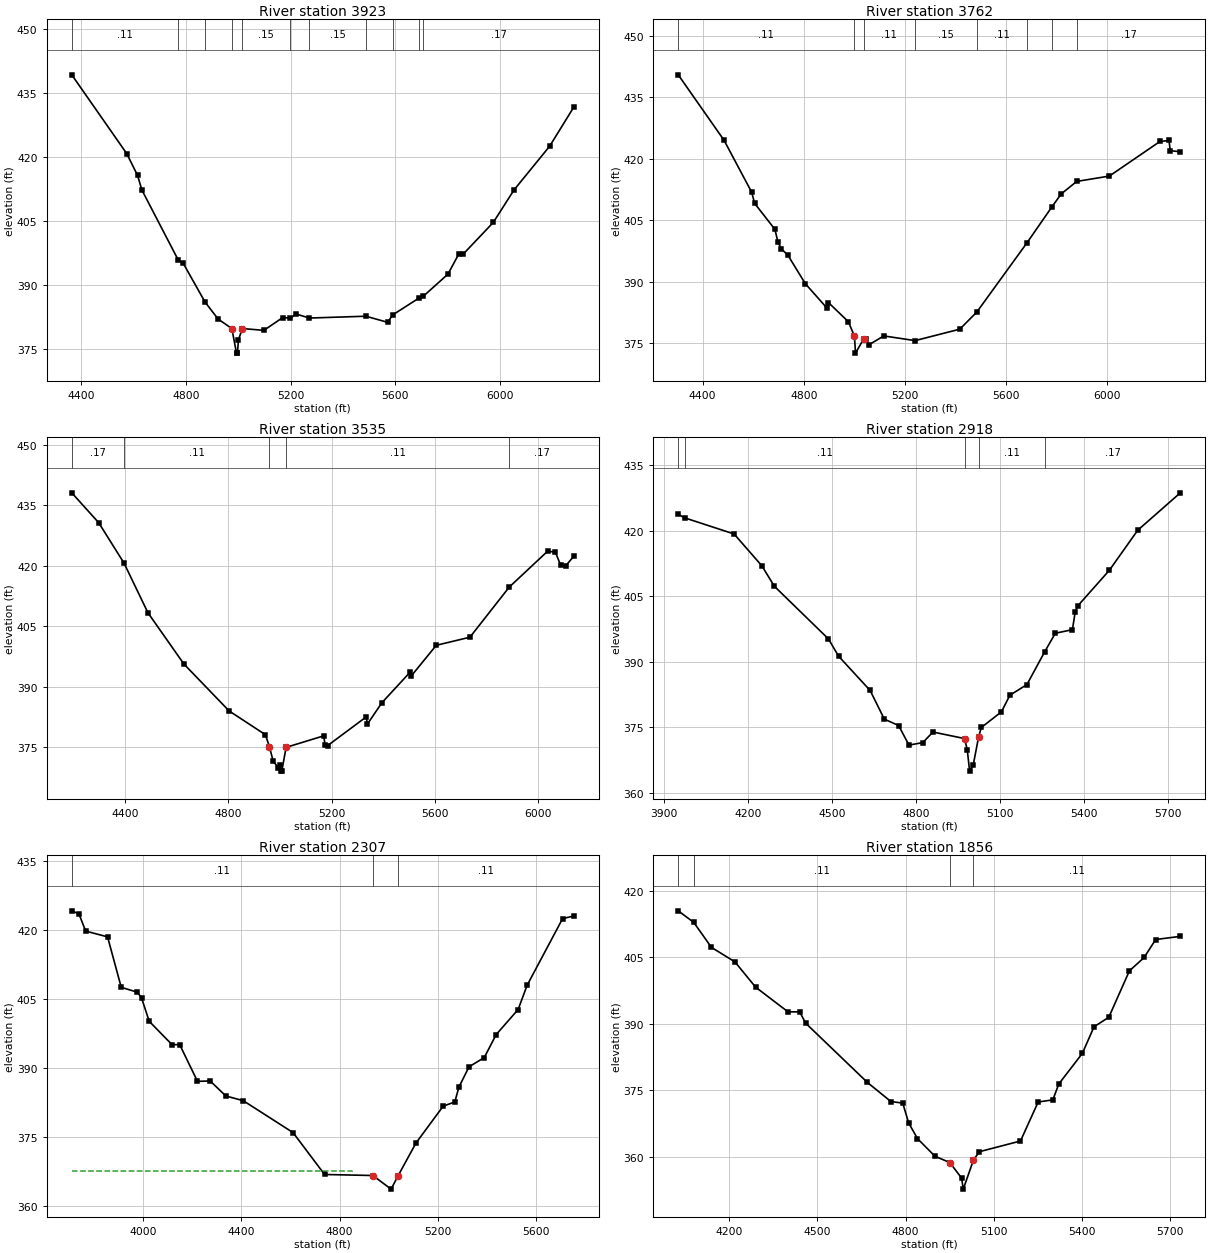
Type RM Length L Ch R = 1 ,3923    ,161,161,161
BEGIN DESCRIPTION:
Mapping XS 6ee8be37
END DESCRIPTION:
XS GIS Cut Line= 3
       3807312.5     10242904.47      3806691.67     10243050.15
      3805445.62     10243348.22
#Sta/Elev= 30
    4363  439.25  4573.2  420.76  4614.3  415.67  4631.2   412.2  4770.1  395.78
  4788.9  395.04  4872.5  385.93  4922.4  381.95  4974.8  379.73  4992.6  373.96
  4996.1  373.96  5000.1  377.08  5014.9  379.73  5097.2   379.3  5169.1   382.3
  5198.5  382.18  5220.5  383.13  5271.3  382.19    5487  382.62  5570.1  381.19
  5589.5  382.93  5691.9  386.95  5706.8  387.32  5800.7  392.49  5842.7  397.28
    5858  397.12    5974  404.62    6053  412.22  6189.5  422.51  6281.9   431.7
#Mann= 11 ,-1 , 0
    4363     .11       0  4770.1     .15       0  4872.5     .11       0
  4974.8     .09       0  5014.9     .15       0  5198.5     .17       0
  5271.3     .15       0    5487     .17       0  5589.5     .11       0
  5691.9     .15       0  5706.8     .17       0
Bank Sta=4974.8,5014.9
XS Rating Curve= 0 ,0
Exp/Cntr=0.3,0.1

Type RM Length L Ch R = 1 ,3762    ,227,227,227
BEGIN DESCRIPTION:
Mapping XS 183f5106
END DESCRIPTION:
XS GIS Cut Line= 5
      3807307.96     10242875.34      3806902.34     10242917.92
      3806613.71     10242914.99      3805332.99      10242843.9
       3805329.3     10242840.22
#Sta/Elev= 30
  4303.5  440.46  4484.6  424.51    4594  411.83  4605.3  409.15  4685.7   402.8
  4697.2  399.78  4711.1  398.02  4735.8  396.62  4805.8  389.57  4892.1  383.57
  4897.1  384.98  4975.9   380.3    5000  376.78  5004.1  372.65  5035.9  376.05
  5045.9  376.19  5055.9  374.64    5116  376.84  5239.7   375.7  5416.5  378.49
    5484  382.69  5681.3  399.48    5780  408.25  5817.1  411.44  5878.6  414.49
  6007.4  415.79  6207.7  424.23  6243.2  424.46  6248.2  421.98  6287.9  421.71
#Mann= 8 ,-1 , 0
  4303.5     .11       0    5000     .07       0  5035.9     .11       0
  5239.7     .15       0    5484     .11       0  5681.3     .15       0
    5780     .11       0  5878.6     .17       0
#XS Ineff= 2 , 0
       0                  5341.4       0     377
Permanent Ineff=
       F       F
Bank Sta=5000,5035.9
XS Rating Curve= 0 ,0
Exp/Cntr=0.3,0.1

Type RM Length L Ch R = 1 ,3535    ,617,617,617
BEGIN DESCRIPTION:
Conroe Lake 056 8.0
END DESCRIPTION:
XS GIS Cut Line= 4
      3807249.76     10242720.69      3806960.61     10242783.45
      3806452.12     10242756.21      3805316.44      10242688.5
#Sta/Elev= 30
  4194.9  438.12  4299.2  430.71  4397.6  420.64  4489.6  408.39  4628.7  395.69
    4804  384.04  4944.2  378.16 4959.53  375.21  4974.2  371.62  4994.3  369.96
  4999.6  370.76  5004.1  369.13  5007.6  369.13  5024.3  375.02    5170  377.88
    5175  375.57  5184.6  375.44  5334.1  382.56  5339.1  380.81    5395  386.09
  5503.3   393.6  5508.3   392.7  5605.3  400.32  5735.6  402.33  5887.9  414.76
  6036.1  423.64  6066.2  423.42  6086.2  420.25  6106.2  420.03  6137.7  422.41
#Mann= 5 ,-1 , 0
  4194.9     .17       0  4397.6     .11       0 4959.53     .07       0
  5024.3     .11       0  5887.9     .17       0
#XS Ineff= 2 , 0
       0                    5170       0  377.88
Permanent Ineff=
       F       F
Bank Sta=4959.53,5024.3
XS Rating Curve= 0 ,0
Exp/Cntr=0.3,0.1

Type RM Length L Ch R = 1 ,2918    ,611,611,611
BEGIN DESCRIPTION:
Conroe Lake 056 6.0
END DESCRIPTION:
XS GIS Cut Line= 3
       3807138.4     10242517.45      3806110.95     10242299.51
      3805377.99     10242428.92
#Sta/Elev= 30
  3949.7   423.8  3973.6  422.98  4149.4   419.3  4248.7     412  4293.2  407.33
  4486.7  395.26  4522.7  391.32  4635.7  383.45  4686.3  376.89  4737.4  375.43
  4774.4  370.94    4824  371.52  4860.1  373.94    4973  372.44  4982.7  369.93
  4991.2  364.98  5004.1  366.38  5023.5  372.87  5033.1  374.98  5104.7  378.55
  5135.2  382.37  5196.1  384.81  5259.8  392.35  5297.6  396.57  5358.6  397.38
  5368.7  401.48  5378.3  402.87  5490.6  410.98  5592.1  420.16  5744.3  428.73
#Mann= 5 ,-1 , 0
  3949.7     .17       0  3973.6     .11       0    4973     .07       0
  5023.5     .11       0  5259.8     .17       0
Bank Sta=4973,5023.5
XS Rating Curve= 0 ,0
Exp/Cntr=0.3,0.1

Type RM Length L Ch R = 1 ,2307    ,451,451,451
BEGIN DESCRIPTION:
Conroe Lake 056 5.0
END DESCRIPTION:
XS GIS Cut Line= 3
       3807302.5     10242033.08        3806055.     10241708.24
      3805323.38     10241533.09
#Sta/Elev= 30
  3710.9  424.09  3740.1  423.42  3767.4  419.69  3856.5  418.43    3912  407.47
    3978   406.4  3994.7  405.15  4025.7  400.09  4118.7     395  4149.7  395.02
    4222  387.04  4273.7  387.12  4337.4  383.86    4408  382.84  4610.7   375.9
  4738.7   366.8  4935.1  366.58  5009.2  363.62  5038.2  366.57  5110.2  373.62
  5221.1  381.65  5268.3  382.56    5285  385.79  5326.1   390.2  5387.8  392.19
  5436.5   397.2  5525.7  402.65  5562.6  407.94  5706.6   422.4  5752.3  422.97
#Mann= 3 , 0 , 0
  3710.9     .11       0  4935.1     .07       0  5038.2     .11       0
#XS Ineff= 2 , 0
       0  4848.5   367.6               0
Permanent Ineff=
       F       F
Bank Sta=4935.1,5038.2
XS Rating Curve= 0 ,0
Exp/Cntr=0.3,0.1

Type RM Length L Ch R = 1 ,1856    ,479,479,479
BEGIN DESCRIPTION:
Conroe Lake 056 4.0
END DESCRIPTION:
XS GIS Cut Line= 3
      3807130.58     10241342.97      3806158.27     10241290.96
      3805424.92     10241251.83
#Sta/Elev= 30
  4026.3  415.46  4079.2  412.85  4139.2  407.23  4219.3  403.96  4289.4  398.28
  4399.6  392.72  4439.6   392.7  4459.6  390.17  4669.9  376.81  4750.1   372.5
  4790.1  372.17  4810.1  367.71  4840.2  364.17  4899.8  360.19  4950.3  358.77
  4990.4  355.27    4996  352.79  5030.5   359.3  5050.5  361.21  5190.7  363.63
  5250.8  372.41  5300.8  372.89  5320.9  376.46    5401  383.35    5441  389.36
  5491.1  391.49  5561.2  401.94  5611.3  404.95  5650.6     409  5734.4  409.71
#Mann= 4 ,-1 , 0
  4026.3     .17       0  4079.2     .11       0  4950.3     .07       0
  5030.5     .11       0
Bank Sta=4950.3,5030.5
XS Rating Curve= 0 ,0
Exp/Cntr=0.3,0.1

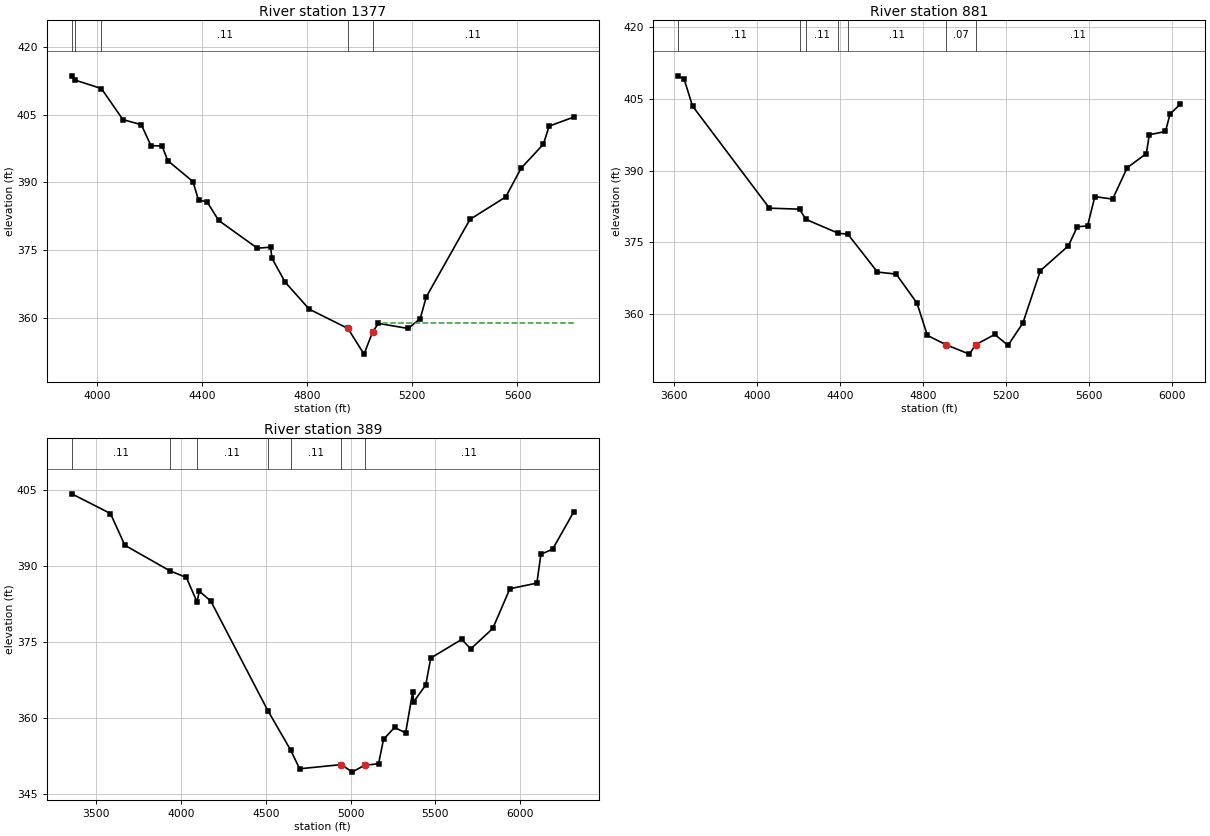
Type RM Length L Ch R = 1 ,1377    ,496,496,496
BEGIN DESCRIPTION:
Conroe Lake 056 3.0
END DESCRIPTION:
XS GIS Cut Line= 3
      3807190.55     10241207.57      3806162.22     10240829.88
      3805422.58     10241170.97
#Sta/Elev= 30
  3904.5  413.62  3916.5  412.69  4017.2   410.8  4099.1  403.92  4169.1   402.8
  4205.7  398.16  4248.3  398.07  4269.6  394.84  4365.5   390.2  4386.8  386.06
  4418.7  385.75  4463.3  381.59  4610.5  375.44  4660.7  375.67    4666  373.21
  4716.3  367.92  4807.8  361.94  4954.9  357.67  5016.3  351.98  5048.9  356.88
  5070.9  358.79  5184.2  357.66  5230.1  359.85  5253.1  364.65  5419.3  381.82
  5555.4   386.8  5613.9  393.16  5698.6  398.47  5720.6  402.48  5814.5  404.49
#Mann= 5 ,-1 , 0
  3904.5     .11       0  3916.5     .17       0  4017.2     .11       0
  4954.9     .07       0  5048.9     .11       0
#XS Ineff= 2 , 0
       0                  5086.9       0  358.91
Permanent Ineff=
       F       F
Bank Sta=4954.9,5048.9
XS Rating Curve= 0 ,0
Exp/Cntr=0.3,0.1

Type RM Length L Ch R = 1 ,881     ,492,492,492
BEGIN DESCRIPTION:
Conroe Lake 056 2.0
END DESCRIPTION:
XS GIS Cut Line= 3
      3807466.56      10240421.1      3806088.23     10240357.29
      3805413.02     10241146.32
#Sta/Elev= 30
  3620.2  409.82  3648.9  409.07    3689   403.5  4059.4  382.14  4204.3  381.93
  4235.4  379.79  4391.7  376.89  4437.2   376.7  4579.9  368.77    4670  368.35
  4770.1  362.28  4820.2  355.53  4910.3  353.57  5022.4  351.61  5052.7  353.58
  5144.9  355.72  5208.6  353.46    5280  358.09  5364.5  369.07  5499.5  374.26
  5542.3  378.26  5591.7  378.42  5626.8  384.55  5712.5  384.04  5782.7  390.59
  5874.9  393.57  5889.2   397.5  5967.1  398.18  5989.1  401.84  6038.5  403.89
#Mann= 7 ,-1 , 0
  3620.2     .11       0  4204.3    .125       0  4235.4     .11       0
  4391.7    .125       0  4437.2     .11       0  4910.3     .07       0
  5052.7     .11       0
#XS Ineff= 2 , 0
       0                  5144.9       0  355.72
Permanent Ineff=
       F       F
Bank Sta=4910.3,5052.7
XS Rating Curve= 0 ,0
Exp/Cntr=0.3,0.1

Type RM Length L Ch R = 1 ,389     ,0,0,0
BEGIN DESCRIPTION:
Conroe Lake 056 1.0
END DESCRIPTION:
XS GIS Cut Line= 3
      3807495.25      10240288.3      3805895.41     10239911.55
      3805388.58     10241126.47
#Sta/Elev= 30
  3356.4  404.22  3584.6  400.33  3669.3  394.07    3934  389.03  4031.8  387.71
  4094.9  382.87  4108.3  384.99  4175.6  383.07  4512.1  361.43  4647.6  353.58
  4699.6  349.93  4946.1  350.76  5009.4  349.27  5082.7  350.64    5165  350.91
  5194.5  355.74  5259.5   358.1  5324.5  357.02  5366.4   365.1  5371.8  363.15
  5443.3  366.47  5472.5  371.79  5655.5  375.48  5708.6   373.6  5838.5  377.64
  5939.2  385.48  6098.4  386.59  6122.2  392.29  6191.4   393.3  6316.4   400.7
#Mann= 7 ,-1 , 0
  3356.4     .11       0    3934    .125       0  4094.9     .11       0
  4512.1    .125       0  4647.6     .11       0  4946.1     .07       0
  5082.7     .11       0
Bank Sta=4946.1,5082.7
XS Rating Curve= 0 ,0
Exp/Cntr=0.3,0.1

Chan Stop Cuts=-1
Use User Specified Reach Order=0
Composite Channel Slope=5