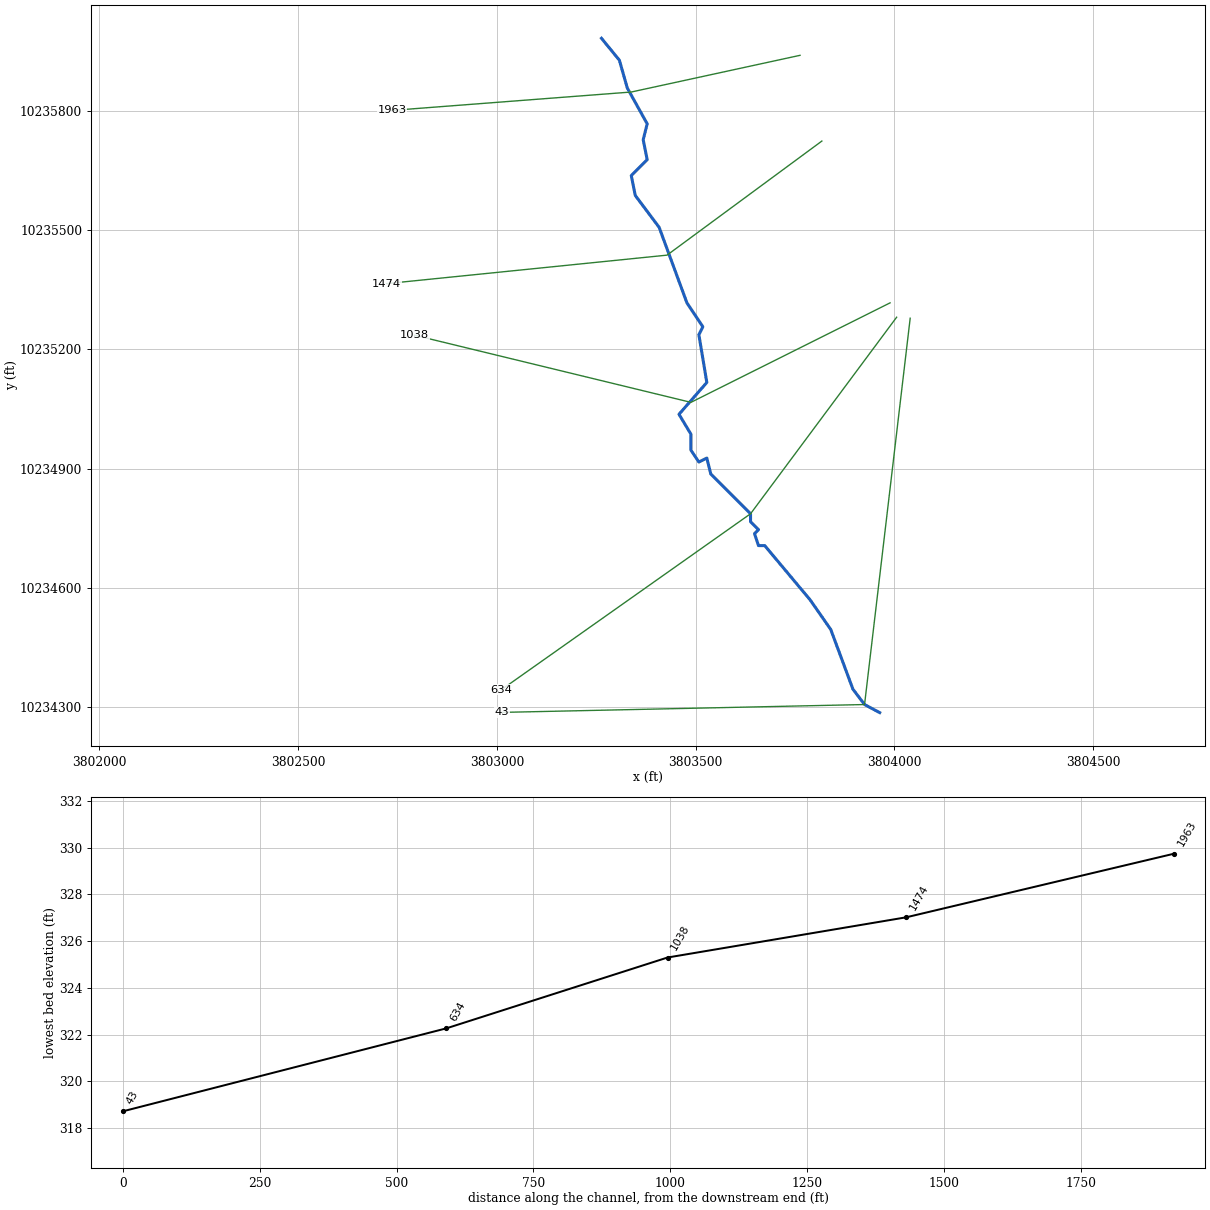
--- Conroe Lake 057.prj (project) ---

Proj Title=Conroe Lake 057 Base Level Engineering
Current Plan=p01
Default Exp/Contr=0.3,0.1
English Units
Geom File=g01
Flow File=f01
Flow File=f02
Plan File=p01
Y Axis Title=Elevation
X Axis Title(PF)=Main Channel Distance
X Axis Title(XS)=Station
BEGIN DESCRIPTION:
Conroe Lake 057
END DESCRIPTION:
DSS Export Rating Curves= 0
DSS Export Rating Curve Sorted= 0
DSS Export Volume Flow Curves= 0
DXF OffsetX= 0
DXF OffsetY= 0
DXF ScaleX= 1
DXF ScaleY= 10

--- Conroe Lake 057.p01 (plan) ---

Plan Title=Multiple Run
Short Identifier=Multiple
Geom File=g01
Flow File=f01
Subcritical Flow
K Sum by GR= 0
Std Step Tol= 0.01
Critical Tol= 0.01
Num of Std Step Trials= 20
Max Error Tol= 0.3
Flow Tol Ratio= 0.001
Split Flow NTrial= 30
Split Flow Tol= 0.02
Split Flow Ratio= 0.02
Log Output Level= 0
Friction Slope Method= 1
Unsteady Friction Slope Method= 2
Unsteady Bridges Friction Slope Method= 1
Parabolic Critical Depth
Global Vel Dist=  1 , 1 , 1
Global Log Level= 0
CheckData=True
Encroach Param= -1, 0, 0, 0
BEGIN DESCRIPTION:
Multiple Run
END DESCRIPTION:

--- Conroe Lake 057.f01 (steady flow) ---

Flow Title=Multiple
Program Version=4.10
Number of Profiles= 7
Profile Names=10-year,25-year,50-year,1pct_min,100-year,1pct_plu,500-year
River Rch & RM=Conroe Lake 057,Reach-1         ,1963
     583     785    1059     471    1422    4294    2644
River Rch & RM=Conroe Lake 057,Reach-1         ,43
    1934    2756    3854    1766    5333   16105   10571
Boundary for River Rch & Prof#=Conroe Lake 057,Reach-1         , 1
Up Type= 0
Dn Type= 3
Dn Slope=0.005
Boundary for River Rch & Prof#=Conroe Lake 057,Reach-1         , 2
Up Type= 0
Dn Type= 3
Dn Slope=0.005
Boundary for River Rch & Prof#=Conroe Lake 057,Reach-1         , 3
Up Type= 0
Dn Type= 3
Dn Slope=0.005
Boundary for River Rch & Prof#=Conroe Lake 057,Reach-1         , 4
Up Type= 0
Dn Type= 3
Dn Slope=0.005
Boundary for River Rch & Prof#=Conroe Lake 057,Reach-1         , 5
Up Type= 0
Dn Type= 3
Dn Slope=0.005
Boundary for River Rch & Prof#=Conroe Lake 057,Reach-1         , 6
Up Type= 0
Dn Type= 3
Dn Slope=0.005
Boundary for River Rch & Prof#=Conroe Lake 057,Reach-1         , 7
Up Type= 0
Dn Type= 3
Dn Slope=0.005
DSS Import GetInterval= 0
DSS Import GetPeak= 0
DSS Import FillOption= 0

--- Conroe Lake 057.f02 (steady flow) ---

Flow Title=Orig_BLE_Flow
Program Version=4.10
Number of Profiles= 7
Profile Names=10-year,25-year,50-year,1pct_min,100-year,1pct_plu,500-year
River Rch & RM=Conroe Lake 057,Reach-1         ,1963
     583     770     921     362    1094    3303    1537
River Rch & RM=Conroe Lake 057,Reach-1         ,43
    1934    2702    3351    1358    4102   12389    6146
Boundary for River Rch & Prof#=Conroe Lake 057,Reach-1         , 1
Up Type= 0
Dn Type= 3
Dn Slope=0.005
Boundary for River Rch & Prof#=Conroe Lake 057,Reach-1         , 2
Up Type= 0
Dn Type= 3
Dn Slope=0.005
Boundary for River Rch & Prof#=Conroe Lake 057,Reach-1         , 3
Up Type= 0
Dn Type= 3
Dn Slope=0.005
Boundary for River Rch & Prof#=Conroe Lake 057,Reach-1         , 4
Up Type= 0
Dn Type= 3
Dn Slope=0.005
Boundary for River Rch & Prof#=Conroe Lake 057,Reach-1         , 5
Up Type= 0
Dn Type= 3
Dn Slope=0.005
Boundary for River Rch & Prof#=Conroe Lake 057,Reach-1         , 6
Up Type= 0
Dn Type= 3
Dn Slope=0.005
Boundary for River Rch & Prof#=Conroe Lake 057,Reach-1         , 7
Up Type= 0
Dn Type= 3
Dn Slope=0.005
DSS Import GetInterval= 0
DSS Import GetPeak= 0
DSS Import FillOption= 0

--- Conroe Lake 057.g01 (geometry) ---

Geom Title=Existing Conditions
Program Version=4.10

River Reach=Conroe Lake 057 ,Reach-1
Reach XY= 30
      3803263.23     10235981.84      3803308.23     10235926.84
      3803328.23     10235856.84      3803378.23     10235766.84
      3803368.23     10235726.84      3803378.23     10235676.84
      3803338.23     10235636.84      3803348.23     10235586.84
      3803408.23     10235506.84      3803478.23     10235316.84
      3803518.23     10235256.84      3803508.23     10235236.84
      3803528.23     10235116.84      3803458.23     10235036.84
      3803488.23     10234986.84      3803488.23     10234946.84
      3803508.23     10234916.84      3803528.23     10234926.84
      3803538.23     10234886.84      3803638.23     10234786.84
      3803638.23     10234766.84      3803658.23     10234746.84
      3803648.23     10234736.84      3803658.23     10234706.84
      3803673.93     10234706.84      3803788.19     10234570.32
      3803839.99     10234495.95      3803895.77     10234345.87
      3803924.99     10234307.35      3803963.22       10234287.

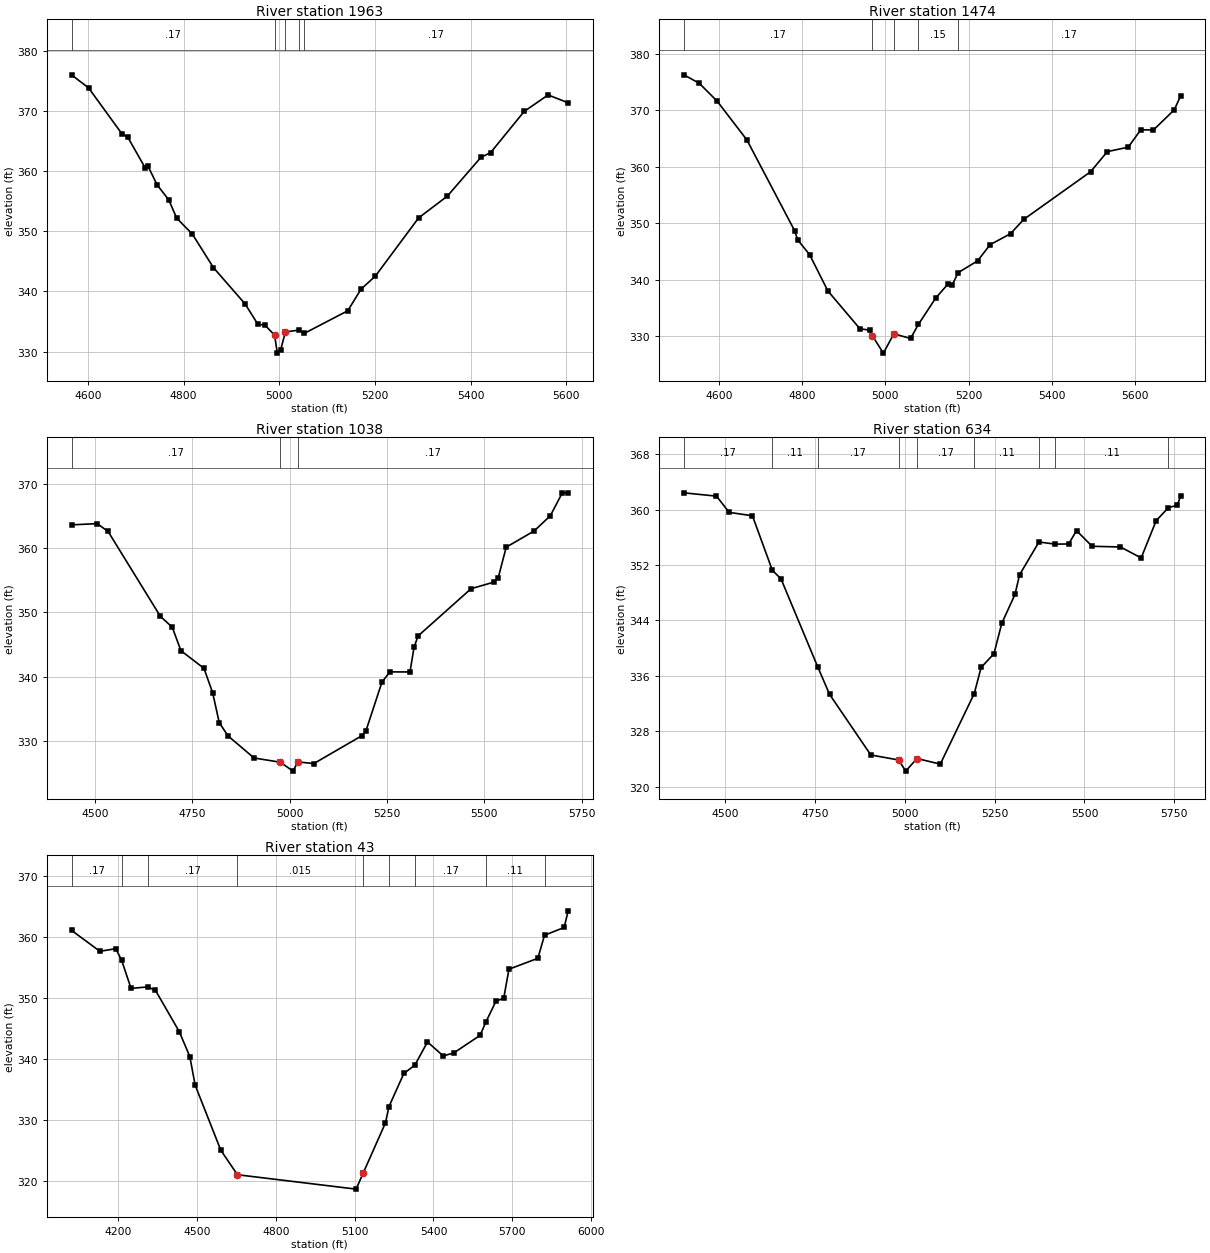
Type RM Length L Ch R = 1 ,1963    ,489,489,489
BEGIN DESCRIPTION:
Conroe Lake 057 4.0
END DESCRIPTION:
XS GIS Cut Line= 3
      3803762.73     10235939.07      3803338.23     10235846.84
      3802736.01     10235800.57
#Sta/Elev= 30
  4565.6  375.98  4601.3  373.81  4670.9  366.19  4683.2  365.63    4720  360.47
  4725.1  360.87  4744.6   357.7  4769.1  355.18  4785.5  352.17  4818.3  349.51
  4862.3  343.95  4928.8  337.89  4955.4  334.51  4969.7  334.41  4990.2  332.73
  4995.9  329.74  5002.7  330.24  5012.8  333.26  5040.5  333.56    5052  333.01
  5143.2  336.78  5170.9  340.37    5201  342.55  5291.2   352.2  5351.4  355.83
  5421.6  362.28  5441.7  363.04  5511.9  369.89    5562  372.64    5604  371.33
#Mann= 5 ,-1 , 0
  4565.6     .17       0  4990.2     .09       0  5012.8     .17       0
  5040.5     .15       0    5052     .17       0
Bank Sta=4990.2,5012.8
XS Rating Curve= 0 ,0
Exp/Cntr=0.3,0.1

Type RM Length L Ch R = 1 ,1474    ,436,436,436
BEGIN DESCRIPTION:
Conroe Lake 057 3.0
END DESCRIPTION:
XS GIS Cut Line= 3
      3803817.65     10235723.59      3803428.23     10235436.84
      3802722.85     10235365.27
#Sta/Elev= 30
  4516.4  376.29  4553.4  374.79  4596.7  371.59  4667.7  364.76  4782.6  348.65
  4789.4  347.08  4818.1  344.48    4862  338.04  4939.2  331.32  4962.3   331.1
  4968.5  330.14  4995.4  327.02  5020.5  330.44  5060.7  329.61  5079.4   332.1
    5121  336.77  5151.2  339.31  5161.2  339.15  5174.8  341.26  5221.5  343.35
  5251.7  346.22  5300.9  348.17  5332.1  350.68  5492.9  359.13  5533.1  362.69
  5583.4  363.49  5613.5  366.57  5643.7  366.51  5693.9   370.1    5709  372.55
#Mann= 5 ,-1 , 0
  4516.4     .17       0  4968.5     .09       0  5020.5     .17       0
  5079.4     .15       0  5174.8     .17       0
Bank Sta=4968.5,5020.5
XS Rating Curve= 0 ,0
Exp/Cntr=0.3,0.1

Type RM Length L Ch R = 1 ,1038    ,404,404,404
BEGIN DESCRIPTION:
Conroe Lake 057 2.0
END DESCRIPTION:
XS GIS Cut Line= 3
      3803989.19      10235316.9      3803488.23     10235066.84
      3802793.21     10235235.55
#Sta/Elev= 30
  4440.1  363.59  4506.1  363.78  4534.1  362.56  4668.3  349.36  4698.7  347.68
    4721  344.03  4780.2  341.28  4802.5  337.48  4819.3  332.86  4841.7  330.79
  4908.8  327.34  4975.9  326.69  5008.9   325.3    5021  326.74  5062.1  326.47
  5185.6  330.81  5195.9  331.55  5237.1  339.14  5257.6  340.73  5309.1  340.72
  5319.4  344.53  5329.7  346.31  5465.8  353.66  5525.2   354.7  5535.5  355.35
  5556.1  360.12  5627.8  362.64  5669.3     365  5700.1  368.57  5715.2  368.54
#Mann= 3 , 0 , 0
  4440.1     .17       0  4975.9     .06       0    5021     .17       0
Bank Sta=4975.9,5021
XS Rating Curve= 0 ,0
Exp/Cntr=0.3,0.1

Type RM Length L Ch R = 1 ,634     ,591,591,591
BEGIN DESCRIPTION:
Mapping XS 822042a2
END DESCRIPTION:
XS GIS Cut Line= 3
      3804005.65     10235280.77      3803638.23     10234786.84
      3803011.05     10234344.29
#Sta/Elev= 30
  4384.4  362.41  4475.2  361.93  4510.6  359.59  4575.3   359.1  4630.8  351.22
  4654.6  350.03  4756.9  337.33  4790.1  333.34  4904.9   324.6  4982.3  323.88
  5002.2  322.27  5033.5  324.09  5098.4  323.28    5193  333.46  5212.1  337.22
  5247.8   339.2  5269.7  343.59  5306.4  347.75  5319.2  350.59  5373.2  355.32
  5418.4  355.01  5455.9  355.03  5477.8  356.96  5521.2   354.7  5600.2   354.6
  5657.8  353.02  5699.7   358.4  5733.6  360.26  5758.8  360.63  5767.6  361.96
#Mann= 9 ,-1 , 0
  4384.4     .17       0  4630.8     .11       0  4756.9     .17       0
  4982.3     .09       0  5033.5     .17       0    5193     .11       0
  5373.2     .17       0  5418.4     .11       0  5733.6     .17       0
Bank Sta=4982.3,5033.5
XS Rating Curve= 0 ,0
Exp/Cntr=0.3,0.1

Type RM Length L Ch R = 1 ,43      ,0,0,0
BEGIN DESCRIPTION:
Conroe Lake 057 1.0
END DESCRIPTION:
XS GIS Cut Line= 3
      3804039.79     10235278.39      3803924.99     10234307.35
       3803012.5     10234287.63
#Sta/Elev= 30
  4022.2  361.14  4130.3  357.71  4190.7  358.13  4212.8  356.26  4248.9  351.62
  4312.1  351.87  4341.8   351.3  4432.4  344.54  4472.6  340.44  4492.8  335.77
  4590.4   325.1  4653.9  321.08  5105.4  318.72  5131.9   321.3  5217.2  329.58
  5230.6  332.26  5287.2  337.68  5329.2  339.05  5377.2  342.85  5437.2  340.55
  5477.3  341.05  5577.3  343.92  5599.4   346.1  5637.3   349.5  5667.3  350.02
  5687.3  354.77  5797.3  356.56  5822.6  360.34  5897.3  361.61  5912.7  364.34
#Mann= 9 ,-1 , 0
  4022.2     .17       0  4212.8     .11       0  4312.1     .17       0
  4653.9    .015       0  5131.9     .17       0  5230.6     .11       0
  5329.2     .17       0  5599.4     .11       0  5822.6     .17       0
Bank Sta=4653.9,5131.9
XS Rating Curve= 0 ,0
Exp/Cntr=0.3,0.1

Chan Stop Cuts=-1
Use User Specified Reach Order=0
Composite Channel Slope=5