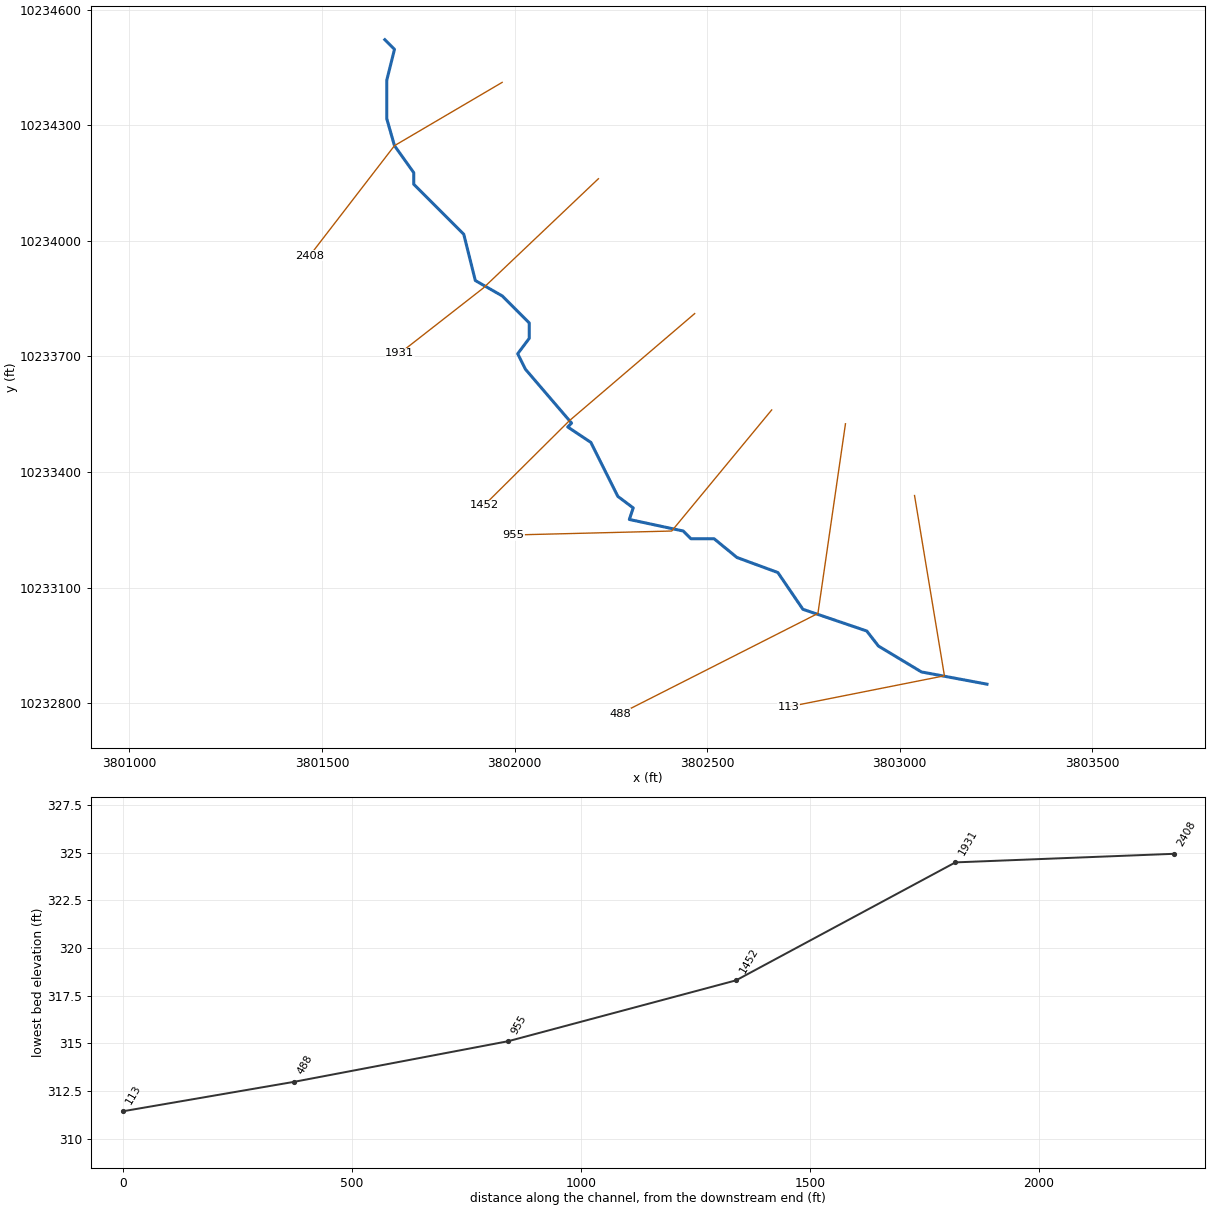
--- Conroe Lake 058.prj (project) ---

Proj Title=Conroe Lake 058 Base Level Engineering
Current Plan=p01
Default Exp/Contr=0.3,0.1
English Units
Geom File=g01
Flow File=f01
Flow File=f02
Plan File=p01
Y Axis Title=Elevation
X Axis Title(PF)=Main Channel Distance
X Axis Title(XS)=Station
BEGIN DESCRIPTION:
Conroe Lake 058
END DESCRIPTION:
DSS File=dss
DSS Export Rating Curves= 0
DSS Export Rating Curve Sorted= 0
DSS Export Volume Flow Curves= 0
DXF OffsetX= 0
DXF OffsetY= 0
DXF ScaleX= 1
DXF ScaleY= 10

--- Conroe Lake 058.p01 (plan) ---

Plan Title=Multiple Run
Program Version=4.10
Short Identifier=Multiple Run
Geom File=g01
Flow File=f01
Subcritical Flow
K Sum by GR= 0
Std Step Tol= 0.01
Critical Tol= 0.01
Num of Std Step Trials= 20
Max Error Tol= 0.3
Flow Tol Ratio= 0.001
Split Flow NTrial= 30
Split Flow Tol= 0.02
Split Flow Ratio= 0.02
Log Output Level= 0
Friction Slope Method= 1
Unsteady Friction Slope Method= 2
Unsteady Bridges Friction Slope Method= 1
Parabolic Critical Depth
Global Vel Dist= 1 , 1 , 1
Global Log Level= 0
CheckData=True
Encroach Param=-1 ,0,0, 0
BEGIN DESCRIPTION:
Multiple Run
END DESCRIPTION:
Computation Interval=1HOUR
Output Interval=1HOUR
Run HTab= 0
Run UNet= 0
Run PostProcess= 0
Run WQNet= 0
UNET Theta= 1
UNET Theta Warmup= 1
UNET ZTol= 0.02
UNET ZSATol= 0.05
UNET MxIter= 20
UNET MaxInSteps= 0
UNET DtIC= 0
UNET DtMin= 0
UNET MaxCRTS= 20
UNET WFStab= 2
UNET SFStab= 1
UNET WFX= 1
UNET SFX= 1
UNET DSS MLevel= 4
UNET DZMax Abort= 100
UNET Convert EG Bridges= 0
UNET Use Existing IB Tables=-1
UNET Froude Reduction=False
UNET Froude Limit= 1
UNET Froude Power= 10
UNET Time Slicing=0,0, 5
UNET Junction Losses=0
Instantaneous Interval=1HOUR
DSS File=dss
Write IC File= 0
Write IC File at Sim End=0
Echo Input=False
Echo Parameters=False
Echo Output=False
Write Detailed= 0
WQ AD Non Conservative
WQ ULTIMATE=-1
WQ Max Comp Step=1HOUR
WQ Output Interval=15MIN
WQ Output Selected Increments= 0
WQ Output face flow=0
WQ Output face velocity=0
WQ Output face area=0
WQ Output face dispersion=0
WQ Output cell volume=0
WQ Output cell surface area=0
WQ Output cell continuity=0
WQ Output cumulative cell continuity=0
WQ Output face conc=0
WQ Output face dconc_dx=0
WQ Output face courant=0
WQ Output face peclet=0
WQ Output face adv mass=0
WQ Output face disp mass=0
WQ Output cell mass=0
WQ Output cell source sink temp=0
WQ Output cell source sink nsm=0
WQ Output MaxMinRange=-1
WQ Daily Max Min Mean=-1
WQ Daily Range=0
WQ Daily Time=0
WQ Create Restart=0
WQ Fixed Restart=0
WQ System Summary=0
WQ Use Fixed Temperature=0
Sorting and Armoring Iterations= 10
XS Update Threshold= 0.02
Hydraulics Update Threshold= 0.02
Energy Slope Method= 1
Volume Change Method= 0
XS Weighting Method= 0
Number of US Weighted Cross Sections= 1
Number of DS Weighted Cross Sections= 1
Upstream XS Weight=0.25
Main XS Weight=0.5
Downstream XS Weight=0.25
Number of DS XS's Weighted with US Boundary= 1
Upstream Boundary Weight= 1
Weight of XSs Associated with US Boundary= 0
Number of US XS's Weighted with DS Boundary= 1
Downstream Boundary Weight= 0.5
Weight of XSs Associated with DS Boundary= 0.5
Sediment Output Level= 4
Mass or Volume Output= 0
Output Increment Type= 1
Profile and TS Output Increment= 10
XS Output Flag= 0
XS Output Increment= 10
Disregard all LS=0
Disregard all Conn=0
Disregard all Breaches=0
Disregard all Pumps=0

--- Conroe Lake 058.f01 (steady flow) ---

Flow Title=Multiple
Program Version=4.10
Number of Profiles= 7
Profile Names=10-year,25-year,50-year,1pct_min,100-year,1pct_plu,500-year
River Rch & RM=Conroe Lake 058,Reach-1         ,2408
     727     995    1354     607    1832    5533    3468
Boundary for River Rch & Prof#=Conroe Lake 058,Reach-1         , 1
Up Type= 0
Dn Type= 3
Dn Slope=0.005
Boundary for River Rch & Prof#=Conroe Lake 058,Reach-1         , 2
Up Type= 0
Dn Type= 3
Dn Slope=0.005
Boundary for River Rch & Prof#=Conroe Lake 058,Reach-1         , 3
Up Type= 0
Dn Type= 3
Dn Slope=0.005
Boundary for River Rch & Prof#=Conroe Lake 058,Reach-1         , 4
Up Type= 0
Dn Type= 3
Dn Slope=0.005
Boundary for River Rch & Prof#=Conroe Lake 058,Reach-1         , 5
Up Type= 0
Dn Type= 3
Dn Slope=0.005
Boundary for River Rch & Prof#=Conroe Lake 058,Reach-1         , 6
Up Type= 0
Dn Type= 3
Dn Slope=0.005
Boundary for River Rch & Prof#=Conroe Lake 058,Reach-1         , 7
Up Type= 0
Dn Type= 3
Dn Slope=0.005
DSS Import GetInterval= 0
DSS Import GetPeak= 0
DSS Import FillOption= 0

--- Conroe Lake 058.f02 (steady flow) ---

Flow Title=Orig_BLE_Flow
Program Version=4.10
Number of Profiles= 7
Profile Names=10-year,25-year,50-year,1pct_min,100-year,1pct_plu,500-year
River Rch & RM=Conroe Lake 058,Reach-1         ,2408
     727     975    1177     467    1409    4256    2016
Boundary for River Rch & Prof#=Conroe Lake 058,Reach-1         , 1
Up Type= 0
Dn Type= 3
Dn Slope=0.009
Boundary for River Rch & Prof#=Conroe Lake 058,Reach-1         , 2
Up Type= 0
Dn Type= 3
Dn Slope=0.009
Boundary for River Rch & Prof#=Conroe Lake 058,Reach-1         , 3
Up Type= 0
Dn Type= 3
Dn Slope=0.009
Boundary for River Rch & Prof#=Conroe Lake 058,Reach-1         , 4
Up Type= 0
Dn Type= 3
Dn Slope=0.009
Boundary for River Rch & Prof#=Conroe Lake 058,Reach-1         , 5
Up Type= 0
Dn Type= 3
Dn Slope=0.009
Boundary for River Rch & Prof#=Conroe Lake 058,Reach-1         , 6
Up Type= 0
Dn Type= 3
Dn Slope=0.009
Boundary for River Rch & Prof#=Conroe Lake 058,Reach-1         , 7
Up Type= 0
Dn Type= 3
Dn Slope=0.009
DSS Import GetInterval= 0
DSS Import GetPeak= 0
DSS Import FillOption= 0

--- Conroe Lake 058.g01 (geometry) ---

Geom Title=Existing Conditions
Program Version=4.10

River Reach=Conroe Lake 058 ,Reach-1
Reach XY= 30
      3801663.23     10234521.84      3801688.23     10234496.84
      3801668.23     10234416.84      3801668.23     10234316.84
      3801688.23     10234246.84      3801738.23     10234176.84
      3801738.23     10234146.84      3801868.23     10234016.84
      3801898.23     10233896.84      3801968.23     10233856.84
      3802038.23     10233786.84      3802038.23     10233746.84
      3802008.23     10233706.84      3802028.23     10233666.84
      3802148.23     10233526.84      3802138.23     10233516.84
      3802198.23     10233476.84      3802268.23     10233336.84
      3802308.23     10233306.84      3802298.23     10233276.84
      3802438.23     10233246.84      3802458.23     10233226.84
      3802518.23     10233226.84      3802577.64     10233178.17
      3802683.88     10233139.14      3802748.92     10233043.74
      3802914.79     10232987.37      3802945.14     10232948.34
       3803056.8     10232881.13      3803226.96     10232849.42

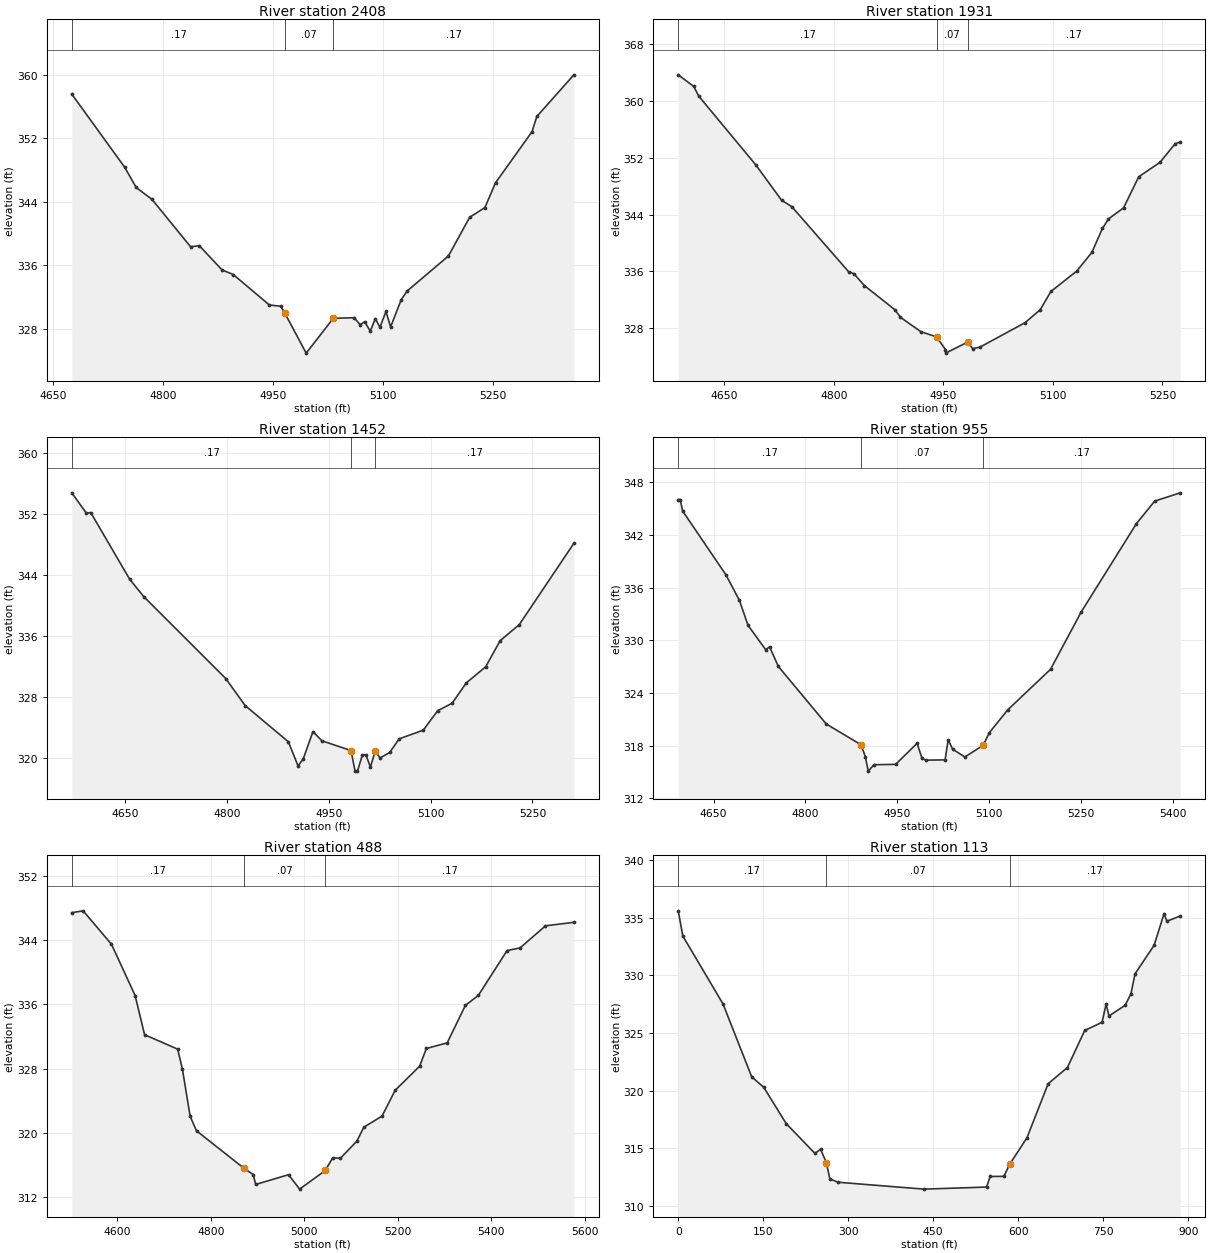
Type RM Length L Ch R = 1 ,2408    ,477,477,477
BEGIN DESCRIPTION:
Conroe Lake 058 5.0
END DESCRIPTION:
XS GIS Cut Line= 3
      3801967.87     10234411.08      3801688.23     10234246.84
      3801467.84     10233961.05
#Sta/Elev= 30
  4675.7  357.59    4748  348.36  4763.6  345.82  4785.1  344.33  4837.9  338.34
  4849.7  338.49  4880.9  335.42  4896.1  334.85  4945.3  331.01  4960.9  330.85
  4966.7  329.94  4995.6  324.94  5032.5  329.32    5061  329.41  5069.2  328.53
  5075.5  328.89  5083.1  327.71    5090  329.29  5096.3  328.19  5104.5   330.2
  5110.8  328.24  5125.3  331.67  5133.5  332.78  5189.7  337.18  5218.7  342.06
  5239.5  343.29    5254  346.41  5303.8  352.85  5310.4  354.77  5360.9  360.02
#Mann= 3 , 0 , 0
  4675.7     .17       0  4966.7     .07       0  5032.5     .17       0
Bank Sta=4966.7,5032.5
XS Rating Curve= 0 ,0
Exp/Cntr=0.3,0.1

Type RM Length L Ch R = 1 ,1931    ,479,479,479
BEGIN DESCRIPTION:
Conroe Lake 058 4.0
END DESCRIPTION:
XS GIS Cut Line= 3
      3802217.86     10234161.08      3801918.23     10233876.84
       3801701.9     10233708.04
#Sta/Elev= 30
    4587  363.67  4608.2  362.04  4615.1  360.67  4693.2  350.99  4728.4  346.03
  4742.6   345.1  4820.6  335.91  4827.5  335.68  4841.7  334.01  4884.1  330.56
    4891  329.55  4919.3   327.5  4940.7  326.78  4952.9  324.99  4953.2  324.49
  4983.2  326.04  4990.1  325.13    5000  325.33  5061.9  328.78  5082.7  330.61
  5097.2  333.17  5132.5  336.03  5153.3  338.67  5167.8  342.04  5175.9  343.37
  5196.7  344.94  5217.5  349.32  5246.5  351.34  5267.3  353.97  5274.4  354.21
#Mann= 3 , 0 , 0
    4587     .17       0  4940.7     .07       0  4983.2     .17       0
Bank Sta=4940.7,4983.2
XS Rating Curve= 0 ,0
Exp/Cntr=0.3,0.1

Type RM Length L Ch R = 1 ,1452    ,497,497,497
BEGIN DESCRIPTION:
Conroe Lake 058 3.0
END DESCRIPTION:
XS GIS Cut Line= 3
      3802467.85     10233811.07       3802142.2     10233532.88
      3801921.51     10233313.89
#Sta/Elev= 30
  4571.7  354.73  4593.1  352.08  4599.7  352.14  4656.8  343.44  4677.6  341.15
  4798.4  330.42  4826.9  326.89  4890.6  322.14  4904.9  318.97  4912.6  319.93
  4926.8  323.48    4940  322.27  4982.8  320.99  4988.8   318.3  4992.3   318.3
  4999.6  320.42  5004.8  320.42  5011.4  318.83  5018.5  320.93  5025.6  320.02
  5039.7  320.74  5053.8  322.53  5089.2  323.66  5110.4  326.21  5131.7  327.19
  5152.8  329.87  5181.1  331.96  5202.4  335.38  5230.6  337.48  5310.9  348.12
#Mann= 3 , 0 , 0
  4571.7     .17       0  4982.8     .07       0  5018.5     .17       0
Bank Sta=4982.8,5018.5
XS Rating Curve= 0 ,0
Exp/Cntr=0.3,0.1

Type RM Length L Ch R = 1 ,955     ,467,467,467
BEGIN DESCRIPTION:
Conroe Lake 058 2.0
END DESCRIPTION:
XS GIS Cut Line= 3
      3802667.85     10233561.07      3802408.23     10233246.84
      3801996.06     10233236.56
#Sta/Elev= 30
  4592.4  346.03  4595.6  346.03  4599.6  344.73  4670.2  337.47  4692.1  334.59
  4706.4  331.71  4735.1  328.95  4741.6  329.26  4755.9  327.03  4834.1  320.48
  4890.7  318.12  4897.9  316.77  4902.6  315.11  4912.2  315.84  4947.4  315.88
  4982.5  318.28  4990.4  316.57  4996.4  316.36  5028.2  316.39  5033.2  318.69
  5040.4  317.62  5060.4  316.72  5090.4  318.05  5100.4  319.49  5130.4  322.08
  5200.4  326.71  5250.5  333.24  5340.5  343.28  5370.5  345.86  5412.3   346.8
#Mann= 3 , 0 , 0
  4592.4     .17       0  4890.7     .07       0  5090.4     .17       0
Bank Sta=4890.7,5090.4
XS Rating Curve= 0 ,0
Exp/Cntr=0.3,0.1

Type RM Length L Ch R = 1 ,488     ,375,375,375
BEGIN DESCRIPTION:
Conroe Lake 058 1.0
END DESCRIPTION:
XS GIS Cut Line= 3
      3802859.46     10233525.13      3802787.95      10233032.9
      3802273.71      10232772.3
#Sta/Elev= 30
  4502.6  347.44  4526.9  347.67  4587.5  343.51  4638.1  337.11  4658.3  332.23
    4729  330.43  4739.1  327.99  4755.8  322.05  4769.4  320.25  4870.5   315.6
  4890.7   314.8    4896  313.56  4966.2  314.78    4990  312.98    5045  315.31
  5060.6  316.88  5077.2  316.83  5112.2  318.95  5127.4   320.7  5166.3  322.09
  5194.2  325.29  5246.7  328.31    5261  330.51  5305.6  331.21  5344.5  335.88
  5372.4  337.14  5433.6  342.71  5461.5  343.05  5515.8   345.8  5576.5  346.24
#Mann= 3 , 0 , 0
  4502.6     .17       0  4870.5     .07       0    5045     .17       0
Bank Sta=4870.5,5045
XS Rating Curve= 0 ,0
Exp/Cntr=0.3,0.1

Type RM Length L Ch R = 1 ,113     ,0,0,0
BEGIN DESCRIPTION:
Conroe Lake 058 0.5
END DESCRIPTION:
XS GIS Cut Line= 3
      3803038.86     10233339.02      3803116.49     10232871.18
      3802712.04     10232790.84
#Sta/Elev= 30
       0  335.62     8.1  333.43      79  327.53   129.7  321.19   150.8  320.29
   190.5  317.13   241.2  314.54   251.3  314.89   261.5  313.72   267.6  312.33
   281.7  312.03   433.8  311.43   544.2  311.61   550.6  312.53   574.8  312.54
     585  313.59   615.6   315.9   652.9  320.59   686.9     322   717.5  325.22
   748.1  325.93   755.2  327.52   760.3  326.48   788.9  327.41   799.1  328.42
   806.3  330.15   839.9  332.62   857.5  335.37   862.6  334.72   886.2  335.17
#Mann= 3 , 0 , 0
       0     .17       0   261.5     .07       0     585     .17       0
Bank Sta=261.5,585
XS Rating Curve= 0 ,0
Exp/Cntr=0.3,0.1

Chan Stop Cuts=-1
Use User Specified Reach Order=0
Composite Channel Slope=5