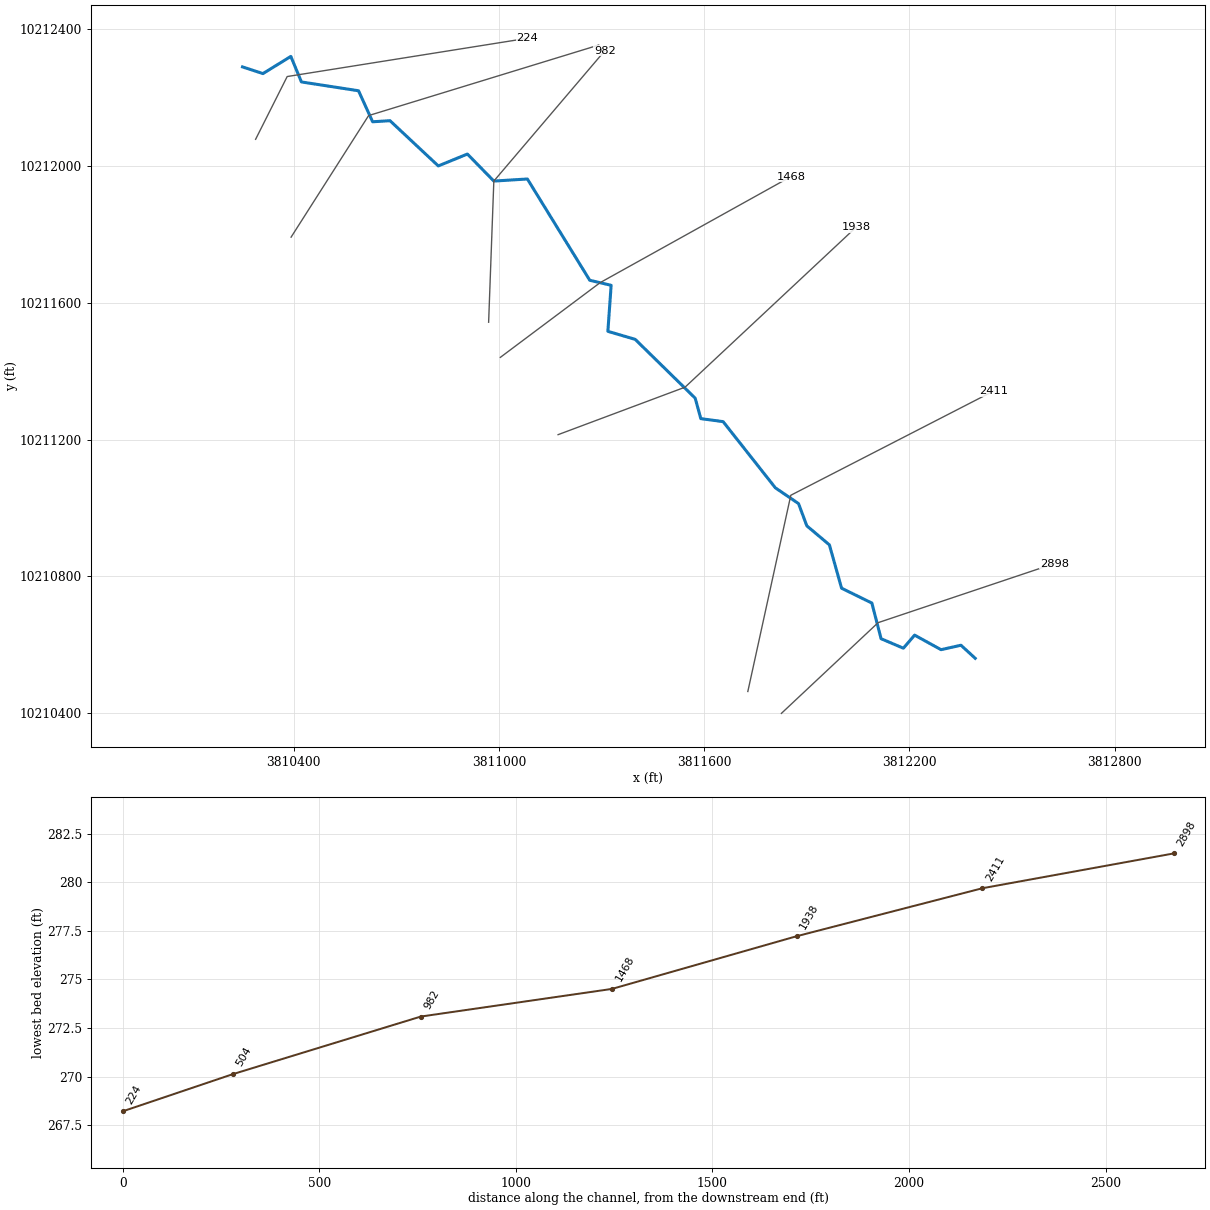
--- Conroe Lake 059.prj (project) ---

Proj Title=Conroe Lake 059 Base Level Engineering
Current Plan=p01
Default Exp/Contr=0.3,0.1
English Units
Geom File=g01
Flow File=f01
Flow File=f02
Plan File=p01
Y Axis Title=Elevation
X Axis Title(PF)=Main Channel Distance
X Axis Title(XS)=Station
BEGIN DESCRIPTION:
Conroe Lake 059
END DESCRIPTION:
DSS Export Rating Curves= 0
DSS Export Rating Curve Sorted= 0
DSS Export Volume Flow Curves= 0
DXF OffsetX= 0
DXF OffsetY= 0
DXF ScaleX= 1
DXF ScaleY= 10

--- Conroe Lake 059.p01 (plan) ---

Plan Title=Multiple Run
Short Identifier=Multiple
Geom File=g01
Flow File=f01
Subcritical Flow
K Sum by GR= 0
Std Step Tol= 0.01
Critical Tol= 0.01
Num of Std Step Trials= 20
Max Error Tol= 0.3
Flow Tol Ratio= 0.001
Split Flow NTrial= 30
Split Flow Tol= 0.02
Split Flow Ratio= 0.02
Log Output Level= 0
Friction Slope Method= 1
Unsteady Friction Slope Method= 2
Unsteady Bridges Friction Slope Method= 1
Parabolic Critical Depth
Global Vel Dist=  1 , 1 , 1
Global Log Level= 0
CheckData=True
Encroach Param= -1, 0, 0, 0
BEGIN DESCRIPTION:
Multiple Run
END DESCRIPTION:

--- Conroe Lake 059.f01 (steady flow) ---

Flow Title=Multiple
Program Version=4.10
Number of Profiles= 7
Profile Names=10-year,25-year,50-year,1pct_min,100-year,1pct_plu,500-year
River Rch & RM=Conroe Lake 059,Reach-1         ,2898
     470     620     825     361    1089    3289    1966
Boundary for River Rch & Prof#=Conroe Lake 059,Reach-1         , 1
Up Type= 0
Dn Type= 3
Dn Slope=0.006
Boundary for River Rch & Prof#=Conroe Lake 059,Reach-1         , 2
Up Type= 0
Dn Type= 3
Dn Slope=0.006
Boundary for River Rch & Prof#=Conroe Lake 059,Reach-1         , 3
Up Type= 0
Dn Type= 3
Dn Slope=0.006
Boundary for River Rch & Prof#=Conroe Lake 059,Reach-1         , 4
Up Type= 0
Dn Type= 3
Dn Slope=0.006
Boundary for River Rch & Prof#=Conroe Lake 059,Reach-1         , 5
Up Type= 0
Dn Type= 3
Dn Slope=0.006
Boundary for River Rch & Prof#=Conroe Lake 059,Reach-1         , 6
Up Type= 0
Dn Type= 3
Dn Slope=0.006
Boundary for River Rch & Prof#=Conroe Lake 059,Reach-1         , 7
Up Type= 0
Dn Type= 3
Dn Slope=0.006
DSS Import GetInterval= 0
DSS Import GetPeak= 0
DSS Import FillOption= 0

--- Conroe Lake 059.f02 (steady flow) ---

Flow Title=Orig_BLE_Flow
Program Version=4.10
Number of Profiles= 7
Profile Names=10-year,25-year,50-year,1pct_min,100-year,1pct_plu,500-year
River Rch & RM=Conroe Lake 059,Reach-1         ,2898
     470     608     717     278     838    2531    1143
Boundary for River Rch & Prof#=Conroe Lake 059,Reach-1         , 1
Up Type= 0
Dn Type= 3
Dn Slope=0.005
Boundary for River Rch & Prof#=Conroe Lake 059,Reach-1         , 2
Up Type= 0
Dn Type= 3
Dn Slope=0.005
Boundary for River Rch & Prof#=Conroe Lake 059,Reach-1         , 3
Up Type= 0
Dn Type= 3
Dn Slope=0.005
Boundary for River Rch & Prof#=Conroe Lake 059,Reach-1         , 4
Up Type= 0
Dn Type= 3
Dn Slope=0.005
Boundary for River Rch & Prof#=Conroe Lake 059,Reach-1         , 5
Up Type= 0
Dn Type= 3
Dn Slope=0.005
Boundary for River Rch & Prof#=Conroe Lake 059,Reach-1         , 6
Up Type= 0
Dn Type= 3
Dn Slope=0.005
Boundary for River Rch & Prof#=Conroe Lake 059,Reach-1         , 7
Up Type= 0
Dn Type= 3
Dn Slope=0.005
DSS Import GetInterval= 0
DSS Import GetPeak= 0
DSS Import FillOption= 0

--- Conroe Lake 059.g01 (geometry) ---

Geom Title=Existing Conditions
Program Version=4.10

River Reach=Conroe Lake 059 ,Reach-1
Reach XY= 30
      3812392.48     10210560.58      3812350.82     10210598.77
      3812292.66     10210585.75       3812215.4     10210628.29
      3812182.42     10210590.09      3812117.31     10210617.87
       3812090.4     10210722.04      3812001.86     10210765.44
      3811966.27     10210892.18       3811900.3     10210947.73
      3811875.99     10211012.83      3811808.28     10211058.84
      3811655.51     10211252.42       3811590.4      10211261.1
      3811573.91     10211320.99      3811398.56     10211492.87
       3811318.7     10211516.31      3811328.25     10211650.86
      3811265.75     10211665.61      3811083.46     10211961.62
      3810985.37     10211955.54      3810908.11     10212034.54
      3810823.04     10211999.81      3810681.81     10212132.02
      3810631.11     10212128.89      3810589.79     10212219.52
      3810422.96     10212245.29      3810391.99     10212319.89
      3810310.49     10212269.74       3810250.7     10212289.28

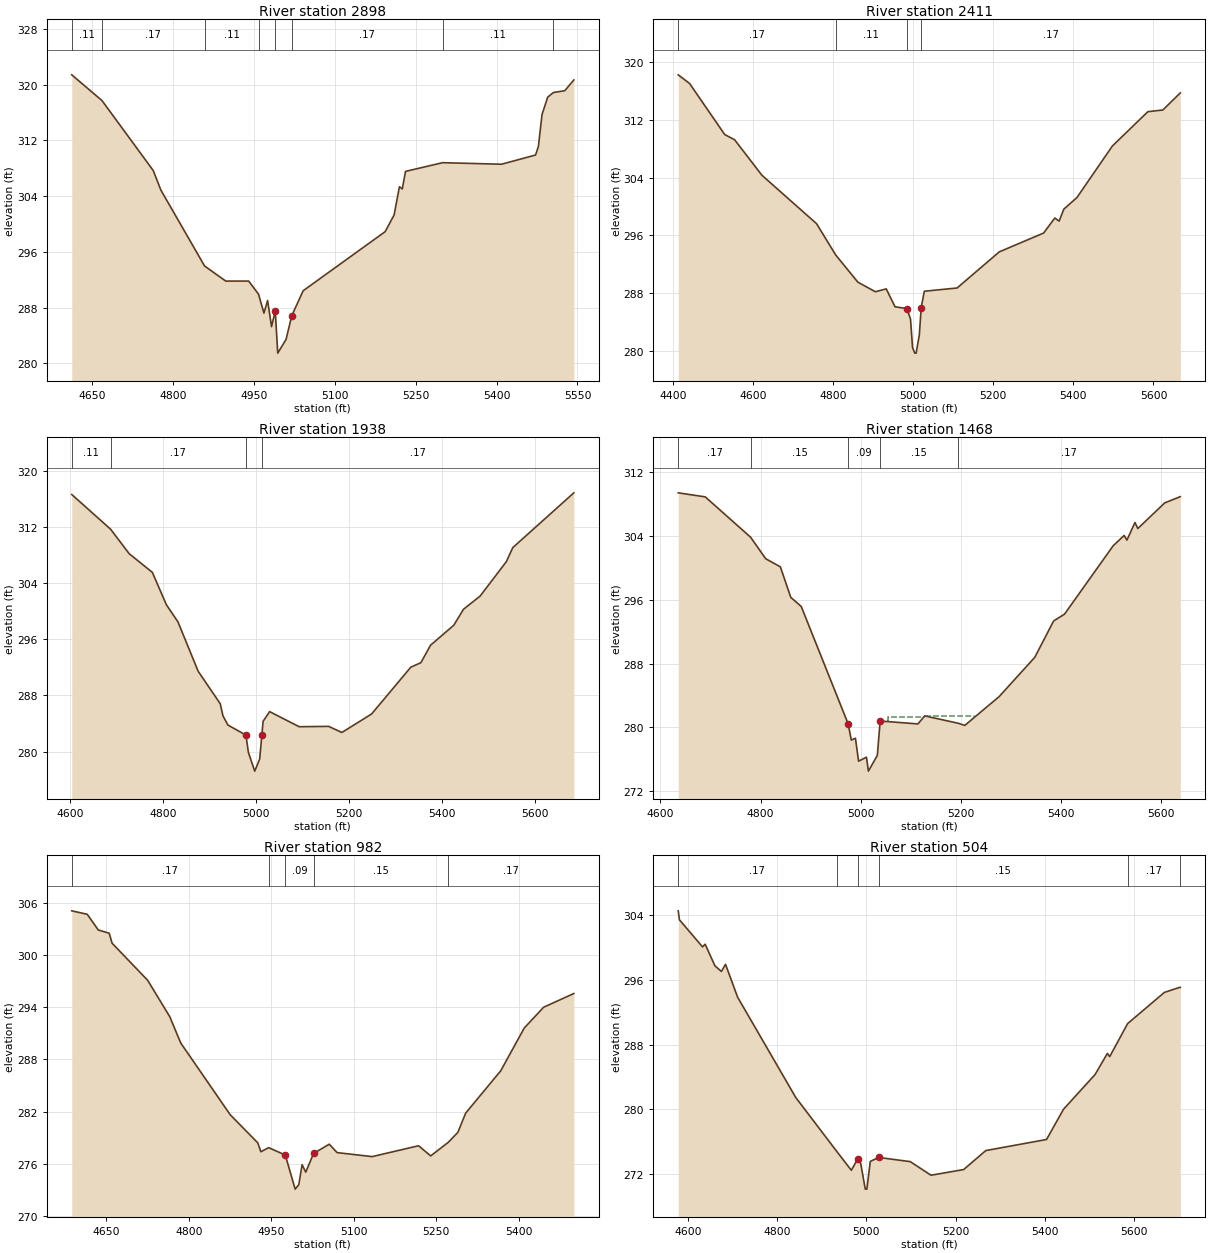
Type RM Length L Ch R = 1 ,2898    ,487,487,487
BEGIN DESCRIPTION:
Conroe Lake 059 6.0
END DESCRIPTION:
XS GIS Cut Line= 3
      3811825.93     10210399.58      3812108.63     10210664.74
      3812623.75     10210837.44
#Sta/Elev= 30
  4612.4  321.42  4668.5  317.72  4763.5  307.68  4777.7  304.87  4858.6  293.99
  4897.9  291.82  4940.4  291.82  4958.7  289.94  4968.7  287.22  4975.5  289.03
  4982.8  285.28  4989.7  287.55  4994.3  281.48  5009.7  283.44  5020.3  286.85
  5041.4  290.43  5193.6  298.92  5210.1  301.32  5219.9  305.36  5225.2  305.04
  5231.2  307.56  5299.9  308.81  5409.2  308.59  5472.3  309.91  5477.6  311.14
  5484.3  315.72  5494.9  318.23  5505.5  318.88  5526.5  319.14  5543.3  320.68
#Mann= 8 ,-1 , 0
  4612.4     .11       0  4668.5     .17       0  4858.6     .11       0
  4958.7     .17       0  4989.7     .09       0  5020.3     .17       0
  5299.9     .11       0  5505.5     .17       0
Bank Sta=4989.7,5020.3
XS Rating Curve= 0 ,0
Exp/Cntr=0.3,0.1

Type RM Length L Ch R = 1 ,2411    ,473,473,473
BEGIN DESCRIPTION:
Conroe Lake 059 5.0
END DESCRIPTION:
XS GIS Cut Line= 3
      3811727.82     10210463.53      3811853.42     10211037.14
      3812446.63     10211342.08
#Sta/Elev= 30
  4412.8  318.23  4441.2  317.03  4528.9  309.96  4553.6  309.24  4621.7  304.33
  4758.3  297.62  4806.2  293.28  4861.5  289.52  4905.3  288.19  4932.4  288.59
  4954.3  286.11  4983.6  285.86    4993  284.43  4998.1  280.47  5003.6  279.69
  5007.1  279.69  5015.1  282.23 5019.76     286  5027.5  288.26  5109.4  288.71
  5214.7  293.71  5325.6  296.32  5353.5   298.4  5364.3  297.97    5376  299.63
  5408.7  301.23  5497.4  308.38  5586.1  313.13  5623.4  313.36    5667  315.73
#Mann= 4 ,-1 , 0
  4412.8     .17       0  4806.2     .11       0  4983.6     .07       0
 5019.76     .17       0
Bank Sta=4983.6,5019.76
XS Rating Curve= 0 ,0
Exp/Cntr=0.3,0.1

Type RM Length L Ch R = 1 ,1938    ,470,470,470
BEGIN DESCRIPTION:
Conroe Lake 059 4.0
END DESCRIPTION:
XS GIS Cut Line= 3
      3811173.21     10211214.29      3811544.39     10211353.11
      3812043.95     10211820.34
#Sta/Elev= 30
  4603.7  316.59  4687.3  311.65  4727.2  308.17  4777.1  305.51  4807.4  300.89
  4832.3  298.45  4875.6  291.44  4923.2  286.81    4929  285.09  4939.6  283.78
  4978.4  282.35  4983.8  279.87  4997.4  277.22    5008  278.94 5012.69  282.33
  5015.3   284.3  5029.4  285.69    5093  283.54  5156.5  283.59  5184.8  282.72
  5248.8  285.35  5333.3  292.02  5354.8  292.65  5375.8  295.15  5425.6  297.98
  5446.6  300.26  5482.3  302.13  5538.7  307.03  5552.6  309.03    5684  316.83
#Mann= 4 ,-1 , 0
  4603.7     .11       0  4687.3     .17       0  4978.4     .09       0
 5012.69     .17       0
#XS Ineff= 2 , 0
       0                  5029.4       0  285.69
Permanent Ineff=
       F       F
Bank Sta=4978.4,5012.69
XS Rating Curve= 0 ,0
Exp/Cntr=0.3,0.1

Type RM Length L Ch R = 1 ,1468    ,486,486,486
BEGIN DESCRIPTION:
Conroe Lake 059 3.0
END DESCRIPTION:
XS GIS Cut Line= 3
      3811004.35     10211440.21      3811296.13     10211658.67
       3811854.2      10211968.9
#Sta/Elev= 30
  4635.5  309.42  4689.5  308.91  4780.1  303.85  4810.3  301.15  4839.5  300.14
  4860.3  296.31  4881.2  295.17    4975  280.43  4981.2  278.41  4989.5  278.63
  4995.8  275.76  5011.5  276.26  5015.4  274.51  5033.2  276.48  5038.9   280.8
  5114.4  280.43  5127.8  281.44  5195.1  280.51  5207.9  280.24  5276.6  283.86
  5347.7  288.78  5385.5  293.35  5407.2   294.2  5504.4  302.78  5526.2  304.07
  5531.9  303.49  5547.9   305.7  5553.6  304.94  5607.4  308.16  5638.5  308.94
#Mann= 5 ,-1 , 0
  4635.5     .17       0  4780.1     .15       0    4975     .09       0
  5038.9     .15       0  5195.1     .17       0
#XS Ineff= 2 ,-1
  5054.9  5127.8  281.36  5127.8 5225.83  281.44
Permanent Ineff=
       F       F
Bank Sta=4975,5038.9
XS Rating Curve= 0 ,0
Exp/Cntr=0.3,0.1

Type RM Length L Ch R = 1 ,982     ,478,478,478
BEGIN DESCRIPTION:
Conroe Lake 059 2.0
END DESCRIPTION:
XS GIS Cut Line= 3
      3810970.14     10211542.92      3810985.37     10211955.54
      3811309.73     10212336.58
#Sta/Elev= 30
  4587.1   305.1  4615.3   304.7  4635.3   302.9  4655.3  302.52  4660.4  301.38
  4725.3   297.1  4765.4  292.92  4785.4  289.89  4875.4  281.64  4925.5  278.41
  4931.1  277.39  4945.3  277.86  4975.5  277.01  4993.5  273.09    5000  273.59
  5006.1   275.9  5012.7  275.04    5027  277.19  5055.5  278.26  5069.8  277.29
  5133.5  276.83    5218  278.08    5240  276.91  5272.1  278.48  5289.4  279.62
  5303.7  281.84  5367.4   286.7  5410.2  291.62  5445.4  294.01  5500.4  295.59
#Mann= 5 ,-1 , 0
  4587.1     .17       0  4945.3     .15       0  4975.5     .09       0
    5027     .15       0  5272.1     .17       0
#XS Ineff= 2 , 0
       0                  5055.5       0  278.26
Permanent Ineff=
       F       T
Bank Sta=4975.5,5027
XS Rating Curve= 0 ,0
Exp/Cntr=0.3,0.1

Type RM Length L Ch R = 1 ,504     ,280,280,280
BEGIN DESCRIPTION:
Conroe Lake 059 1.0
END DESCRIPTION:
XS GIS Cut Line= 3
      3810392.74     10211791.64      3810619.31     10212146.95
      3811291.93     10212353.09
#Sta/Elev= 30
  4578.6  304.56  4581.3  303.45    4633   300.1  4638.9  300.43  4660.9  297.75
  4675.3  297.06  4684.6  297.94  4711.7  293.87    4842  281.46  4933.2  274.84
  4966.4  272.46  4981.2  273.91  4987.5   273.3  4997.7  270.13  5001.2  270.13
  5008.9  273.56  5027.9  274.05  5098.6  273.53  5144.9  271.85  5218.1  272.55
  5267.6   274.9  5403.8  276.27  5441.8  280.01  5512.6  284.31  5540.1  286.92
  5545.3  286.52  5585.5  290.61  5667.9  294.47  5702.1  295.09  5703.5  295.09
#Mann= 6 ,-1 , 0
  4578.6     .17       0  4933.2     .15       0  4981.2     .09       0
  5027.9     .15       0  5585.5     .17       0  5702.1     .15       0
#XS Ineff= 2 , 0
       0                  5267.6       0   274.9
Permanent Ineff=
       F       F
Bank Sta=4981.2,5027.9
XS Rating Curve= 0 ,0
Exp/Cntr=0.3,0.1

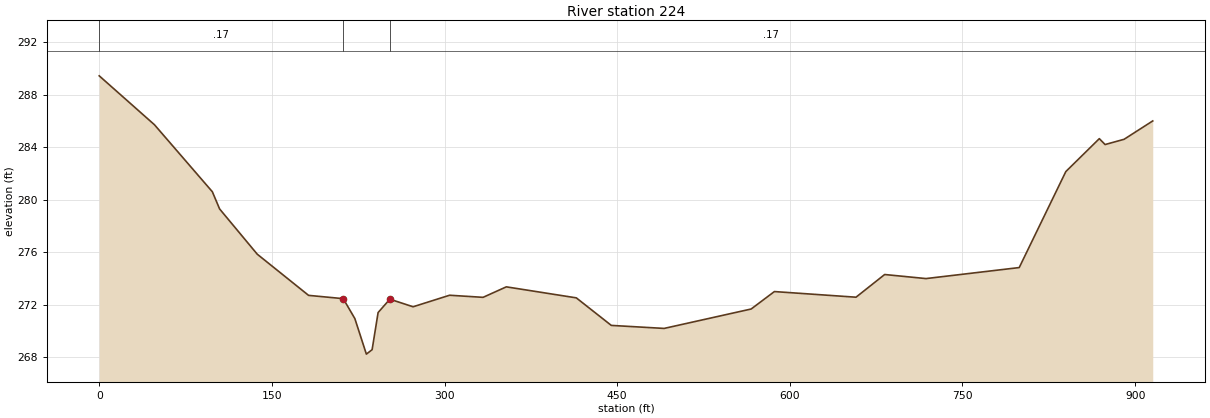
Type RM Length L Ch R = 1 ,224     ,0,0,0
BEGIN DESCRIPTION:
Conroe Lake 059 0.5
END DESCRIPTION:
XS GIS Cut Line= 3
      3810289.01     10212077.65      3810381.34      10212261.1
      3811082.41     10212372.78
#Sta/Elev= 30
       0  289.44      48  285.71    98.3   280.6   104.6  279.29   137.3  275.84
   181.9   272.7     212  272.45   222.1  270.93   232.1  268.22   237.1  268.56
   242.3  271.39   252.5  272.41   272.7  271.83   304.4  272.71   333.5  272.55
   353.7  273.35   414.5  272.51   444.9  270.41   490.8  270.18   566.4  271.66
   586.6  272.99   657.5  272.56   682.4  274.29   718.3  273.98   799.3  274.82
   839.8  282.14   868.9  284.65   873.9   284.2   890.4   284.6   915.3     286
#Mann= 3 , 0 , 0
       0     .17       0     212     .09       0   252.5     .17       0
Bank Sta=212,252.5
XS Rating Curve= 0 ,0
Exp/Cntr=0.3,0.1

Chan Stop Cuts=-1
Use User Specified Reach Order=0
Composite Channel Slope=5