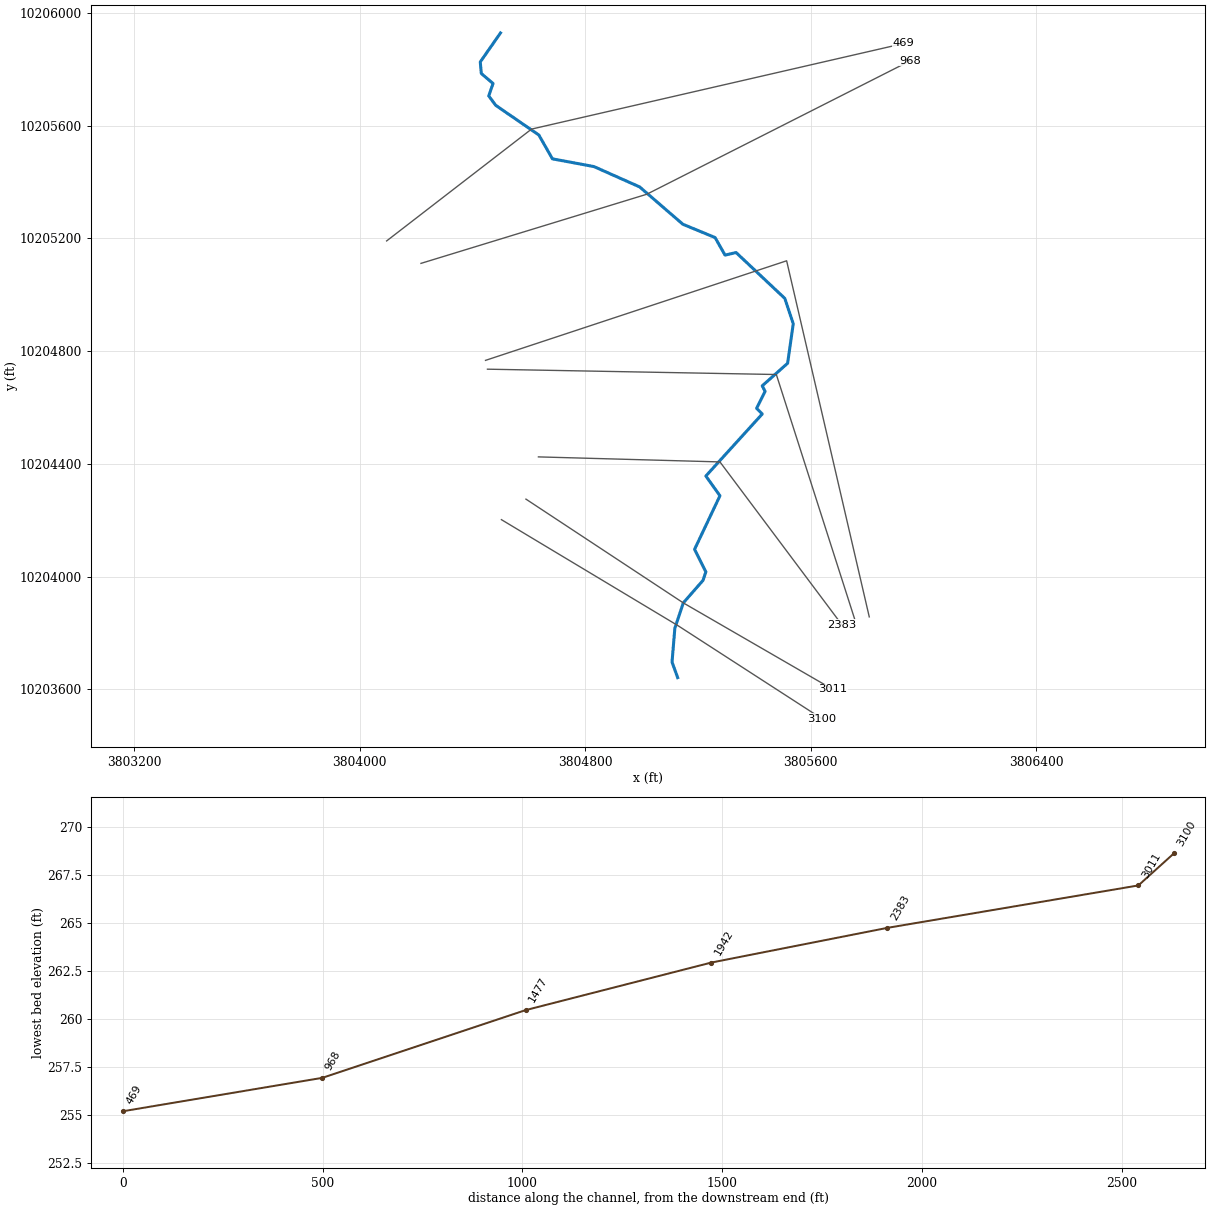
--- Conroe Lake 061.prj (project) ---

Proj Title=Conroe Lake 061 Base Level Engineering
Current Plan=p01
Default Exp/Contr=0.3,0.1
English Units
Geom File=g01
Flow File=f01
Flow File=f02
Plan File=p01
Y Axis Title=Elevation
X Axis Title(PF)=Main Channel Distance
X Axis Title(XS)=Station
BEGIN DESCRIPTION:
Conroe Lake 061
END DESCRIPTION:
DSS Export Rating Curves= 0
DSS Export Rating Curve Sorted= 0
DSS Export Volume Flow Curves= 0
DXF OffsetX= 0
DXF OffsetY= 0
DXF ScaleX= 1
DXF ScaleY= 10

--- Conroe Lake 061.p01 (plan) ---

Plan Title=Multiple Run
Short Identifier=Multiple
Geom File=g01
Flow File=f01
Subcritical Flow
K Sum by GR= 0
Std Step Tol= 0.01
Critical Tol= 0.01
Num of Std Step Trials= 20
Max Error Tol= 0.3
Flow Tol Ratio= 0.001
Split Flow NTrial= 30
Split Flow Tol= 0.02
Split Flow Ratio= 0.02
Log Output Level= 0
Friction Slope Method= 1
Unsteady Friction Slope Method= 2
Unsteady Bridges Friction Slope Method= 1
Parabolic Critical Depth
Global Vel Dist=  1 , 1 , 1
Global Log Level= 0
CheckData=True
Encroach Param= -1, 0, 0, 0
BEGIN DESCRIPTION:
Multiple Run
END DESCRIPTION:

--- Conroe Lake 061.f01 (steady flow) ---

Flow Title=Multiple
Program Version=4.10
Number of Profiles= 7
Profile Names=10-year,25-year,50-year,1pct_min,100-year,1pct_plu,500-year
River Rch & RM=Conroe Lake 061,Reach-1         ,3100
     815    1117    1521     682    2061    6224    3903
River Rch & RM=Conroe Lake 061,Reach-1         ,1477
     798    1089    1480     662    1998    6034    3762
River Rch & RM=Conroe Lake 061,Reach-1         ,968
    2179    3101    4330    1980    5980   18059   11803
River Rch & RM=Conroe Lake 061,Reach-1         ,469
    2179    3101    4330    1980    5980   18059   11803
Boundary for River Rch & Prof#=Conroe Lake 061,Reach-1         , 1
Up Type= 0
Dn Type= 3
Dn Slope=0.005
Boundary for River Rch & Prof#=Conroe Lake 061,Reach-1         , 2
Up Type= 0
Dn Type= 3
Dn Slope=0.005
Boundary for River Rch & Prof#=Conroe Lake 061,Reach-1         , 3
Up Type= 0
Dn Type= 3
Dn Slope=0.005
Boundary for River Rch & Prof#=Conroe Lake 061,Reach-1         , 4
Up Type= 0
Dn Type= 3
Dn Slope=0.005
Boundary for River Rch & Prof#=Conroe Lake 061,Reach-1         , 5
Up Type= 0
Dn Type= 3
Dn Slope=0.005
Boundary for River Rch & Prof#=Conroe Lake 061,Reach-1         , 6
Up Type= 0
Dn Type= 3
Dn Slope=0.005
Boundary for River Rch & Prof#=Conroe Lake 061,Reach-1         , 7
Up Type= 0
Dn Type= 3
Dn Slope=0.005
DSS Import GetInterval= 0
DSS Import GetPeak= 0
DSS Import FillOption= 0

--- Conroe Lake 061.f02 (steady flow) ---

Flow Title=Orig_BLE_Flow
Program Version=4.10
Number of Profiles= 7
Profile Names=10-year,25-year,50-year,1pct_min,100-year,1pct_plu,500-year
River Rch & RM=Conroe Lake 061,Reach-1         ,3100
     815    1095    1323     525    1585    4787    2269
River Rch & RM=Conroe Lake 061,Reach-1         ,1477
     798    1068    1287     509    1537    4640    2187
River Rch & RM=Conroe Lake 061,Reach-1         ,968
    2179    3040    3765    1523    4600   13891    6862
River Rch & RM=Conroe Lake 061,Reach-1         ,469
    2179    3040    3765    1523    4600   13891    6862
Boundary for River Rch & Prof#=Conroe Lake 061,Reach-1         , 1
Up Type= 0
Dn Type= 3
Dn Slope=0.005
Boundary for River Rch & Prof#=Conroe Lake 061,Reach-1         , 2
Up Type= 0
Dn Type= 3
Dn Slope=0.005
Boundary for River Rch & Prof#=Conroe Lake 061,Reach-1         , 3
Up Type= 0
Dn Type= 3
Dn Slope=0.005
Boundary for River Rch & Prof#=Conroe Lake 061,Reach-1         , 4
Up Type= 0
Dn Type= 3
Dn Slope=0.005
Boundary for River Rch & Prof#=Conroe Lake 061,Reach-1         , 5
Up Type= 0
Dn Type= 3
Dn Slope=0.005
Boundary for River Rch & Prof#=Conroe Lake 061,Reach-1         , 6
Up Type= 0
Dn Type= 3
Dn Slope=0.005
Boundary for River Rch & Prof#=Conroe Lake 061,Reach-1         , 7
Up Type= 0
Dn Type= 3
Dn Slope=0.005
DSS Import GetInterval= 0
DSS Import GetPeak= 0
DSS Import FillOption= 0

--- Conroe Lake 061.g01 (geometry) ---

Geom Title=Existing Conditions
Program Version=4.10

River Reach=Conroe Lake 061 ,Reach-1
Reach XY= 30
      3805128.23     10203641.84      3805108.23     10203696.84
      3805118.23     10203816.84      3805148.23     10203906.84
      3805218.23     10203986.84      3805228.23     10204016.84
      3805188.23     10204096.84      3805278.23     10204286.84
      3805228.23     10204356.84      3805428.23     10204576.84
      3805408.23     10204596.84      3805438.23     10204656.84
      3805428.23     10204676.84      3805518.23     10204756.84
      3805538.23     10204896.84      3805508.23     10204986.84
      3805335.31     10205149.53      3805296.19     10205140.36
      3805260.93     10205202.63      3805146.66     10205249.82
      3804993.29     10205382.28      3804831.14     10205454.45
      3804684.01     10205481.79      3804635.83     10205566.43
       3804482.9     10205671.58      3804458.23     10205704.93
      3804473.36     10205749.05      3804431.75     10205784.44
      3804428.14     10205825.56      3804499.84     10205928.31

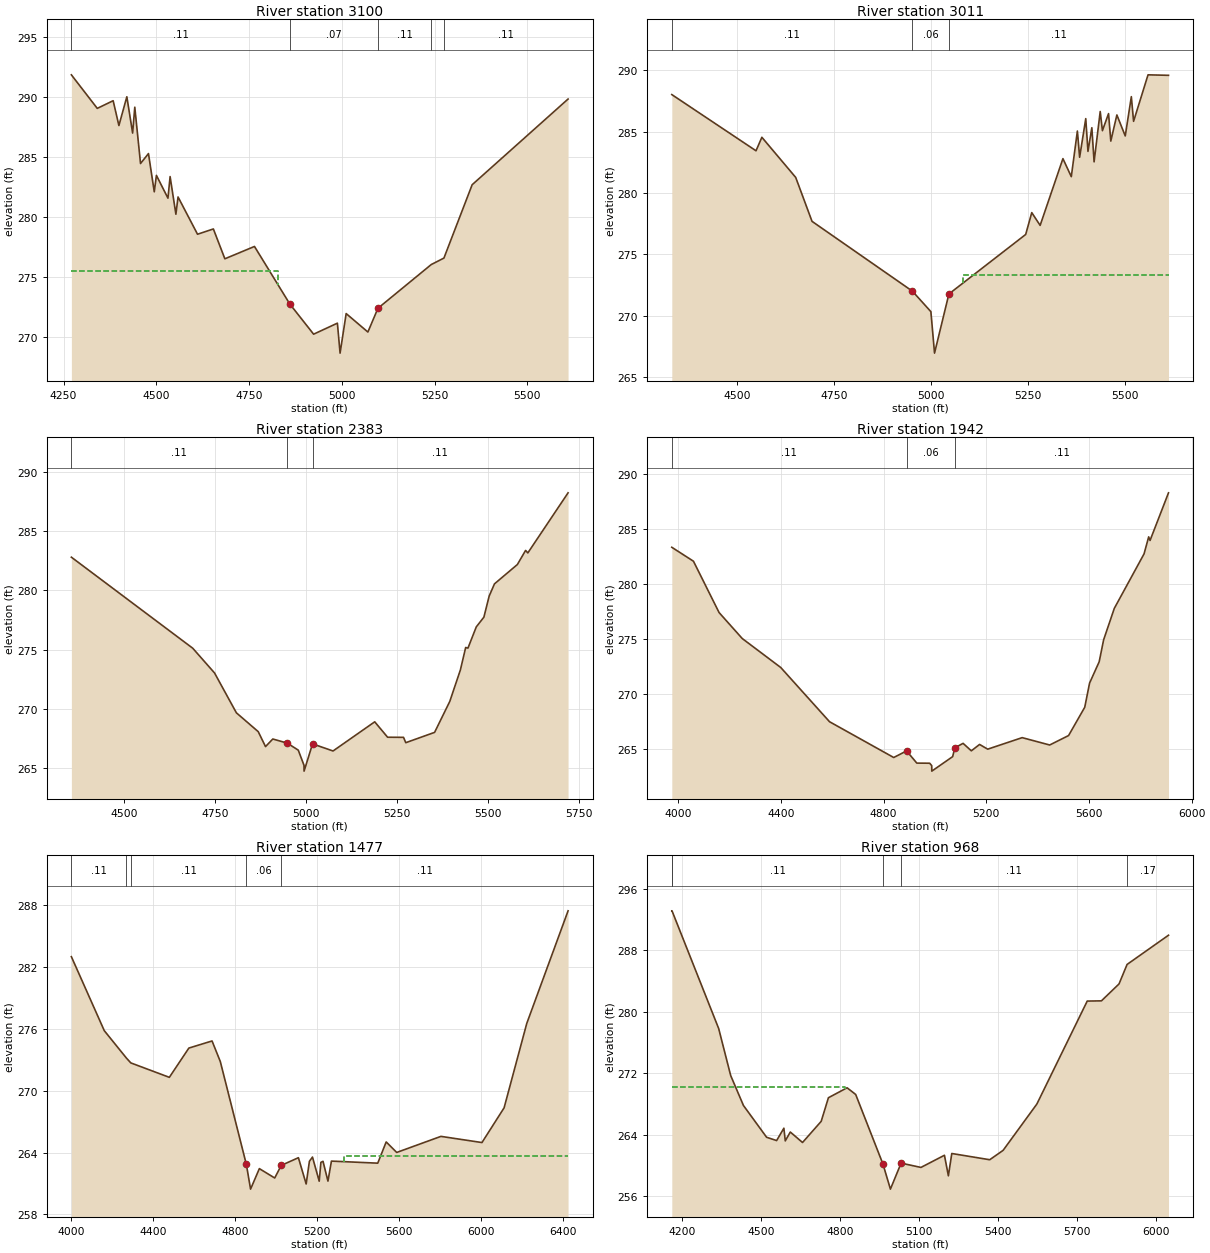
Type RM Length L Ch R = 1 ,3100    ,89,89,89
BEGIN DESCRIPTION:
Conroe Lake 061 6.5
END DESCRIPTION:
XS GIS Cut Line= 3
      3804503.11     10204202.09      3805128.23     10203826.84
      3805640.17     10203495.89
#Sta/Elev= 30
  4270.9  291.85  4340.7  289.05  4383.5  289.69    4399  287.62  4420.4  290.02
    4436  286.99  4441.8  289.15  4457.3  284.45  4478.7  285.28  4494.3  282.09
  4500.1  283.46  4531.2  281.56    4537  283.36  4552.6  280.22  4558.4  281.66
  4610.9  278.55  4653.6  278.99  4684.6   276.5  4764.4  277.53  4859.6  272.73
  4923.8  270.21  4987.9  271.13  4995.1  268.63  5011.5  271.93  5070.1  270.39
  5097.1  272.37  5240.8  276.02    5275  276.56  5351.1  282.68  5609.6  289.83
#Mann= 5 ,-1 , 0
  4270.9     .11       0  4859.6     .07       0  5097.1     .11       0
  5240.8     .17       0    5275     .11       0
#XS Ineff= 2 , 0
       0  4828.5  275.47               0
Permanent Ineff=
       F       F
Bank Sta=4859.6,5097.1
XS Rating Curve= 0 ,0
Exp/Cntr=0.3,0.1

Type RM Length L Ch R = 1 ,3011    ,628,628,628
BEGIN DESCRIPTION:
Conroe Lake 061 6.0
END DESCRIPTION:
XS GIS Cut Line= 3
      3804590.15     10204274.87      3805148.23     10203906.84
      3805678.96     10203599.89
#Sta/Elev= 30
  4331.5  288.03  4548.8  283.45  4563.9  284.55  4651.2  281.28  4693.3   277.7
  4952.3  272.01    5000  270.34  5009.4  266.96  5046.5  271.78  5244.6  276.63
  5260.3  278.41  5281.9  277.37  5340.7  282.81  5362.3  281.34    5378  285.06
  5383.8  282.92  5399.6  286.07  5405.3   283.4  5415.3  285.33  5421.1  282.55
  5436.9  286.65  5442.6  285.09  5458.4  286.48  5464.2  284.24  5479.9  286.37
  5501.5  284.66  5517.2  287.86    5523  285.85  5560.3  289.64  5613.1   289.6
#Mann= 3 , 0 , 0
  4331.5     .11       0  4952.3     .06       0  5046.5     .11       0
#XS Ineff= 2 , 0
       0                  5083.8       0  273.35
Permanent Ineff=
       F       F
Bank Sta=4952.3,5046.5
XS Rating Curve= 0 ,0
Exp/Cntr=0.3,0.1

Type RM Length L Ch R = 1 ,2383    ,441,441,441
BEGIN DESCRIPTION:
Conroe Lake 061 5.0
END DESCRIPTION:
XS GIS Cut Line= 3
      3804634.38     10204424.69      3805278.23     10204406.84
      3805710.58     10203829.48
#Sta/Elev= 30
  4355.9   282.8  4689.5  275.12  4749.5  273.03  4809.5  269.67  4869.6  268.08
  4889.6  266.82  4909.6  267.46  4949.6  267.11  4979.6  266.52  4995.3  265.25
  4995.6  264.75  5018.9  267.05  5075.2  266.45  5189.8  268.91  5225.2  267.61
    5269   267.6  5275.2  267.15  5354.4  268.02  5396.1  270.63  5425.3  273.29
  5439.8  275.18  5446.1  275.13    5469  276.92  5489.9  277.74  5504.4  279.52
    5519  280.55  5581.9  282.18  5604.5  283.37  5610.7  283.16  5721.3  288.23
#Mann= 3 , 0 , 0
  4355.9     .11       0  4949.6     .06       0  5018.9     .11       0
Bank Sta=4949.6,5018.9
XS Rating Curve= 0 ,0
Exp/Cntr=0.3,0.1

Type RM Length L Ch R = 1 ,1942    ,465,465,465
BEGIN DESCRIPTION:
Conroe Lake 061 4.0
END DESCRIPTION:
XS GIS Cut Line= 3
       3804453.6     10204735.76      3805478.23     10204716.84
      3805755.69     10203850.38
#Sta/Elev= 30
  3975.2  283.33  4059.5  282.06  4159.5  277.38  4249.5  275.02  4399.5  272.38
  4589.6  267.44  4839.6  264.18  4889.6  264.78  4929.6  263.67  4979.6  263.66
  4987.6  263.44  4987.9  262.94  5069.1  264.26  5077.5  265.06  5109.7  265.47
  5141.8  264.79    5174  265.37  5205.6  264.94  5339.9  265.99  5447.1  265.32
  5520.6  266.18  5583.6  268.76  5602.4  270.96  5639.8   272.9  5657.1   274.9
  5698.8  277.77  5814.6  282.73  5832.6  284.28  5837.9  283.95  5909.8  288.29
#Mann= 3 , 0 , 0
  3975.2     .11       0  4889.6     .06       0  5077.5     .11       0
#XS Ineff= 2 , 0
       0                  5339.9       0  265.99
Permanent Ineff=
       F       F
Bank Sta=4889.6,5077.5
XS Rating Curve= 0 ,0
Exp/Cntr=0.3,0.1

Type RM Length L Ch R = 1 ,1477    ,509,509,509
BEGIN DESCRIPTION:
Conroe Lake 061 3.0
END DESCRIPTION:
XS GIS Cut Line= 3
       3804446.7     10204767.02      3805514.73     10205120.22
      3805807.78     10203857.28
#Sta/Elev= 30
  4001.7  283.02  4162.1  275.84    4270  273.18  4291.5  272.71  4479.3  271.31
  4574.5  274.15  4687.5  274.84  4727.8  272.84  4854.7  262.86  4875.3  260.46
  4918.1  262.45    4993  261.54  5024.6  262.76  5108.5  263.51  5146.3  260.96
  5162.1  263.16  5177.1  263.57  5209.9  261.23  5218.1  263.06  5228.4  263.16
  5252.5  261.24  5269.5  263.18  5495.3  262.98  5536.4  265.04  5587.7  264.02
  5803.3  265.58  6003.3  264.98  6111.2  268.35  6221.7  276.54  6423.1  287.47
#Mann= 5 ,-1 , 0
  4001.7     .11       0    4270     .17       0  4291.5     .11       0
  4854.7     .06       0  5024.6     .11       0
#XS Ineff= 2 , 0
       0                    5331       0  263.65
Permanent Ineff=
       F       F
Bank Sta=4854.7,5024.6
XS Rating Curve= 0 ,0
Exp/Cntr=0.3,0.1

Type RM Length L Ch R = 1 ,968     ,499,499,499
BEGIN DESCRIPTION:
Conroe Lake 061 2.0
END DESCRIPTION:
XS GIS Cut Line= 3
      3804217.82     10205111.06      3805018.73     10205356.24
        3805953.      10205829.5
#Sta/Elev= 30
  4162.4   293.1  4163.2   293.1  4340.2  277.81  4385.9  271.69  4434.3   267.8
  4522.2  263.67  4560.2  263.24  4587.7  264.85    4593   263.2  4612.1  264.35
  4658.5  262.99  4729.3  265.74  4756.8  268.81  4827.6   270.1  4860.3  269.23
  4963.9  260.17    4992  256.93  5032.6  260.31  5107.9  259.75    5197  261.33
    5212  258.66  5224.9  261.56  5368.9  260.75  5419.7  261.97  5547.8  267.99
  5738.9  281.37  5792.8   281.4  5859.6   283.6  5890.1  286.13  6047.3  289.93
#Mann= 5 ,-1 , 0
  4162.4     .17       0  4163.2     .11       0  4963.9     .06       0
  5032.6     .11       0  5890.1     .17       0
#XS Ineff= 2 , 0
       0  4821.3  270.14               0
Permanent Ineff=
       F       F
Bank Sta=4963.9,5032.6
XS Rating Curve= 0 ,0
Exp/Cntr=0.3,0.1

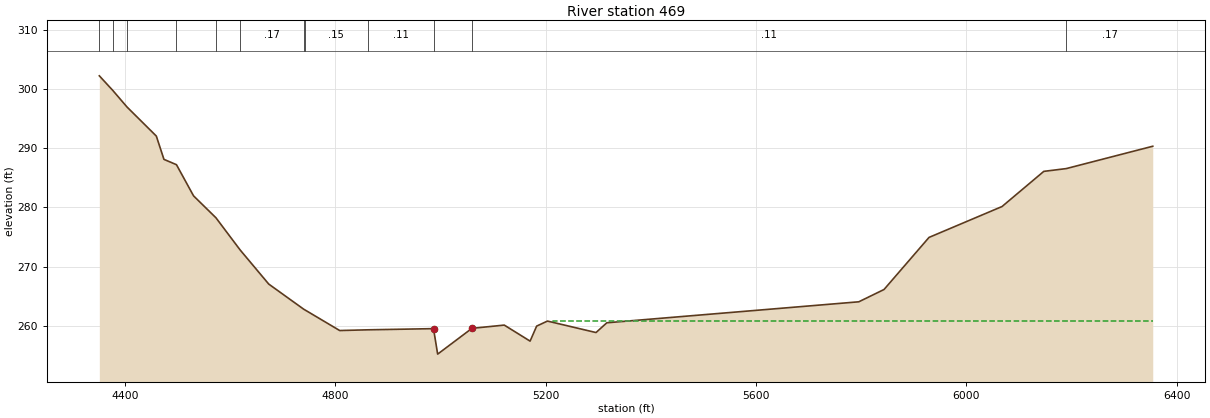
Type RM Length L Ch R = 1 ,469     ,0,0,0
BEGIN DESCRIPTION:
Conroe Lake 061 1.0
END DESCRIPTION:
XS GIS Cut Line= 3
      3804095.98     10205190.62      3804609.79     10205587.26
      3805929.81     10205890.92
#Sta/Elev= 30
  4350.9  302.26  4376.5  299.79  4403.5  296.99  4459.3  292.07  4473.8  288.13
  4497.6  287.23  4530.1  281.96  4572.7  278.25  4618.7  272.81  4673.1  267.04
  4739.9  262.77  4741.9  262.67  4808.1  259.18    4861   259.3  4986.5   259.5
  4994.4  255.19  5059.6  259.55  5121.1   260.1  5170.2  257.39  5182.7  259.93
  5203.2  260.78  5295.6  258.84  5316.1  260.49  5795.4  264.04  5843.4  266.12
    5929  274.93  6067.8  280.15  6147.3   286.1    6190  286.57  6354.5  290.35
#Mann= 12 ,-1 , 0
  4350.9     .11       0  4376.5     .17       0  4403.5     .11       0
  4497.6     .17       0  4572.7     .11       0  4618.7     .17       0
  4739.9     .11       0  4741.9     .15       0    4861     .11       0
  4986.5     .06       0  5059.6     .11       0    6190     .17       0
#XS Ineff= 2 , 0
       0                    5213       0   260.8
Permanent Ineff=
       F       T
Bank Sta=4986.5,5059.6
XS Rating Curve= 0 ,0
Exp/Cntr=0.3,0.1

Chan Stop Cuts=-1
Use User Specified Reach Order=0
Composite Channel Slope=5