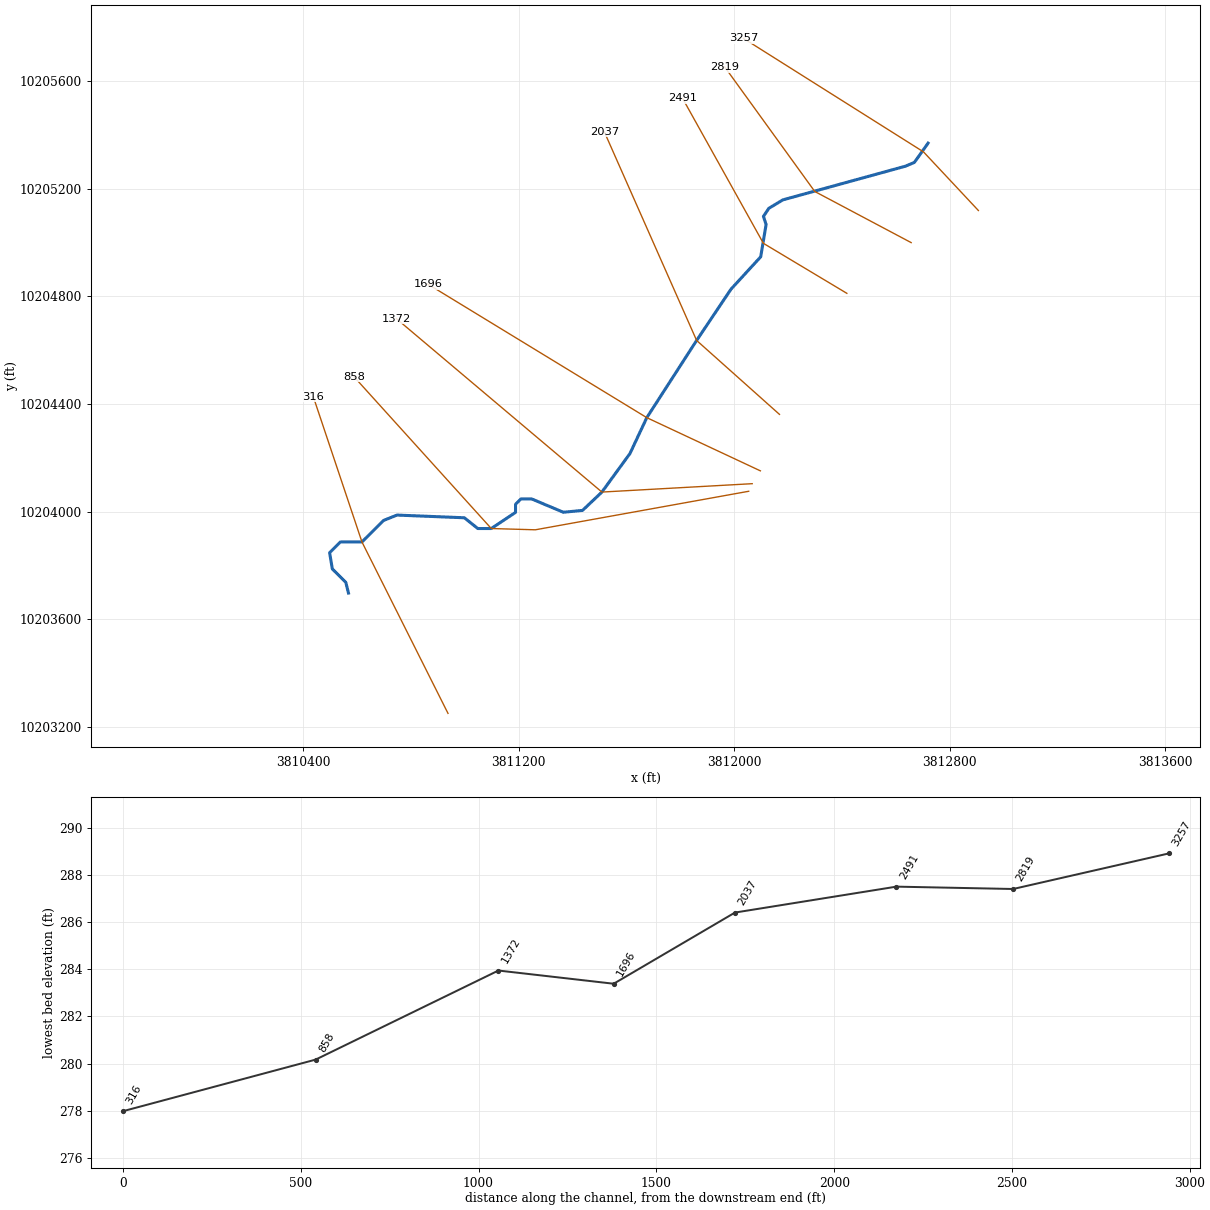
--- Conroe Lake 063.prj (project) ---

Proj Title=Conroe Lake 063 Base Level Engineering
Current Plan=p01
Default Exp/Contr=0.3,0.1
English Units
Geom File=g01
Flow File=f01
Flow File=f02
Plan File=p01
Y Axis Title=Elevation
X Axis Title(PF)=Main Channel Distance
X Axis Title(XS)=Station
BEGIN DESCRIPTION:
Conroe Lake 063
END DESCRIPTION:
DSS File=dss
DSS Export Rating Curves= 0
DSS Export Rating Curve Sorted= 0
DSS Export Volume Flow Curves= 0
DXF OffsetX= 0
DXF OffsetY= 0
DXF ScaleX= 1
DXF ScaleY= 10

--- Conroe Lake 063.p01 (plan) ---

Plan Title=Multiple Run
Program Version=4.10
Short Identifier=Multiple Run
Geom File=g01
Flow File=f01
Subcritical Flow
K Sum by GR= 0
Std Step Tol= 0.01
Critical Tol= 0.01
Num of Std Step Trials= 20
Max Error Tol= 0.3
Flow Tol Ratio= 0.001
Split Flow NTrial= 30
Split Flow Tol= 0.02
Split Flow Ratio= 0.02
Log Output Level= 0
Friction Slope Method= 1
Unsteady Friction Slope Method= 2
Unsteady Bridges Friction Slope Method= 1
Parabolic Critical Depth
Global Vel Dist= 1 , 1 , 1
Global Log Level= 0
CheckData=True
Encroach Param=-1 ,0,0, 0
BEGIN DESCRIPTION:
Multiple Run
END DESCRIPTION:
Computation Interval=1HOUR
Output Interval=1HOUR
Run HTab= 0
Run UNet= 0
Run PostProcess= 0
Run WQNet= 0
UNET Theta= 1
UNET Theta Warmup= 1
UNET ZTol= 0.02
UNET ZSATol= 0.05
UNET MxIter= 20
UNET MaxInSteps= 0
UNET DtIC= 0
UNET DtMin= 0
UNET MaxCRTS= 20
UNET WFStab= 2
UNET SFStab= 1
UNET WFX= 1
UNET SFX= 1
UNET DSS MLevel= 4
UNET DZMax Abort= 100
UNET Convert EG Bridges= 0
UNET Use Existing IB Tables=-1
UNET Froude Reduction=False
UNET Froude Limit= 1
UNET Froude Power= 10
UNET Time Slicing=0,0, 5
UNET Junction Losses=0
Instantaneous Interval=1HOUR
DSS File=dss
Write IC File= 0
Write IC File at Sim End=0
Echo Input=False
Echo Parameters=False
Echo Output=False
Write Detailed= 0
WQ AD Non Conservative
WQ ULTIMATE=-1
WQ Max Comp Step=1HOUR
WQ Output Interval=15MIN
WQ Output Selected Increments= 0
WQ Output face flow=0
WQ Output face velocity=0
WQ Output face area=0
WQ Output face dispersion=0
WQ Output cell volume=0
WQ Output cell surface area=0
WQ Output cell continuity=0
WQ Output cumulative cell continuity=0
WQ Output face conc=0
WQ Output face dconc_dx=0
WQ Output face courant=0
WQ Output face peclet=0
WQ Output face adv mass=0
WQ Output face disp mass=0
WQ Output cell mass=0
WQ Output cell source sink temp=0
WQ Output cell source sink nsm=0
WQ Output MaxMinRange=-1
WQ Daily Max Min Mean=-1
WQ Daily Range=0
WQ Daily Time=0
WQ Create Restart=0
WQ Fixed Restart=0
WQ System Summary=0
WQ Use Fixed Temperature=0
Sorting and Armoring Iterations= 10
XS Update Threshold= 0.02
Hydraulics Update Threshold= 0.02
Energy Slope Method= 1
Volume Change Method= 0
XS Weighting Method= 0
Number of US Weighted Cross Sections= 1
Number of DS Weighted Cross Sections= 1
Upstream XS Weight=0.25
Main XS Weight=0.5
Downstream XS Weight=0.25
Number of DS XS's Weighted with US Boundary= 1
Upstream Boundary Weight= 1
Weight of XSs Associated with US Boundary= 0
Number of US XS's Weighted with DS Boundary= 1
Downstream Boundary Weight= 0.5
Weight of XSs Associated with DS Boundary= 0.5
Sediment Output Level= 4
Mass or Volume Output= 0
Output Increment Type= 1
Profile and TS Output Increment= 10
XS Output Flag= 0
XS Output Increment= 10
Disregard all LS=0
Disregard all Conn=0
Disregard all Breaches=0
Disregard all Pumps=0

--- Conroe Lake 063.f01 (steady flow) ---

Flow Title=Multiple
Program Version=4.10
Number of Profiles= 7
Profile Names=10-year,25-year,50-year,1pct_min,100-year,1pct_plu,500-year
River Rch & RM=Conroe Lake 063,Reach-1         ,3257
     871    1202    1645     741    2237    6756    4278
River Rch & RM=Conroe Lake 063,Reach-1         ,2491
    1017    1414    1945     880    2657    8024    5126
River Rch & RM=Conroe Lake 063,Reach-1         ,316
    1359    1908    2643    1201    3626   10950    7066
Boundary for River Rch & Prof#=Conroe Lake 063,Reach-1         , 1
Up Type= 0
Dn Type= 3
Dn Slope=0.009
Boundary for River Rch & Prof#=Conroe Lake 063,Reach-1         , 2
Up Type= 0
Dn Type= 3
Dn Slope=0.009
Boundary for River Rch & Prof#=Conroe Lake 063,Reach-1         , 3
Up Type= 0
Dn Type= 3
Dn Slope=0.009
Boundary for River Rch & Prof#=Conroe Lake 063,Reach-1         , 4
Up Type= 0
Dn Type= 3
Dn Slope=0.009
Boundary for River Rch & Prof#=Conroe Lake 063,Reach-1         , 5
Up Type= 0
Dn Type= 3
Dn Slope=0.009
Boundary for River Rch & Prof#=Conroe Lake 063,Reach-1         , 6
Up Type= 0
Dn Type= 3
Dn Slope=0.009
Boundary for River Rch & Prof#=Conroe Lake 063,Reach-1         , 7
Up Type= 0
Dn Type= 3
Dn Slope=0.009
DSS Import GetInterval= 0
DSS Import GetPeak= 0
DSS Import FillOption= 0

--- Conroe Lake 063.f02 (steady flow) ---

Flow Title=Orig_BLE_Flow
Program Version=4.10
Number of Profiles= 7
Profile Names=10-year,25-year,50-year,1pct_min,100-year,1pct_plu,500-year
River Rch & RM=Conroe Lake 063,Reach-1         ,3257
     871    1178    1430     570    1721    5198    2487
River Rch & RM=Conroe Lake 063,Reach-1         ,2491
    1017    1386    1691     677    2044    6173    2980
River Rch & RM=Conroe Lake 063,Reach-1         ,316
    1359    1871    2298     924    2789    8424    4108
Boundary for River Rch & Prof#=Conroe Lake 063,Reach-1         , 1
Up Type= 0
Dn Type= 3
Dn Slope=0.009
Boundary for River Rch & Prof#=Conroe Lake 063,Reach-1         , 2
Up Type= 0
Dn Type= 3
Dn Slope=0.009
Boundary for River Rch & Prof#=Conroe Lake 063,Reach-1         , 3
Up Type= 0
Dn Type= 3
Dn Slope=0.009
Boundary for River Rch & Prof#=Conroe Lake 063,Reach-1         , 4
Up Type= 0
Dn Type= 3
Dn Slope=0.009
Boundary for River Rch & Prof#=Conroe Lake 063,Reach-1         , 5
Up Type= 0
Dn Type= 3
Dn Slope=0.009
Boundary for River Rch & Prof#=Conroe Lake 063,Reach-1         , 6
Up Type= 0
Dn Type= 3
Dn Slope=0.009
Boundary for River Rch & Prof#=Conroe Lake 063,Reach-1         , 7
Up Type= 0
Dn Type= 3
Dn Slope=0.009
DSS Import GetInterval= 0
DSS Import GetPeak= 0
DSS Import FillOption= 0

--- Conroe Lake 063.g01 (geometry) ---

Geom Title=Existing Conditions
Program Version=4.10

River Reach=Conroe Lake 063 ,Reach-1
Reach XY= 30
      3812719.36      10205369.3      3812668.58     10205297.69
      3812634.73     10205283.36       3812180.3     10205158.36
      3812128.23     10205126.84      3812108.23     10205096.84
      3812118.23     10205066.84      3812098.23     10204946.84
      3811988.23     10204826.84      3811860.32     10204635.91
      3811675.42     10204348.93      3811612.92      10204215.6
      3811508.76     10204072.37      3811436.88     10204004.14
      3811365.53     10203997.37      3811248.23     10204046.84
      3811208.23     10204046.84      3811188.23     10204026.84
      3811188.23     10203996.84      3811098.23     10203936.84
      3811048.23     10203936.84      3810998.23     10203976.84
      3810748.23     10203986.84      3810698.23     10203966.84
      3810618.23     10203886.84      3810538.23     10203886.84
      3810498.23     10203846.84      3810508.23     10203786.84
      3810558.23     10203736.84      3810568.23     10203696.84

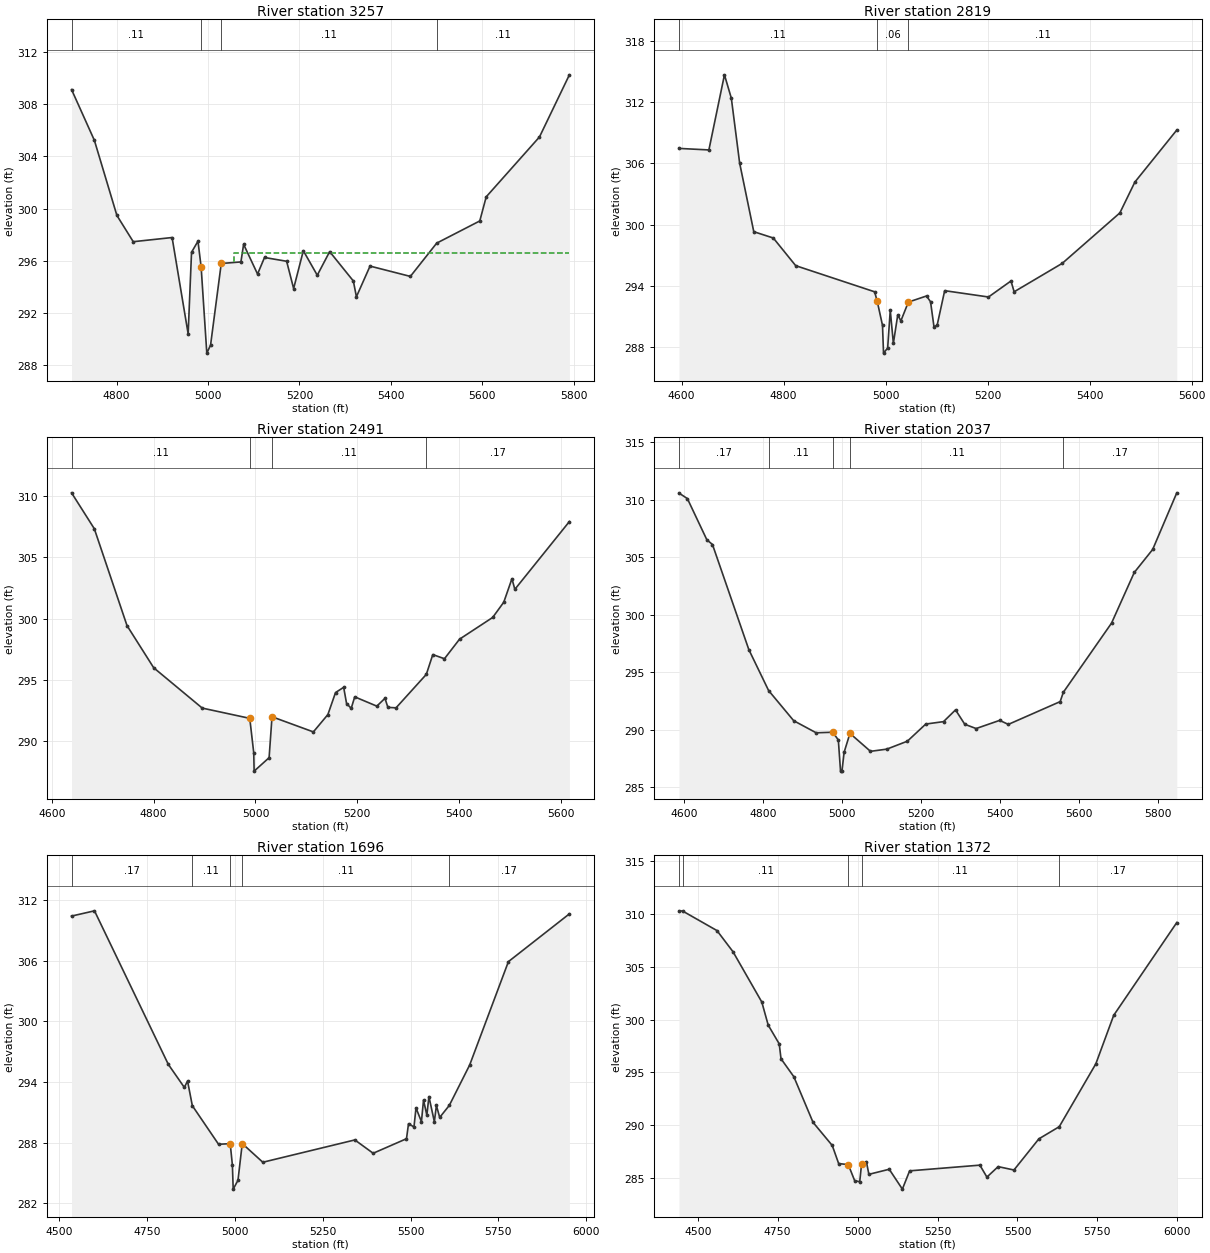
Type RM Length L Ch R = 1 ,3257    ,438,438,438
BEGIN DESCRIPTION:
Conroe Lake 063 6.0
END DESCRIPTION:
XS GIS Cut Line= 3
      3812906.13     10205118.83      3812702.43     10205336.75
      3812034.03      10205758.8
#Sta/Elev= 30
  4701.7  309.12  4751.6  305.23  4800.9  299.47  4836.6  297.46  4921.6  297.78
  4956.7   290.4  4964.1  296.65  4978.2   297.5  4985.1  295.52  4997.5  288.92
  5005.7  289.53  5029.1  295.79  5072.1  295.91    5078  297.26  5108.5  294.98
  5123.7  296.25  5172.1  295.96  5187.4  293.87  5208.6  296.77  5239.1  294.89
  5266.2   296.7    5318  294.45  5324.7  293.24  5354.5  295.59  5442.7   294.8
  5500.3  297.35  5594.5  299.05  5608.6   300.9  5725.1  305.49  5790.5  310.25
#Mann= 4 ,-1 , 0
  4701.7     .11       0  4985.1     .06       0  5029.1     .11       0
  5500.3     .11       0
#XS Ineff= 2 , 0
       0  4978.2   297.5  5056.8       0  296.61
Permanent Ineff=
       F       F
Bank Sta=4985.1,5029.1
XS Rating Curve= 0 ,0
Exp/Cntr=0.3,0.1

Type RM Length L Ch R = 1 ,2819    ,328,328,328
BEGIN DESCRIPTION:
Conroe Lake 063 5.0
END DESCRIPTION:
XS GIS Cut Line= 3
      3812656.63     10204999.52      3812298.79     10205189.61
      3811964.61     10205652.49
#Sta/Elev= 30
  4594.8  307.47  4653.5  307.32    4684  314.68  4697.5  312.39  4713.8  306.03
  4741.5  299.31  4779.8  298.69  4823.7  295.98  4978.4  293.42 4983.28  292.55
  4993.9  290.13  4995.9  287.41    5004  287.91  5009.1  291.61  5015.2  288.37
  5023.8  291.16  5029.9  290.57  5044.6  292.41  5080.2  293.01  5088.1  292.44
  5094.9  289.97  5101.1  290.16  5115.8  293.53  5201.7  292.91  5245.8  294.48
    5252  293.42  5346.4  296.21  5459.3  301.15  5488.7  304.17  5570.9  309.27
#Mann= 3 , 0 , 0
  4594.8     .11       0 4983.28     .06       0  5044.6     .11       0
#XS Ineff= 2 , 0
       0                  5245.8       0  294.48
Permanent Ineff=
       F       F
Bank Sta=4983.28,5044.6
XS Rating Curve= 0 ,0
Exp/Cntr=0.3,0.1

Type RM Length L Ch R = 1 ,2491    ,454,454,454
BEGIN DESCRIPTION:
Conroe Lake 063 4.0
END DESCRIPTION:
XS GIS Cut Line= 3
      3812417.87     10204811.06      3812108.23     10204996.84
      3811808.37     10205535.39
#Sta/Elev= 30
  4638.9  310.29  4683.6  307.35  4747.8  299.42  4800.2  295.97  4895.5  292.67
  4988.8  291.83  4996.6  289.02  4997.4  287.51  5026.8  288.61  5032.5  291.96
  5113.7  290.72  5142.2  292.14  5157.2  293.94  5173.2  294.37  5178.9  293.04
    5188  292.65  5194.9  293.59  5238.3  292.83  5254.3  293.47    5260  292.73
    5276  292.69  5335.5  295.43  5348.2  297.05  5371.1  296.71  5400.7  298.31
  5465.8  300.09  5487.6  301.34  5503.6  303.26  5509.3  302.39  5616.4  307.94
#Mann= 4 ,-1 , 0
  4638.9     .11       0  4988.8     .06       0  5032.5     .11       0
  5335.5     .17       0
Bank Sta=4988.8,5032.5
XS Rating Curve= 0 ,0
Exp/Cntr=0.3,0.1

Type RM Length L Ch R = 1 ,2037    ,341,341,341
BEGIN DESCRIPTION:
Conroe Lake 063 3.0
END DESCRIPTION:
XS GIS Cut Line= 3
      3812167.82      10204361.1      3811860.32     10204635.91
      3811517.87     10205411.03
#Sta/Elev= 30
  4587.6  310.57  4608.9  310.09  4658.2  306.51  4672.4   306.1  4764.4  296.97
  4814.5  293.41    4878  290.79  4934.9  289.74  4976.7  289.79  4990.9  289.12
  4996.5  286.41  5000.1  286.41  5005.6  288.05  5020.3  289.69  5072.3  288.13
  5113.5  288.32  5165.6  289.01  5212.2   290.5  5257.1  290.71  5287.5  291.73
  5310.9  290.48  5339.6  290.11  5399.2  290.82  5421.1  290.47  5552.3  292.45
  5560.3  293.26  5682.3  299.27  5739.8  303.67  5786.4  305.67  5847.4  310.59
#Mann= 5 ,-1 , 0
  4587.6     .17       0  4814.5     .11       0  4976.7     .07       0
  5020.3     .11       0  5560.3     .17       0
Bank Sta=4976.7,5020.3
XS Rating Curve= 0 ,0
Exp/Cntr=0.3,0.1

Type RM Length L Ch R = 1 ,1696    ,324,324,324
BEGIN DESCRIPTION:
Conroe Lake 063 2.0
END DESCRIPTION:
XS GIS Cut Line= 3
      3812096.96     10204151.23      3811675.42     10204348.93
      3810862.65     10204845.39
#Sta/Elev= 30
  4534.4  310.42  4599.7  310.94    4810  295.74  4855.6  293.46  4864.8  294.09
  4878.4  291.65  4953.1  287.83  4986.3  287.89  4992.5  285.78  4994.8  283.39
  5008.4  284.26  5020.6   287.9  5079.2  286.05  5341.3  288.26  5393.5  286.94
  5488.4  288.38  5494.2  289.87  5509.7  289.54  5515.5  291.43    5531  290.07
  5536.9  292.21  5546.4  290.71  5552.3  292.55  5567.8  290.06  5573.6  291.67
    5583  290.49  5610.4  291.68  5668.4  295.68  5778.7  305.91  5952.4  310.64
#Mann= 5 ,-1 , 0
  4534.4     .17       0  4878.4     .11       0  4986.3     .07       0
  5020.6     .11       0  5610.4     .17       0
#XS Ineff= 2 , 0
       0                  5536.9       0  292.21
Permanent Ineff=
       F       F
Bank Sta=4986.3,5020.6
XS Rating Curve= 0 ,0
Exp/Cntr=0.3,0.1

Type RM Length L Ch R = 1 ,1372    ,514,514,514
BEGIN DESCRIPTION:
Conroe Lake 063 1.0
END DESCRIPTION:
XS GIS Cut Line= 3
      3812066.59     10204103.52      3811508.76     10204072.37
      3810746.17     10204716.78
#Sta/Elev= 30
  4441.3  310.29  4452.8  310.27  4560.2  308.42  4610.3  306.42  4700.4  301.66
  4720.5  299.47  4754.9   297.7  4760.5  296.29  4800.6  294.59  4860.7  290.27
  4920.8  288.08  4940.8  286.37  4970.9  286.27  4990.9  284.75  5006.7  284.65
 5012.39   286.3  5027.6  286.55  5035.3  285.35    5099  285.83  5140.1  283.95
  5162.8  285.68  5382.5  286.22  5404.5  285.09  5439.7  286.08  5489.1  285.76
  5567.1  288.71  5630.8  289.86  5745.2  295.81  5801.1   300.4  5998.4  309.18
#Mann= 5 ,-1 , 0
  4441.3     .17       0  4452.8     .11       0  4970.9     .09       0
 5012.39     .11       0  5630.8     .17       0
Bank Sta=4970.9,5012.39
XS Rating Curve= 0 ,0
Exp/Cntr=0.3,0.1

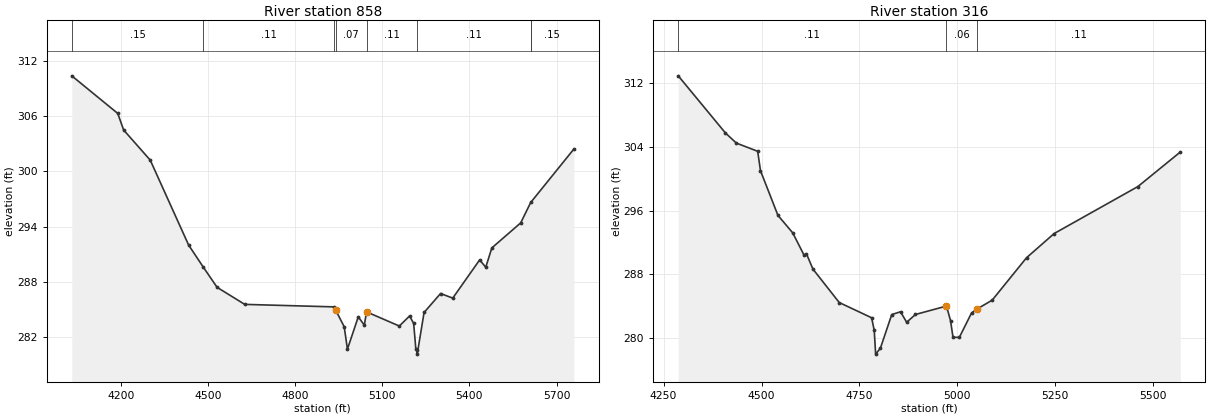
Type RM Length L Ch R = 1 ,858     ,542,542,542
BEGIN DESCRIPTION:
Conroe Lake 063 2.5
END DESCRIPTION:
XS GIS Cut Line= 4
      3812053.52     10204075.31      3811261.68     10203932.13
      3811098.23     10203936.84      3810589.18      10204500.5
#Sta/Elev= 30
  4031.8  310.38    4190   306.3  4210.3   304.5  4301.8  301.23  4433.9  292.01
  4484.7   289.6  4531.9  287.42    4627  285.57  4932.8   285.3  4940.4  284.92
  4969.3  283.14  4980.4  280.71  5017.7  284.22  5038.6  283.31  5046.1  284.76
  5158.9  283.22  5194.3  284.31  5208.3   283.5  5215.7  280.76  5220.4  280.67
  5220.6  280.17  5244.1  284.69  5300.9  286.75  5342.8  286.25  5435.4   290.4
  5456.4   289.6  5477.3   291.7  5576.7  294.42    5611  296.63  5759.5  302.43
#Mann= 8 ,-1 , 0
  4031.8     .15       0  4484.7     .11       0  4932.8     .11       0
  4940.4     .07       0  5046.1     .11       0  5220.4     .11       0
    5611     .17       0    5611     .15       0
#XS Ineff= 2 , 0
       0  4596.5  286.15  5300.9       0  286.75
Permanent Ineff=
       F       F
Bank Sta=4940.4,5046.1
XS Rating Curve= 0 ,0
Exp/Cntr=0.3,0.1

Type RM Length L Ch R = 1 ,316     ,0,0,0
BEGIN DESCRIPTION:
Conroe Lake 063 1.5
END DESCRIPTION:
XS GIS Cut Line= 3
      3810937.56      10203249.8      3810618.23     10203886.84
      3810437.71     10204426.45
#Sta/Elev= 30
  4287.4  312.94  4407.9  305.76  4435.8  304.49  4490.2  303.46  4497.3  301.03
  4541.9  295.41  4579.7  293.21    4609  290.37  4614.6  290.59  4631.3  288.66
  4698.4  284.46    4781  282.55  4787.7  280.96  4791.3  277.98  4803.4  278.72
  4832.4  282.95  4854.8   283.3  4870.5  281.98  4892.9  282.96  4972.1  284.02
  4982.4   282.2  4988.8   280.1  5004.9  280.08  5036.1  283.15  5050.2  283.65
  5088.8  284.76  5176.5  290.09    5247  293.13  5460.7  299.03    5569  303.37
#Mann= 3 , 0 , 0
  4287.4     .11       0  4972.1     .06       0  5050.2     .11       0
Bank Sta=4972.1,5050.2
XS Rating Curve= 0 ,0
Exp/Cntr=0.3,0.1

Chan Stop Cuts=-1
Use User Specified Reach Order=0
Composite Channel Slope=5