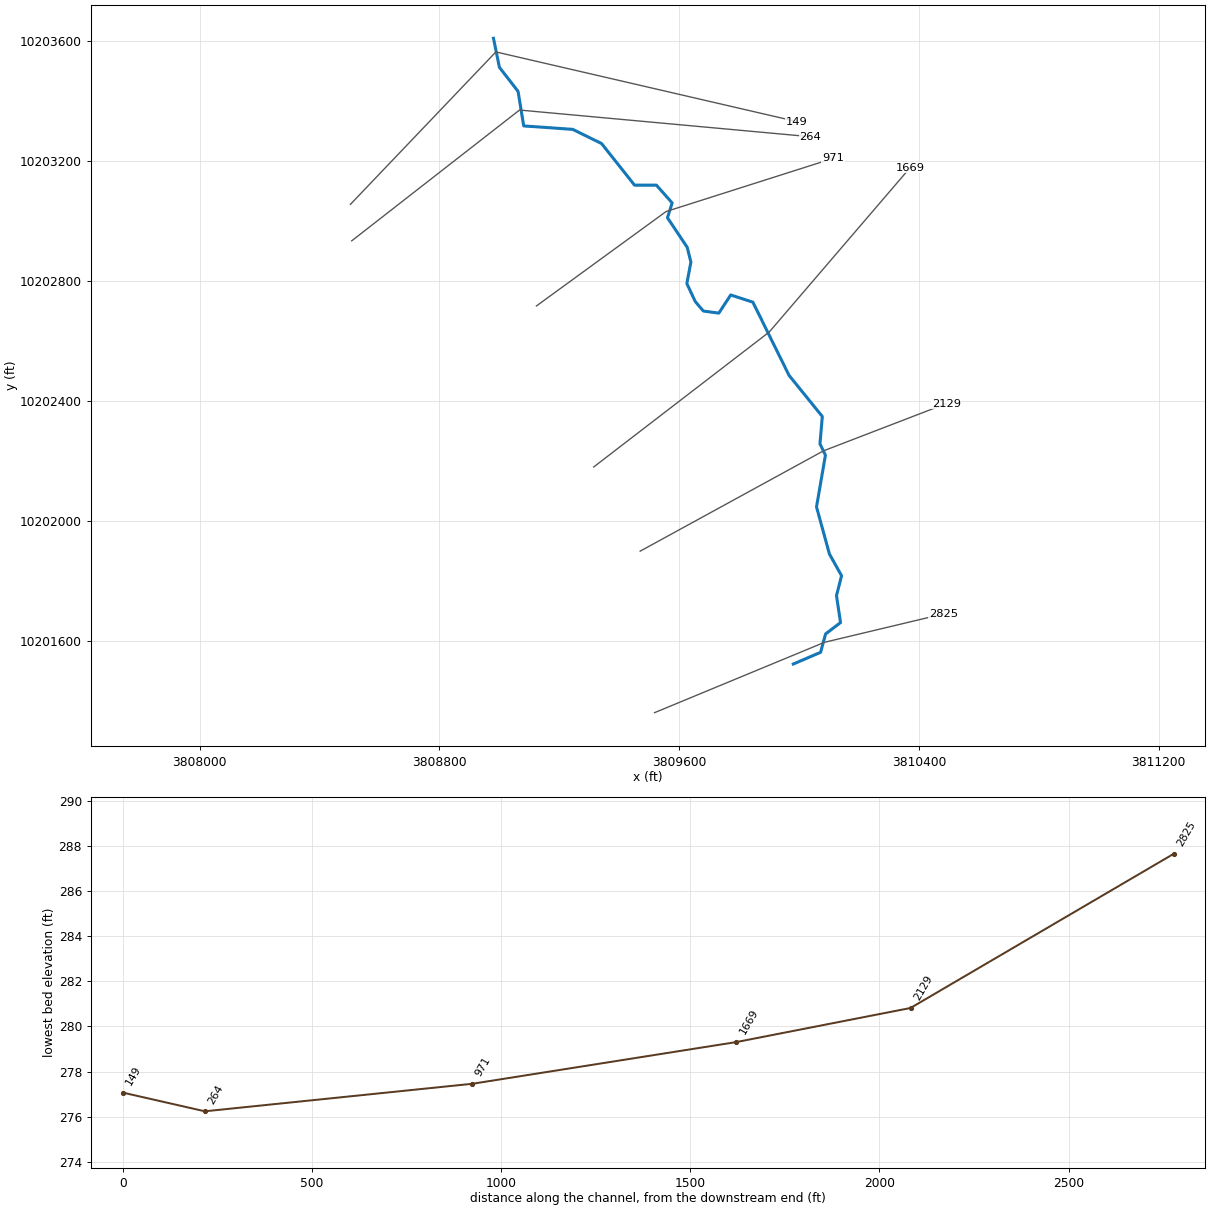
--- Conroe Lake 064.prj (project) ---

Proj Title=Conroe Lake 064 Base Level Engineering
Current Plan=p01
Default Exp/Contr=0.3,0.1
English Units
Geom File=g01
Flow File=f01
Flow File=f02
Plan File=p01
Y Axis Title=Elevation
X Axis Title(PF)=Main Channel Distance
X Axis Title(XS)=Station
BEGIN DESCRIPTION:
Conroe Lake 064
END DESCRIPTION:
DSS Export Rating Curves= 0
DSS Export Rating Curve Sorted= 0
DSS Export Volume Flow Curves= 0
DXF OffsetX= 0
DXF OffsetY= 0
DXF ScaleX= 1
DXF ScaleY= 10

--- Conroe Lake 064.p01 (plan) ---

Plan Title=Multiple Run
Short Identifier=Multiple
Geom File=g01
Flow File=f01
Subcritical Flow
K Sum by GR= 0
Std Step Tol= 0.01
Critical Tol= 0.01
Num of Std Step Trials= 20
Max Error Tol= 0.3
Flow Tol Ratio= 0.001
Split Flow NTrial= 30
Split Flow Tol= 0.02
Split Flow Ratio= 0.02
Log Output Level= 0
Friction Slope Method= 1
Unsteady Friction Slope Method= 2
Unsteady Bridges Friction Slope Method= 1
Parabolic Critical Depth
Global Vel Dist=  1 , 1 , 1
Global Log Level= 0
CheckData=True
Encroach Param= -1, 0, 0, 0
BEGIN DESCRIPTION:
Multiple Run
END DESCRIPTION:

--- Conroe Lake 064.f01 (steady flow) ---

Flow Title=Multiple
Program Version=4.10
Number of Profiles= 7
Profile Names=10-year,25-year,50-year,1pct_min,100-year,1pct_plu,500-year
River Rch & RM=Conroe Lake 064,Reach-1         ,2825
     481     642     858     378    1143    3452    2095
River Rch & RM=Conroe Lake 064,Reach-1         ,1669
     596     805    1086     483    1459    4406    2714
Boundary for River Rch & Prof#=Conroe Lake 064,Reach-1         , 1
Up Type= 0
Dn Type= 3
Dn Slope=0.01
Boundary for River Rch & Prof#=Conroe Lake 064,Reach-1         , 2
Up Type= 0
Dn Type= 3
Dn Slope=0.01
Boundary for River Rch & Prof#=Conroe Lake 064,Reach-1         , 3
Up Type= 0
Dn Type= 3
Dn Slope=0.01
Boundary for River Rch & Prof#=Conroe Lake 064,Reach-1         , 4
Up Type= 0
Dn Type= 3
Dn Slope=0.01
Boundary for River Rch & Prof#=Conroe Lake 064,Reach-1         , 5
Up Type= 0
Dn Type= 3
Dn Slope=0.01
Boundary for River Rch & Prof#=Conroe Lake 064,Reach-1         , 6
Up Type= 0
Dn Type= 3
Dn Slope=0.01
Boundary for River Rch & Prof#=Conroe Lake 064,Reach-1         , 7
Up Type= 0
Dn Type= 3
Dn Slope=0.01
DSS Import GetInterval= 0
DSS Import GetPeak= 0
DSS Import FillOption= 0

--- Conroe Lake 064.f02 (steady flow) ---

Flow Title=Orig_BLE_Flow
Program Version=4.10
Number of Profiles= 7
Profile Names=10-year,25-year,50-year,1pct_min,100-year,1pct_plu,500-year
River Rch & RM=Conroe Lake 064,Reach-1         ,2825
     481     629     746     291     879    2656    1218
River Rch & RM=Conroe Lake 064,Reach-1         ,1669
     596     789     944     371    1122    3387    1578
Boundary for River Rch & Prof#=Conroe Lake 064,Reach-1         , 1
Up Type= 0
Dn Type= 3
Dn Slope=0.005
Boundary for River Rch & Prof#=Conroe Lake 064,Reach-1         , 2
Up Type= 0
Dn Type= 3
Dn Slope=0.005
Boundary for River Rch & Prof#=Conroe Lake 064,Reach-1         , 3
Up Type= 0
Dn Type= 3
Dn Slope=0.005
Boundary for River Rch & Prof#=Conroe Lake 064,Reach-1         , 4
Up Type= 0
Dn Type= 3
Dn Slope=0.005
Boundary for River Rch & Prof#=Conroe Lake 064,Reach-1         , 5
Up Type= 0
Dn Type= 3
Dn Slope=0.005
Boundary for River Rch & Prof#=Conroe Lake 064,Reach-1         , 6
Up Type= 0
Dn Type= 3
Dn Slope=0.005
Boundary for River Rch & Prof#=Conroe Lake 064,Reach-1         , 7
Up Type= 0
Dn Type= 3
Dn Slope=0.005
DSS Import GetInterval= 0
DSS Import GetPeak= 0
DSS Import FillOption= 0

--- Conroe Lake 064.g01 (geometry) ---

Geom Title=Existing Conditions
Program Version=4.10

River Reach=Conroe Lake 064 ,Reach-1
Reach XY= 30
      3809980.72     10201523.17      3810071.73     10201562.18
      3810088.45     10201623.48      3810138.29     10201661.36
      3810124.83     10201751.16      3810141.76     10201817.61
      3810101.22     10201890.05      3810058.17     10202046.99
      3810087.94     10202219.52      3810069.71     10202257.28
      3810077.52     10202348.43      3809966.69     10202485.24
      3809845.86     10202729.51       3809771.9     10202753.47
      3809732.31     10202693.05      3809680.75     10202699.82
      3809653.67     10202731.59      3809625.54     10202791.49
      3809639.09     10202863.36      3809626.59     10202912.84
      3809560.96     10203010.76      3809576.59     10203060.24
      3809523.98     10203119.61      3809451.07     10203119.61
      3809341.17     10203258.16      3809244.81     10203305.55
      3809081.27     10203317.01      3809062.52     10203432.11
       3809000.2     10203512.28      3808980.44      10203609.1

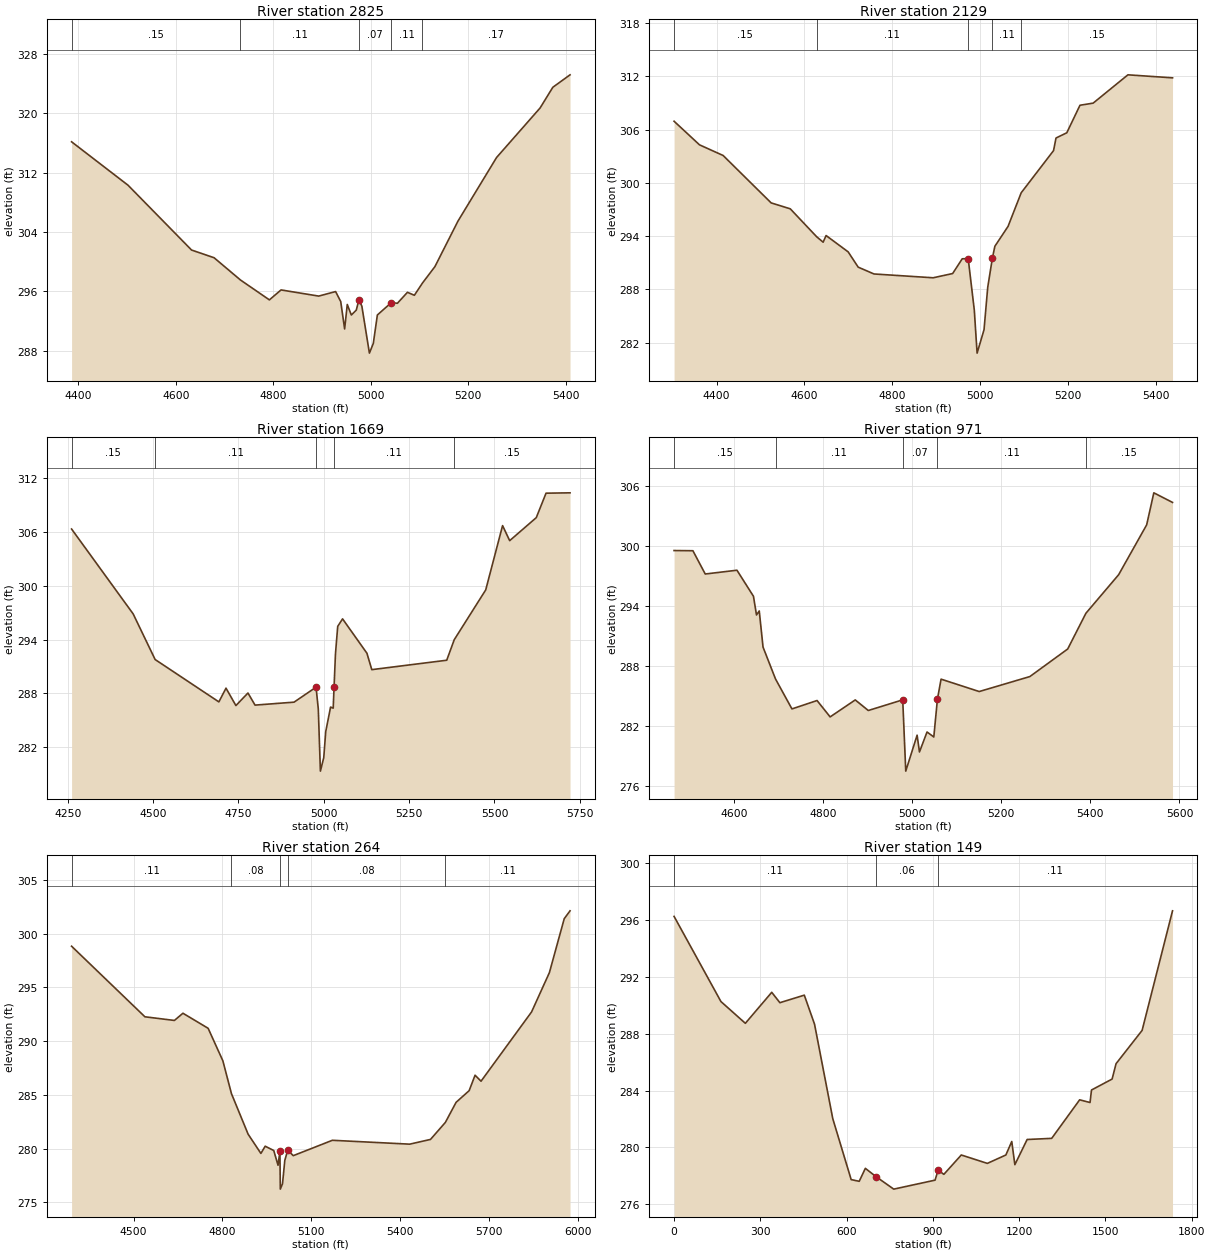
Type RM Length L Ch R = 1 ,2825    ,696,696,696
BEGIN DESCRIPTION:
Conroe Lake 064 4.0
END DESCRIPTION:
XS GIS Cut Line= 3
      3809517.84     10201361.07      3810084.74     10201595.62
       3810482.2     10201690.35
#Sta/Elev= 30
  4386.5  316.15  4502.2   310.3  4632.5  301.56  4678.7  300.52  4732.8  297.52
  4792.1  294.84    4816  296.18  4893.2  295.35  4927.9  295.96  4938.4  294.61
  4946.4  290.92  4951.8  294.22  4960.1   292.8  4970.3  293.46  4975.7  294.86
  4981.7     294  4997.2  287.66  5005.2  288.97  5013.5   292.8  5042.1  294.47
  5054.6  294.38  5075.2  295.86  5089.4  295.46    5106  297.11  5131.5  299.32
  5178.8  305.46  5257.9  314.03  5347.3  320.72  5373.3   323.5  5408.6  325.18
#Mann= 5 ,-1 , 0
  4386.5     .15       0  4732.8     .11       0  4975.7     .07       0
  5042.1     .11       0    5106     .17       0
Bank Sta=4975.7,5042.1
XS Rating Curve= 0 ,0
Exp/Cntr=0.3,0.1

Type RM Length L Ch R = 1 ,2129    ,460,460,460
BEGIN DESCRIPTION:
Conroe Lake 064 3.0
END DESCRIPTION:
XS GIS Cut Line= 3
      3809469.79     10201899.42      3810081.43     10202233.84
       3810490.9      10202391.3
#Sta/Elev= 30
  4302.9  306.95  4360.9  304.29  4414.7  303.09  4524.1  297.75  4567.7  297.08
  4627.5  293.95  4642.6  293.32  4649.3  294.07  4699.6  292.23  4722.4  290.51
  4758.4  289.74  4893.3  289.31  4937.7  289.79  4959.5  291.45  4973.1  291.47
    4987  285.68  4993.4  280.82  5009.2  283.46  5017.6  288.23  5028.3  291.55
  5033.9  292.86  5063.9   295.1  5093.9  298.89  5167.6  303.64  5173.2  305.06
  5197.8  305.65  5227.8  308.75  5257.8  308.99  5337.1  312.18  5438.7  311.84
#Mann= 5 ,-1 , 0
  4302.9     .15       0  4627.5     .11       0  4973.1     .07       0
  5028.3     .11       0  5093.9     .15       0
Bank Sta=4973.1,5028.3
XS Rating Curve= 0 ,0
Exp/Cntr=0.3,0.1

Type RM Length L Ch R = 1 ,1669    ,698,698,698
BEGIN DESCRIPTION:
Conroe Lake 064 2.0
END DESCRIPTION:
XS GIS Cut Line= 3
      3809314.82     10202180.07      3809900.54     10202630.03
      3810370.26     10203177.56
#Sta/Elev= 30
  4261.4  306.34  4441.8  296.86  4506.1  291.77  4692.8  287.04  4713.7  288.57
  4742.7  286.63    4778  288.03  4798.8  286.68    4913  287.01  4977.4  288.68
    4984  286.26  4990.2  279.31    5000  280.82  5005.8  283.72    5020  286.46
  5027.7  286.34 5030.27  288.74  5034.3  292.39  5040.9  295.47  5055.1  296.31
  5126.5  292.47  5140.7  290.64  5360.2  291.69  5382.2  293.98  5474.4  299.54
  5523.8  306.72  5544.6  305.04  5622.5  307.61  5651.1  310.34  5721.4  310.38
#Mann= 5 ,-1 , 0
  4261.4     .15       0  4506.1     .11       0  4977.4     .07       0
 5030.27     .11       0  5382.2     .15       0
Bank Sta=4977.4,5030.27
XS Rating Curve= 0 ,0
Exp/Cntr=0.3,0.1

Type RM Length L Ch R = 1 ,971     ,707,707,707
BEGIN DESCRIPTION:
Conroe Lake 064 1.0
END DESCRIPTION:
XS GIS Cut Line= 3
      3809123.69      10202716.8      3809556.27     10203031.59
      3810113.19     10203208.69
#Sta/Elev= 30
    4465  299.55  4507.3  299.53    4535   297.2  4606.2  297.58  4643.3  294.97
  4650.1   293.1  4656.3   293.5  4664.8  289.88  4692.8  286.69  4729.7  283.69
  4786.1  284.53  4815.5  282.89  4871.9  284.59  4901.2  283.53  4978.5   284.6
  4985.3  277.46  5010.8  281.06  5016.1  279.38  5033.1  281.38  5048.3  280.88
 5056.39  284.65  5064.6  286.67  5150.3  285.43    5264  286.93    5349  289.69
  5389.9  293.27  5463.4  297.13  5526.3  302.12  5542.4  305.33  5584.4  304.37
#Mann= 5 ,-1 , 0
    4465     .15       0  4692.8     .11       0  4978.5     .07       0
 5056.39     .11       0  5389.9     .15       0
Bank Sta=4978.5,5056.39
XS Rating Curve= 0 ,0
Exp/Cntr=0.3,0.1

Type RM Length L Ch R = 1 ,264     ,217,217,217
BEGIN DESCRIPTION:
Conroe Lake 064 1.5
END DESCRIPTION:
XS GIS Cut Line= 3
      3808507.39     10202933.84      3809067.29     10203369.94
      3810037.33     10203281.06
#Sta/Elev= 30
  4290.3  298.82    4538  292.26  4637.6  291.92  4666.5  292.59  4751.6  291.19
  4801.3  288.17  4830.3  285.12  4886.6  281.35  4929.8  279.56  4944.3  280.23
  4973.2  279.83  4987.7  278.46    4994  279.76  4995.4  276.24  5002.8  276.74
  5010.6  278.92  5020.6  279.86  5039.1  279.35  5171.2  280.78  5432.4  280.42
  5502.7  280.86  5552.9  282.44  5589.2  284.31  5633.2  285.39  5653.3  286.83
  5673.4  286.27  5844.1  292.71  5904.3  296.36  5954.5  301.38  5974.1  302.11
#Mann= 5 ,-1 , 0
  4290.3     .11       0  4830.3     .08       0    4994     .06       0
  5020.6     .08       0  5552.9     .11       0
Bank Sta=4994,5020.6
XS Rating Curve= 0 ,0
Exp/Cntr=0.3,0.1

Type RM Length L Ch R = 1 ,149     ,0,0,0
XS GIS Cut Line= 3
      3808502.99      10203055.4      3808988.48     10203563.71
      3809992.57     10203331.44
#Sta/Elev= 30
       0  296.25     163  290.26   247.9  288.73   339.7  290.91     368  290.18
   452.9  290.71   488.5  288.67     552  282.02   615.9  277.74   643.9  277.62
   665.2  278.53   702.9  277.94   763.9  277.07   907.5   277.7   918.6   278.4
   938.3  278.11   998.9  279.47  1089.5  278.88  1153.9  279.47  1174.4  280.42
  1185.2  278.79  1227.9  280.56  1313.3  280.64  1410.5  283.35  1446.6  283.16
  1451.7  284.04  1523.4  284.81  1537.1  285.89  1627.7  288.23  1733.5  296.64
#Mann= 3 , 0 , 0
       0     .11       0   702.9     .06       0   918.6     .11       0
Bank Sta=702.9,918.6
XS Rating Curve= 0 ,0
Exp/Cntr=0.3,0.1

Chan Stop Cuts=-1
Use User Specified Reach Order=0
Composite Channel Slope=5