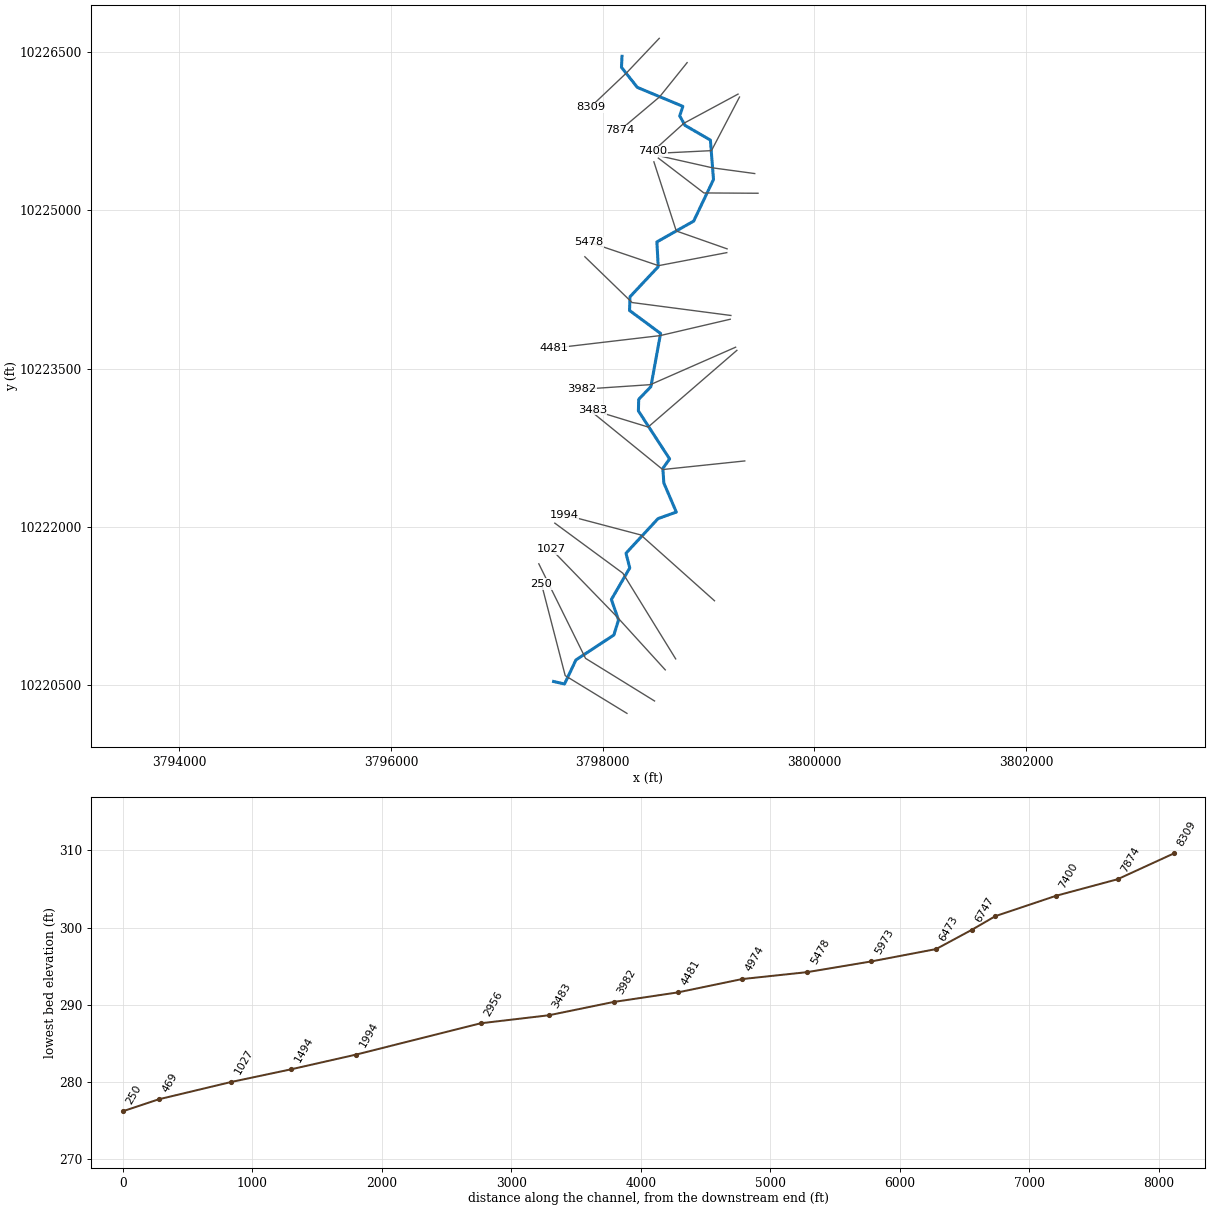
--- Conroe Lake 065.prj (project) ---

Proj Title=Conroe Lake 065 Base Level Engineering
Current Plan=p01
Default Exp/Contr=0.3,0.1
English Units
Geom File=g01
Flow File=f01
Flow File=f02
Plan File=p01
Y Axis Title=Elevation
X Axis Title(PF)=Main Channel Distance
X Axis Title(XS)=Station
BEGIN DESCRIPTION:
Conroe Lake 065
END DESCRIPTION:
DSS Export Rating Curves= 0
DSS Export Rating Curve Sorted= 0
DSS Export Volume Flow Curves= 0
DXF OffsetX= 0
DXF OffsetY= 0
DXF ScaleX= 1
DXF ScaleY= 10

--- Conroe Lake 065.p01 (plan) ---

Plan Title=Multiple Run
Short Identifier=Multiple
Geom File=g01
Flow File=f01
Subcritical Flow
K Sum by GR= 0
Std Step Tol= 0.01
Critical Tol= 0.01
Num of Std Step Trials= 20
Max Error Tol= 0.3
Flow Tol Ratio= 0.001
Split Flow NTrial= 30
Split Flow Tol= 0.02
Split Flow Ratio= 0.02
Log Output Level= 0
Friction Slope Method= 1
Unsteady Friction Slope Method= 2
Unsteady Bridges Friction Slope Method= 1
Parabolic Critical Depth
Global Vel Dist=  1 , 1 , 1
Global Log Level= 0
CheckData=True
Encroach Param= -1, 0, 0, 0
BEGIN DESCRIPTION:
Multiple Run
END DESCRIPTION:

--- Conroe Lake 065.f01 (steady flow) ---

Flow Title=Multiple
Program Version=4.10
Number of Profiles= 7
Profile Names=10-year,25-year,50-year,1pct_min,100-year,1pct_plu,500-year
River Rch & RM=Conroe Lake 065,Reach-1         ,8309
     612     826    1117     497    1500    4530    2797
River Rch & RM=Conroe Lake 065,Reach-1         ,6473
    1296    1811    2499    1131    3416   10316    6608
Boundary for River Rch & Prof#=Conroe Lake 065,Reach-1         , 1
Up Type= 0
Dn Type= 3
Dn Slope=0.003
Boundary for River Rch & Prof#=Conroe Lake 065,Reach-1         , 2
Up Type= 0
Dn Type= 3
Dn Slope=0.003
Boundary for River Rch & Prof#=Conroe Lake 065,Reach-1         , 3
Up Type= 0
Dn Type= 3
Dn Slope=0.003
Boundary for River Rch & Prof#=Conroe Lake 065,Reach-1         , 4
Up Type= 0
Dn Type= 3
Dn Slope=0.003
Boundary for River Rch & Prof#=Conroe Lake 065,Reach-1         , 5
Up Type= 0
Dn Type= 3
Dn Slope=0.003
Boundary for River Rch & Prof#=Conroe Lake 065,Reach-1         , 6
Up Type= 0
Dn Type= 3
Dn Slope=0.003
Boundary for River Rch & Prof#=Conroe Lake 065,Reach-1         , 7
Up Type= 0
Dn Type= 3
Dn Slope=0.003
DSS Import GetInterval= 0
DSS Import GetPeak= 0
DSS Import FillOption= 0

--- Conroe Lake 065.f02 (steady flow) ---

Flow Title=Orig_BLE_Flow
Program Version=4.10
Number of Profiles= 7
Profile Names=10-year,25-year,50-year,1pct_min,100-year,1pct_plu,500-year
River Rch & RM=Conroe Lake 065,Reach-1         ,8309
     612     810     971     382    1154    3485    1626
River Rch & RM=Conroe Lake 065,Reach-1         ,6473
    1296    1775    2173     870    2628    7937    3842
Boundary for River Rch & Prof#=Conroe Lake 065,Reach-1         , 1
Up Type= 0
Dn Type= 3
Dn Slope=0.003
Boundary for River Rch & Prof#=Conroe Lake 065,Reach-1         , 2
Up Type= 0
Dn Type= 3
Dn Slope=0.003
Boundary for River Rch & Prof#=Conroe Lake 065,Reach-1         , 3
Up Type= 0
Dn Type= 3
Dn Slope=0.003
Boundary for River Rch & Prof#=Conroe Lake 065,Reach-1         , 4
Up Type= 0
Dn Type= 3
Dn Slope=0.003
Boundary for River Rch & Prof#=Conroe Lake 065,Reach-1         , 5
Up Type= 0
Dn Type= 3
Dn Slope=0.003
Boundary for River Rch & Prof#=Conroe Lake 065,Reach-1         , 6
Up Type= 0
Dn Type= 3
Dn Slope=0.003
Boundary for River Rch & Prof#=Conroe Lake 065,Reach-1         , 7
Up Type= 0
Dn Type= 3
Dn Slope=0.003
DSS Import GetInterval= 0
DSS Import GetPeak= 0
DSS Import FillOption= 0

--- Conroe Lake 065.g01 (geometry) ---

Geom Title=Existing Conditions
Program Version=4.10

River Reach=Conroe Lake 065 ,Reach-1
Reach XY= 30
      3798183.23     10226461.84      3798178.23     10226356.84
      3798328.23     10226166.84      3798758.23     10225986.84
      3798728.23     10225896.84      3798778.23     10225806.84
      3799018.23     10225666.84       3799047.6     10225293.03
      3798860.19      10224898.3       3798512.7     10224700.89
      3798525.54     10224466.05      3798258.73     10224180.61
      3798254.46      10224050.6      3798547.55     10223832.58
      3798455.85     10223327.67      3798340.86     10223207.55
      3798338.17     10223097.83      3798632.95     10222642.31
      3798568.85     10222552.47      3798578.42     10222413.92
       3798696.3     10222138.17      3798523.33     10222075.83
       3798220.9     10221747.61      3798256.59     10221608.22
      3798082.64     10221308.65      3798150.29      10221114.7
      3798106.33     10220971.79      3797748.14     10220735.64
      3797640.36     10220507.41      3797537.23     10220530.96

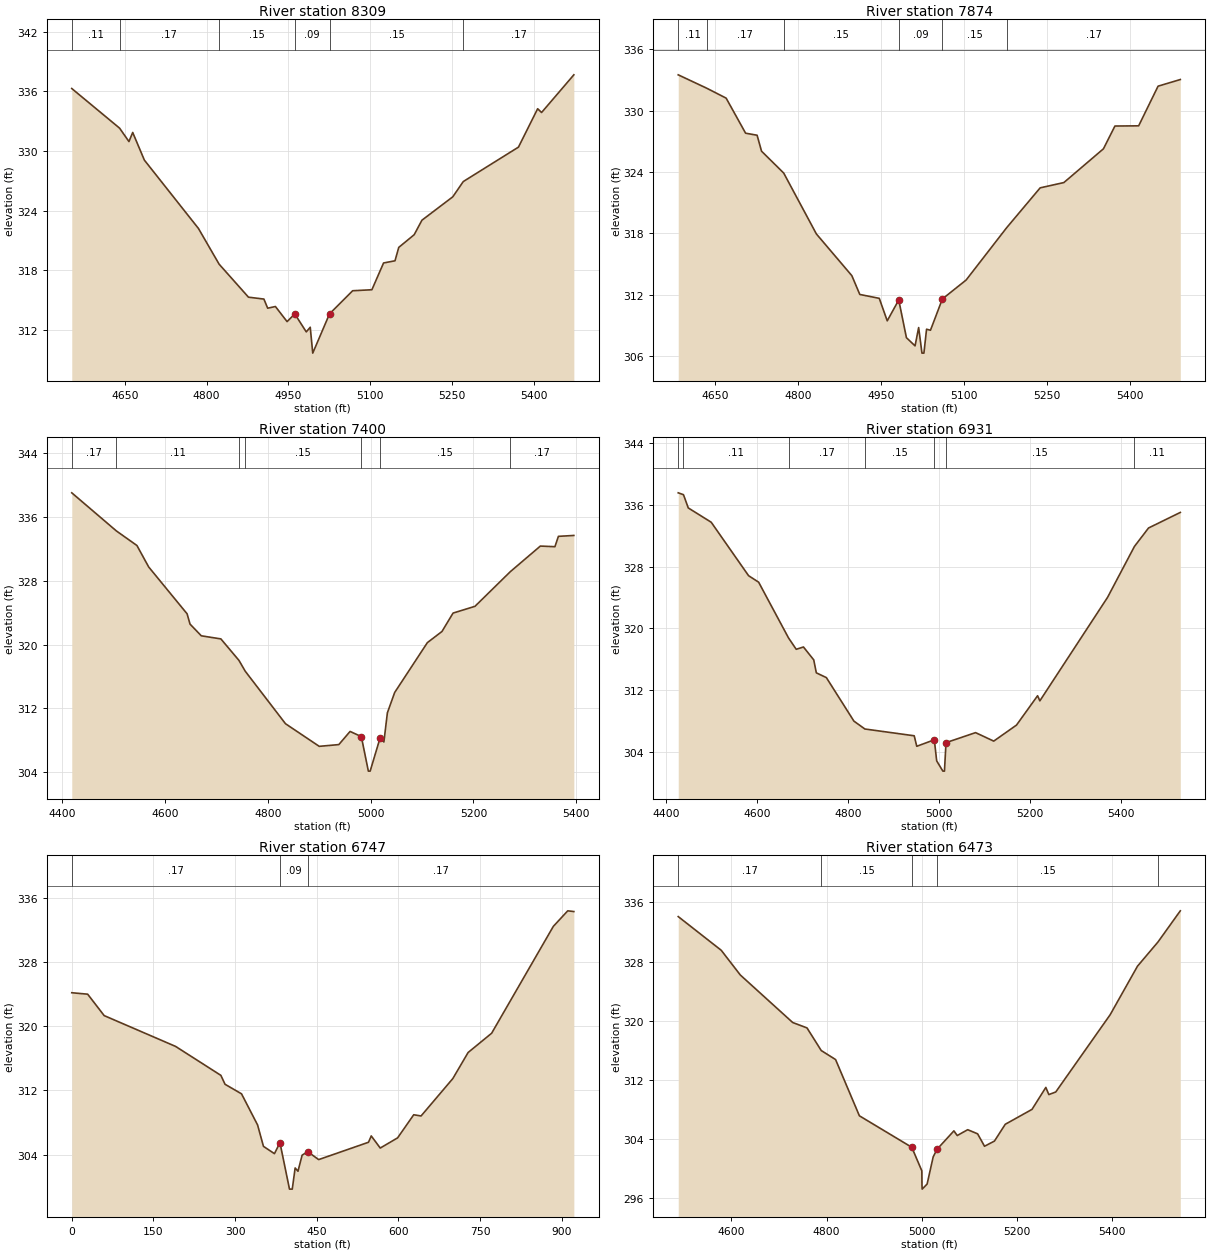
Type RM Length L Ch R = 1 ,8309    ,435,435,435
BEGIN DESCRIPTION:
Conroe Lake 065 17.0
END DESCRIPTION:
XS GIS Cut Line= 3
      3798535.03     10226632.21      3798228.23     10226306.84
      3797885.22     10225979.85
#Sta/Elev= 30
  4552.8   336.3  4640.6   332.3  4657.7  330.95  4664.6  331.87    4686  329.08
  4785.2  322.19  4823.1  318.59    4877  315.26  4905.3  315.07  4912.2  314.15
  4926.4  314.32  4947.8   312.8    4962  313.57    4983  311.76  4990.3  312.23
  4994.9  309.62  5025.7  313.58  5068.1  315.91  5103.4  316.01  5124.8  318.71
  5145.8  318.93  5152.7  320.28    5181  321.56  5195.2  323.02  5251.8  325.38
  5271.1  326.92  5372.3  330.39  5407.5  334.26  5414.7  333.88  5473.9  337.68
#Mann= 6 ,-1 , 0
  4552.8     .11       0  4640.6     .17       0  4823.1     .15       0
    4962     .09       0  5025.7     .15       0  5271.1     .17       0
Bank Sta=4962,5025.7
XS Rating Curve= 0 ,0
Exp/Cntr=0.3,0.1

Type RM Length L Ch R = 1 ,7874    ,474,474,474
BEGIN DESCRIPTION:
Conroe Lake 065 16.0
END DESCRIPTION:
XS GIS Cut Line= 3
      3798798.47     10226401.78      3798538.23     10226076.84
      3798163.01     10225759.38
#Sta/Elev= 30
  4583.7   333.5  4635.6  332.18  4670.3  331.22  4705.5  327.79  4726.3  327.59
  4734.3  326.03  4774.4  323.89  4833.5  317.93  4897.6  313.85    4912  312.01
  4947.2  311.63  4961.6  309.43  4982.4  311.47  4996.3  307.78  5011.9  306.98
  5018.4  308.77  5024.4  306.27  5027.9  306.27  5032.7  308.61  5039.8  308.51
  5061.3  311.57  5104.2  313.42  5177.8  318.56  5238.1  322.44    5281  322.96
  5352.5  326.26  5373.3  328.49  5416.2  328.51  5451.3  332.39  5491.5  333.04
#Mann= 6 ,-1 , 0
  4583.7     .11       0  4635.6     .17       0  4774.4     .15       0
  4982.4     .09       0  5061.3     .15       0  5177.8     .17       0
Bank Sta=4982.4,5061.3
XS Rating Curve= 0 ,0
Exp/Cntr=0.3,0.1

Type RM Length L Ch R = 1 ,7400    ,469,469,469
BEGIN DESCRIPTION:
Conroe Lake 065 15.0
END DESCRIPTION:
XS GIS Cut Line= 3
      3799279.33     10226103.13      3798768.23     10225826.84
      3798475.52     10225561.47
#Sta/Elev= 30
    4419  339.05  4505.7  334.27  4545.7  332.44  4568.5  329.75  4643.2  323.87
  4648.9  322.58  4670.8  321.11  4708.9  320.72  4744.1  318.02  4756.2  316.67
  4834.5  310.08  4900.1  307.24  4938.2  307.46  4960.1  309.11    4982  308.46
  4995.6  304.13  4999.1  304.13  5018.4  308.29  5025.8  307.79  5032.6  311.45
  5046.8     314  5110.3  320.25  5138.7  321.65  5160.3  323.96  5202.9  324.81
  5271.5  329.15    5330  332.37  5358.3  332.29  5365.1  333.59  5395.1   333.7
#Mann= 7 ,-1 , 0
    4419     .17       0  4505.7     .11       0  4744.1     .17       0
  4756.2     .15       0    4982     .09       0  5018.4     .15       0
  5271.5     .17       0
Bank Sta=4982,5018.4
XS Rating Curve= 0 ,0
Exp/Cntr=0.3,0.1

Type RM Length L Ch R = 1 ,6931    ,184,184,184
BEGIN DESCRIPTION:
Conroe Lake 065 14.0
END DESCRIPTION:
XS GIS Cut Line= 3
      3799293.22     10226075.34      3799028.23     10225566.84
      3798498.08     10225540.64
#Sta/Elev= 30
  4426.6  337.56  4438.1  337.32  4448.7   335.6  4499.1  333.75  4581.3  326.82
  4603.4  325.98  4669.2  318.75  4686.1  317.28    4702  317.58  4724.6  315.91
  4730.3  314.23  4752.4  313.61    4813  307.97  4837.1  306.95  4945.6  306.07
  4951.2  304.71  4989.8  305.55    4995  302.82  5008.6  301.49  5012.1  301.49
  5015.5  305.18  5080.5  306.48  5120.5  305.38  5170.6  307.46  5216.9  311.26
  5221.9   310.6  5370.8  324.01  5429.9  330.61  5460.9     333  5530.8  335.02
#Mann= 7 ,-1 , 0
  4426.6     .17       0  4438.1     .11       0  4669.2     .17       0
  4837.1     .15       0  4989.8     .09       0  5015.5     .15       0
  5429.9     .11       0
Bank Sta=4989.8,5015.5
XS Rating Curve= 0 ,0
Exp/Cntr=0.3,0.1

Type RM Length L Ch R = 1 ,6747    ,274,274,274
XS GIS Cut Line= 3
      3799436.77     10225349.48      3799038.22     10225403.71
      3798529.22     10225518.75
#Sta/Elev= 30
       0  324.18    29.2     324    59.5  321.33   190.7  317.49   273.9  313.88
   281.5  312.77   311.8  311.58   341.3   307.7   352.1  305.03   372.3  304.12
   382.4  305.49   399.9   299.7     405   299.7   410.3  302.34   415.5  301.93
   423.1  303.93   433.4  304.37   453.5  303.38     545  305.54   550.1  306.33
   566.6  304.82   598.5  306.09   628.1  308.97   641.6  308.82   699.9  313.48
     728  316.73   771.2  319.13   884.5  332.45     911  334.39   922.2   334.3
#Mann= 3 , 0 , 0
       0     .17       0   382.4     .09       0   433.4     .17       0
Bank Sta=382.4,433.4
XS Rating Curve= 0 ,0
Exp/Cntr=0.3,0.1

Type RM Length L Ch R = 1 ,6473    ,500,500,500
BEGIN DESCRIPTION:
Conroe Lake 065 13.0
END DESCRIPTION:
XS GIS Cut Line= 3
      3799468.14     10225162.66      3798956.75     10225165.53
      3798526.59     10225496.25
#Sta/Elev= 30
  4488.6  334.09  4578.9  329.53  4618.9  326.19  4728.9  319.76  4758.9  319.03
  4788.8  315.97  4818.9  314.75  4868.9  307.14  4978.9  302.88    5000  299.69
  5000.3  297.72  5000.7  297.22  5011.1  297.91  5023.8  301.58  5031.9  302.61
  5067.3   305.1  5074.3  304.47  5096.3  305.26  5117.1   304.7  5131.6  303.02
  5152.4  303.72  5175.1  305.99  5231.3  308.01  5260.3  310.98  5266.6  310.01
  5281.1  310.36  5395.3  320.81  5452.7  327.38  5495.8  330.66  5542.6  334.87
#Mann= 5 ,-1 , 0
  4488.6     .17       0  4788.8     .15       0  4978.9     .09       0
  5031.9     .15       0  5495.8     .11       0
Bank Sta=4978.9,5031.9
XS Rating Curve= 0 ,0
Exp/Cntr=0.3,0.1

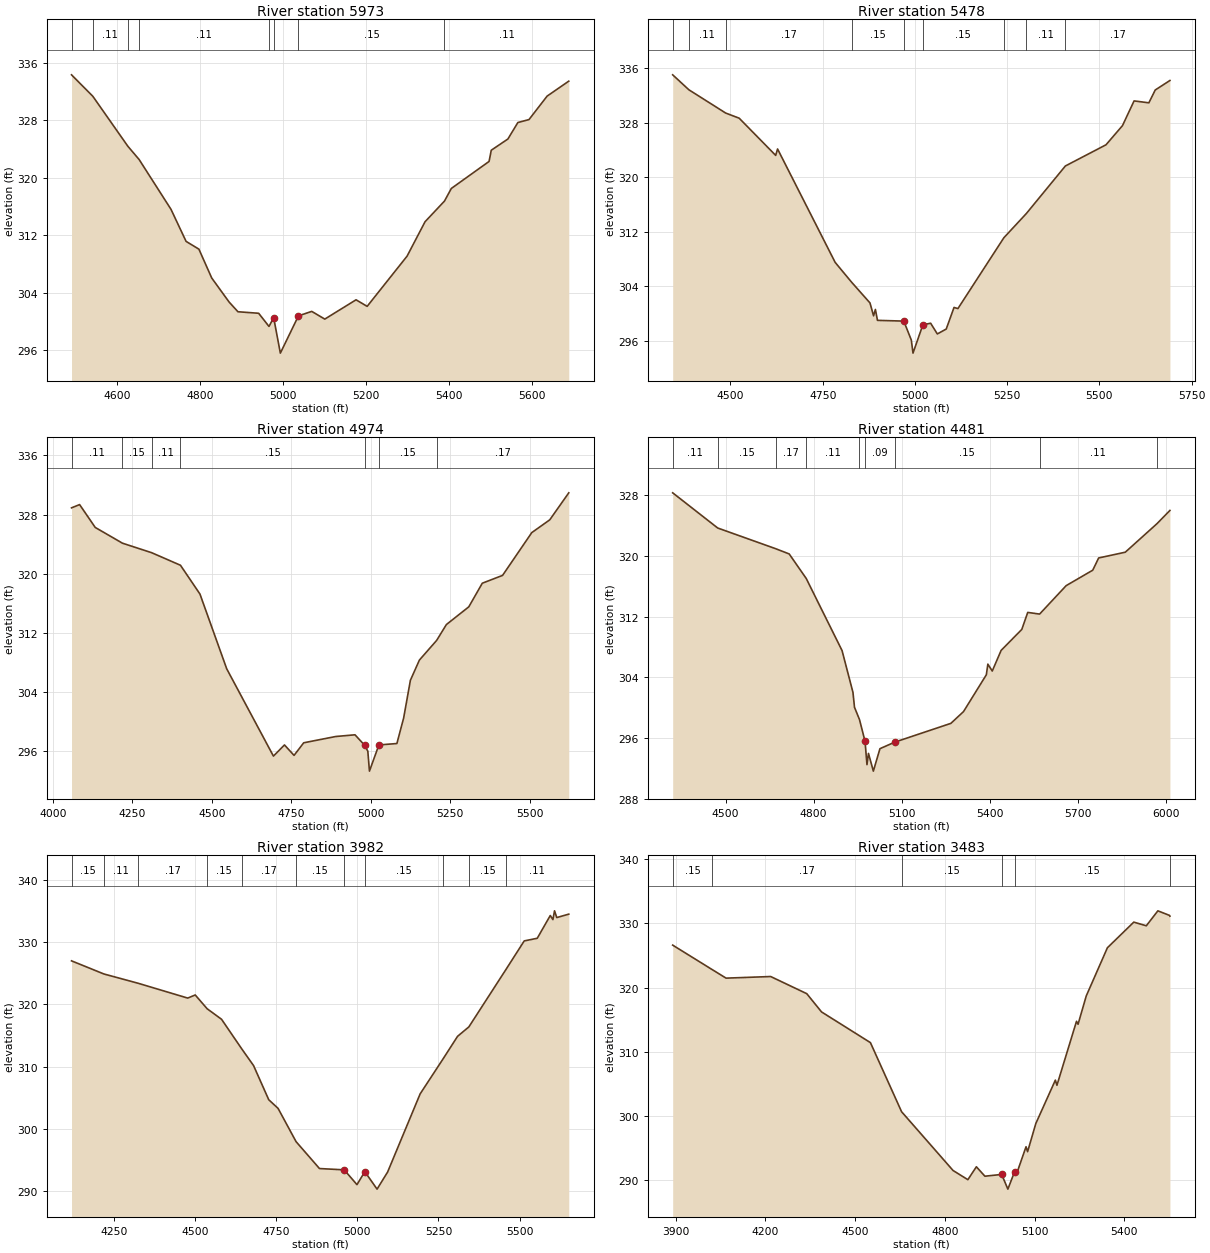
Type RM Length L Ch R = 1 ,5973    ,495,495,495
BEGIN DESCRIPTION:
Conroe Lake 065 12.0
END DESCRIPTION:
XS GIS Cut Line= 3
      3799176.01     10224635.13      3798695.89     10224804.74
      3798484.56     10225460.74
#Sta/Elev= 30
  4490.8   334.3  4542.1  331.32  4626.6  324.37  4653.7  322.53  4730.6   315.6
  4766.9  311.15  4797.8  310.07  4828.7  306.06  4870.6  302.72  4891.9  301.37
  4941.8  301.16  4966.7  299.33    4978  300.54  4994.1  295.62  5037.7   300.8
  5069.7  301.42  5101.2  300.35  5176.5  303.03  5203.3  302.12  5299.5   309.1
  5342.8  313.88  5389.6  316.75  5406.2  318.51  5497.1  322.26  5502.4  323.82
  5542.5  325.38  5566.5  327.67  5593.3  328.08    5637  331.34  5689.2  333.42
#Mann= 8 ,-1 , 0
  4490.8     .17       0  4542.1     .11       0  4626.6     .17       0
  4653.7     .11       0  4966.7     .15       0    4978     .09       0
  5037.7     .15       0  5389.6     .11       0
Bank Sta=4978,5037.7
XS Rating Curve= 0 ,0
Exp/Cntr=0.3,0.1

Type RM Length L Ch R = 1 ,5478    ,504,504,504
BEGIN DESCRIPTION:
Conroe Lake 065 11.0
END DESCRIPTION:
XS GIS Cut Line= 3
      3799173.07     10224599.35      3798528.09     10224475.82
      3797873.81     10224698.39
#Sta/Elev= 30
  4343.3  334.99  4387.2   332.8    4487  329.39  4523.5  328.64  4622.5  323.19
  4627.6  324.13  4783.7  307.52  4828.4  304.61  4878.1  301.58  4887.8  299.69
  4892.8  300.63  4898.4  299.03  4969.7  298.92  4990.1  296.15  4994.7  294.23
  5021.4  298.37  5042.5  298.61  5060.6  297.04  5084.8  297.76  5105.9  300.92
  5116.4  300.75    5241  311.13    5302  314.68  5407.7  321.64  5517.8  324.74
  5562.5  327.55  5593.9  331.17    5634  330.89  5651.3  332.77  5691.1  334.16
#Mann= 9 ,-1 , 0
  4343.3     .17       0  4387.2     .11       0    4487     .17       0
  4828.4     .15       0  4969.7     .09       0  5021.4     .15       0
    5241     .17       0    5302     .11       0  5407.7     .17       0
Bank Sta=4969.7,5021.4
XS Rating Curve= 0 ,0
Exp/Cntr=0.3,0.1

Type RM Length L Ch R = 1 ,4974    ,493,493,493
BEGIN DESCRIPTION:
Conroe Lake 065 10.0
END DESCRIPTION:
XS GIS Cut Line= 3
      3799211.81     10224003.26      3798278.33     10224125.91
      3797832.38     10224560.09
#Sta/Elev= 30
  4058.5  328.92  4083.9  329.36  4133.1  326.27  4218.8  324.14  4310.3  322.86
  4401.1  321.16  4462.4  317.27  4546.6  307.16  4693.5  295.36  4728.2  296.87
  4758.4  295.46  4788.7  297.16  4889.5  298.01  4950.1  298.24  4980.3  296.83
  4990.4  296.02  4995.5  293.33  5025.2  296.87  5081.8  297.06    5103   300.5
  5124.3  305.61  5152.6  308.34    5207  311.01  5237.4  313.14    5308  315.54
  5350.4  318.73  5414.2  319.79    5506  325.57  5562.6   327.3  5622.4  330.95
#Mann= 7 ,-1 , 0
  4058.5     .11       0  4218.8     .15       0  4310.3     .11       0
  4401.1     .15       0  4980.3     .09       0  5025.2     .15       0
    5207     .17       0
Bank Sta=4980.3,5025.2
XS Rating Curve= 0 ,0
Exp/Cntr=0.3,0.1

Type RM Length L Ch R = 1 ,4481    ,499,499,499
BEGIN DESCRIPTION:
Conroe Lake 065 9.0
END DESCRIPTION:
XS GIS Cut Line= 3
      3799205.81     10223967.48      3798543.76     10223812.28
      3797536.76     10223693.29
#Sta/Elev= 30
    4320  328.31  4473.4  323.67  4671.7  320.93  4716.9  320.25  4774.9  317.02
    4897  307.51  4934.2  301.99  4939.4  300.03  4956.4  298.41  4975.3  295.55
  4981.9  292.46    4987  293.95  5003.6  291.61  5026.1  294.57  5076.4  295.43
  5267.8  297.91  5310.8  299.46  5388.6  304.32  5393.7  305.72  5408.7  304.81
  5438.9  307.53  5509.4   310.3  5529.6  312.54    5570  312.32  5660.5  316.07
  5751.1  318.11  5771.2  319.72  5861.9  320.48  5970.1  324.25    6014  325.99
#Mann= 9 ,-1 , 0
    4320     .11       0  4473.4     .15       0  4671.7     .17       0
  4774.9     .11       0  4956.4     .15       0  4975.3     .09       0
  5076.4     .15       0    5570     .11       0  5970.1     .17       0
Bank Sta=4975.3,5076.4
XS Rating Curve= 0 ,0
Exp/Cntr=0.3,0.1

Type RM Length L Ch R = 1 ,3982    ,499,499,499
BEGIN DESCRIPTION:
Conroe Lake 065 8.0
END DESCRIPTION:
XS GIS Cut Line= 3
      3799256.52     10223702.23       3798450.9      10223346.9
      3797800.98     10223302.98
#Sta/Elev= 30
  4119.5  326.96    4219  324.86  4325.1  323.36  4477.5  320.99  4500.6  321.49
  4537.3  319.28  4581.7  317.59  4643.2   312.9  4680.4  310.16  4727.1  304.69
  4755.8  303.31  4811.3  297.97  4883.4  293.66  4959.6  293.45  4998.9  291.08
  5023.1  293.16  5060.8  290.36  5093.3   293.1  5193.5  305.63  5262.6  311.12
  5308.8  314.86  5343.6  316.37  5457.8  325.57  5514.2  330.16  5554.3  330.58
  5594.4  334.23  5602.5  333.57  5607.5  334.98  5614.4   333.9  5651.4  334.45
#Mann= 11 ,-1 , 0
  4119.5     .15       0    4219     .11       0  4325.1     .17       0
  4537.3     .15       0  4643.2     .17       0  4811.3     .15       0
  4959.6     .07       0  5023.1     .15       0  5262.6     .11       0
  5343.6     .15       0  5457.8     .11       0
Bank Sta=4959.6,5023.1
XS Rating Curve= 0 ,0
Exp/Cntr=0.3,0.1

Type RM Length L Ch R = 1 ,3483    ,527,527,527
BEGIN DESCRIPTION:
Conroe Lake 065 7.0
END DESCRIPTION:
XS GIS Cut Line= 3
      3799268.44     10223672.43      3798430.24      10222944.9
      3797902.37     10223107.34
#Sta/Elev= 30
  3890.1  326.63  4022.5  322.81  4068.6  321.49  4217.7  321.74  4338.3  319.07
  4387.7  316.23  4551.1  311.45  4655.3  300.69  4827.4  291.54  4876.8  290.11
  4905.3  292.12  4933.8  290.65  4989.9  290.93  5010.6  288.64  5033.3  291.38
  5038.6  290.87  5071.3  295.24  5076.5  294.47  5103.9  298.84  5169.3  305.61
  5174.6  304.81    5240  314.77  5245.2  314.31  5272.6  318.72  5343.3  326.22
  5431.5  330.21  5473.3  329.64    5512  331.97  5551.2  331.25  5552.3  331.14
#Mann= 6 ,-1 , 0
  3890.1     .15       0  4022.5     .17       0  4655.3     .15       0
  4989.9     .07       0  5033.3     .15       0  5551.2     .17       0
Bank Sta=4989.9,5033.3
XS Rating Curve= 0 ,0
Exp/Cntr=0.3,0.1

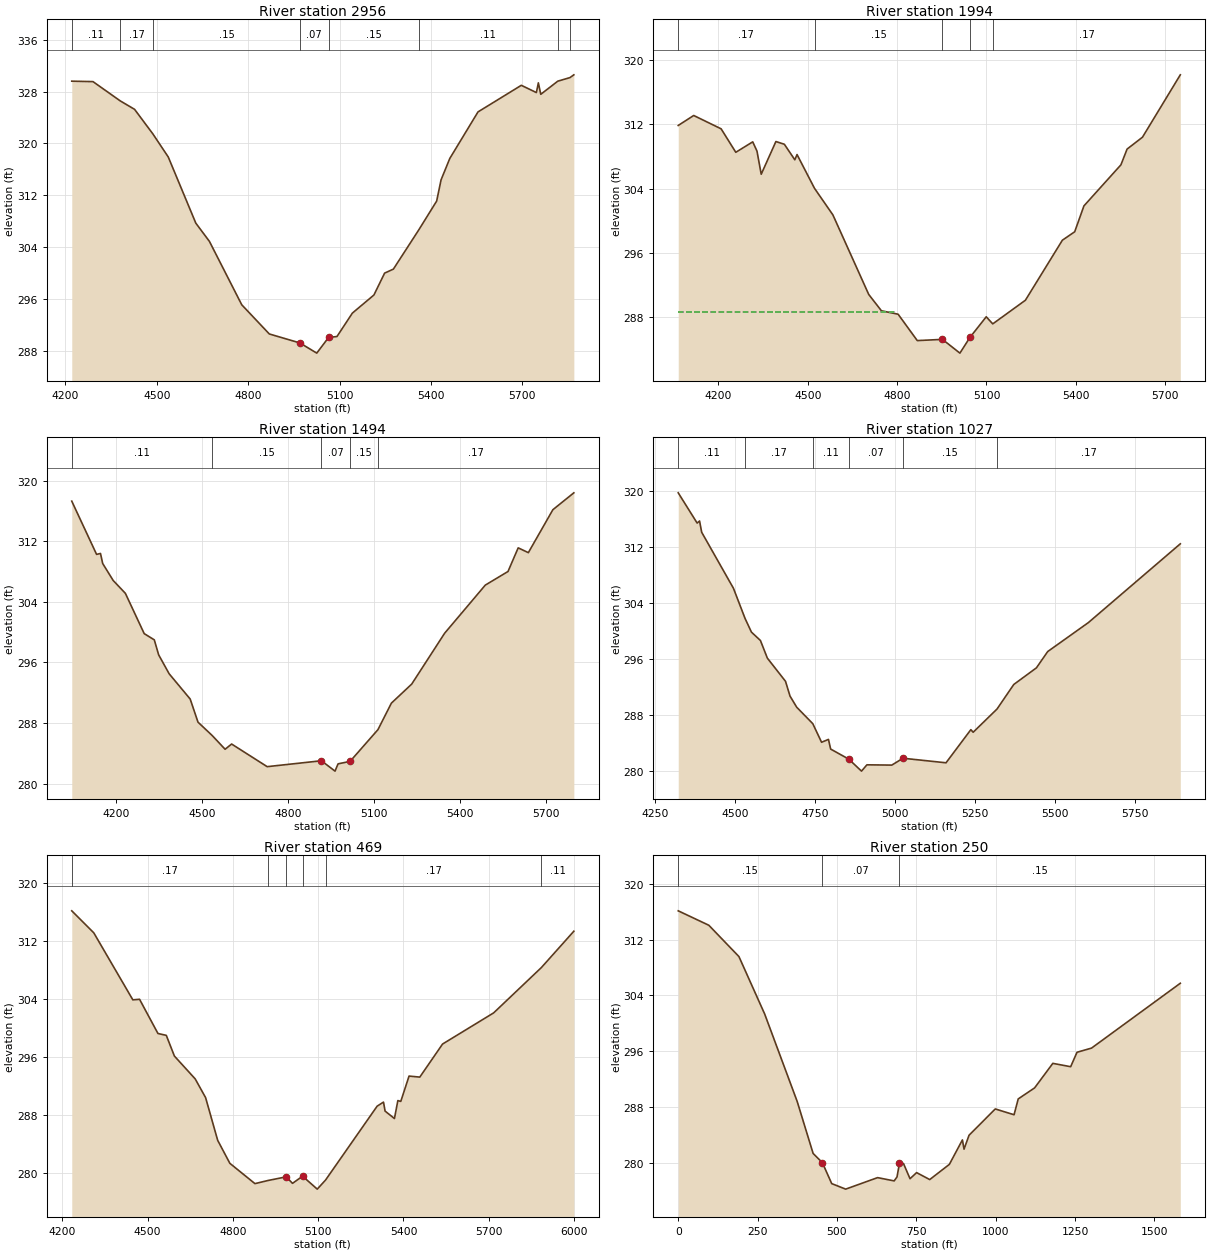
Type RM Length L Ch R = 1 ,2956    ,962,962,962
BEGIN DESCRIPTION:
Conroe Lake 065 6.0
END DESCRIPTION:
XS GIS Cut Line= 3
       3799342.9     10222623.29      3798567.78     10222541.76
      3797894.42     10223091.24
#Sta/Elev= 30
  4220.6  329.61  4290.3  329.54  4379.9  326.56  4426.8  325.26  4486.8  321.47
  4537.4   317.9  4627.9  307.68  4672.6  304.86  4778.7  295.07  4869.2  290.56
  4969.8  289.17    5025   287.6    5064  290.03  5091.3  290.16  5141.9  293.78
  5212.7  296.58  5247.8  299.96  5276.6  300.58    5360  306.64  5418.7  311.09
  5433.1  314.36  5461.8  317.67  5554.4  324.86  5696.6  328.97  5746.1  327.85
  5752.6  329.35  5760.5  327.58  5816.4  329.61  5856.3  330.16  5869.1  330.59
#Mann= 8 ,-1 , 0
  4220.6     .11       0  4379.9     .17       0  4486.8     .15       0
  4969.8     .07       0    5064     .15       0    5360     .11       0
  5816.4     .15       0  5856.3     .17       0
Bank Sta=4969.8,5064
XS Rating Curve= 0 ,0
Exp/Cntr=0.3,0.1

Type RM Length L Ch R = 1 ,1994    ,500,500,500
BEGIN DESCRIPTION:
Conroe Lake 065 4.0
END DESCRIPTION:
XS GIS Cut Line= 3
      3799056.79     10221297.01      3798360.81     10221921.22
      3797635.08     10222113.65
#Sta/Elev= 30
  4065.1  311.87  4117.1  313.11  4209.1  311.45  4258.4  308.53  4315.2  309.83
  4329.5  308.68  4343.7   305.8    4393  309.87  4421.4  309.53  4456.5   307.6
    4464  308.25  4522.6  304.05  4584.4  300.74  4704.7  290.84  4747.3  288.81
  4803.4  288.38  4867.7   285.1  4952.2  285.25  5010.8  283.54  5044.4  285.49
  5099.2  288.06  5121.1  287.18  5230.7  290.12  5354.8  297.59  5396.2  298.64
  5427.2  301.86  5551.4  306.97  5572.1  308.93  5623.8  310.41  5750.8  318.17
#Mann= 5 ,-1 , 0
  4065.1     .17       0  4522.6     .15       0  4952.2     .07       0
  5044.4     .15       0  5121.1     .17       0
#XS Ineff= 2 , 0
       0  4789.2  288.62               0
Permanent Ineff=
       F       F
Bank Sta=4952.2,5044.4
XS Rating Curve= 0 ,0
Exp/Cntr=0.3,0.1

Type RM Length L Ch R = 1 ,1494    ,467,467,467
BEGIN DESCRIPTION:
Conroe Lake 065 3.0
END DESCRIPTION:
XS GIS Cut Line= 3
      3798690.23     10220745.58      3798191.15     10221558.39
      3797548.74     10222033.14
#Sta/Elev= 30
  4046.2   317.3  4132.8  310.27  4146.5  310.39  4154.1  309.07  4190.8  306.82
  4233.4  305.12  4299.1   299.8  4334.3  298.98  4349.4  297.01  4386.1   294.5
  4459.6  291.16  4486.8  288.11  4536.5  286.34  4581.4  284.53  4604.2  285.22
  4728.3  282.23  4917.7  283.01  4965.2  281.64  4975.7   282.6  5017.8  282.93
    5115  287.12  5161.9  290.62  5232.9  293.14  5347.7  299.85  5489.7  306.21
    5569  308.01  5604.5  311.13    5640   310.5  5725.6  316.17  5798.8   318.4
#Mann= 5 ,-1 , 0
  4046.2     .11       0  4536.5     .15       0  4917.7     .07       0
  5017.8     .15       0    5115     .17       0
Bank Sta=4917.7,5017.8
XS Rating Curve= 0 ,0
Exp/Cntr=0.3,0.1

Type RM Length L Ch R = 1 ,1027    ,558,558,558
BEGIN DESCRIPTION:
Conroe Lake 065 2.0
END DESCRIPTION:
XS GIS Cut Line= 3
      3798591.83     10220641.32       3798136.1     10221144.25
      3797515.91     10221785.78
#Sta/Elev= 30
  4321.3  319.71  4380.5  315.39    4388  315.69  4394.7  314.08  4494.1  306.08
  4530.2   301.8  4550.4  299.82  4578.5  298.63  4600.2  296.11    4657   292.8
  4671.1  290.69  4692.1   289.1  4742.4  286.75  4769.8   284.1  4791.4  284.51
  4798.2  283.13    4855  281.69  4894.7  279.98  4911.7  280.88  4989.5  280.84
  5024.7  281.82  5159.2  281.17  5236.9   285.9  5244.1  285.53  5318.7  288.84
  5371.2  292.35    5442  294.72  5477.4  297.05  5604.8  301.19  5892.3  312.43
#Mann= 6 ,-1 , 0
  4321.3     .11       0  4530.2     .17       0  4742.4     .11       0
    4855     .07       0  5024.7     .15       0  5318.7     .17       0
Bank Sta=4855,5024.7
XS Rating Curve= 0 ,0
Exp/Cntr=0.3,0.1

Type RM Length L Ch R = 1 ,469     ,275,275,275
BEGIN DESCRIPTION:
Conroe Lake 065 1.0
END DESCRIPTION:
XS GIS Cut Line= 3
      3798490.49     10220346.24      3797838.73     10220750.61
      3797397.34     10221647.36
#Sta/Elev= 30
    4233  316.22  4310.6  313.17  4447.9  303.91  4471.5  303.99  4536.2  299.26
  4565.6     299  4594.1  296.14  4667.3  292.98  4703.9  290.39  4746.4  284.49
  4789.2  281.31  4877.5   278.5  4921.9  278.92  4987.4  279.44  5009.7  278.54
  5045.1  279.53  5096.7  277.74  5125.8  278.99  5307.4  289.21  5329.8  289.77
  5335.4  288.53  5368.3   287.5  5380.3  289.98  5390.6  289.87  5419.7  293.37
  5457.5  293.23  5537.6   297.8  5717.4  302.11  5885.4  308.38  5999.5   313.4
#Mann= 6 ,-1 , 0
    4233     .17       0  4921.9     .15       0  4987.4     .07       0
  5045.1     .15       0  5125.8     .17       0  5885.4     .11       0
Bank Sta=4987.4,5045.1
XS Rating Curve= 0 ,0
Exp/Cntr=0.3,0.1

Type RM Length L Ch R = 1 ,250     ,0,0,0
XS GIS Cut Line= 3
      3798229.93     10220228.62       3797646.7     10220586.66
      3797422.45     10221456.57
#Sta/Elev= 30
       0  316.12    96.4  314.05   191.2  309.56   272.3  301.32   374.7  288.78
   424.9  281.32     454     280   483.5  276.99   527.5   276.2     628  277.85
   680.2  277.38   689.2  277.95   696.9  279.92   709.6  279.87   730.2  277.69
   750.9  278.57   792.2  277.57   854.1  279.75   895.2  283.26   900.3  281.93
   916.1  283.93   998.7   287.7  1057.9  286.87    1071  289.14  1122.6  290.72
    1180  294.24  1236.2  293.76  1256.2  295.83    1302  296.43  1581.6  305.73
#Mann= 3 , 0 , 0
       0     .15       0     454     .07       0   696.9     .15       0
Bank Sta=454,696.9
XS Rating Curve= 0 ,0
Exp/Cntr=0.3,0.1

Chan Stop Cuts=-1
Use User Specified Reach Order=0
Composite Channel Slope=5