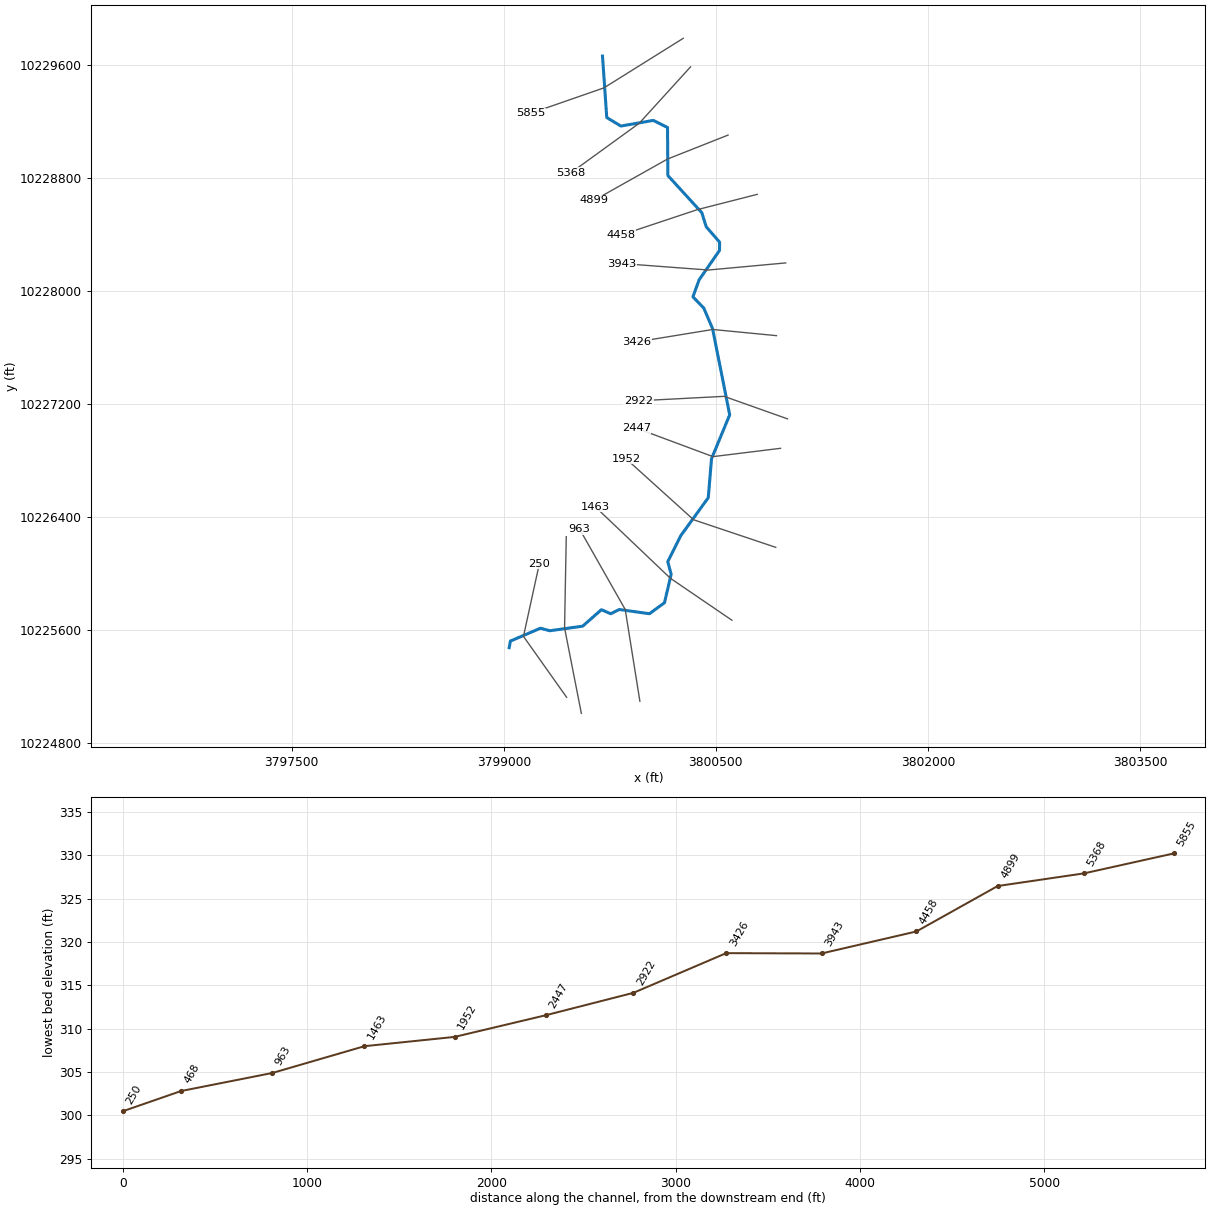
--- Conroe Lake 066.prj (project) ---

Proj Title=Conroe Lake 066 Base Level Engineering
Current Plan=p01
Default Exp/Contr=0.3,0.1
English Units
Geom File=g01
Flow File=f01
Flow File=f02
Plan File=p01
Y Axis Title=Elevation
X Axis Title(PF)=Main Channel Distance
X Axis Title(XS)=Station
BEGIN DESCRIPTION:
Conroe Lake 066
END DESCRIPTION:
DSS Export Rating Curves= 0
DSS Export Rating Curve Sorted= 0
DSS Export Volume Flow Curves= 0
DXF OffsetX= 0
DXF OffsetY= 0
DXF ScaleX= 1
DXF ScaleY= 10

--- Conroe Lake 066.p01 (plan) ---

Plan Title=Multiple Run
Short Identifier=Multiple
Geom File=g01
Flow File=f01
Subcritical Flow
K Sum by GR= 0
Std Step Tol= 0.01
Critical Tol= 0.01
Num of Std Step Trials= 20
Max Error Tol= 0.3
Flow Tol Ratio= 0.001
Split Flow NTrial= 30
Split Flow Tol= 0.02
Split Flow Ratio= 0.02
Log Output Level= 0
Friction Slope Method= 1
Unsteady Friction Slope Method= 2
Unsteady Bridges Friction Slope Method= 1
Parabolic Critical Depth
Global Vel Dist=  1 , 1 , 1
Global Log Level= 0
CheckData=True
Encroach Param= -1, 0, 0, 0
BEGIN DESCRIPTION:
Multiple Run
END DESCRIPTION:

--- Conroe Lake 066.f01 (steady flow) ---

Flow Title=Multiple
Program Version=4.10
Number of Profiles= 7
Profile Names=10-year,25-year,50-year,1pct_min,100-year,1pct_plu,500-year
River Rch & RM=Conroe Lake 066,Reach-1         ,5855
     522     697     932     411    1242    3751    2274
River Rch & RM=Conroe Lake 066,Reach-1         ,5368
     708     959    1297     577    1742    5261    3251
Boundary for River Rch & Prof#=Conroe Lake 066,Reach-1         , 1
Up Type= 0
Dn Type= 3
Dn Slope=0.01
Boundary for River Rch & Prof#=Conroe Lake 066,Reach-1         , 2
Up Type= 0
Dn Type= 3
Dn Slope=0.01
Boundary for River Rch & Prof#=Conroe Lake 066,Reach-1         , 3
Up Type= 0
Dn Type= 3
Dn Slope=0.01
Boundary for River Rch & Prof#=Conroe Lake 066,Reach-1         , 4
Up Type= 0
Dn Type= 3
Dn Slope=0.01
Boundary for River Rch & Prof#=Conroe Lake 066,Reach-1         , 5
Up Type= 0
Dn Type= 3
Dn Slope=0.01
Boundary for River Rch & Prof#=Conroe Lake 066,Reach-1         , 6
Up Type= 0
Dn Type= 3
Dn Slope=0.01
Boundary for River Rch & Prof#=Conroe Lake 066,Reach-1         , 7
Up Type= 0
Dn Type= 3
Dn Slope=0.01
DSS Import GetInterval= 0
DSS Import GetPeak= 0
DSS Import FillOption= 0

--- Conroe Lake 066.f02 (steady flow) ---

Flow Title=Orig_BLE_Flow
Program Version=4.10
Number of Profiles= 7
Profile Names=10-year,25-year,50-year,1pct_min,100-year,1pct_plu,500-year
River Rch & RM=Conroe Lake 066,Reach-1         ,5855
     522     683     810     316     955    2884    1322
River Rch & RM=Conroe Lake 066,Reach-1         ,5368
     708     940    1128     444    1340    4048    1890
Boundary for River Rch & Prof#=Conroe Lake 066,Reach-1         , 1
Up Type= 0
Dn Type= 3
Dn Slope=0.01
Boundary for River Rch & Prof#=Conroe Lake 066,Reach-1         , 2
Up Type= 0
Dn Type= 3
Dn Slope=0.01
Boundary for River Rch & Prof#=Conroe Lake 066,Reach-1         , 3
Up Type= 0
Dn Type= 3
Dn Slope=0.01
Boundary for River Rch & Prof#=Conroe Lake 066,Reach-1         , 4
Up Type= 0
Dn Type= 3
Dn Slope=0.01
Boundary for River Rch & Prof#=Conroe Lake 066,Reach-1         , 5
Up Type= 0
Dn Type= 3
Dn Slope=0.01
Boundary for River Rch & Prof#=Conroe Lake 066,Reach-1         , 6
Up Type= 0
Dn Type= 3
Dn Slope=0.01
Boundary for River Rch & Prof#=Conroe Lake 066,Reach-1         , 7
Up Type= 0
Dn Type= 3
Dn Slope=0.01
DSS Import GetInterval= 0
DSS Import GetPeak= 0
DSS Import FillOption= 0

--- Conroe Lake 066.g01 (geometry) ---

Geom Title=Existing Conditions
Program Version=4.10

River Reach=Conroe Lake 066 ,Reach-1
Reach XY= 30
      3799698.23     10229661.84      3799728.23     10229226.84
      3799828.23     10229166.84      3800058.23     10229206.84
      3800158.23     10229156.84      3800160.56     10228816.88
      3800400.77     10228553.78      3800431.89     10228454.48
       3800526.6     10228345.21      3800525.93     10228286.88
      3800381.35     10228078.44      3800337.88     10227958.91
      3800414.62     10227879.22      3800476.76      10227734.3
      3800597.93       10227124.      3800469.38     10226813.48
      3800446.33      10226537.6       3800251.8     10226269.25
      3800159.78     10226085.23      3800183.91     10225996.36
      3800136.67     10225794.79       3800030.2     10225717.12
      3799817.46      10225747.1      3799756.34       10225717.
      3799690.76     10225745.71      3799557.39     10225628.89
      3799325.53     10225596.74      3799259.04     10225614.62
      3799046.67     10225523.74      3799038.23     10225476.84

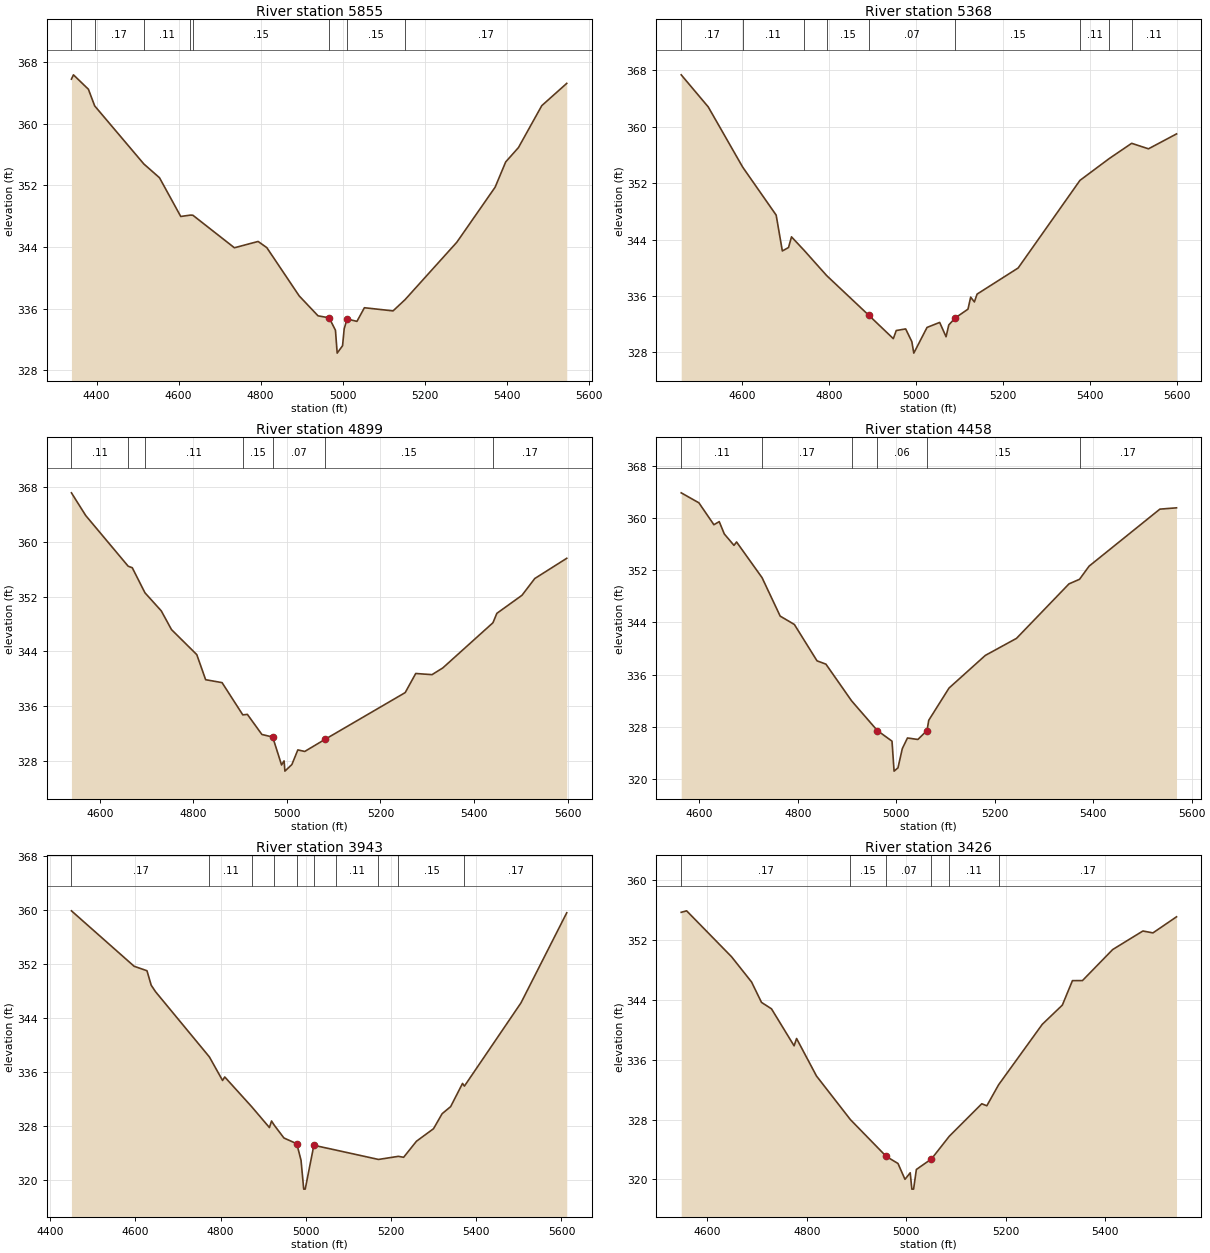
Type RM Length L Ch R = 1 ,5855    ,487,487,487
BEGIN DESCRIPTION:
Conroe Lake 066 12.0
END DESCRIPTION:
XS GIS Cut Line= 3
      3800269.15      10229787.3      3799708.23     10229436.84
       3799191.6     10229257.41
#Sta/Elev= 30
  4338.6  365.76  4343.5  366.32    4380  364.45  4395.3  362.29  4515.3  354.75
  4553.4  352.97  4605.3  347.94    4629  348.12  4634.9   348.1  4736.2  343.88
    4794   344.7  4815.2   343.9  4894.3  337.63  4940.2  335.05  4967.3  334.79
  4982.7  333.18  4986.9  330.21    5000  331.17    5004  333.37    5011  334.64
  5035.1  334.33  5053.3   336.1  5123.2  335.69  5152.5  337.15  5278.8   344.6
  5372.2  351.74    5398  355.02  5429.1  356.88    5486  362.32  5546.9  365.21
#Mann= 8 ,-1 , 0
  4338.6     .11       0  4395.3     .17       0  4515.3     .11       0
    4629     .17       0  4634.9     .15       0  4967.3     .07       0
    5011     .15       0  5152.5     .17       0
Bank Sta=4967.3,5011
XS Rating Curve= 0 ,0
Exp/Cntr=0.3,0.1

Type RM Length L Ch R = 1 ,5368    ,469,469,469
BEGIN DESCRIPTION:
Conroe Lake 066 11.0
END DESCRIPTION:
XS GIS Cut Line= 3
      3800321.22     10229585.56      3799958.23     10229186.84
      3799474.12     10228835.79
#Sta/Elev= 30
  4460.8  367.33  4522.8  362.79    4602  354.25  4678.8  347.46    4693  342.38
  4707.2  342.87    4714  344.38  4742.7  342.49  4794.8  338.89    4891   333.3
  4947.8  329.96  4954.5  331.11  4976.1  331.34  4990.3  329.54  4994.8  327.91
  5025.2  331.55  5054.2  332.26  5068.9  330.23  5075.1   331.9  5089.8  332.88
  5119.2  334.14  5125.4  335.84  5133.9  335.16  5140.1  336.27  5234.4  339.97
  5376.3  352.38  5443.5  355.47    5495  357.63  5533.6  356.85    5598  358.96
#Mann= 9 ,-1 , 0
  4460.8     .17       0    4602     .11       0  4742.7     .17       0
  4794.8     .15       0    4891     .07       0  5089.8     .15       0
  5376.3     .11       0  5443.5     .17       0    5495     .11       0
#XS Ineff= 2 , 0
       0                  5125.4       0  335.84
Permanent Ineff=
       F       F
Bank Sta=4891,5089.8
XS Rating Curve= 0 ,0
Exp/Cntr=0.3,0.1

Type RM Length L Ch R = 1 ,4899    ,441,441,441
BEGIN DESCRIPTION:
Conroe Lake 066 10.0
END DESCRIPTION:
XS GIS Cut Line= 3
      3800586.35     10229102.87      3800158.23      10228933.5
      3799636.88      10228640.6
#Sta/Elev= 30
  4539.6  367.21  4570.2  363.88  4660.9  356.46  4669.6  356.24  4696.7  352.57
  4731.6  349.92  4753.4  347.18  4807.5  343.51  4826.4  339.84  4861.5  339.41
  4905.8  334.69  4915.6  334.76  4946.6  331.82  4969.7  331.44  4988.6  327.35
    4994  327.95  4995.8  326.45  5010.7  327.42  5023.4  329.56  5038.1  329.33
  5081.4   331.1  5252.8  337.95  5275.3  340.75  5310.1  340.58  5333.1  341.56
  5440.3  348.18  5448.7  349.56  5502.3   352.2  5529.7  354.66    5598  357.62
#Mann= 7 ,-1 , 0
  4539.6     .11       0  4660.9     .17       0  4696.7     .11       0
  4905.8     .15       0  4969.7     .07       0  5081.4     .15       0
  5440.3     .17       0
Bank Sta=4969.7,5081.4
XS Rating Curve= 0 ,0
Exp/Cntr=0.3,0.1

Type RM Length L Ch R = 1 ,4458    ,515,515,515
BEGIN DESCRIPTION:
Conroe Lake 066 9.0
END DESCRIPTION:
XS GIS Cut Line= 3
      3800792.64     10228683.65      3800369.61     10228575.63
      3799829.45     10228395.82
#Sta/Elev= 30
  4563.4  363.85  4599.3  362.32  4629.8  358.96  4640.6  359.44  4650.9  357.55
  4670.6   355.8  4675.8  356.32  4727.6  350.85  4764.4  344.96  4793.2  343.68
  4839.2  338.11  4857.3   337.6  4909.4  331.98  4961.7  327.43  4991.5   325.8
  4995.7  321.21  5003.6  321.71  5012.4  324.66  5022.9  326.29    5044  326.06
 5062.58  327.43  5066.1     329  5107.3  333.94    5181  338.94  5244.3  341.55
  5350.9   349.9  5372.3   350.6  5391.8  352.62  5535.5  361.35  5569.3  361.55
#Mann= 6 ,-1 , 0
  4563.4     .11       0  4727.6     .17       0  4909.4     .11       0
  4961.7     .06       0 5062.58     .15       0  5372.3     .17       0
Bank Sta=4961.7,5062.58
XS Rating Curve= 0 ,0
Exp/Cntr=0.3,0.1

Type RM Length L Ch R = 1 ,3943    ,517,517,517
BEGIN DESCRIPTION:
Conroe Lake 066 8.0
END DESCRIPTION:
XS GIS Cut Line= 3
      3800994.31     10228198.67      3800446.82     10228148.37
      3799836.23     10228194.14
#Sta/Elev= 30
  4450.2  359.93  4597.3  351.71  4627.4  351.05  4637.4   348.9  4647.5  347.94
  4773.9  338.27  4804.8  334.78  4809.9   335.3  4873.4  330.87  4914.7   327.8
  4919.7  328.77  4926.5  328.11  4948.8  326.25  4978.9   325.4  4988.9  322.94
  4995.2  318.67  4998.7  318.67    5019  325.17  5071.3  324.45  5170.6  323.07
  5217.3  323.53  5229.6  323.39  5259.7  325.77  5299.8  327.63  5319.9  329.85
  5339.9   330.9  5367.8  334.34  5372.2  333.94  5504.9  346.28  5612.3  359.64
#Mann= 10 ,-1 , 0
  4450.2     .17       0  4773.9     .11       0  4873.4     .17       0
  4926.5     .15       0  4978.9     .07       0    5019     .15       0
  5071.3     .11       0  5170.6     .17       0  5217.3     .15       0
  5372.2     .17       0
Bank Sta=4978.9,5019
XS Rating Curve= 0 ,0
Exp/Cntr=0.3,0.1

Type RM Length L Ch R = 1 ,3426    ,504,504,504
BEGIN DESCRIPTION:
Conroe Lake 066 7.0
END DESCRIPTION:
XS GIS Cut Line= 3
      3800928.74     10227684.11      3800478.06     10227727.82
      3799941.07     10227640.14
#Sta/Elev= 30
  4547.2  355.74  4558.1  355.94  4648.6  349.79  4688.8  346.42  4708.8  343.69
  4728.9  342.83  4774.4  337.88  4779.4  338.86  4819.4  333.85  4887.7  328.01
    4960  323.08  4983.5  322.14  4997.6  320.02  5008.1   320.9  5011.4  318.71
  5014.9  318.71  5020.5  321.34  5050.9  322.75  5086.7  325.78  5152.2  330.13
  5162.3  329.86  5186.1  332.68  5273.8  340.75  5314.3  343.33  5334.6   346.6
  5354.8  346.61  5415.6  350.76  5476.4  353.24  5496.7  352.99  5544.1  355.14
#Mann= 6 ,-1 , 0
  4547.2     .17       0  4887.7     .15       0    4960     .07       0
  5050.9     .15       0  5086.7     .11       0  5186.1     .17       0
Bank Sta=4960,5050.9
XS Rating Curve= 0 ,0
Exp/Cntr=0.3,0.1

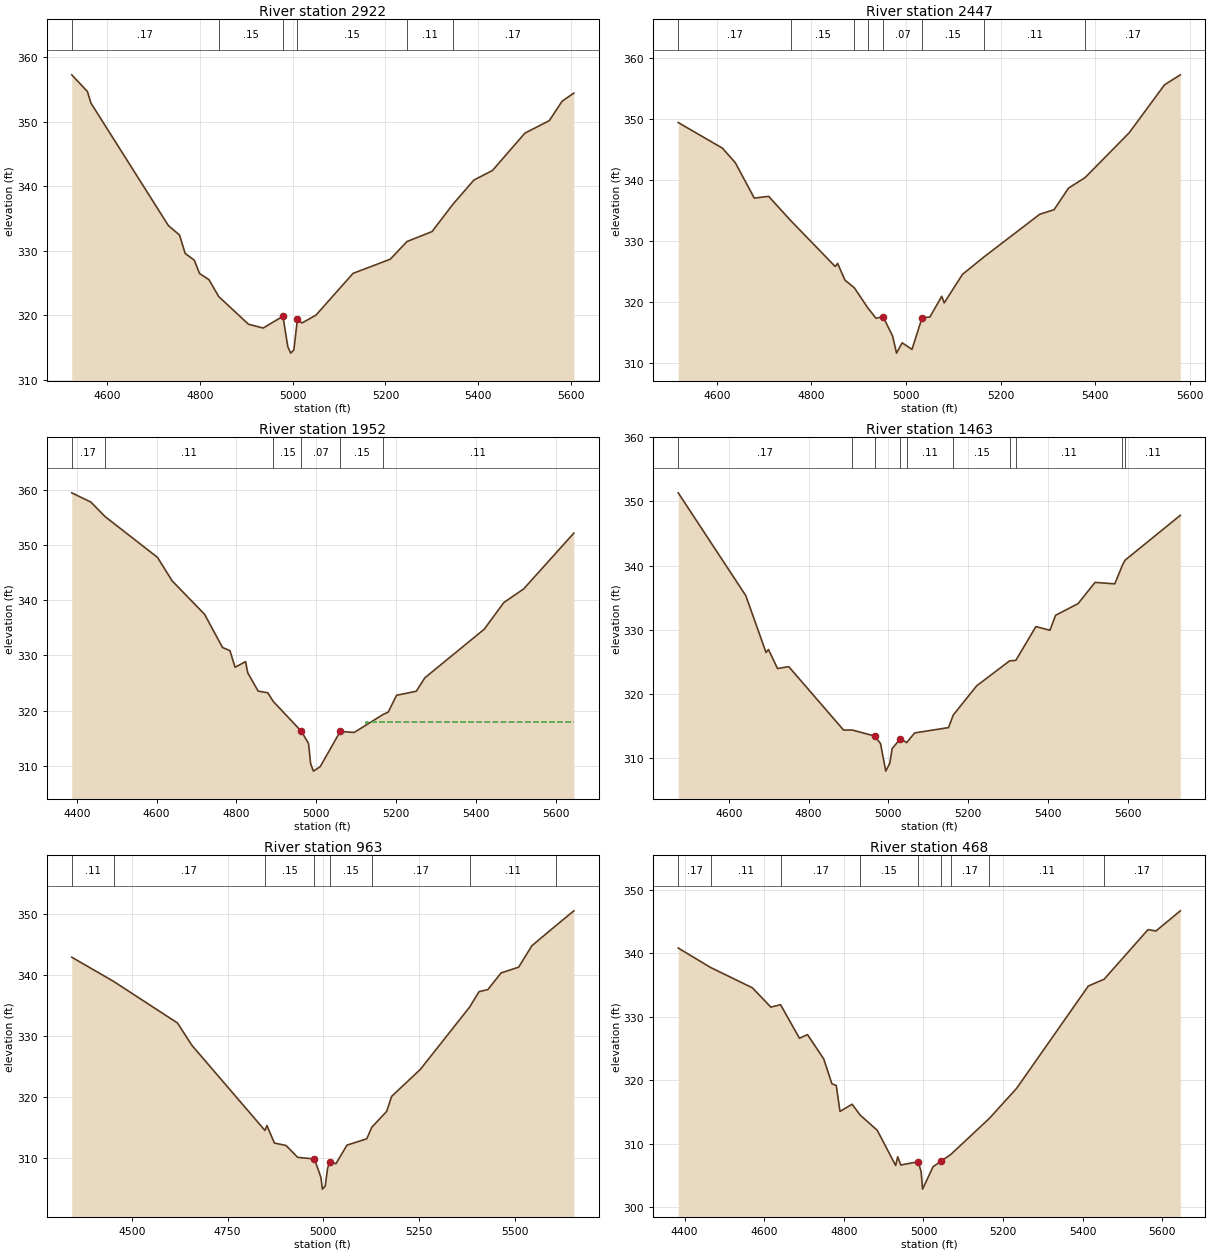
Type RM Length L Ch R = 1 ,2922    ,475,475,475
BEGIN DESCRIPTION:
Conroe Lake 066 6.0
END DESCRIPTION:
XS GIS Cut Line= 3
      3801006.89     10227095.57      3800558.01     10227254.84
      3799952.54     10227223.18
#Sta/Elev= 30
  4523.7  357.28  4557.5  354.69  4565.1  352.89  4732.1   333.9  4756.1  332.44
  4768.2  329.59    4788  328.54  4799.1  326.48  4819.4  325.53  4840.6   322.9
  4904.7  318.61  4936.5  318.02    4979  319.85  4989.6  315.12  4995.7  314.13
  5002.6  314.63  5010.2  319.36  5020.2  318.81  5050.2  320.02  5130.3   326.5
  5210.4  328.69  5246.5  331.43  5300.6  332.98  5345.2  337.18  5390.7  340.96
  5430.7  342.44  5500.8  348.24  5553.4  350.18    5581  353.19  5606.3  354.45
#Mann= 6 ,-1 , 0
  4523.7     .17       0  4840.6     .15       0    4979     .07       0
  5010.2     .15       0  5246.5     .11       0  5345.2     .17       0
Bank Sta=4979,5010.2
XS Rating Curve= 0 ,0
Exp/Cntr=0.3,0.1

Type RM Length L Ch R = 1 ,2447    ,495,495,495
BEGIN DESCRIPTION:
Conroe Lake 066 5.0
END DESCRIPTION:
XS GIS Cut Line= 3
      3800957.39     10226887.22       3800479.7     10226828.35
      3799936.59     10227030.46
#Sta/Elev= 30
  4518.7  349.39  4611.9   345.2  4639.1  342.82  4679.4  336.99  4709.7  337.28
  4756.5  333.29  4850.4  325.76  4855.5  326.27  4870.9  323.54  4890.9  322.26
  4919.3  318.97  4936.6  317.27  4951.5  317.55  4971.6  314.35    4980  311.55
  4991.8  313.24  5012.6  312.17    5034  317.37  5050.4  317.47  5075.4  320.88
  5080.7   319.8  5119.3  324.48  5164.6  327.33  5282.5  334.34  5312.8  335.09
  5343.4  338.64  5378.1  340.34  5471.5  347.71  5546.1  355.58  5579.5  357.22
#Mann= 8 ,-1 , 0
  4518.7     .17       0  4756.5     .15       0  4890.9     .17       0
  4919.3     .15       0  4951.5     .07       0    5034     .15       0
  5164.6     .11       0  5378.1     .17       0
#XS Ineff= 2 , 0
       0                  5075.4       0  320.88
Permanent Ineff=
       F       F
Bank Sta=4951.5,5034
XS Rating Curve= 0 ,0
Exp/Cntr=0.3,0.1

Type RM Length L Ch R = 1 ,1952    ,489,489,489
BEGIN DESCRIPTION:
Conroe Lake 066 4.0
END DESCRIPTION:
XS GIS Cut Line= 3
      3800923.59     10226186.71      3800342.92     10226381.61
      3799863.67     10226814.32
#Sta/Elev= 30
  4387.5  359.47  4435.7  357.78  4470.6  355.19  4602.4  347.77  4639.2  343.51
  4720.5  337.45  4765.3  331.45  4783.8  330.88  4796.9  327.87  4823.1  328.89
  4828.4  326.88  4854.6  323.55  4878.8  323.24  4892.5  321.67  4963.2  316.24
  4980.8  314.05  4986.1  310.41    4993  309.05  5010.1  309.86  5060.2  316.24
  5095.3  316.06  5167.4   319.3  5180.5  319.74  5201.4  322.79  5250.7  323.52
  5272.4  325.96  5421.1  334.76  5470.4   339.6  5519.8  342.05  5645.7  352.17
#Mann= 6 ,-1 , 0
  4387.5     .17       0  4470.6     .11       0  4892.5     .15       0
  4963.2     .07       0  5060.2     .15       0  5167.4     .11       0
#XS Ineff= 2 , 0
       0                  5123.7       0  317.91
Permanent Ineff=
       F       F
Bank Sta=4963.2,5060.2
XS Rating Curve= 0 ,0
Exp/Cntr=0.3,0.1

Type RM Length L Ch R = 1 ,1463    ,500,500,500
BEGIN DESCRIPTION:
Conroe Lake 066 3.0
END DESCRIPTION:
XS GIS Cut Line= 3
      3800613.65     10225671.11      3800178.09     10225968.13
      3799647.53     10226473.17
#Sta/Elev= 30
  4472.8  351.33  4642.3  335.32  4693.1  326.46  4699.2  326.93  4721.9  323.96
    4750  324.26  4887.6  314.38  4909.5  314.38  4965.4  313.45  4980.4  312.27
  4993.5  307.98  5003.6  309.22  5009.4  311.47  5030.4  313.05  5045.8  312.42
    5066  313.93  5150.9  314.76  5162.8  316.72  5221.3  321.25  5304.3  325.16
  5319.8  325.23  5370.2   330.5  5405.4  329.92  5419.5  332.25  5476.1  334.08
  5518.6  337.38    5568  337.15  5587.2  340.05  5593.8  340.83  5732.5  347.83
#Mann= 10 ,-1 , 0
  4472.8     .17       0  4909.5     .15       0  4965.4     .07       0
  5030.4     .15       0  5045.8     .11       0  5162.8     .15       0
  5304.3     .17       0  5319.8     .11       0  5587.2     .17       0
  5593.8     .11       0
Bank Sta=4965.4,5030.4
XS Rating Curve= 0 ,0
Exp/Cntr=0.3,0.1

Type RM Length L Ch R = 1 ,963     ,495,495,495
BEGIN DESCRIPTION:
Conroe Lake 066 2.0
END DESCRIPTION:
XS GIS Cut Line= 3
      3799962.64      10225098.2      3799858.93     10225746.96
      3799535.81     10226316.48
#Sta/Elev= 30
    4343  342.93  4452.2  338.97  4619.3  332.14  4656.6   328.5  4847.8  314.51
  4852.9  315.32  4872.5  312.45  4902.9  312.05  4933.3   310.1    4977  309.84
    4994  306.81  4997.8  304.89  5005.2  305.39  5011.4  308.31  5017.1   309.4
    5033  309.05  5062.2  312.11  5113.8  313.15  5126.9  315.04  5165.7  317.64
  5178.7   320.1  5253.7  324.53  5382.7  334.77  5407.1  337.28  5430.1  337.62
  5464.6  340.35  5510.6   341.3  5545.1  344.81  5607.6   348.1  5654.8  350.54
#Mann= 8 ,-1 , 0
    4343     .11       0  4452.2     .17       0  4847.8     .15       0
    4977     .07       0  5017.1     .15       0  5126.9     .17       0
  5382.7     .11       0  5607.6     .17       0
Bank Sta=4977,5017.1
XS Rating Curve= 0 ,0
Exp/Cntr=0.3,0.1

Type RM Length L Ch R = 1 ,468     ,316,316,316
BEGIN DESCRIPTION:
Conroe Lake 066 1.0
END DESCRIPTION:
XS GIS Cut Line= 3
      3799548.58     10225012.21      3799429.88     10225616.87
      3799441.81     10226262.26
#Sta/Elev= 30
  4383.8  340.86  4465.1  337.79  4570.2  334.58  4616.6  331.53    4641  331.92
  4688.4  326.62  4708.7   327.2  4749.5  323.35  4769.9  319.44    4781  319.16
  4790.3  315.07  4820.8  316.21    4841   314.5  4883.9   312.1  4930.2  306.54
  4935.3  307.92  4943.1  306.62  4986.8  307.13  4994.1  305.58  4997.8  302.81
  5024.2  306.35  5044.2  307.22  5068.7  308.28  5165.1  313.94  5234.2  318.72
  5414.3  334.86  5454.1  335.94  5564.3  343.76  5584.3  343.55  5645.5  346.73
#Mann= 9 ,-1 , 0
  4383.8     .17       0  4465.1     .11       0    4641     .17       0
    4841     .15       0  4986.8     .07       0  5044.2     .15       0
  5068.7     .17       0  5165.1     .11       0  5454.1     .17       0
Bank Sta=4986.8,5044.2
XS Rating Curve= 0 ,0
Exp/Cntr=0.3,0.1

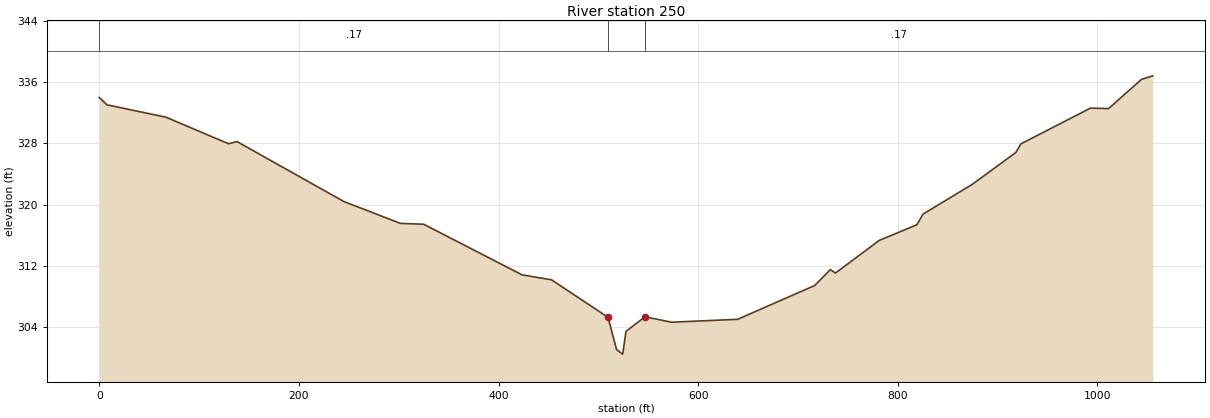
Type RM Length L Ch R = 1 ,250     ,0,0,0
XS GIS Cut Line= 3
      3799444.44     10225125.88      3799139.13     10225556.75
      3799251.73     10226072.06
#Sta/Elev= 30
       0  334.01     7.6  333.05    66.7  331.44   129.4  327.97   138.1  328.24
   245.1  320.41   301.7  317.56     325  317.45   423.5  310.84   453.1  310.19
   509.7  305.29   518.3  301.06   524.4  300.48   527.7  303.45   546.7  305.36
   573.4  304.65   639.6  305.03   716.7  309.44   732.5  311.52   737.6  311.07
   781.5  315.34   819.1  317.38   825.4  318.78   874.4  322.64   918.3  326.82
   923.4  327.95   993.1  332.62  1011.2  332.56  1044.3  336.38  1055.5  336.84
#Mann= 3 , 0 , 0
       0     .17       0   509.7     .07       0   546.7     .17       0
Bank Sta=509.7,546.7
XS Rating Curve= 0 ,0
Exp/Cntr=0.3,0.1

Chan Stop Cuts=-1
Use User Specified Reach Order=0
Composite Channel Slope=5