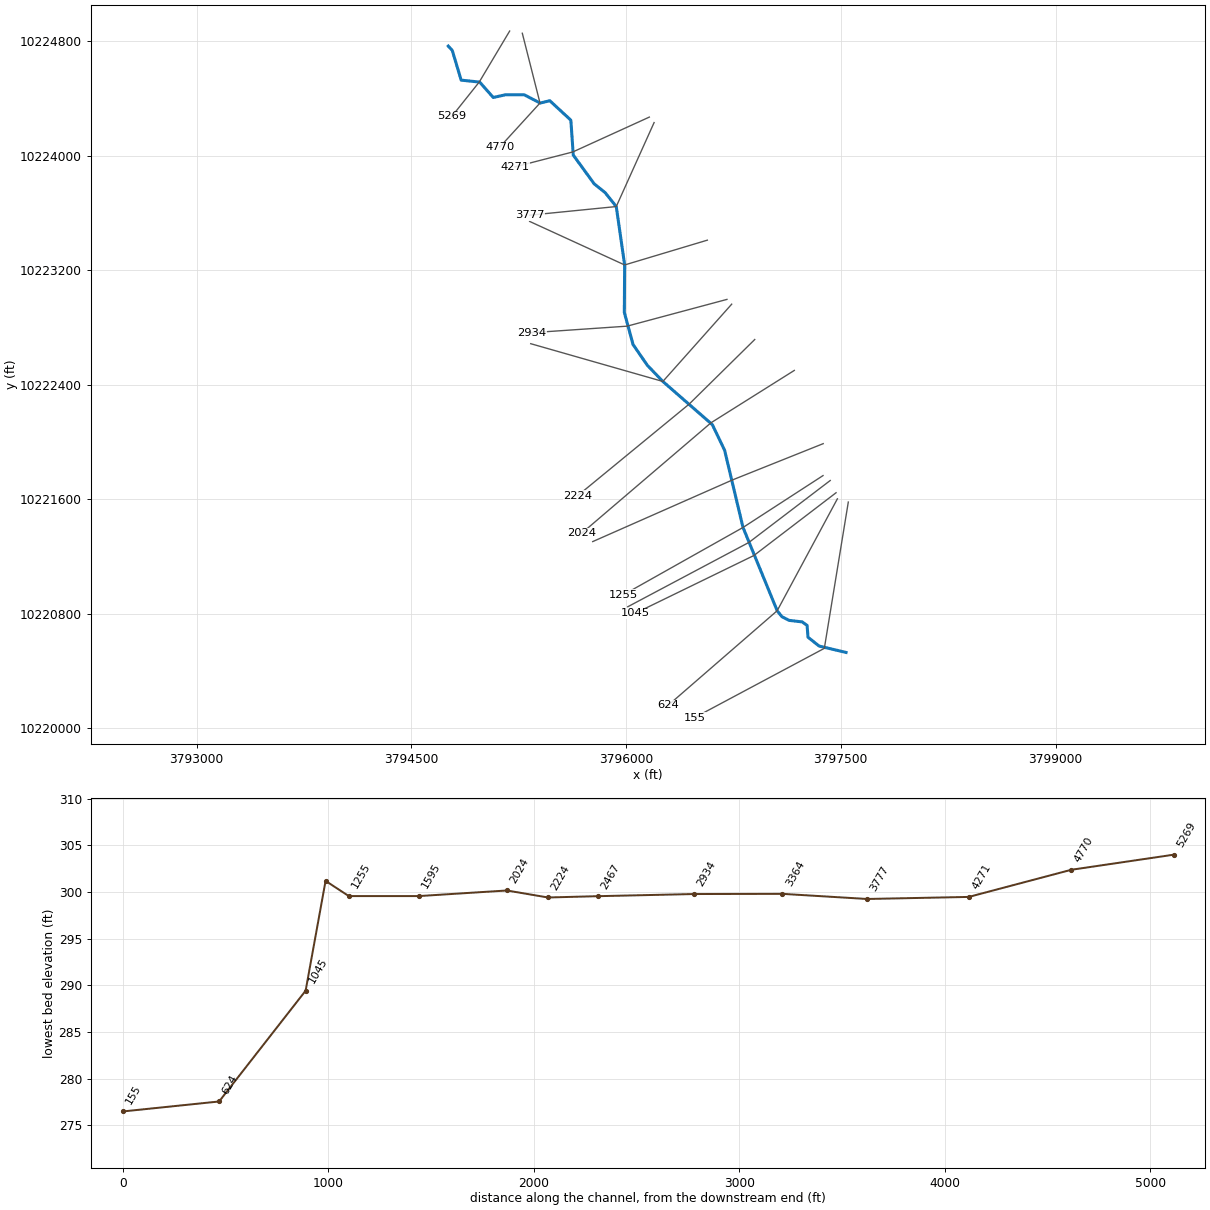
--- Conroe Lake 067.prj (project) ---

Proj Title=Conroe Lake 067 Base Level Engineering
Current Plan=p01
Default Exp/Contr=0.3,0.1
English Units
Geom File=g01
Flow File=f01
Flow File=f02
Plan File=p01
Y Axis Title=Elevation
X Axis Title(PF)=Main Channel Distance
X Axis Title(XS)=Station
BEGIN DESCRIPTION:
Conroe Lake 067
END DESCRIPTION:
DSS Export Rating Curves= 0
DSS Export Rating Curve Sorted= 0
DSS Export Volume Flow Curves= 0
DXF OffsetX= 0
DXF OffsetY= 0
DXF ScaleX= 1
DXF ScaleY= 10

--- Conroe Lake 067.p01 (plan) ---

Plan Title=Multiple Run
Short Identifier=Multiple
Geom File=g01
Flow File=f01
Subcritical Flow
K Sum by GR= 0
Std Step Tol= 0.01
Critical Tol= 0.01
Num of Std Step Trials= 20
Max Error Tol= 0.3
Flow Tol Ratio= 0.001
Split Flow NTrial= 30
Split Flow Tol= 0.02
Split Flow Ratio= 0.02
Log Output Level= 0
Friction Slope Method= 1
Unsteady Friction Slope Method= 2
Unsteady Bridges Friction Slope Method= 1
Parabolic Critical Depth
Global Vel Dist=  1 , 1 , 1
Global Log Level= 0
CheckData=True
Encroach Param= -1, 0, 0, 0
BEGIN DESCRIPTION:
Multiple Run
END DESCRIPTION:

--- Conroe Lake 067.f01 (steady flow) ---

Flow Title=Multiple
Program Version=4.10
Number of Profiles= 7
Profile Names=10-year,25-year,50-year,1pct_min,100-year,1pct_plu,500-year
River Rch & RM=Conroe Lake 067,Reach-1         ,5269
     520     697     936     415    1253    3784    2317
River Rch & RM=Conroe Lake 067,Reach-1         ,4770
     832    1143    1562     702    2120    6402    4035
River Rch & RM=Conroe Lake 067,Reach-1         ,1595
     784    1068    1448     646    1950    5889    3655
Boundary for River Rch & Prof#=Conroe Lake 067,Reach-1         , 1
Up Type= 0
Dn Type= 3
Dn Slope=0.002
Boundary for River Rch & Prof#=Conroe Lake 067,Reach-1         , 2
Up Type= 0
Dn Type= 3
Dn Slope=0.002
Boundary for River Rch & Prof#=Conroe Lake 067,Reach-1         , 3
Up Type= 0
Dn Type= 3
Dn Slope=0.002
Boundary for River Rch & Prof#=Conroe Lake 067,Reach-1         , 4
Up Type= 0
Dn Type= 3
Dn Slope=0.002
Boundary for River Rch & Prof#=Conroe Lake 067,Reach-1         , 5
Up Type= 0
Dn Type= 3
Dn Slope=0.002
Boundary for River Rch & Prof#=Conroe Lake 067,Reach-1         , 6
Up Type= 0
Dn Type= 3
Dn Slope=0.002
Boundary for River Rch & Prof#=Conroe Lake 067,Reach-1         , 7
Up Type= 0
Dn Type= 3
Dn Slope=0.002
DSS Import GetInterval= 0
DSS Import GetPeak= 0
DSS Import FillOption= 0

--- Conroe Lake 067.f02 (steady flow) ---

Flow Title=Orig_BLE_Flow
Program Version=4.10
Number of Profiles= 7
Profile Names=10-year,25-year,50-year,1pct_min,100-year,1pct_plu,500-year
River Rch & RM=Conroe Lake 067,Reach-1         ,5269
     520     683     814     319     964    2912    1347
River Rch & RM=Conroe Lake 067,Reach-1         ,4770
     832    1121    1358     540    1631    4925    2346
River Rch & RM=Conroe Lake 067,Reach-1         ,1595
     784    1047    1259     497    1500    4530    2125
Boundary for River Rch & Prof#=Conroe Lake 067,Reach-1         , 1
Up Type= 0
Dn Type= 3
Dn Slope=0.002
Boundary for River Rch & Prof#=Conroe Lake 067,Reach-1         , 2
Up Type= 0
Dn Type= 3
Dn Slope=0.002
Boundary for River Rch & Prof#=Conroe Lake 067,Reach-1         , 3
Up Type= 0
Dn Type= 3
Dn Slope=0.002
Boundary for River Rch & Prof#=Conroe Lake 067,Reach-1         , 4
Up Type= 0
Dn Type= 3
Dn Slope=0.002
Boundary for River Rch & Prof#=Conroe Lake 067,Reach-1         , 5
Up Type= 0
Dn Type= 3
Dn Slope=0.002
Boundary for River Rch & Prof#=Conroe Lake 067,Reach-1         , 6
Up Type= 0
Dn Type= 3
Dn Slope=0.002
Boundary for River Rch & Prof#=Conroe Lake 067,Reach-1         , 7
Up Type= 0
Dn Type= 3
Dn Slope=0.002
DSS Import GetInterval= 0
DSS Import GetPeak= 0
DSS Import FillOption= 0

--- Conroe Lake 067.g01 (geometry) ---

Geom Title=Existing Conditions
Program Version=4.10

River Reach=Conroe Lake 067 ,Reach-1
Reach XY= 30
      3794758.23     10224766.84      3794786.23     10224736.03
      3794848.18      10224528.8      3794977.54     10224515.21
      3795072.47     10224407.62      3795158.51     10224426.79
       3795289.2     10224426.42      3795399.86     10224368.77
      3795467.42     10224385.09      3795614.52      10224249.2
      3795631.33     10224005.24      3795777.61     10223804.25
      3795853.57     10223743.49      3795931.69     10223645.83
      3795990.28     10223237.85      3795988.11     10222905.82
      3796048.88     10222682.29       3796148.7     10222536.89
      3796257.21     10222424.04      3796603.02      10222122.2
      3796688.74     10221942.85      3796817.11     10221404.08
      3797055.82     10220822.48      3797088.37     10220781.25
      3797138.29     10220755.21      3797230.56      10220744.4
      3797264.73     10220719.79      3797271.07     10220637.38
      3797348.74     10220575.56      3797537.23     10220530.96

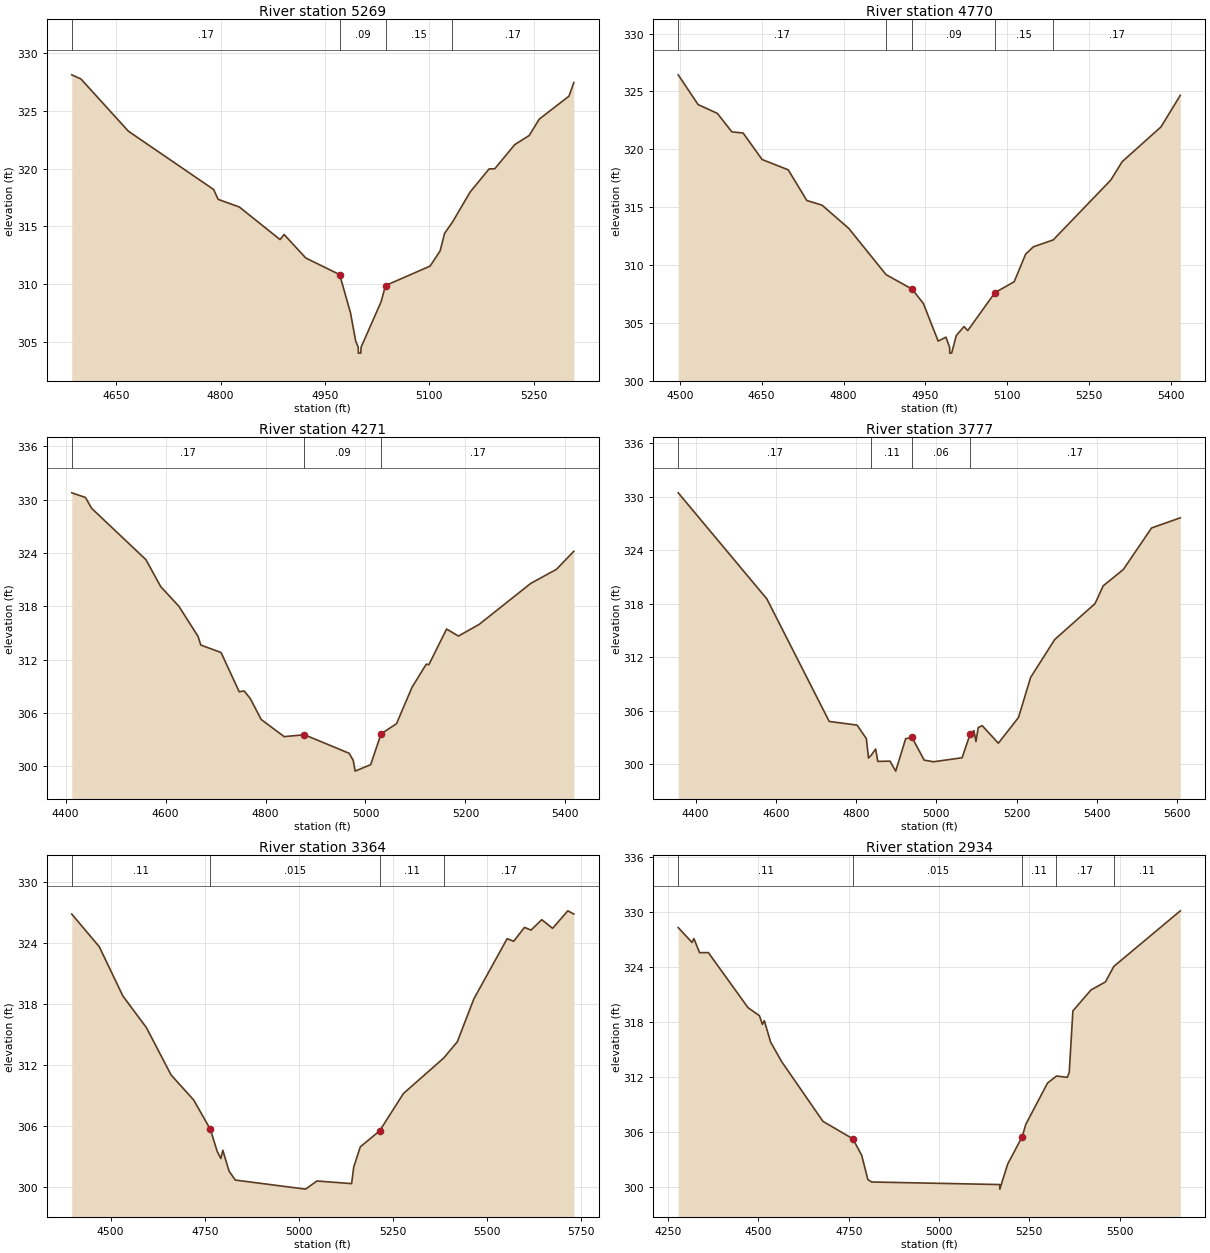
Type RM Length L Ch R = 1 ,5269    ,499,499,499
BEGIN DESCRIPTION:
Conroe Lake 067 12.0
END DESCRIPTION:
XS GIS Cut Line= 3
        3795187.     10224871.81      3794975.08     10224516.39
      3794783.17     10224275.62
#Sta/Elev= 30
  4586.2  328.14  4599.4  327.78  4667.6  323.25  4790.2  318.19  4796.6  317.34
  4827.2  316.67  4885.6  313.85  4891.4  314.29  4922.6  312.25  4971.3  310.81
  4986.8  307.51  4994.4  305.03    4998   304.5  4998.2     304  5001.7     304
    5002   304.5  5030.8  308.45  5037.2  309.86  5101.3  311.55  5115.7  312.87
  5122.1  314.39  5133.4  315.36  5158.9  317.98  5186.1  319.98  5194.2  319.99
    5223  322.09  5243.8  322.88  5258.2   324.3  5300.9  326.29  5307.9  327.47
#Mann= 4 ,-1 , 0
  4586.2     .17       0  4971.3     .09       0  5037.2     .15       0
  5133.4     .17       0
Bank Sta=4971.3,5037.2
XS Rating Curve= 0 ,0
Exp/Cntr=0.3,0.1

Type RM Length L Ch R = 1 ,4770    ,499,499,499
BEGIN DESCRIPTION:
Conroe Lake 067 11.0
END DESCRIPTION:
XS GIS Cut Line= 3
       3795275.4     10224856.36      3795399.07     10224369.01
      3795117.87     10224061.09
#Sta/Elev= 30
  4497.2  326.43  4533.6  323.86  4568.9   323.1  4595.5   321.5  4616.1   321.4
  4650.9  319.11  4698.7  318.22  4732.8  315.57  4760.6  315.17  4809.6  313.16
    4878  309.16  4925.7  307.91  4946.3  306.67  4973.4  303.42  4987.6  303.76
  4994.4  302.88  4994.6  302.38  4998.1  302.38  5006.6   303.9  5020.8  304.68
  5027.6  304.33  5077.5  307.61  5112.7  308.55  5133.6  310.93  5147.8  311.57
  5184.1  312.16  5289.7  317.34  5310.6  318.93  5381.6  321.93    5417  324.66
#Mann= 5 ,-1 , 0
  4497.2     .17       0    4878     .15       0  4925.7     .09       0
  5077.5     .15       0  5184.1     .17       0
Bank Sta=4925.7,5077.5
XS Rating Curve= 0 ,0
Exp/Cntr=0.3,0.1

Type RM Length L Ch R = 1 ,4271    ,494,494,494
BEGIN DESCRIPTION:
Conroe Lake 067 10.0
END DESCRIPTION:
XS GIS Cut Line= 3
      3796162.78     10224270.78      3795627.96     10224027.14
      3795224.28       10223923.
#Sta/Elev= 30
  4412.3  330.77  4439.7  330.25    4452  329.03  4560.6  323.26  4590.3  320.22
  4626.5  318.02  4664.9  314.63  4670.5  313.65    4711  312.81  4747.4  308.39
  4757.1  308.49  4769.4  307.64  4791.3  305.28  4837.3  303.35  4877.9  303.56
  4967.2  301.48  4975.5  300.68  4979.3  299.47  5010.4   300.2  5031.1  303.65
  5062.1  304.81  5093.1   308.9  5121.6   311.5  5126.8  311.44  5162.3  315.45
    5186  314.66  5227.3  315.97  5330.6  320.58  5382.2  322.17  5416.9   324.2
#Mann= 3 , 0 , 0
  4412.3     .17       0  4877.9     .09       0  5031.1     .17       0
Bank Sta=4877.9,5031.1
XS Rating Curve= 0 ,0
Exp/Cntr=0.3,0.1

Type RM Length L Ch R = 1 ,3777    ,413,413,413
BEGIN DESCRIPTION:
Conroe Lake 067 9.0
END DESCRIPTION:
XS GIS Cut Line= 3
      3796196.01     10224232.43      3795931.69     10223645.83
       3795326.5     10223585.43
#Sta/Elev= 30
  4356.6  330.45  4577.5  318.56    4733  304.82  4802.4  304.41  4825.5   302.9
    4831  300.72    4838  301.05  4848.7  301.73  4854.1  300.34  4884.6  300.37
  4898.7  299.25  4923.6  302.89  4939.4  303.02  4969.8  300.48    4993   300.3
  5064.2  300.75  5084.3   303.4  5093.8  303.79  5098.8  302.57  5104.4  304.14
  5114.4  304.35  5154.6  302.38  5204.9  305.27    5235  309.75    5295     314
  5395.6  318.03  5415.9  320.02  5466.1  321.85  5536.5  326.51  5608.2  327.65
#Mann= 4 ,-1 , 0
  4356.6     .17       0    4838     .11       0  4939.4     .06       0
  5084.3     .17       0
Bank Sta=4939.4,5084.3
XS Rating Curve= 0 ,0
Exp/Cntr=0.3,0.1

Type RM Length L Ch R = 1 ,3364    ,430,430,430
BEGIN DESCRIPTION:
Conroe Lake 067 8.0
END DESCRIPTION:
XS GIS Cut Line= 3
      3796567.87     10223411.08      3795990.28     10223237.85
      3795326.54     10223541.96
#Sta/Elev= 30
    4397  326.83  4470.1  323.62  4532.7  318.78  4595.4  315.66  4660.7  311.02
  4720.7  308.56  4765.1  305.67  4783.3  303.49  4792.9  302.81  4798.1  303.62
  4814.6  301.57  4831.2  300.69  5017.7   299.8    5048   300.6    5140  300.34
  5145.7  301.97    5163  303.95  5214.5  305.53  5277.7   309.2  5384.5  312.68
  5420.7  314.28  5464.7   318.5    5553  324.41  5570.5  324.16    5599  325.52
  5616.5  325.26    5645  326.28  5673.7  325.43  5714.1  327.15  5730.1  326.84
#Mann= 4 ,-1 , 0
    4397     .11       0  4765.1    .015       0  5214.5     .11       0
  5384.5     .17       0
Bank Sta=4765.1,5214.5
XS Rating Curve= 0 ,0
Exp/Cntr=0.3,0.1

Type RM Length L Ch R = 1 ,2934    ,467,467,467
BEGIN DESCRIPTION:
Conroe Lake 067 7.0
END DESCRIPTION:
XS GIS Cut Line= 3
      3796704.92     10222997.26      3796007.65     10222810.33
      3795341.11     10222764.67
#Sta/Elev= 30
  4278.1  328.34  4316.3  326.72  4321.5  327.14  4337.2   325.6  4361.5  325.61
  4471.2   319.6  4502.8  318.72  4511.2  317.77  4516.4  318.18  4533.9  315.83
    4565  313.67  4678.8  307.18  4761.7  305.27  4786.1  303.46  4803.1  300.82
  4813.4  300.56  5168.2  300.28  5168.4  299.78  5190.2  302.52  5230.3   305.5
  5240.4  306.86  5300.5  311.36  5325.3  312.13  5355.3  311.99  5360.6  312.54
  5370.7  319.24  5420.8  321.53  5460.9  322.41    5484   324.1  5668.1  330.17
#Mann= 5 ,-1 , 0
  4278.1     .11       0  4761.7    .015       0  5230.3     .11       0
  5325.3     .17       0    5484     .11       0
Bank Sta=4761.7,5230.3
XS Rating Curve= 0 ,0
Exp/Cntr=0.3,0.1

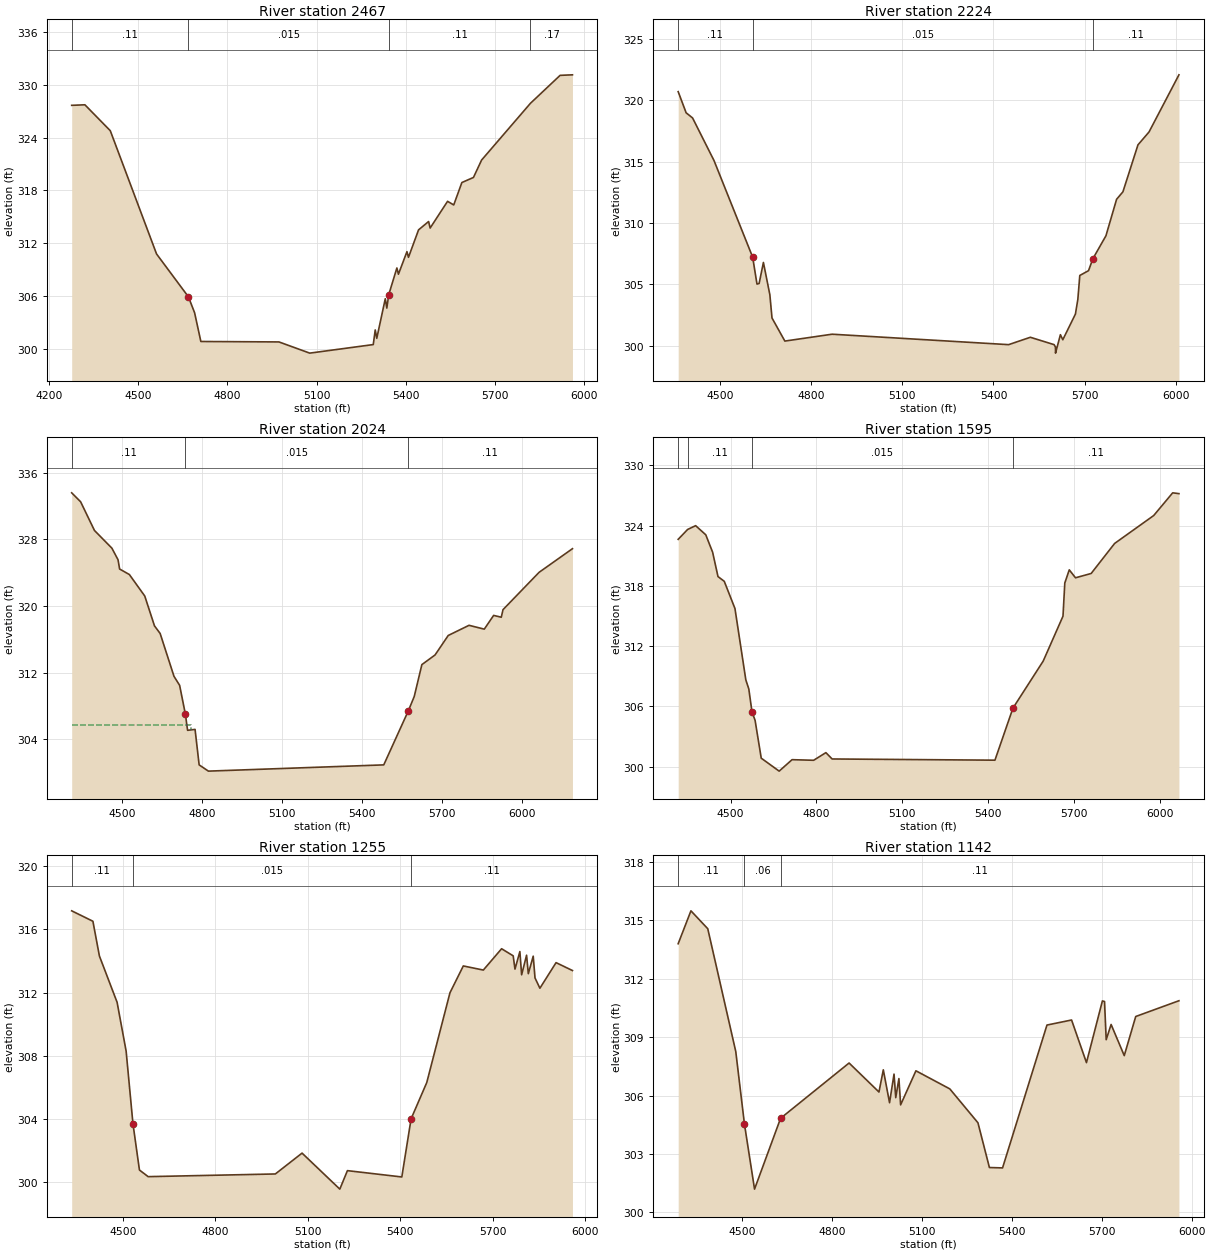
Type RM Length L Ch R = 1 ,2467    ,243,243,243
BEGIN DESCRIPTION:
Conroe Lake 067 6.0
END DESCRIPTION:
XS GIS Cut Line= 3
      3796738.15     10222964.02      3796257.21     10222424.04
      3795334.17     10222687.84
#Sta/Elev= 30
  4276.9  327.66  4321.3  327.72  4406.6  324.78  4562.1   310.8  4669.1  305.94
    4690  304.13    4711  300.87  4973.5  300.82    5077  299.55  5290.5  300.52
  5297.1  302.18  5302.3  301.23  5330.9  305.72  5336.1  304.66  5342.5  306.18
  5369.9  309.21  5375.1   308.5  5403.7  311.06  5408.9  310.42  5442.7  313.53
  5476.5  314.48  5481.7  313.74  5540.2  316.77    5561  316.36  5588.3   318.9
  5627.3  319.48  5654.6  321.45  5818.8  327.89  5918.5  331.06    5960  331.12
#Mann= 4 ,-1 , 0
  4276.9     .11       0  4669.1    .015       0  5342.5     .11       0
  5818.8     .17       0
#XS Ineff= 2 , 0
       0                  5330.9       0  305.72
Permanent Ineff=
       F       F
Bank Sta=4669.1,5342.5
XS Rating Curve= 0 ,0
Exp/Cntr=0.3,0.1

Type RM Length L Ch R = 1 ,2224    ,200,200,200
BEGIN DESCRIPTION:
Mapping XS 800df153
END DESCRIPTION:
XS GIS Cut Line= 3
      3796898.99     10222717.01      3796440.66     10222265.62
       3795662.9     10221626.75
#Sta/Elev= 30
  4361.3  320.69  4387.5  318.97  4408.7  318.55  4479.4  315.08  4606.7  307.22
  4620.9  305.03    4628  305.08  4642.1  306.79  4663.3  304.17  4670.4  302.27
  4712.8  300.39  4868.3  300.95  5449.9   300.1  5521.6   300.7  5599.8   300.1
  5604.3  299.91  5604.5  299.41  5620.6  300.91  5628.5   300.5  5670.1  302.59
    5678  303.78  5684.5  305.73  5713.2  306.12  5727.5  307.09  5770.6  308.96
  5805.7  311.93  5826.6  312.54  5876.1  316.36  5912.6  317.41  6011.1  322.06
#Mann= 3 , 0 , 0
  4361.3     .11       0  4606.7    .015       0  5727.5     .11       0
#XS Ineff= 2 , 0
       0  4642.1  306.79               0
Permanent Ineff=
       F       F
Bank Sta=4606.7,5727.5
XS Rating Curve= 0 ,0
Exp/Cntr=0.3,0.1

Type RM Length L Ch R = 1 ,2024    ,429,429,429
BEGIN DESCRIPTION:
Conroe Lake 067 5.0
END DESCRIPTION:
XS GIS Cut Line= 3
      3797175.48     10222501.17      3796593.58     10222135.42
      3795689.65     10221363.15
#Sta/Elev= 30
  4312.7  333.58  4346.2   332.5    4398  329.06  4463.4  326.93  4486.3  325.54
  4492.2  324.43  4528.7  323.77  4586.4  321.19  4622.9   317.6  4644.1  316.69
  4695.9  311.55  4717.1  310.46  4738.4  307.04  4746.9  305.06  4774.9  305.17
  4790.2  300.91  4824.9  300.16  5481.9  300.91  5574.1  307.41  5596.1  309.12
  5624.7  312.95  5674.1  314.11  5723.5  316.45  5801.4  317.67  5858.5  317.21
  5893.6  318.86  5922.2  318.64  5928.7  319.55  6063.8  324.03  6188.9  326.87
#Mann= 3 , 0 , 0
  4312.7     .11       0  4738.4    .015       0  5574.1     .11       0
#XS Ineff= 2 , 0
       0  4759.6  305.66               0
Permanent Ineff=
       F       F
Bank Sta=4738.4,5574.1
XS Rating Curve= 0 ,0
Exp/Cntr=0.3,0.1

Type RM Length L Ch R = 1 ,1595    ,340,340,340
BEGIN DESCRIPTION:
Conroe Lake 067 4.0
END DESCRIPTION:
XS GIS Cut Line= 3
      3797377.33     10221989.59      3796743.32     10221736.11
      3795767.23      10221305.4
#Sta/Elev= 30
  4317.2  322.64  4350.1  323.62  4378.2     324  4413.6  323.09  4437.5  321.36
  4456.3  318.93  4478.2  318.46  4515.6  315.75  4553.6  308.64    4564  307.74
  4575.1  305.46  4585.9  304.62  4607.4  300.85    4670  299.56  4715.1   300.7
  4790.5  300.64  4833.3   301.4  4855.1  300.77    5424  300.65  5486.9  305.83
  5592.7  310.52  5661.8  314.99  5668.1  318.29  5683.7   319.6  5705.5  318.81
  5760.2  319.24  5842.2  322.23  5978.8  325.01  6045.1  327.27  6066.9  327.19
#Mann= 4 ,-1 , 0
  4317.2     .17       0  4350.1     .11       0  4575.1    .015       0
  5486.9     .11       0
Bank Sta=4575.1,5486.9
XS Rating Curve= 0 ,0
Exp/Cntr=0.3,0.1

Type RM Length L Ch R = 1 ,1255    ,113,113,113
BEGIN DESCRIPTION:
Conroe Lake 067 3.0
END DESCRIPTION:
XS GIS Cut Line= 3
      3797375.99     10221766.49      3796817.11     10221404.08
       3795981.5     10220933.91
#Sta/Elev= 30
  4333.9  317.18  4402.7  316.52  4423.8  314.32  4481.2  311.39  4510.5   308.3
  4532.6  303.71  4553.7  300.77    4582  300.35  4994.7  300.52  5081.4  301.84
  5203.9  299.56  5228.6  300.73  5405.1  300.33  5435.2  304.01  5486.1  306.31
  5561.3  311.99  5604.6  313.69  5669.6  313.43  5728.9  314.78  5766.5  314.33
  5772.3  313.49  5788.2   314.6  5793.9  313.13  5809.9  314.37  5815.6   313.2
  5831.5  314.31  5837.3  312.93  5853.2  312.28  5905.6   313.9  5958.8   313.4
#Mann= 3 , 0 , 0
  4333.9     .11       0  4532.6    .015       0  5435.2     .11       0
Bank Sta=4532.6,5435.2
XS Rating Curve= 0 ,0
Exp/Cntr=0.3,0.1

Type RM Length L Ch R = 1 ,1142    ,97,97,97
BEGIN DESCRIPTION:
Mapping XS 430cb1c1
END DESCRIPTION:
XS GIS Cut Line= 3
       3797426.4     10221732.17      3796857.97     10221299.28
       3796012.1     10220850.19
#Sta/Elev= 30
  4285.5   313.8  4328.1  315.49  4384.3  314.57  4477.8  308.26  4506.9  304.52
  4540.5  301.19  4627.5  304.83  4856.2  307.67    4956  306.18  4970.5  307.32
  4991.3  305.63  5006.3   307.1    5012  305.89  5022.6  306.87  5028.3  305.52
  5079.4  307.27  5192.6  306.34  5286.5   304.6  5324.8   302.3  5368.7  302.28
    5517  309.62  5599.2  309.88  5648.9  307.69  5702.1  310.86  5709.2  310.83
  5714.8  308.87  5731.2  309.65  5775.1  308.05  5813.4  310.06  5957.7  310.87
#Mann= 3 , 0 , 0
  4285.5     .11       0  4506.9     .06       0  4627.5     .11       0
Bank Sta=4506.9,4627.5
XS Rating Curve= 0 ,0
Exp/Cntr=0.3,0.1

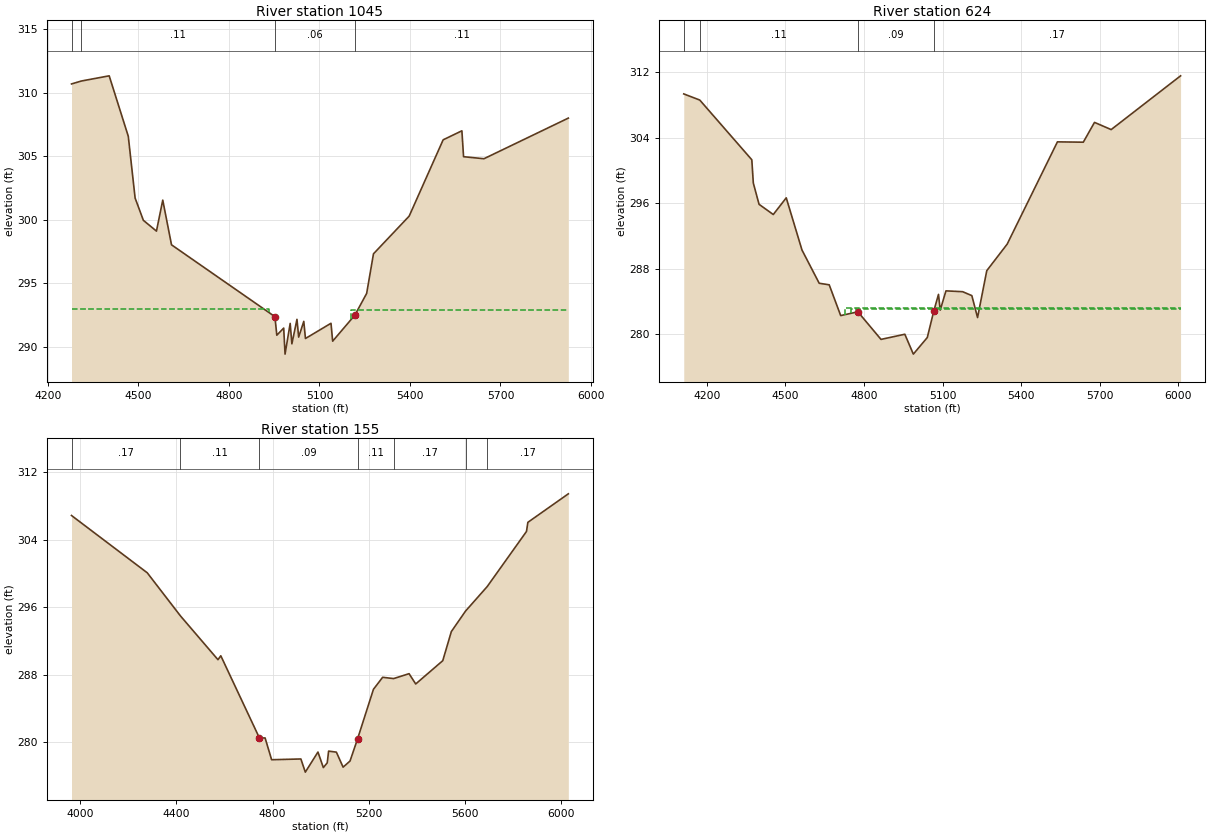
Type RM Length L Ch R = 1 ,1045    ,421,421,421
BEGIN DESCRIPTION:
Conroe Lake 067 2.0
END DESCRIPTION:
XS GIS Cut Line= 3
      3797467.13     10221646.69      3796893.44     10221208.32
      3796061.87     10220803.43
#Sta/Elev= 30
    4278   310.7  4310.4  310.93  4402.9  311.34  4466.2  306.58  4488.9  301.71
  4516.2  299.96  4559.6  299.11  4580.5  301.55  4609.5  298.03  4952.3  292.37
  4958.6  290.91  4981.4  291.47  4985.9  289.42  5002.9  291.84  5008.5  290.23
  5025.4  292.16    5031  290.76    5048     292  5053.5  290.65  5138.2  291.85
  5143.7  290.44  5217.5   292.5  5256.4   294.2    5279  297.32  5397.3  300.29
    5510   306.3  5572.1  307.01  5577.6  304.97  5645.2  304.81  5924.9  308.01
#Mann= 4 ,-1 , 0
    4278     .17       0  4310.4     .11       0  4952.3     .06       0
  5217.5     .11       0
#XS Ineff= 2 , 0
       0  4931.5     293  5205.8       0  292.91
Permanent Ineff=
       F       F
Bank Sta=4952.3,5217.5
XS Rating Curve= 0 ,0
Exp/Cntr=0.3,0.1

Type RM Length L Ch R = 1 ,624     ,469,469,469
BEGIN DESCRIPTION:
Mapping XS 62c34987
END DESCRIPTION:
XS GIS Cut Line= 3
      3797476.27     10221604.19      3797055.82     10220822.48
      3796293.93     10220161.43
#Sta/Elev= 30
  4112.4  309.34  4173.5  308.59  4372.2  301.29  4377.9  298.45  4399.8  295.85
  4454.1   294.6  4503.6  296.64  4563.7  290.26  4629.4   286.2  4667.6  286.01
  4711.4  282.25  4777.1  282.71  4865.3  279.34  4956.2  279.97  4988.7  277.54
    5042  279.57  5066.8  282.81  5084.7  284.84  5091.3  282.92  5113.2  285.27
  5176.8  285.17    5212  284.69  5233.8  282.01    5269  287.74  5346.8  290.98
  5538.7  303.48  5637.4  303.44  5680.2  305.86  5743.8  304.98  6008.7  311.55
#Mann= 4 ,-1 , 0
  4112.4     .17       0  4173.5     .11       0  4777.1     .09       0
  5066.8     .17       0
#XS Ineff= 3 ,-1
  4749.5  4727.6  283.02  4727.6  4705.7  283.14  5084.7  5254.7  284.84
Permanent Ineff=
       F       F       F
Bank Sta=4777.1,5066.8
XS Rating Curve= 0 ,0
Exp/Cntr=0.3,0.1

Type RM Length L Ch R = 1 ,155     ,0,0,0
BEGIN DESCRIPTION:
Conroe Lake 067 1.0
END DESCRIPTION:
XS GIS Cut Line= 3
      3797552.64     10221581.58      3797385.19     10220559.71
      3796477.55     10220075.34
#Sta/Elev= 30
  3964.5  306.89  4279.2   300.1  4417.1  294.99    4573   289.8  4584.9  290.26
  4745.3  280.52  4768.9  280.52    4796  277.94  4917.6  278.03    4936  276.47
  4988.5  278.85  5010.9  277.01  5027.1  277.57  5032.8  278.96    5065  278.84
    5093  277.06  5121.7  277.78  5153.2  280.42  5219.1  286.29  5257.3  287.71
    5303  287.56  5367.1  288.14  5394.7  286.92  5507.1  289.68  5542.7  293.13
  5601.7  295.56  5691.6  298.46    5855     305  5860.7  306.08  6028.8  309.46
#Mann= 7 ,-1 , 0
  3964.5     .17       0  4417.1     .11       0  4745.3     .09       0
  5153.2     .11       0    5303     .17       0  5601.7     .11       0
  5691.6     .17       0
#XS Ineff= 2 , 0
       0  4768.9  280.52               0
Permanent Ineff=
       F       F
Bank Sta=4745.3,5153.2
XS Rating Curve= 0 ,0
Exp/Cntr=0.3,0.1

Chan Stop Cuts=-1
Use User Specified Reach Order=0
Composite Channel Slope=5