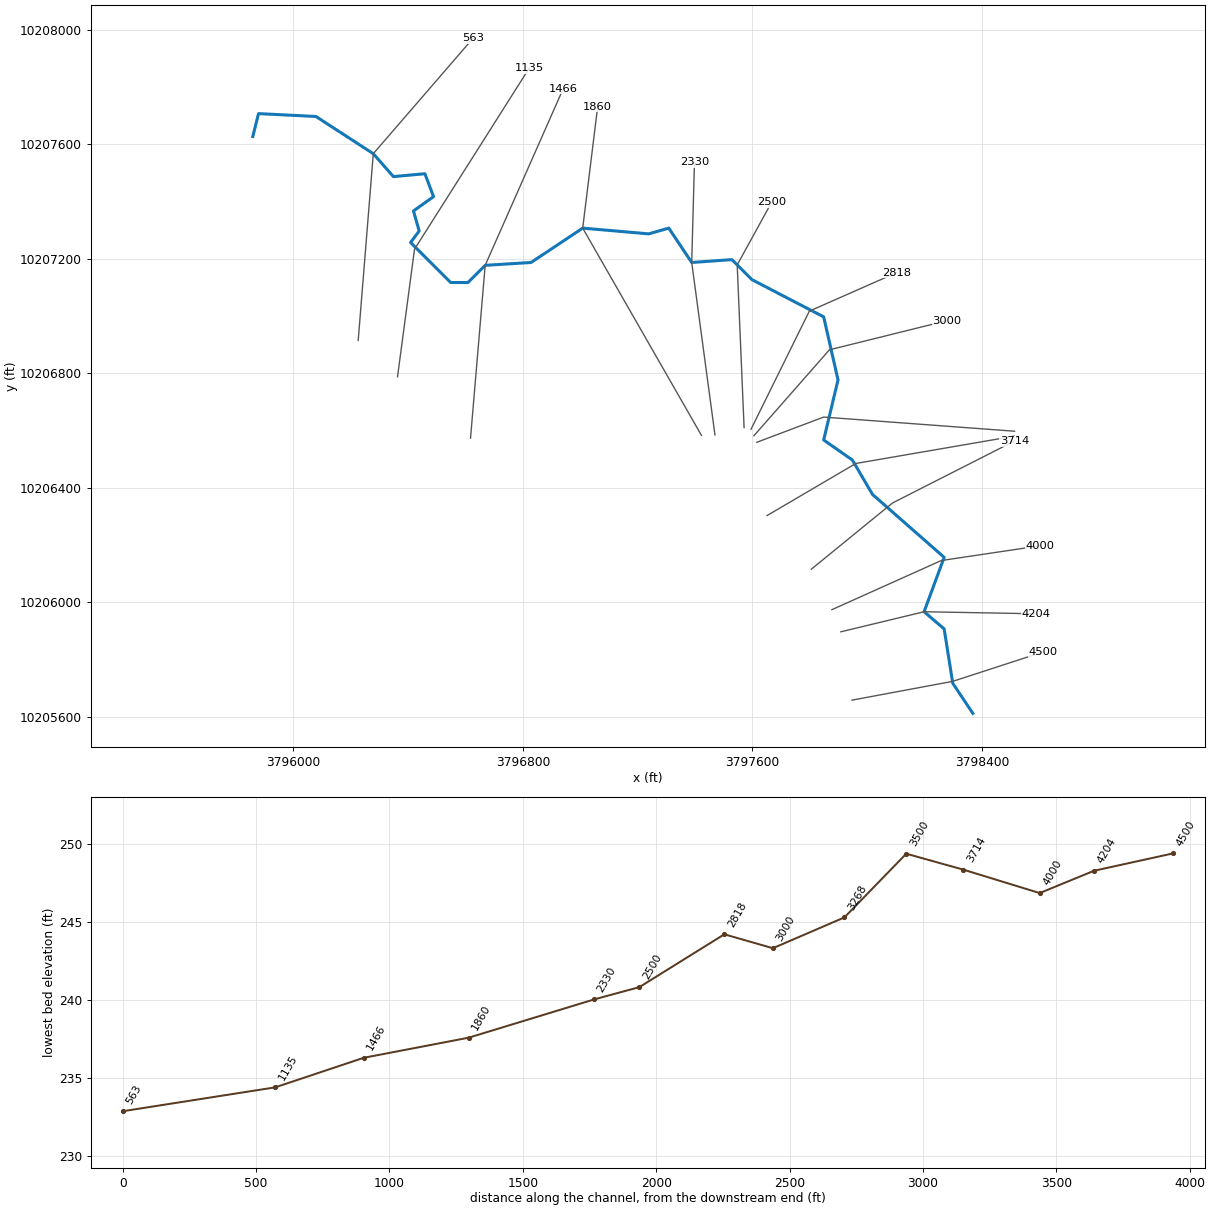
--- Conroe Lake 068.prj (project) ---

Proj Title=Conroe Lake 068 Base Level Engineering
Current Plan=p01
Default Exp/Contr=0.3,0.1
English Units
Geom File=g01
Flow File=f01
Flow File=f02
Plan File=p01
Y Axis Title=Elevation
X Axis Title(PF)=Main Channel Distance
X Axis Title(XS)=Station
BEGIN DESCRIPTION:
Conroe Lake 068
END DESCRIPTION:
DSS Export Rating Curves= 0
DSS Export Rating Curve Sorted= 0
DSS Export Volume Flow Curves= 0
DXF OffsetX= 0
DXF OffsetY= 0
DXF ScaleX= 1
DXF ScaleY= 10

--- Conroe Lake 068.p01 (plan) ---

Plan Title=Multiple Run
Short Identifier=Multiple
Geom File=g01
Flow File=f01
Subcritical Flow
K Sum by GR= 0
Std Step Tol= 0.01
Critical Tol= 0.01
Num of Std Step Trials= 20
Max Error Tol= 0.3
Flow Tol Ratio= 0.001
Split Flow NTrial= 30
Split Flow Tol= 0.02
Split Flow Ratio= 0.02
Log Output Level= 0
Friction Slope Method= 1
Unsteady Friction Slope Method= 2
Unsteady Bridges Friction Slope Method= 1
Parabolic Critical Depth
Global Vel Dist=  1 , 1 , 1
Global Log Level= 0
CheckData=True
Encroach Param= -1, 0, 0, 0
BEGIN DESCRIPTION:
Multiple Run
END DESCRIPTION:

--- Conroe Lake 068.f01 (steady flow) ---

Flow Title=Multiple
Program Version=4.10
Number of Profiles= 7
Profile Names=10-year,25-year,50-year,1pct_min,100-year,1pct_plu,500-year
River Rch & RM=Conroe Lake 068,Reach-1         ,4500
     575     778    1051     468    1413    4267    2638
River Rch & RM=Conroe Lake 068,Reach-1         ,4000
     686     934    1267     566    1708    5158    3211
Boundary for River Rch & Prof#=Conroe Lake 068,Reach-1         , 1
Up Type= 0
Dn Type= 3
Dn Slope=0.005
Boundary for River Rch & Prof#=Conroe Lake 068,Reach-1         , 2
Up Type= 0
Dn Type= 3
Dn Slope=0.005
Boundary for River Rch & Prof#=Conroe Lake 068,Reach-1         , 3
Up Type= 0
Dn Type= 3
Dn Slope=0.005
Boundary for River Rch & Prof#=Conroe Lake 068,Reach-1         , 4
Up Type= 0
Dn Type= 3
Dn Slope=0.005
Boundary for River Rch & Prof#=Conroe Lake 068,Reach-1         , 5
Up Type= 0
Dn Type= 3
Dn Slope=0.005
Boundary for River Rch & Prof#=Conroe Lake 068,Reach-1         , 6
Up Type= 0
Dn Type= 3
Dn Slope=0.005
Boundary for River Rch & Prof#=Conroe Lake 068,Reach-1         , 7
Up Type= 0
Dn Type= 3
Dn Slope=0.005
DSS Import GetInterval= 0
DSS Import GetPeak= 0
DSS Import FillOption= 0

--- Conroe Lake 068.f02 (steady flow) ---

Flow Title=Orig_BLE_Flow
Program Version=4.10
Number of Profiles= 7
Profile Names=10-year,25-year,50-year,1pct_min,100-year,1pct_plu,500-year
River Rch & RM=Conroe Lake 068,Reach-1         ,4500
     575     763     914     360    1087    3282    1534
River Rch & RM=Conroe Lake 068,Reach-1         ,4000
     686     916    1102     435    1314    3969    1867
Boundary for River Rch & Prof#=Conroe Lake 068,Reach-1         , 1
Up Type= 0
Dn Type= 3
Dn Slope=0.005
Boundary for River Rch & Prof#=Conroe Lake 068,Reach-1         , 2
Up Type= 0
Dn Type= 3
Dn Slope=0.005
Boundary for River Rch & Prof#=Conroe Lake 068,Reach-1         , 3
Up Type= 0
Dn Type= 3
Dn Slope=0.005
Boundary for River Rch & Prof#=Conroe Lake 068,Reach-1         , 4
Up Type= 0
Dn Type= 3
Dn Slope=0.005
Boundary for River Rch & Prof#=Conroe Lake 068,Reach-1         , 5
Up Type= 0
Dn Type= 3
Dn Slope=0.005
Boundary for River Rch & Prof#=Conroe Lake 068,Reach-1         , 6
Up Type= 0
Dn Type= 3
Dn Slope=0.005
Boundary for River Rch & Prof#=Conroe Lake 068,Reach-1         , 7
Up Type= 0
Dn Type= 3
Dn Slope=0.005
DSS Import GetInterval= 0
DSS Import GetPeak= 0
DSS Import FillOption= 0

--- Conroe Lake 068.g01 (geometry) ---

Geom Title=Existing Conditions
Program Version=4.10

River Reach=Conroe Lake 068 ,Reach-1
Reach XY= 30
      3798368.23     10205611.84      3798298.23     10205716.84
      3798268.23     10205906.84      3798198.23     10205966.84
      3798268.23     10206156.84      3798018.23     10206376.84
      3797948.23     10206496.84      3797848.23     10206566.84
      3797898.23     10206776.84      3797848.23     10206996.84
      3797598.23     10207126.84      3797528.23     10207196.84
      3797388.23     10207186.84      3797308.23     10207306.84
      3797238.23     10207286.84      3797008.23     10207306.84
      3796828.23     10207186.84      3796668.23     10207176.84
      3796608.23     10207116.84      3796548.23     10207116.84
      3796408.23     10207256.84      3796438.23     10207296.84
      3796418.23     10207366.84      3796488.23     10207416.84
      3796458.23     10207496.84      3796348.23     10207486.84
      3796278.23     10207566.84      3796078.23     10207696.84
      3795878.23     10207706.84      3795858.23     10207626.84

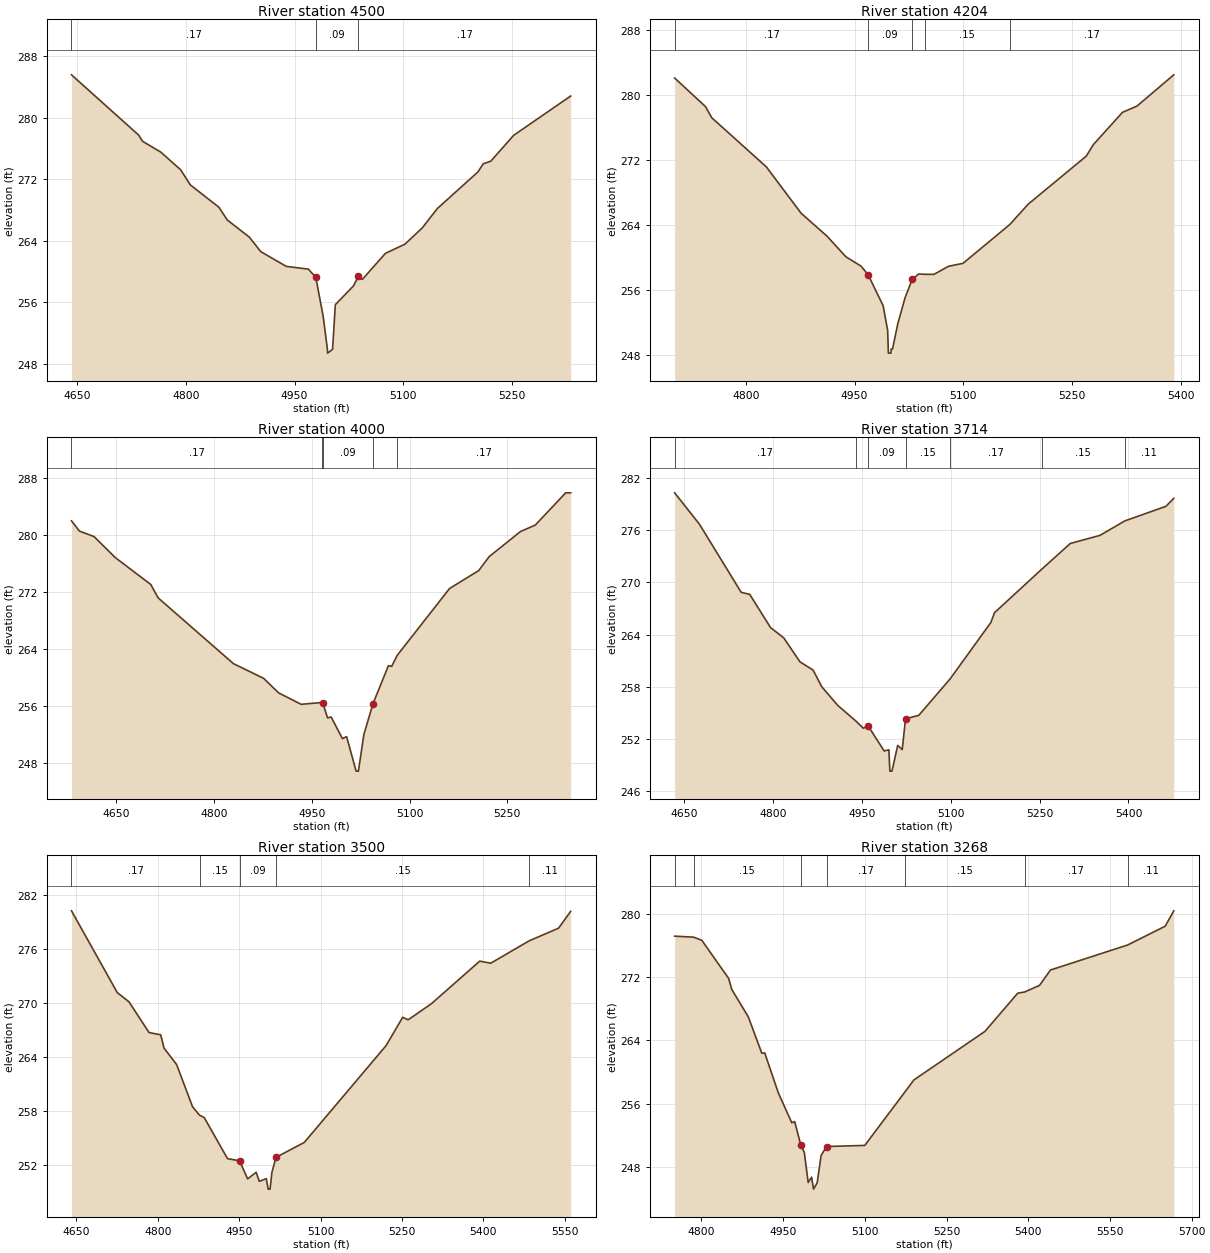
Type RM Length L Ch R = 1 ,4500    ,296,296,296
BEGIN DESCRIPTION:
Conroe Lake 068 9.5
END DESCRIPTION:
XS GIS Cut Line= 3
      3797946.81     10205658.06      3798298.23     10205723.73
      3798612.57     10205826.15
#Sta/Elev= 30
  4642.5  285.56  4735.1  277.72  4740.4  276.92  4765.6  275.51    4793  273.21
  4806.3  271.25  4845.7  268.34  4857.2  266.69  4887.7  264.45  4903.4  262.57
  4938.6  260.65  4969.1  260.29  4979.3  259.21  4989.4  254.18  4995.3  249.87
  4995.5  249.37  5002.4  249.87  5006.2  255.67  5031.2  258.11  5038.1  259.37
  5043.4  258.95  5075.3  262.35    5102  263.53  5125.8  265.63  5146.8  268.17
    5203  272.95    5210  273.99  5220.5  274.33    5252  277.69  5330.6   282.8
#Mann= 3 , 0 , 0
  4642.5     .17       0  4979.3     .09       0  5038.1     .17       0
Bank Sta=4979.3,5038.1
XS Rating Curve= 0 ,0
Exp/Cntr=0.3,0.1

Type RM Length L Ch R = 1 ,4204    ,204,204,204
BEGIN DESCRIPTION:
Conroe Lake 068 9.0
END DESCRIPTION:
XS GIS Cut Line= 3
      3797908.17      10205896.8      3798198.23     10205966.84
      3798588.66     10205959.71
#Sta/Elev= 30
  4701.6  282.06  4744.3  278.54  4752.7  277.19  4828.1  271.15  4876.2  265.44
  4911.8  262.64  4937.9   260.1  4958.9  258.95  4968.7  257.88  4989.3   254.1
  4995.6  251.07  4996.6  248.26  5000.1  248.26  5000.4  248.76  5002.3  248.76
  5009.6  251.87  5019.6  255.05  5029.6  257.34  5038.5  257.99    5047  257.94
  5059.6  257.94  5079.6  258.93  5099.6  259.29  5163.9  264.04  5189.7  266.57
  5269.7  272.46  5279.7   273.9  5319.7  277.84  5339.7  278.61  5390.5  282.45
#Mann= 5 ,-1 , 0
  4701.6     .17       0  4968.7     .09       0  5029.6     .17       0
    5047     .15       0  5163.9     .17       0
Bank Sta=4968.7,5029.6
XS Rating Curve= 0 ,0
Exp/Cntr=0.3,0.1

Type RM Length L Ch R = 1 ,4000    ,286,286,286
BEGIN DESCRIPTION:
Conroe Lake 068 8.5
END DESCRIPTION:
XS GIS Cut Line= 3
       3797876.7       10205974.      3798258.23     10206145.74
      3798601.52     10206197.03
#Sta/Elev= 30
  4581.6  281.94  4593.8   280.5  4616.1  279.74  4648.7  276.79  4703.2  273.01
  4714.5  271.13  4829.9  261.91  4876.2  259.85  4899.4   257.8  4933.8   256.2
  4965.8  256.46  4966.7  256.45  4974.3   254.3  4979.8  254.42  4997.1  251.39
  5003.5  251.67  5018.1  246.83  5021.6  246.83    5030  251.98 5043.98  256.29
  5067.6  261.62  5072.7  261.53  5081.1  263.07  5161.4  272.45  5206.1  274.96
  5222.1  276.92  5270.3  280.45  5292.8  281.34  5339.5  285.87  5347.1  285.87
#Mann= 5 ,-1 , 0
  4581.6     .17       0  4965.8     .15       0  4966.7     .09       0
 5043.98     .15       0  5081.1     .17       0
Bank Sta=4966.7,5043.98
XS Rating Curve= 0 ,0
Exp/Cntr=0.3,0.1

Type RM Length L Ch R = 1 ,3714    ,214,214,214
BEGIN DESCRIPTION:
Conroe Lake 068 8.0
END DESCRIPTION:
XS GIS Cut Line= 3
      3797805.23     10206115.54      3798088.23     10206346.84
      3798512.88     10206563.01
#Sta/Elev= 30
  4634.5  280.26  4676.5  276.65  4746.8  268.84  4761.2  268.61  4796.3   264.8
  4818.6  263.62  4845.9  260.87  4868.1  259.92  4882.5  258.03  4909.8  255.86
  4940.2  254.08  4952.8  253.25  4960.7  253.54    4988  250.64  4995.9  250.78
  4997.6  248.33  5001.1  248.33  5010.8  251.28  5018.4   250.8    5024  254.34
  5046.2  254.72  5099.3  258.92  5167.9  265.38  5174.1  266.51  5253.7  271.49
  5301.9  274.45    5352  275.38    5394  277.04  5463.2  278.71  5476.5  279.63
#Mann= 7 ,-1 , 0
  4634.5     .17       0  4940.2     .15       0  4960.7     .09       0
    5024     .15       0  5099.3     .17       0  5253.7     .15       0
    5394     .11       0
Bank Sta=4960.7,5024
XS Rating Curve= 0 ,0
Exp/Cntr=0.3,0.1

Type RM Length L Ch R = 1 ,3500    ,232,232,232
BEGIN DESCRIPTION:
Conroe Lake 068 7.5
END DESCRIPTION:
XS GIS Cut Line= 3
      3797650.83     10206302.83      3797960.31     10206484.76
      3798512.93     10206580.19
#Sta/Elev= 30
    4641  280.28  4725.4  271.19  4746.9  270.17    4784  266.75  4805.5   266.5
  4811.5  265.02  4834.7   263.2  4864.1   258.5  4876.9  257.57  4885.6   257.3
  4928.5  252.74  4950.7   252.5  4965.6  250.49  4981.3  251.22  4987.1  250.21
    5000  250.52  5003.4  249.35  5006.9  249.35  5010.2  251.18  5017.8  252.88
    5070  254.54  5220.8  265.31  5251.2  268.44  5261.4  268.17  5304.3  269.96
  5393.3  274.69  5413.6  274.46  5484.5  276.95  5538.5  278.35  5560.8  280.22
#Mann= 5 ,-1 , 0
    4641     .17       0  4876.9     .15       0  4950.7     .09       0
  5017.8     .15       0  5484.5     .11       0
Bank Sta=4950.7,5017.8
XS Rating Curve= 0 ,0
Exp/Cntr=0.3,0.1

Type RM Length L Ch R = 1 ,3268    ,268,268,268
BEGIN DESCRIPTION:
Conroe Lake 068 7.0
END DESCRIPTION:
XS GIS Cut Line= 3
      3797615.12     10206558.76      3797848.23     10206646.84
       3798513.6      10206597.4
#Sta/Elev= 30
  4750.8  277.15  4785.9  277.02  4800.8  276.62  4849.9  271.83  4855.8  270.42
    4886  266.99  4910.8   262.4  4916.2  262.44    4941  257.43  4965.9  253.63
  4971.2  253.78 4982.55  250.79  4988.9  249.89    4996  246.11  5002.3  246.78
  5005.8  245.27  5012.5  246.07  5019.7   249.5  5029.7  250.64  5099.9  250.78
  5174.5   257.6  5190.1  259.03  5320.5  265.15  5380.7  269.96  5393.7  270.12
  5420.8  270.95  5440.8  272.88  5582.7  276.04  5651.4   278.4  5667.2  280.34
#Mann= 7 ,-1 , 0
  4750.8     .17       0  4785.9     .15       0 4982.55     .09       0
  5029.7     .17       0  5174.5     .15       0  5393.7     .17       0
  5582.7     .11       0
Bank Sta=4982.55,5029.7
XS Rating Curve= 0 ,0
Exp/Cntr=0.3,0.1

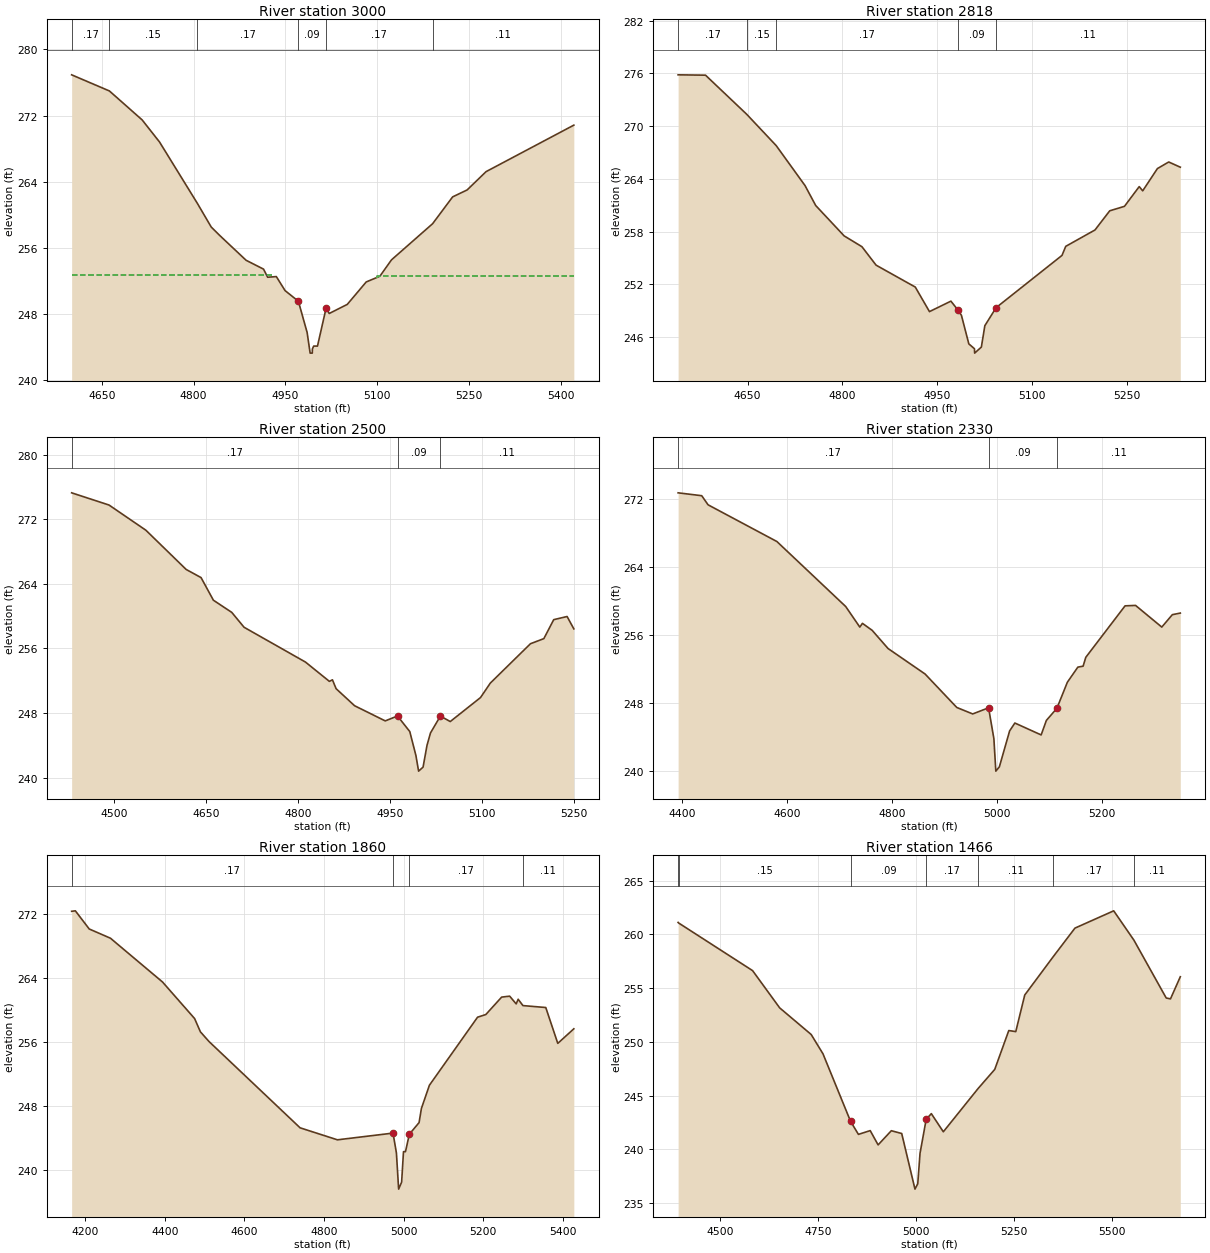
Type RM Length L Ch R = 1 ,3000    ,182,182,182
BEGIN DESCRIPTION:
Conroe Lake 068 6.5
END DESCRIPTION:
XS GIS Cut Line= 3
      3797605.06      10206581.6      3797868.23     10206881.77
        3798277.     10206983.35
#Sta/Elev= 30
  4600.8  276.93  4662.5  274.98    4716  271.48  4744.4  268.81    4806  261.42
  4828.9  258.53  4843.1  257.49  4885.8  254.52  4914.3  253.45    4921  252.47
  4935.2  252.55  4949.4  250.86  4971.2  249.57  4985.5  245.79  4990.4   243.3
  4993.9   243.3  4994.1   243.8  4996.2  244.15  5002.4  244.15  5016.5  248.74
  5021.6  248.09  5051.1  249.19    5082   251.9  5104.3  252.59  5123.3  254.57
  5190.5  258.94  5223.2  262.18  5246.9  263.02  5277.8  265.23  5421.2  270.85
#Mann= 6 ,-1 , 0
  4600.8     .17       0  4662.5     .15       0    4806     .17       0
  4971.2     .09       0  5016.5     .17       0  5190.5     .11       0
#XS Ineff= 2 , 0
       0  4928.5  252.78  5099.1       0  252.66
Permanent Ineff=
       F       F
Bank Sta=4971.2,5016.5
XS Rating Curve= 0 ,0
Exp/Cntr=0.3,0.1

Type RM Length L Ch R = 1 ,2818    ,318,318,318
BEGIN DESCRIPTION:
Conroe Lake 068 6.0
END DESCRIPTION:
XS GIS Cut Line= 3
      3797595.06     10206604.48      3797798.23     10207016.84
      3798103.43     10207151.79
#Sta/Elev= 30
  4540.3  275.83  4583.6  275.79  4648.6  271.35  4695.3  267.78  4740.8  263.24
  4757.7  260.97  4802.6  257.52  4830.7  256.29  4853.1  254.19    4915   251.7
  4937.4  248.91  4971.3   250.1  4982.3   249.1  4987.9  248.49  4999.6  245.24
  5008.5  244.69  5008.8  244.19  5019.4  244.88  5024.9  247.31  5042.7  249.36
  5146.8   255.3  5152.7  256.33  5198.9  258.19  5222.2  260.37  5245.5  260.88
  5268.8  263.12  5274.3  262.64  5297.5  265.17  5315.4  265.92  5333.7  265.33
#Mann= 5 ,-1 , 0
  4540.3     .17       0  4648.6     .15       0  4695.3     .17       0
  4982.3     .09       0  5042.7     .11       0
Bank Sta=4982.3,5042.7
XS Rating Curve= 0 ,0
Exp/Cntr=0.3,0.1

Type RM Length L Ch R = 1 ,2500    ,170,170,170
BEGIN DESCRIPTION:
Conroe Lake 068 5.5
END DESCRIPTION:
XS GIS Cut Line= 3
      3797570.76     10206610.22      3797546.76     10207178.32
      3797667.05      10207397.7
#Sta/Elev= 30
  4431.4  275.28  4492.3  273.77  4552.4  270.65  4618.1  265.79  4642.4  264.78
  4662.5  261.98  4692.5  260.47  4712.5  258.63  4812.6  254.32  4851.6  251.93
  4856.6  252.12  4862.6  251.02  4892.7  248.91  4942.7  247.03  4962.7  247.64
  4982.7  245.71  4992.7  242.75  4997.1  240.81  5004.4  241.31  5010.8  244.01
  5016.5  245.54  5032.6  247.63  5048.7  246.95    5098  249.92  5114.1  251.72
  5179.5  256.59  5201.3  257.22  5217.4  259.57  5239.2  259.96  5250.2  258.43
#Mann= 3 , 0 , 0
  4431.4     .17       0  4962.7     .09       0  5032.6     .11       0
Bank Sta=4962.7,5032.6
XS Rating Curve= 0 ,0
Exp/Cntr=0.3,0.1

Type RM Length L Ch R = 1 ,2330    ,470,470,470
BEGIN DESCRIPTION:
Conroe Lake 068 5.0
END DESCRIPTION:
XS GIS Cut Line= 3
      3797469.26     10206584.47      3797388.23     10207186.84
      3797397.76     10207536.31
#Sta/Elev= 30
  4392.2  272.77  4437.2  272.43  4449.3  271.36  4580.5  267.04  4711.7  259.39
  4738.6  256.97  4743.6  257.41  4762.1  256.59  4792.4  254.45    4863  251.45
  4923.5  247.51  4953.8  246.75  4984.1  247.47  4994.2  243.84  4997.9  240.02
  5004.6  240.52  5024.2  244.75  5034.2  245.68  5084.3  244.28  5094.3  245.99
  5114.3  247.41  5134.3  250.48  5154.3  252.26  5164.3  252.37  5169.4  253.41
  5244.3  259.47  5264.3  259.52  5314.3  256.97  5334.4  258.43  5349.6  258.62
#Mann= 3 , 0 , 0
  4392.2     .17       0  4984.1     .09       0  5114.3     .11       0
Bank Sta=4984.1,5114.3
XS Rating Curve= 0 ,0
Exp/Cntr=0.3,0.1

Type RM Length L Ch R = 1 ,1860    ,394,394,394
BEGIN DESCRIPTION:
Conroe Lake 068 4.0
END DESCRIPTION:
XS GIS Cut Line= 3
       3797422.1     10206583.01      3797008.23     10207306.84
      3797060.37     10207731.05
#Sta/Elev= 30
  4166.2  272.28  4175.5  272.34  4210.4  270.07  4263.6  268.92  4394.4  263.45
    4475  258.88  4489.6  257.22  4511.2  256.01  4739.9  245.23  4833.7  243.73
  4973.3  244.57  4981.8   242.1  4987.4  237.57  4994.9  238.44  4999.6  242.25
  5004.6  242.25  5014.3  244.43  5038.7  245.88  5044.6  247.65  5064.7  250.55
  5185.6  259.05  5206.3  259.38  5246.1  261.56  5266.2  261.68  5282.6  260.71
  5287.6  261.29  5299.6   260.5  5356.9  260.26  5387.1  255.78  5427.4   257.6
#Mann= 4 ,-1 , 0
  4166.2     .17       0  4973.3     .09       0  5014.3     .17       0
  5299.6     .11       0
Bank Sta=4973.3,5014.3
XS Rating Curve= 0 ,0
Exp/Cntr=0.3,0.1

Type RM Length L Ch R = 1 ,1466    ,331,331,331
BEGIN DESCRIPTION:
Conroe Lake 068 3.0
END DESCRIPTION:
XS GIS Cut Line= 3
      3796617.17       10206573.      3796668.23     10207176.84
      3796940.26     10207793.95
#Sta/Elev= 30
    4394  261.12  4395.2  261.07  4583.9  256.63    4653  253.16  4733.3  250.68
  4763.4  248.88  4833.6   242.6  4853.7  241.38  4883.8  241.73  4903.9   240.4
  4937.6  241.72  4964.1  241.46  4997.9  236.28    5005  236.78  5010.8  239.62
  5026.5  242.78  5039.6  243.31  5070.2  241.62  5159.1  245.66  5201.3  247.43
  5237.1  251.05  5254.9  250.95  5277.8  254.36  5349.8   257.9  5405.8  260.59
  5504.6   262.2  5556.1  259.47  5638.5  254.08  5649.4     254  5674.4  256.06
#Mann= 7 ,-1 , 0
    4394     .17       0  4395.2     .15       0  4833.6     .09       0
  5026.5     .17       0  5159.1     .11       0  5349.8     .17       0
  5556.1     .11       0
Bank Sta=4833.6,5026.5
XS Rating Curve= 0 ,0
Exp/Cntr=0.3,0.1

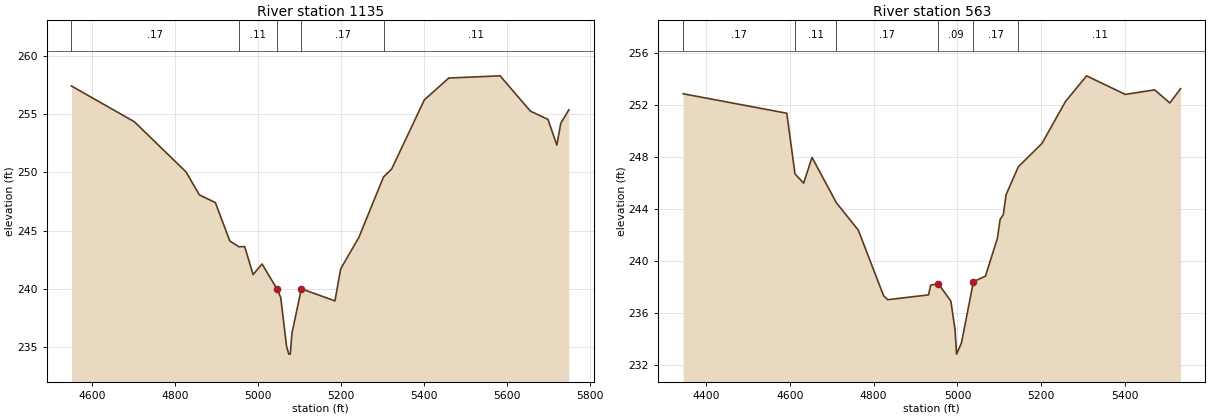
Type RM Length L Ch R = 1 ,1135    ,572,572,572
BEGIN DESCRIPTION:
Conroe Lake 068 2.0
END DESCRIPTION:
XS GIS Cut Line= 3
      3796362.69     10206787.47      3796421.93     10207233.15
      3796821.59     10207865.42
#Sta/Elev= 30
  4550.4  257.41  4701.9  254.34  4826.4  250.03  4858.5  248.06    4897   247.4
  4931.7  244.11  4953.5  243.61  4967.6  243.62  4987.8  241.22  5009.4  242.13
    5045     240  5054.3  239.26  5068.5  235.04  5073.8  234.39  5077.3  234.39
  5081.4  236.19    5104     240  5184.9  238.96  5198.7  241.71  5242.5  244.41
  5301.8   249.6  5321.4  250.28  5400.2  256.22  5458.9  258.09  5582.5  258.28
  5655.5  255.25  5697.8  254.54  5719.2  252.33  5728.4  254.19    5748  255.36
#Mann= 5 ,-1 , 0
  4550.4     .17       0  4953.5     .11       0    5045     .06       0
    5104     .17       0  5301.8     .11       0
Bank Sta=5045,5104
XS Rating Curve= 0 ,0
Exp/Cntr=0.3,0.1

Type RM Length L Ch R = 1 ,563     ,0,0,0
BEGIN DESCRIPTION:
Conroe Lake 068 1.0
END DESCRIPTION:
XS GIS Cut Line= 3
      3796225.62     10206914.56      3796278.23     10207566.84
      3796625.73      10207969.8
#Sta/Elev= 30
  4345.6   252.9  4592.9   251.4  4612.5  246.73    4633  246.02  4653.1     248
  4711.4   244.5  4763.5   242.4  4823.7  237.36  4833.7  237.05    4931  237.42
  4936.1  238.17  4954.1  238.28  4984.2  236.95  4994.2  234.76  4997.9  232.86
  5009.6  233.73  5038.1  238.44  5066.7  238.86  5095.2  241.77  5101.8  243.23
  5109.4   243.6    5116  245.14  5145.2  247.28  5201.6  249.08  5257.6   252.3
    5308  254.28  5400.2  252.85  5470.4   253.2  5506.6  252.19  5532.1  253.29
#Mann= 6 ,-1 , 0
  4345.6     .17       0  4612.5     .11       0  4711.4     .17       0
  4954.1     .09       0  5038.1     .17       0  5145.2     .11       0
Bank Sta=4954.1,5038.1
XS Rating Curve= 0 ,0
Exp/Cntr=0.3,0.1

Chan Stop Cuts=-1
Use User Specified Reach Order=0
Composite Channel Slope=5