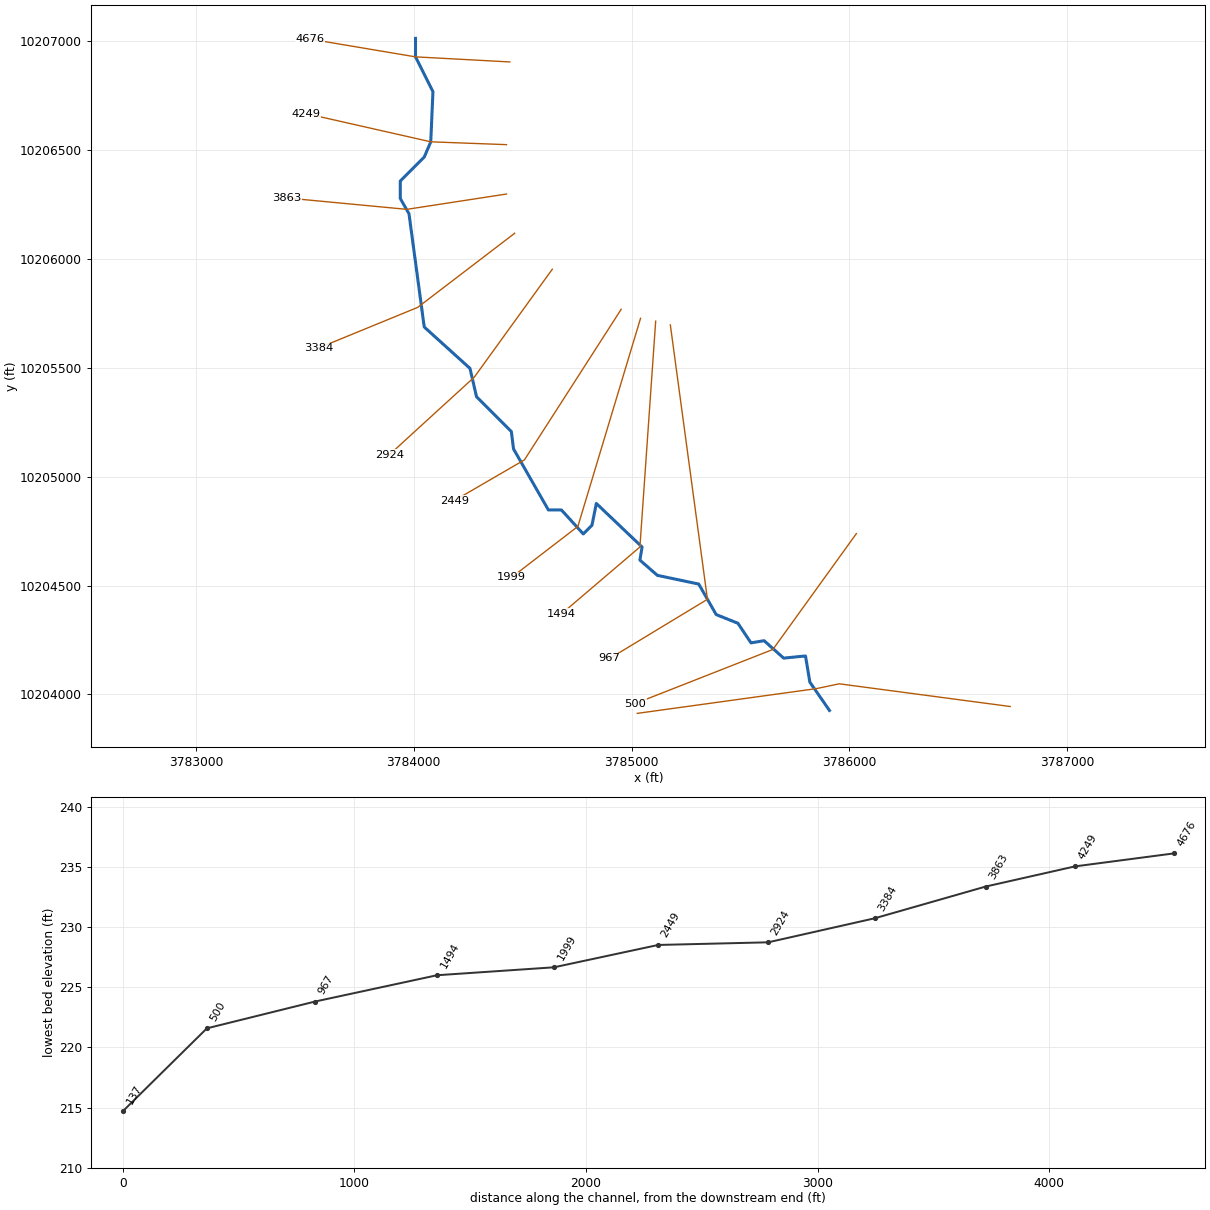
--- Conroe Lake 069.prj (project) ---

Proj Title=Conroe Lake 069 Base Level Engineering
Current Plan=p01
Default Exp/Contr=0.3,0.1
English Units
Geom File=g01
Flow File=f01
Flow File=f02
Plan File=p01
Y Axis Title=Elevation
X Axis Title(PF)=Main Channel Distance
X Axis Title(XS)=Station
BEGIN DESCRIPTION:
Conroe Lake 069
END DESCRIPTION:
DSS File=dss
DSS Export Rating Curves= 0
DSS Export Rating Curve Sorted= 0
DSS Export Volume Flow Curves= 0
DXF OffsetX= 0
DXF OffsetY= 0
DXF ScaleX= 1
DXF ScaleY= 10

--- Conroe Lake 069.p01 (plan) ---

Plan Title=Multiple Run
Program Version=4.10
Short Identifier=Multiple Run
Geom File=g01
Flow File=f01
Subcritical Flow
K Sum by GR= 0
Std Step Tol= 0.01
Critical Tol= 0.01
Num of Std Step Trials= 20
Max Error Tol= 0.3
Flow Tol Ratio= 0.001
Split Flow NTrial= 30
Split Flow Tol= 0.02
Split Flow Ratio= 0.02
Log Output Level= 0
Friction Slope Method= 1
Unsteady Friction Slope Method= 2
Unsteady Bridges Friction Slope Method= 1
Parabolic Critical Depth
Global Vel Dist= 1 , 1 , 1
Global Log Level= 0
CheckData=True
Encroach Param=-1 ,0,0, 0
BEGIN DESCRIPTION:
Multiple Run
END DESCRIPTION:
Computation Interval=1HOUR
Output Interval=1HOUR
Run HTab= 0
Run UNet= 0
Run PostProcess= 0
Run WQNet= 0
UNET Theta= 1
UNET Theta Warmup= 1
UNET ZTol= 0.02
UNET ZSATol= 0.05
UNET MxIter= 20
UNET MaxInSteps= 0
UNET DtIC= 0
UNET DtMin= 0
UNET MaxCRTS= 20
UNET WFStab= 2
UNET SFStab= 1
UNET WFX= 1
UNET SFX= 1
UNET DSS MLevel= 4
UNET DZMax Abort= 100
UNET Convert EG Bridges= 0
UNET Use Existing IB Tables=-1
UNET Froude Reduction=False
UNET Froude Limit= 1
UNET Froude Power= 10
UNET Time Slicing=0,0, 5
UNET Junction Losses=0
Instantaneous Interval=1HOUR
DSS File=dss
Write IC File= 0
Write IC File at Sim End=0
Echo Input=False
Echo Parameters=False
Echo Output=False
Write Detailed= 0
WQ AD Non Conservative
WQ ULTIMATE=-1
WQ Max Comp Step=1HOUR
WQ Output Interval=15MIN
WQ Output Selected Increments= 0
WQ Output face flow=0
WQ Output face velocity=0
WQ Output face area=0
WQ Output face dispersion=0
WQ Output cell volume=0
WQ Output cell surface area=0
WQ Output cell continuity=0
WQ Output cumulative cell continuity=0
WQ Output face conc=0
WQ Output face dconc_dx=0
WQ Output face courant=0
WQ Output face peclet=0
WQ Output face adv mass=0
WQ Output face disp mass=0
WQ Output cell mass=0
WQ Output cell source sink temp=0
WQ Output cell source sink nsm=0
WQ Output MaxMinRange=-1
WQ Daily Max Min Mean=-1
WQ Daily Range=0
WQ Daily Time=0
WQ Create Restart=0
WQ Fixed Restart=0
WQ System Summary=0
WQ Use Fixed Temperature=0
Sorting and Armoring Iterations= 10
XS Update Threshold= 0.02
Hydraulics Update Threshold= 0.02
Energy Slope Method= 1
Volume Change Method= 0
XS Weighting Method= 0
Number of US Weighted Cross Sections= 1
Number of DS Weighted Cross Sections= 1
Upstream XS Weight=0.25
Main XS Weight=0.5
Downstream XS Weight=0.25
Number of DS XS's Weighted with US Boundary= 1
Upstream Boundary Weight= 1
Weight of XSs Associated with US Boundary= 0
Number of US XS's Weighted with DS Boundary= 1
Downstream Boundary Weight= 0.5
Weight of XSs Associated with DS Boundary= 0.5
Sediment Output Level= 4
Mass or Volume Output= 0
Output Increment Type= 1
Profile and TS Output Increment= 10
XS Output Flag= 0
XS Output Increment= 10
Disregard all LS=0
Disregard all Conn=0
Disregard all Breaches=0
Disregard all Pumps=0

--- Conroe Lake 069.f01 (steady flow) ---

Flow Title=Multiple
Program Version=4.10
Number of Profiles= 7
Profile Names=10-year,25-year,50-year,1pct_min,100-year,1pct_plu,500-year
River Rch & RM=Conroe Lake 069,Reach-1         ,4676
     503     673     904     400    1208    3648    2229
River Rch & RM=Conroe Lake 069,Reach-1         ,4249
     543     725     972     429    1296    3914    2375
River Rch & RM=Conroe Lake 069,Reach-1         ,137
    1986    2833    3963    1817    5486   16567   10881
Boundary for River Rch & Prof#=Conroe Lake 069,Reach-1         , 1
Up Type= 0
Dn Type= 3
Dn Slope=0.02
Boundary for River Rch & Prof#=Conroe Lake 069,Reach-1         , 2
Up Type= 0
Dn Type= 3
Dn Slope=0.02
Boundary for River Rch & Prof#=Conroe Lake 069,Reach-1         , 3
Up Type= 0
Dn Type= 3
Dn Slope=0.02
Boundary for River Rch & Prof#=Conroe Lake 069,Reach-1         , 4
Up Type= 0
Dn Type= 3
Dn Slope=0.02
Boundary for River Rch & Prof#=Conroe Lake 069,Reach-1         , 5
Up Type= 0
Dn Type= 3
Dn Slope=0.02
Boundary for River Rch & Prof#=Conroe Lake 069,Reach-1         , 6
Up Type= 0
Dn Type= 3
Dn Slope=0.02
Boundary for River Rch & Prof#=Conroe Lake 069,Reach-1         , 7
Up Type= 0
Dn Type= 3
Dn Slope=0.02
DSS Import GetInterval= 0
DSS Import GetPeak= 0
DSS Import FillOption= 0

--- Conroe Lake 069.f02 (steady flow) ---

Flow Title=Orig_BLE_Flow
Program Version=4.10
Number of Profiles= 7
Profile Names=10-year,25-year,50-year,1pct_min,100-year,1pct_plu,500-year
River Rch & RM=Conroe Lake 069,Reach-1         ,4676
     503     660     786     308     929    2806    1296
River Rch & RM=Conroe Lake 069,Reach-1         ,4249
     543     711     845     330     997    3010    1381
Boundary for River Rch & Prof#=Conroe Lake 069,Reach-1         , 1
Up Type= 0
Dn Type= 3
Dn Slope=0.01
Boundary for River Rch & Prof#=Conroe Lake 069,Reach-1         , 2
Up Type= 0
Dn Type= 3
Dn Slope=0.01
Boundary for River Rch & Prof#=Conroe Lake 069,Reach-1         , 3
Up Type= 0
Dn Type= 3
Dn Slope=0.01
Boundary for River Rch & Prof#=Conroe Lake 069,Reach-1         , 4
Up Type= 0
Dn Type= 3
Dn Slope=0.01
Boundary for River Rch & Prof#=Conroe Lake 069,Reach-1         , 5
Up Type= 0
Dn Type= 3
Dn Slope=0.01
Boundary for River Rch & Prof#=Conroe Lake 069,Reach-1         , 6
Up Type= 0
Dn Type= 3
Dn Slope=0.01
Boundary for River Rch & Prof#=Conroe Lake 069,Reach-1         , 7
Up Type= 0
Dn Type= 3
Dn Slope=0.01
DSS Import GetInterval= 0
DSS Import GetPeak= 0
DSS Import FillOption= 0

--- Conroe Lake 069.g01 (geometry) ---

Geom Title=Existing Conditions
Program Version=4.10

River Reach=Conroe Lake 069 ,Reach-1
Reach XY= 30
      3784008.23     10207011.84      3784008.23     10206926.84
      3784088.23     10206766.84      3784078.23     10206536.84
      3784048.23     10206466.84      3783938.23     10206356.84
      3783938.23     10206276.84      3783978.23     10206206.84
      3784048.23     10205686.84      3784258.23     10205496.84
      3784288.23     10205366.84      3784448.23     10205206.84
      3784458.23     10205126.84      3784618.23     10204846.84
      3784678.23     10204846.84      3784778.23     10204736.84
      3784818.23     10204776.84      3784838.23     10204876.84
      3785048.23     10204676.84      3785038.23     10204616.84
      3785118.23     10204546.84      3785308.23     10204506.84
      3785388.23     10204366.84      3785488.23     10204326.84
      3785548.23     10204236.84      3785608.23     10204246.84
      3785698.23     10204166.84      3785798.23     10204176.84
      3785818.23     10204056.84      3785908.23     10203926.84

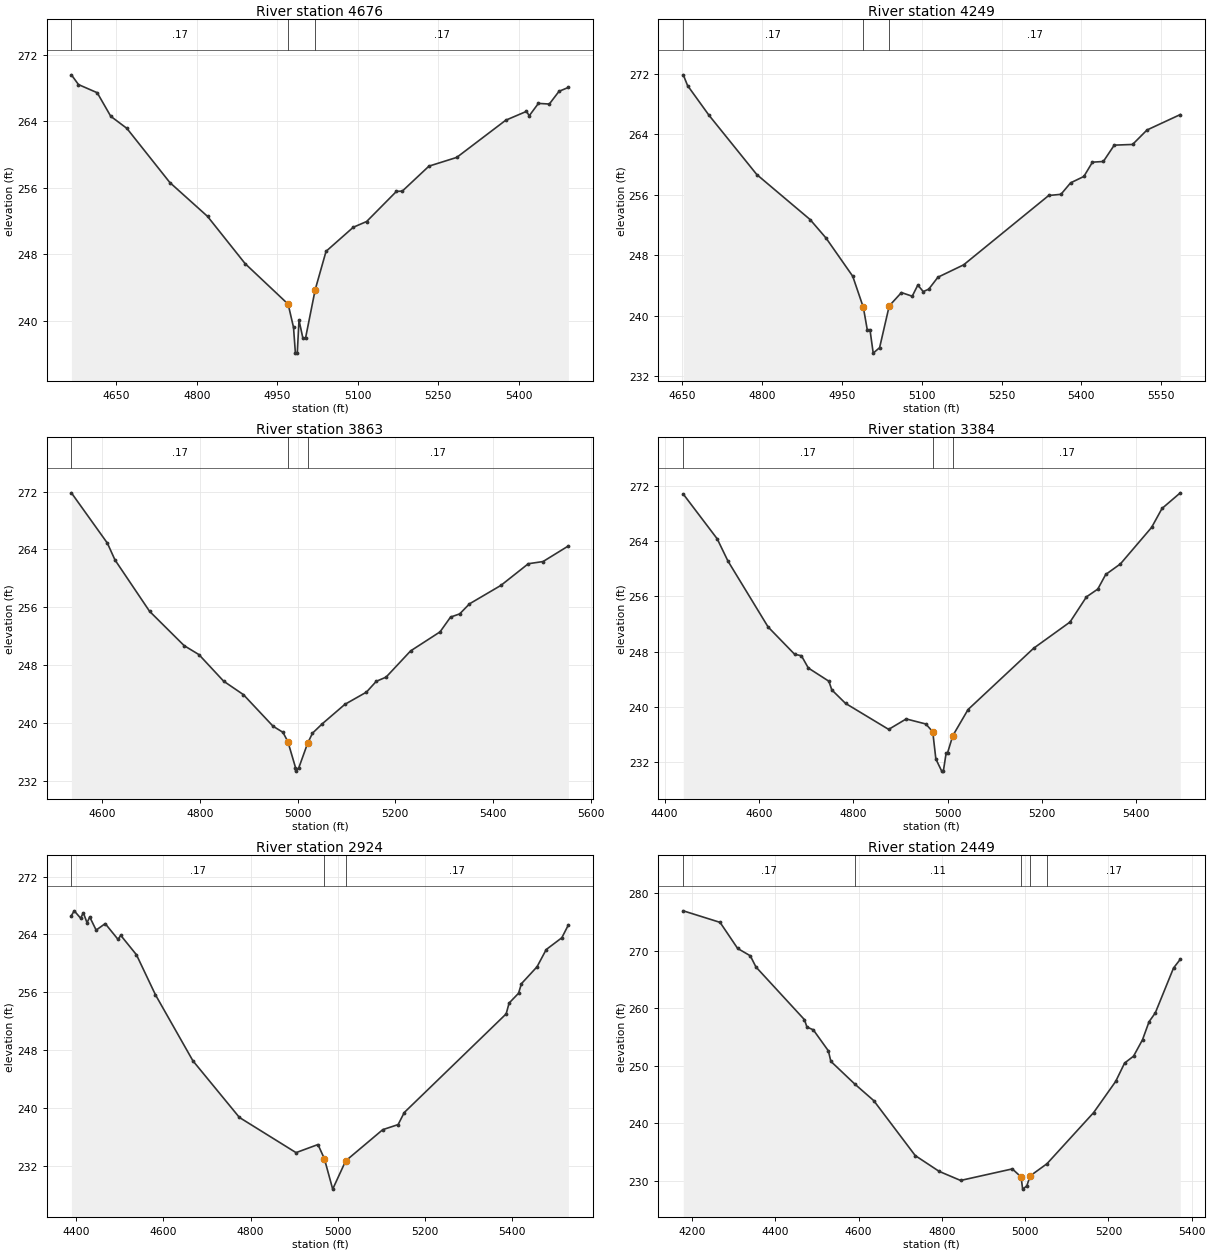
Type RM Length L Ch R = 1 ,4676    ,427,427,427
BEGIN DESCRIPTION:
Conroe Lake 069 9.0
END DESCRIPTION:
XS GIS Cut Line= 3
      3784441.02     10206903.48      3784008.23     10206926.84
      3783522.61     10207008.53
#Sta/Elev= 30
  4566.6  269.58  4579.8  268.41  4614.7  267.43  4639.9   264.6  4669.9  263.15
    4750  256.64  4820.1  252.58  4890.2   246.9  4970.3  242.03  4980.3  239.24
  4983.8  236.15  4987.3  236.15  4990.5  240.12  4997.7  237.96  5002.7  237.96
  5020.7  243.78  5040.9  248.38  5091.6  251.27  5116.5  251.96    5172  255.58
  5182.9  255.61  5232.5  258.61  5284.3  259.66  5375.6  264.13  5414.2  265.19
  5419.3  264.66  5436.4  266.15  5456.7  266.07  5474.8   267.6  5492.3  268.07
#Mann= 3 , 0 , 0
  4566.6     .17       0  4970.3     .06       0  5020.7     .17       0
Bank Sta=4970.3,5020.7
XS Rating Curve= 0 ,0
Exp/Cntr=0.3,0.1

Type RM Length L Ch R = 1 ,4249    ,386,386,386
BEGIN DESCRIPTION:
Conroe Lake 069 8.0
END DESCRIPTION:
XS GIS Cut Line= 3
      3784425.99     10206523.81      3784078.23     10206536.84
      3783506.79     10206666.22
#Sta/Elev= 30
    4652  271.84  4660.1  270.42  4700.2  266.51  4790.2  258.66  4890.3  252.72
  4920.3  250.27  4970.4  245.23  4990.4   241.1  4997.7  238.17  5002.8  238.17
  5008.9  235.07  5020.9  235.79    5039  241.31  5061.9  243.07  5082.2  242.59
  5092.7  244.06  5102.9   243.2  5113.2  243.52  5130.5   245.1  5178.7  246.73
  5338.7   255.9  5361.6  256.05  5379.8  257.57  5404.7  258.41  5420.8   260.3
  5441.3  260.39  5461.8  262.55  5496.2  262.64  5523.3  264.55  5585.9  266.59
#Mann= 3 , 0 , 0
    4652     .17       0  4990.4     .06       0    5039     .17       0
#XS Ineff= 2 , 0
       0                  5092.7       0  244.06
Permanent Ineff=
       F       F
Bank Sta=4990.4,5039
XS Rating Curve= 0 ,0
Exp/Cntr=0.3,0.1

Type RM Length L Ch R = 1 ,3863    ,479,479,479
BEGIN DESCRIPTION:
Conroe Lake 069 7.0
END DESCRIPTION:
XS GIS Cut Line= 3
      3784426.05     10206297.22      3783968.23     10206226.84
      3783416.11      10206279.2
#Sta/Elev= 30
  4536.8  271.82  4610.5  264.87    4626  262.56  4696.9  255.46  4767.7  250.72
    4798  249.48  4848.6  245.81  4889.1  243.95  4949.8  239.59    4970  238.75
  4980.1  237.46  4995.7  233.89  4995.9  233.39  5002.7  233.89  5020.5  237.23
  5030.5  238.63  5050.6  239.93  5096.8  242.61    5141   244.3  5161.1  245.79
  5181.2  246.37  5231.4  249.99  5291.7  252.62  5313.2  254.66  5331.9   255.1
    5352  256.49  5416.4  259.04  5472.5  262.03  5502.6  262.33  5554.6  264.49
#Mann= 3 , 0 , 0
  4536.8     .17       0  4980.1     .06       0  5020.5     .17       0
Bank Sta=4980.1,5020.5
XS Rating Curve= 0 ,0
Exp/Cntr=0.3,0.1

Type RM Length L Ch R = 1 ,3384    ,460,460,460
BEGIN DESCRIPTION:
Conroe Lake 069 6.0
END DESCRIPTION:
XS GIS Cut Line= 3
       3784463.5     10206117.11      3784018.23     10205776.84
      3783561.48     10205589.45
#Sta/Elev= 30
  4439.6  270.78  4511.6  264.31  4534.3  261.11  4619.5  251.58  4675.7  247.64
  4690.2  247.42  4704.8  245.65  4748.4  243.74  4754.6  242.49  4783.7  240.54
  4875.2  236.78  4912.4  238.29  4954.1  237.56  4968.7  236.43  4975.3   232.5
  4987.7  230.75  4991.2  230.75  4997.1  233.37    5000  233.37  5011.2  235.87
  5043.6  239.65  5182.6   248.5  5259.8  252.29  5294.7  255.93  5318.7  257.05
  5335.5  259.16  5366.7  260.69  5432.8  265.96  5454.9   268.7  5493.7  270.96
#Mann= 3 , 0 , 0
  4439.6     .17       0  4968.7     .06       0  5011.2     .17       0
Bank Sta=4968.7,5011.2
XS Rating Curve= 0 ,0
Exp/Cntr=0.3,0.1

Type RM Length L Ch R = 1 ,2924    ,475,475,475
BEGIN DESCRIPTION:
Conroe Lake 069 5.0
END DESCRIPTION:
XS GIS Cut Line= 3
      3784636.11     10205952.07      3784278.23     10205456.84
       3783887.3     10205099.71
#Sta/Elev= 30
    4389   266.6  4395.5  267.26  4410.2  266.24  4416.4  266.99  4424.9  265.61
  4431.1  266.41  4445.8  264.59  4466.6  265.49    4496  263.31  4502.2  263.87
  4538.3  261.18  4581.9  255.64  4667.8  246.51  4774.5  238.67  4904.5   233.8
  4954.8  234.92  4969.5  232.96  4988.6  228.75  5018.4  232.66  5103.5  236.98
  5138.7  237.68  5152.8  239.35  5386.6     253  5393.4   254.5    5415  255.85
  5421.7  257.18  5457.5  259.52  5478.5   261.9  5514.3  263.53  5529.5  265.32
#Mann= 3 , 0 , 0
    4389     .17       0  4969.5     .06       0  5018.4     .17       0
Bank Sta=4969.5,5018.4
XS Rating Curve= 0 ,0
Exp/Cntr=0.3,0.1

Type RM Length L Ch R = 1 ,2449    ,450,450,450
BEGIN DESCRIPTION:
Conroe Lake 069 4.0
END DESCRIPTION:
XS GIS Cut Line= 3
      3784952.25     10205768.01      3784508.23     10205076.84
      3784185.88     10204889.57
#Sta/Elev= 30
  4178.5  276.98  4266.9  274.97  4309.2  270.43  4339.6  269.15  4353.1  267.21
  4469.7  258.03  4475.7  256.74  4490.9  256.27  4527.2   252.6  4533.1  250.78
  4590.7  246.82  4636.2  243.94  4735.9  234.37  4793.4  231.62  4844.9  230.04
  4969.1  232.05  4990.2  230.65    4994  228.53  5003.9  229.08    5012  230.83
  5052.4  232.95  5164.5  241.85  5217.5  247.28    5239  250.48  5260.5  251.68
    5282  254.54  5297.7  257.67  5312.7  259.21  5356.5  267.02  5372.8  268.55
#Mann= 5 ,-1 , 0
  4178.5     .17       0  4590.7     .11       0  4990.2     .06       0
    5012     .11       0  5052.4     .17       0
Bank Sta=4990.2,5012
XS Rating Curve= 0 ,0
Exp/Cntr=0.3,0.1

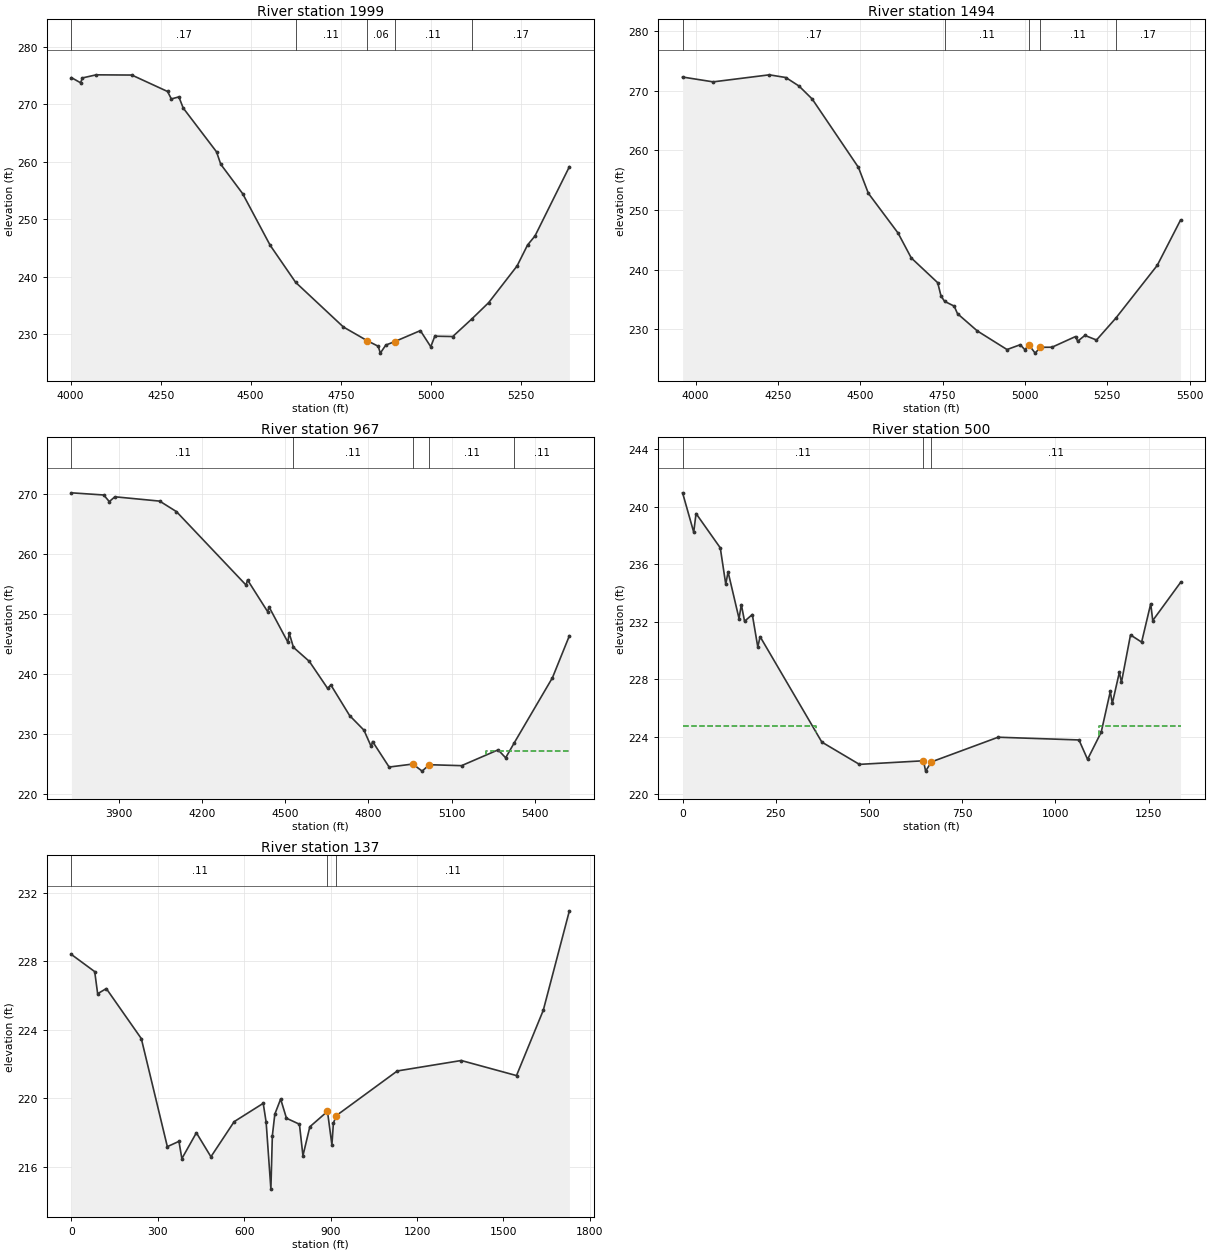
Type RM Length L Ch R = 1 ,1999    ,505,505,505
BEGIN DESCRIPTION:
Conroe Lake 069 3.0
END DESCRIPTION:
XS GIS Cut Line= 3
       3785041.2     10205726.72       3784753.6     10204771.48
      3784448.53     10204536.94
#Sta/Elev= 30
  4002.4  274.64  4027.7  273.75  4032.9  274.59  4071.1  275.13  4170.1  275.09
  4269.2  272.23  4279.8  270.93  4300.7  271.29  4312.6  269.36  4405.2  261.72
  4416.9  259.56  4477.7  254.44  4554.1  245.45  4624.9  238.99  4757.4  231.22
  4822.9  228.86  4854.2  227.86  4859.9  226.67  4875.1  228.07  4899.9  228.68
  4971.1  230.59    5000  227.78  5011.2  229.62    5061  229.56  5114.1  232.63
  5160.7  235.46  5239.6  241.85  5268.6  245.49  5289.4  247.08  5384.8  259.13
#Mann= 5 ,-1 , 0
  4002.4     .17       0  4624.9     .11       0  4822.9     .06       0
  4899.9     .11       0  5114.1     .17       0
Bank Sta=4822.9,4899.9
XS Rating Curve= 0 ,0
Exp/Cntr=0.3,0.1

Type RM Length L Ch R = 1 ,1494    ,527,527,527
BEGIN DESCRIPTION:
Conroe Lake 069 2.0
END DESCRIPTION:
XS GIS Cut Line= 3
      3785110.65     10205713.72      3785038.23     10204676.84
      3784678.82     10204370.43
#Sta/Elev= 30
  3960.6   272.3  4053.5  271.49  4223.9  272.67    4274  272.22  4314.1  270.79
  4354.2  268.61  4494.5  257.15  4524.6  252.81  4614.8  246.14  4654.9  241.97
  4735.1  237.82  4745.2  235.59  4756.1  234.69  4785.2  233.89  4795.3  232.62
  4855.4  229.73  4945.6  226.61  4985.7  227.42    5000  226.57  5011.8  227.41
  5030.9  226.01    5047  226.99  5082.1     227  5153.5  228.79    5160     228
    5182  228.98  5217.2  228.21  5275.5  231.85  5401.6  240.72  5472.3  248.31
#Mann= 5 ,-1 , 0
  3960.6     .17       0  4756.1     .11       0  5011.8     .06       0
    5047     .11       0  5275.5     .17       0
Bank Sta=5011.8,5047
XS Rating Curve= 0 ,0
Exp/Cntr=0.3,0.1

Type RM Length L Ch R = 1 ,967     ,467,467,467
BEGIN DESCRIPTION:
Conroe Lake 069 1.0
END DESCRIPTION:
XS GIS Cut Line= 3
      3785177.92     10205696.38      3785348.23     10204436.84
      3784899.47     10204165.15
#Sta/Elev= 30
    3729  270.16  3845.4   269.8  3865.5   268.7  3885.7   269.5  4047.2  268.78
  4107.7  267.03  4358.9  254.79  4363.9  255.66  4436.6  250.37  4441.6  251.16
  4509.2  245.31  4514.3  246.79  4529.6  244.43  4586.9  242.09  4652.6  237.61
  4664.6  238.16  4732.2  233.07  4783.8  230.64  4809.8  227.93  4814.9  228.75
  4874.6   224.5  4960.1     225  4993.6  223.82  5019.4  224.89  5135.8  224.73
  5267.6  227.36  5294.8  226.04  5326.4  228.58  5463.5  239.37  5524.6  246.36
#Mann= 5 ,-1 , 0
    3729     .11       0  4529.6     .11       0  4960.1     .06       0
  5019.4     .11       0  5326.4     .11       0
#XS Ineff= 2 , 0
       0                  5222.6       0  227.17
Permanent Ineff=
       F       F
Bank Sta=4960.1,5019.4
XS Rating Curve= 0 ,0
Exp/Cntr=0.3,0.1

Type RM Length L Ch R = 1 ,500     ,363,363,363
XS GIS Cut Line= 3
      3786031.84     10204738.32      3785648.52     10204206.55
      3785015.88     10203957.89
#Sta/Elev= 30
       0  240.96    29.9  238.22    36.1  239.52   101.1  237.13   115.8   234.6
     122  235.46   151.4  232.21   157.6  233.18   166.2  232.02     187  232.49
   201.7  230.23   207.9  230.95   373.5  223.61   474.2  222.06   645.9  222.31
   651.8  221.59     667  222.23   846.2  223.95    1063  223.76    1086  222.41
  1122.6   224.3    1147  227.14  1152.4   226.3  1171.4  228.48  1176.8  227.76
  1201.2  231.07    1231  230.57  1255.4  233.24  1260.8  232.07  1335.3  234.72
#Mann= 3 , 0 , 0
       0     .11       0   645.9     .06       0     667     .11       0
#XS Ineff= 2 , 0
       0   358.8   224.7  1117.2       0  224.71
Permanent Ineff=
       F       F
Bank Sta=645.9,667
XS Rating Curve= 0 ,0
Exp/Cntr=0.3,0.1

Type RM Length L Ch R = 1 ,137     ,0,0,0
XS GIS Cut Line= 4
      3786737.93     10203944.75      3785953.21     10204048.92
      3785848.23     10204026.84      3785025.99     10203913.23
#Sta/Elev= 30
       0  228.39    80.8  227.39      91   226.1   121.1   226.4   242.6  223.48
     333  217.17   373.3  217.48   383.4  216.47   433.8  217.98   484.3  216.58
     565  218.63   665.9   219.7     676   218.6   692.5  214.69   697.6  217.81
   706.2  219.07   726.4  219.95   746.6  218.83   791.6  218.48   803.8  216.64
   827.7  218.33     889  219.23   904.4  217.27   909.5  218.54   919.4  218.98
  1131.4  221.59  1353.5   222.2  1545.3  221.32  1638.2  225.13  1728.9  230.94
#Mann= 3 , 0 , 0
       0     .11       0     889     .06       0   919.4     .11       0
Bank Sta=889,919.4
XS Rating Curve= 0 ,0
Exp/Cntr=0.3,0.1

Chan Stop Cuts=-1
Use User Specified Reach Order=0
Composite Channel Slope=5