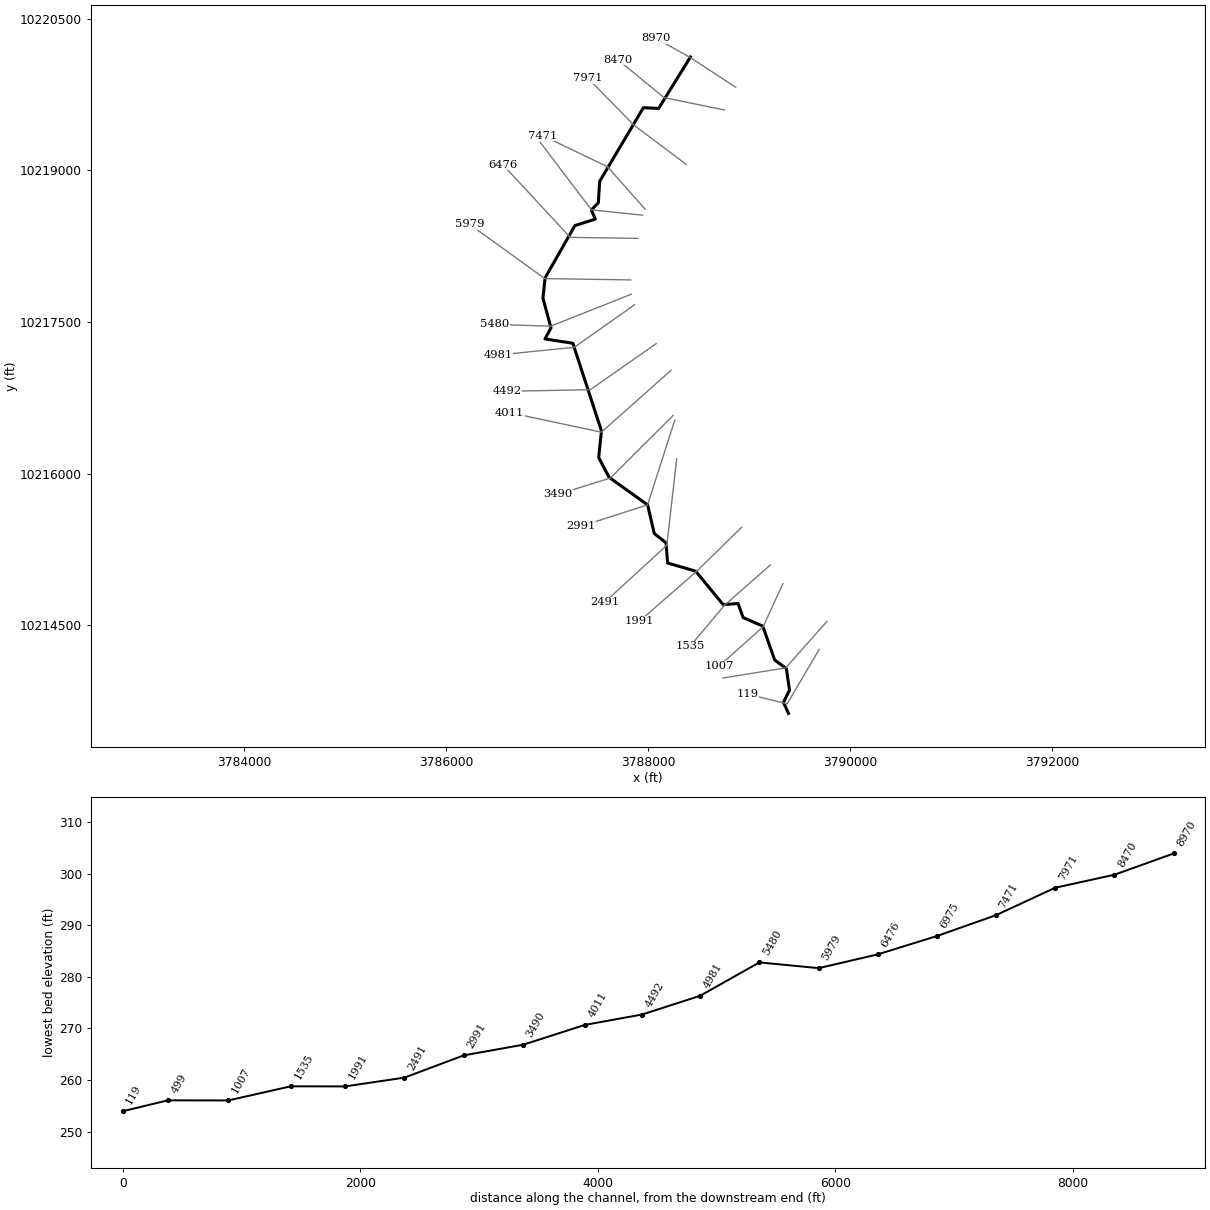
--- Conroe Lake 071.prj (project) ---

Proj Title=Conroe Lake 071 Base Level Engineering
Current Plan=p01
Default Exp/Contr=0.3,0.1
English Units
Geom File=g01
Flow File=f01
Flow File=f02
Plan File=p01
Y Axis Title=Elevation
X Axis Title(PF)=Main Channel Distance
X Axis Title(XS)=Station
BEGIN DESCRIPTION:
Conroe Lake 071
END DESCRIPTION:
DSS Export Rating Curves= 0
DSS Export Rating Curve Sorted= 0
DSS Export Volume Flow Curves= 0
DXF OffsetX= 0
DXF OffsetY= 0
DXF ScaleX= 1
DXF ScaleY= 10

--- Conroe Lake 071.p01 (plan) ---

Plan Title=Multiple Run
Short Identifier=Multiple
Geom File=g01
Flow File=f01
Subcritical Flow
K Sum by GR= 0
Std Step Tol= 0.01
Critical Tol= 0.01
Num of Std Step Trials= 20
Max Error Tol= 0.3
Flow Tol Ratio= 0.001
Split Flow NTrial= 30
Split Flow Tol= 0.02
Split Flow Ratio= 0.02
Log Output Level= 0
Friction Slope Method= 1
Unsteady Friction Slope Method= 2
Unsteady Bridges Friction Slope Method= 1
Parabolic Critical Depth
Global Vel Dist=  1 , 1 , 1
Global Log Level= 0
CheckData=True
Encroach Param= -1, 0, 0, 0
BEGIN DESCRIPTION:
Multiple Run
END DESCRIPTION:

--- Conroe Lake 071.f01 (steady flow) ---

Flow Title=Multiple
Program Version=4.10
Number of Profiles= 7
Profile Names=10-year,25-year,50-year,1pct_min,100-year,1pct_plu,500-year
River Rch & RM=Conroe Lake 071,Reach-1         ,8970
     249     318     413     178     537    1622     934
River Rch & RM=Conroe Lake 071,Reach-1         ,7471
     671     909    1229     547    1651    4986    3081
Boundary for River Rch & Prof#=Conroe Lake 071,Reach-1         , 1
Up Type= 0
Dn Type= 3
Dn Slope=0.005
Boundary for River Rch & Prof#=Conroe Lake 071,Reach-1         , 2
Up Type= 0
Dn Type= 3
Dn Slope=0.005
Boundary for River Rch & Prof#=Conroe Lake 071,Reach-1         , 3
Up Type= 0
Dn Type= 3
Dn Slope=0.005
Boundary for River Rch & Prof#=Conroe Lake 071,Reach-1         , 4
Up Type= 0
Dn Type= 3
Dn Slope=0.005
Boundary for River Rch & Prof#=Conroe Lake 071,Reach-1         , 5
Up Type= 0
Dn Type= 3
Dn Slope=0.005
Boundary for River Rch & Prof#=Conroe Lake 071,Reach-1         , 6
Up Type= 0
Dn Type= 3
Dn Slope=0.005
Boundary for River Rch & Prof#=Conroe Lake 071,Reach-1         , 7
Up Type= 0
Dn Type= 3
Dn Slope=0.005
DSS Import GetInterval= 0
DSS Import GetPeak= 0
DSS Import FillOption= 0

--- Conroe Lake 071.f02 (steady flow) ---

Flow Title=Orig_BLE_Flow
Program Version=4.10
Number of Profiles= 7
Profile Names=10-year,25-year,50-year,1pct_min,100-year,1pct_plu,500-year
River Rch & RM=Conroe Lake 071,Reach-1         ,8970
     249     312     359     137     413    1248     543
River Rch & RM=Conroe Lake 071,Reach-1         ,7471
     671     891    1069     421    1270    3836    1791
Boundary for River Rch & Prof#=Conroe Lake 071,Reach-1         , 1
Up Type= 0
Dn Type= 3
Dn Slope=0.005
Boundary for River Rch & Prof#=Conroe Lake 071,Reach-1         , 2
Up Type= 0
Dn Type= 3
Dn Slope=0.005
Boundary for River Rch & Prof#=Conroe Lake 071,Reach-1         , 3
Up Type= 0
Dn Type= 3
Dn Slope=0.005
Boundary for River Rch & Prof#=Conroe Lake 071,Reach-1         , 4
Up Type= 0
Dn Type= 3
Dn Slope=0.005
Boundary for River Rch & Prof#=Conroe Lake 071,Reach-1         , 5
Up Type= 0
Dn Type= 3
Dn Slope=0.005
Boundary for River Rch & Prof#=Conroe Lake 071,Reach-1         , 6
Up Type= 0
Dn Type= 3
Dn Slope=0.005
Boundary for River Rch & Prof#=Conroe Lake 071,Reach-1         , 7
Up Type= 0
Dn Type= 3
Dn Slope=0.005
DSS Import GetInterval= 0
DSS Import GetPeak= 0
DSS Import FillOption= 0

--- Conroe Lake 071.g01 (geometry) ---

Geom Title=Existing Conditions
Program Version=4.10

River Reach=Conroe Lake 071 ,Reach-1
Reach XY= 30
      3788418.23     10220121.84      3788103.44     10219613.06
      3787952.36     10219620.04      3787519.62     10218890.84
      3787506.86     10218679.25      3787438.25     10218609.55
      3787476.46     10218517.61      3787274.72     10218453.52
      3786979.96     10217936.08      3786958.67     10217734.94
      3787038.42     10217441.81      3786978.66     10217331.84
      3787254.63     10217289.35      3787537.57     10216422.47
      3787510.15     10216157.64      3787614.04     10215962.13
      3787994.12       10215690.      3788060.29     10215406.73
      3788176.71     10215314.29      3788191.77     10215114.75
      3788469.81     10215033.85      3788741.99     10214703.02
      3788889.06      10214714.2      3788939.48     10214575.23
      3789134.07       10214490.      3789251.45     10214155.37
      3789367.26     10214070.34      3789398.25     10213856.86
      3789338.53     10213735.35      3789388.23     10213626.84

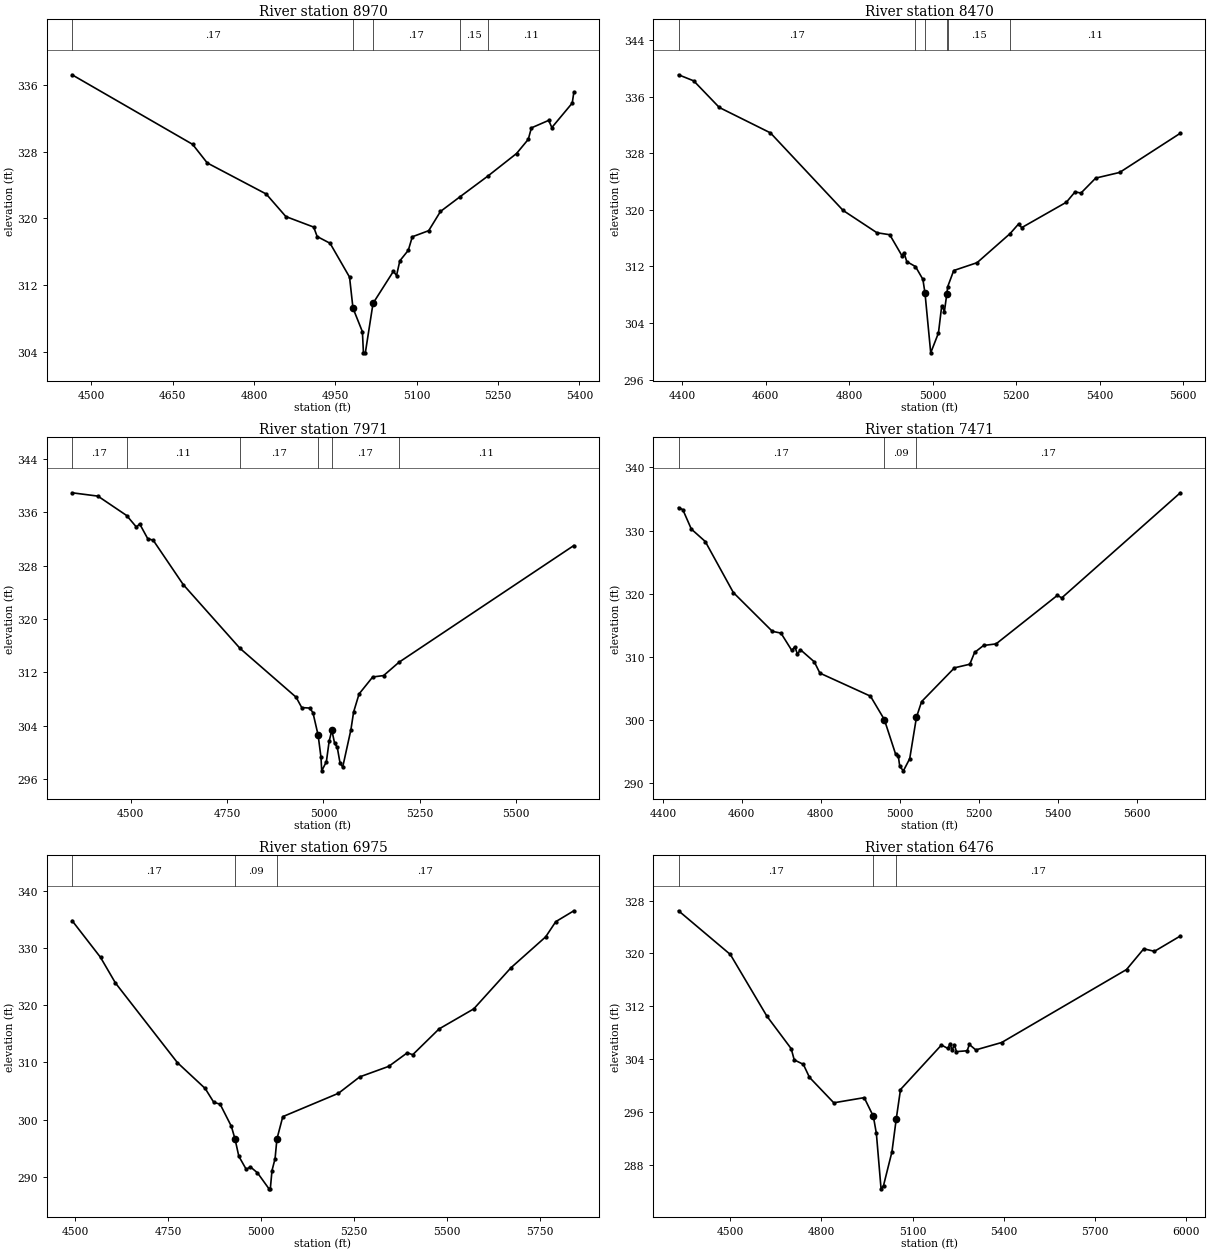
Type RM Length L Ch R = 1 ,8970    ,500,500,500
BEGIN DESCRIPTION:
Conroe Lake 071 18.0
END DESCRIPTION:
XS GIS Cut Line= 3
      3788866.16     10219822.82      3788418.03     10220115.42
      3788078.24     10220306.44
#Sta/Elev= 30
  4464.8  337.21    4687  328.88    4714  326.65  4822.7  322.93  4858.9  320.23
  4910.2  318.97  4916.6  317.84  4940.4  317.03  4976.3  312.98  4982.6  309.27
    5000  306.44  5001.9  303.91  5005.4  303.91  5019.6  309.84  5057.2  313.68
  5062.9  313.16    5069  314.93  5084.6  316.19    5092  317.81  5122.2  318.54
  5143.9  320.84  5179.5  322.58  5231.9  325.11  5284.1  327.78  5305.8  329.48
  5311.5  330.85  5343.4  331.75  5349.2  330.89  5386.8  333.82  5389.8  335.13
#Mann= 5 ,-1 , 0
  4464.8     .17       0  4982.6     .09       0  5019.6     .17       0
  5179.5     .15       0  5231.9     .11       0
Bank Sta=4982.6,5019.6
XS Rating Curve= 0 ,0
Exp/Cntr=0.3,0.1

Type RM Length L Ch R = 1 ,8470    ,499,499,499
BEGIN DESCRIPTION:
Conroe Lake 071 17.0
END DESCRIPTION:
XS GIS Cut Line= 3
      3788753.53     10219597.46      3788157.03     10219720.24
      3787697.84     10220096.09
#Sta/Elev= 30
    4391  339.07  4427.4  338.21  4488.7  334.45  4611.2  330.86  4785.4   319.9
  4866.4  316.75  4897.1  316.47  4926.2  313.52  4931.3  313.92  4937.9  312.67
  4958.8  311.97  4976.5  310.17  4981.6  308.21  4995.3  299.78  5013.8  302.58
  5021.7  306.44  5028.1  305.62 5033.86  308.11    5036  309.13  5050.4  311.41
  5106.4  312.52  5185.5  316.63  5205.7  317.98  5213.3  317.47  5320.3  321.06
  5341.1  322.52  5355.4  322.36  5390.6  324.47    5448  325.27  5593.4  330.81
#Mann= 6 ,-1 , 0
    4391     .17       0  4958.8     .15       0  4981.6     .09       0
 5033.86     .12       0    5036     .15       0  5185.5     .11       0
#XS Ineff= 2 , 0
       0                  5021.7       0  306.44
Permanent Ineff=
       F       F
Bank Sta=4981.6,5033.86
XS Rating Curve= 0 ,0
Exp/Cntr=0.3,0.1

Type RM Length L Ch R = 1 ,7971    ,500,500,500
BEGIN DESCRIPTION:
Conroe Lake 071 16.0
END DESCRIPTION:
XS GIS Cut Line= 3
      3788378.78     10219057.53       3787856.9     10219449.19
      3787402.18     10219913.94
#Sta/Elev= 30
  4347.5  338.91  4414.6  338.41  4489.3   335.5  4514.6  333.77  4522.9  334.26
  4543.7  332.06  4558.3  331.79  4636.2  325.15  4783.4  315.61  4929.1  308.29
  4943.7  306.74  4964.5  306.66  4972.8  305.98  4986.3   302.6  4993.7  299.29
  4995.6  297.26  5007.7  298.62  5014.9  301.69  5021.9  303.34    5029  301.41
    5036  300.77  5043.1  298.45  5050.1  297.83  5071.4  303.42  5078.4  306.07
  5092.6  308.78    5128  311.32  5156.3  311.53  5196.1  313.52  5650.2  331.01
#Mann= 6 ,-1 , 0
  4347.5     .17       0  4489.3     .11       0  4783.4     .17       0
  4986.3     .09       0  5021.9     .17       0  5196.1     .11       0
Bank Sta=4986.3,5021.9
XS Rating Curve= 0 ,0
Exp/Cntr=0.3,0.1

Type RM Length L Ch R = 1 ,7471    ,496,496,496
BEGIN DESCRIPTION:
Conroe Lake 071 15.0
END DESCRIPTION:
XS GIS Cut Line= 3
      3787969.04     10218616.84      3787597.57      10219036.3
      3786957.09     10219342.94
#Sta/Elev= 30
  4439.7  333.63  4450.5  333.31  4472.1  330.23  4507.4  328.26  4578.5  320.17
  4677.2  314.03    4699  313.75  4726.5     311  4734.1  311.59  4740.8  310.41
  4748.3  311.12  4783.4   309.2  4797.6  307.41  4925.6  303.76  4960.7  300.06
  4989.2  294.59  4995.9  294.36  4999.8  292.62    5009  291.93    5025  293.86
  5042.1  300.43  5055.1   302.9  5138.3  308.25  5177.1  308.82  5189.2  310.68
  5211.9  311.79  5243.6  312.04  5398.8  319.73  5409.9  319.33  5710.1  335.98
#Mann= 3 , 0 , 0
  4439.7     .17       0  4960.7     .09       0  5042.1     .17       0
Bank Sta=4960.7,5042.1
XS Rating Curve= 0 ,0
Exp/Cntr=0.3,0.1

Type RM Length L Ch R = 1 ,6975    ,499,499,499
BEGIN DESCRIPTION:
Conroe Lake 071 14.0
END DESCRIPTION:
XS GIS Cut Line= 3
      3787943.96     10218556.35      3787438.25     10218609.55
      3786929.99     10219280.34
#Sta/Elev= 30
  4491.5  334.74    4568  328.33  4608.2  323.85  4774.9  309.94  4849.6  305.43
  4872.9     303  4889.8  302.69    4920  298.83    4930  296.59  4940.1   293.6
  4960.2  291.29    4971  291.75  4990.3   290.7  5021.4   287.9  5024.9   287.9
  5029.4  291.09  5037.7  293.18 5042.71  296.62  5058.5  300.51  5208.3  304.59
  5265.4  307.45  5343.5  309.29  5393.5  311.66    5408  311.32  5478.8  315.82
  5572.3  319.33  5672.2   326.5  5765.8  331.91  5792.9  334.56  5841.6  336.46
#Mann= 3 , 0 , 0
  4491.5     .17       0    4930     .09       0 5042.71     .17       0
Bank Sta=4930,5042.71
XS Rating Curve= 0 ,0
Exp/Cntr=0.3,0.1

Type RM Length L Ch R = 1 ,6476    ,497,497,497
BEGIN DESCRIPTION:
Conroe Lake 071 13.0
END DESCRIPTION:
XS GIS Cut Line= 3
      3787898.11     10218326.84      3787228.59     10218337.09
      3786562.25     10219055.42
#Sta/Elev= 30
  4330.4  326.45  4500.7  319.83  4620.7   310.5  4700.7  305.57  4710.7  303.87
  4740.7  303.19  4760.7  301.23  4840.7  297.37  4940.7  298.15  4970.7  295.33
  4980.7  292.73  4996.1  284.34  5004.2  284.84  5031.9  289.95    5046  294.92
    5060  299.38  5194.6  306.12  5215.6   305.6  5222.9  306.33  5229.7  305.33
  5237.1  306.18  5243.9  305.12  5279.1  305.25  5286.4   306.2  5307.4  305.38
  5392.5   306.5  5802.9  317.55  5859.6  320.69  5894.8  320.31  5979.8  322.63
#Mann= 3 , 0 , 0
  4330.4     .17       0  4970.7     .09       0    5046     .17       0
Bank Sta=4970.7,5046
XS Rating Curve= 0 ,0
Exp/Cntr=0.3,0.1

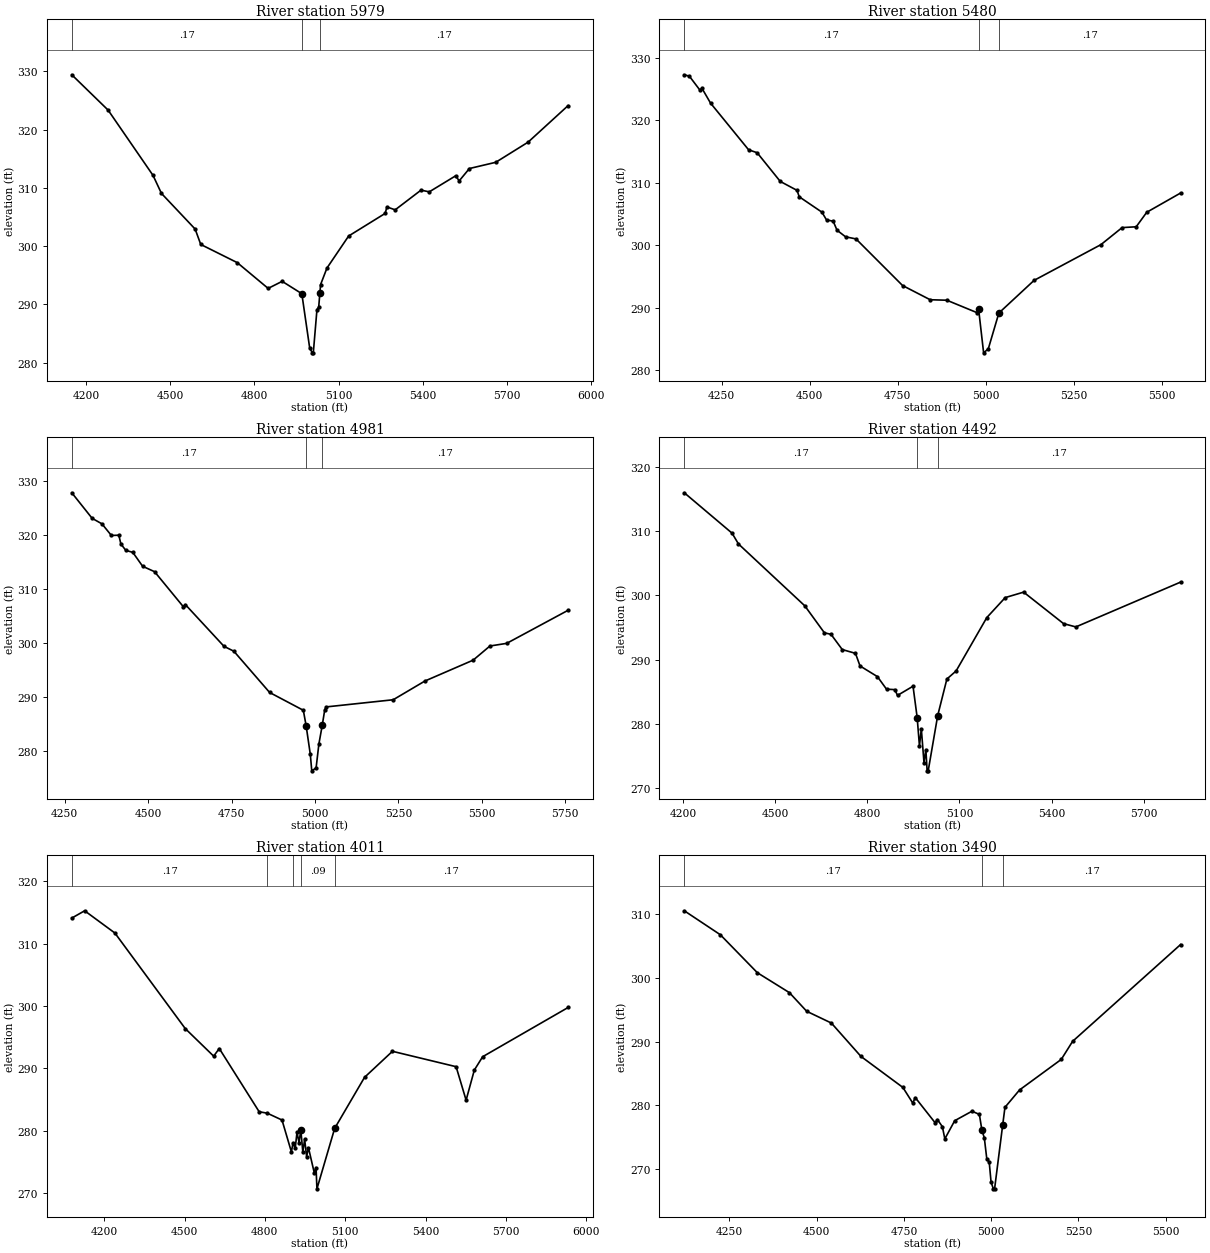
Type RM Length L Ch R = 1 ,5979    ,499,499,499
BEGIN DESCRIPTION:
Conroe Lake 071 12.0
END DESCRIPTION:
XS GIS Cut Line= 3
      3787827.17     10217915.82      3786976.98     10217929.35
       3786232.6     10218465.91
#Sta/Elev= 30
  4149.7   329.4    4279  323.34  4439.1  312.13  4469.1  309.04  4589.1  302.92
  4609.1  300.28  4739.1  297.16  4849.1  292.74  4899.1  293.95  4969.1  291.83
  4997.1  282.51  5006.5  281.68    5010  281.68    5023  289.11  5029.2  289.52
 5033.27  291.87  5035.9  293.39  5058.6  296.23  5135.9  301.73    5266  305.61
  5272.2  306.72  5301.6  306.22  5393.6   309.6  5423.1  309.31  5516.7  312.05
  5529.8   311.2    5566  313.31  5659.9  314.38  5775.2  317.84  5917.6  324.11
#Mann= 3 , 0 , 0
  4149.7     .17       0  4969.1     .09       0 5033.27     .17       0
#XS Ineff= 2 , 0
       0  4899.1  293.95               0
Permanent Ineff=
       F       F
Bank Sta=4969.1,5033.27
XS Rating Curve= 0 ,0
Exp/Cntr=0.3,0.1

Type RM Length L Ch R = 1 ,5480    ,499,499,499
BEGIN DESCRIPTION:
Conroe Lake 071 11.0
END DESCRIPTION:
XS GIS Cut Line= 3
      3787831.32     10217773.94      3787035.22     10217458.27
       3786481.7     10217475.67
#Sta/Elev= 30
  4143.6  327.24  4158.1  327.01  4188.5  324.75  4193.9  325.07  4218.2  322.71
  4326.3  315.25  4350.6  314.78  4416.3  310.19    4464  308.76  4470.1  307.74
  4534.6  305.28  4547.7  304.04  4566.7  303.83  4577.6  302.39  4601.8  301.34
  4631.5     301  4763.8  293.55  4842.2  291.28  4889.6   291.2  4974.6  289.23
  4979.9  289.76  4994.1  282.79  5007.4  283.43  5037.4  289.15  5137.4  294.37
  5327.5  300.09  5387.6  302.81  5427.6  302.94  5457.6  305.26  5553.8  308.34
#Mann= 3 ,-1 , 0
  4143.6     .17       0  4979.9     .09       0  5037.4     .17       0
#XS Ineff= 2 , 0
       0  4889.6   291.2               0
Permanent Ineff=
       F       F
Bank Sta=4979.9,5037.4
XS Rating Curve= 0 ,0
Exp/Cntr=0.3,0.1

Type RM Length L Ch R = 1 ,4981    ,489,489,489
BEGIN DESCRIPTION:
Conroe Lake 071 10.0
END DESCRIPTION:
XS GIS Cut Line= 3
      3787864.74     10217669.65      3787269.27     10217249.27
      3786514.81     10217173.06
#Sta/Elev= 30
  4271.1  327.84    4332  323.11  4361.5  322.08  4389.7  319.93    4412  319.98
  4418.2  318.36  4432.9  317.17  4453.9   316.8  4483.4  314.22  4519.1  313.22
  4605.3  306.73  4611.5  307.12  4727.2  299.39  4756.8  298.48  4863.9  290.84
  4964.9  287.54 4973.26  284.69  4985.8  279.38  4990.2  276.32  5003.2  276.87
  5011.5  281.28  5021.5  284.74  5029.2  287.67  5034.2  288.17  5234.2  289.49
  5329.2  292.96  5473.8  296.83  5524.1  299.45  5574.3  299.94  5758.3  306.07
#Mann= 3 , 0 , 0
  4271.1     .17       0 4973.26     .09       0  5021.5     .17       0
Bank Sta=4973.26,5021.5
XS Rating Curve= 0 ,0
Exp/Cntr=0.3,0.1

Type RM Length L Ch R = 1 ,4492    ,481,481,481
BEGIN DESCRIPTION:
Conroe Lake 071 9.0
END DESCRIPTION:
XS GIS Cut Line= 3
      3788079.65     10217285.75      3787426.83     10216829.41
      3786606.57      10216814.2
#Sta/Elev= 30
  4203.5  315.93  4359.1  309.65    4380  307.97  4596.1  298.35    4660  294.15
  4681.5  293.92  4718.1  291.55  4761.2  290.96    4776     289  4832.7  287.34
  4862.3  285.39  4889.3  285.32  4898.1  284.42  4948.7  285.85  4962.2  280.97
  4969.6  276.57  4975.7  279.23  4984.4  273.98  4990.5  275.99  4994.6  272.69
  4998.1  272.69    5029  281.27    5059  286.97    5089  288.22    5189  296.52
    5249  299.63    5309  300.48  5439.1  295.58  5479.1  295.07  5820.4  302.04
#Mann= 3 , 0 , 0
  4203.5     .17       0  4962.2     .09       0    5029     .17       0
Bank Sta=4962.2,5029
XS Rating Curve= 0 ,0
Exp/Cntr=0.3,0.1

Type RM Length L Ch R = 1 ,4011    ,521,521,521
BEGIN DESCRIPTION:
Conroe Lake 071 8.0
END DESCRIPTION:
XS GIS Cut Line= 3
      3788225.65     10217020.74       3787537.1     10216409.37
      3786625.43     10216603.46
#Sta/Elev= 30
  4079.2  314.13  4127.2   315.3  4240.1  311.73  4502.7   296.4  4608.9  291.97
  4629.8   293.2  4778.7  283.05    4809  282.82    4864  281.72  4899.1  276.61
  4904.9  278.02  4913.3  277.19    4920  279.76  4927.6   278.1  4934.2  280.13
  4941.8  276.57  4948.5  278.63    4956  275.83  4962.7  277.29  4984.4  273.26
  4991.1   274.1  4994.4  270.68  5060.6  280.38  5172.1  288.57  5276.3  292.75
    5514  290.28  5551.3  284.91    5582  289.74  5613.1  291.88  5932.1  299.78
#Mann= 5 ,-1 , 0
  4079.2     .17       0    4809     .15       0  4904.9     .17       0
  4934.2     .09       0  5060.6     .17       0
#XS Ineff= 2 , 0
       0  4934.2  280.13               0
Permanent Ineff=
       F       F
Bank Sta=4934.2,5060.6
XS Rating Curve= 0 ,0
Exp/Cntr=0.3,0.1

Type RM Length L Ch R = 1 ,3490    ,499,499,499
BEGIN DESCRIPTION:
Conroe Lake 071 7.0
END DESCRIPTION:
XS GIS Cut Line= 3
      3788248.62     10216576.35      3787625.56     10215955.61
       3787107.3     10215793.93
#Sta/Elev= 30
  4120.5  310.57  4223.8   306.8  4329.8  300.83  4421.8  297.69  4471.3  294.76
    4542  292.91  4626.8  287.66    4747  282.78  4775.3  280.32  4782.4  281.19
    4839  277.25    4846  277.73  4860.2   276.6  4867.2  274.69  4895.5  277.55
    4945  279.04  4966.2  278.54  4973.3   276.1  4980.4  274.83  4987.4  271.57
  4994.5  270.98  4999.7  267.89  5006.3  266.83  5009.8  266.83  5033.1  276.92
  5039.5  279.65  5081.4  282.39  5200.9  287.19  5233.4  290.03  5542.9  305.26
#Mann= 3 , 0 , 0
  4120.5     .17       0  4973.3     .09       0  5033.1     .17       0
#XS Ineff= 2 , 0
       0    4945  279.04               0
Permanent Ineff=
       F       F
Bank Sta=4973.3,5033.1
XS Rating Curve= 0 ,0
Exp/Cntr=0.3,0.1

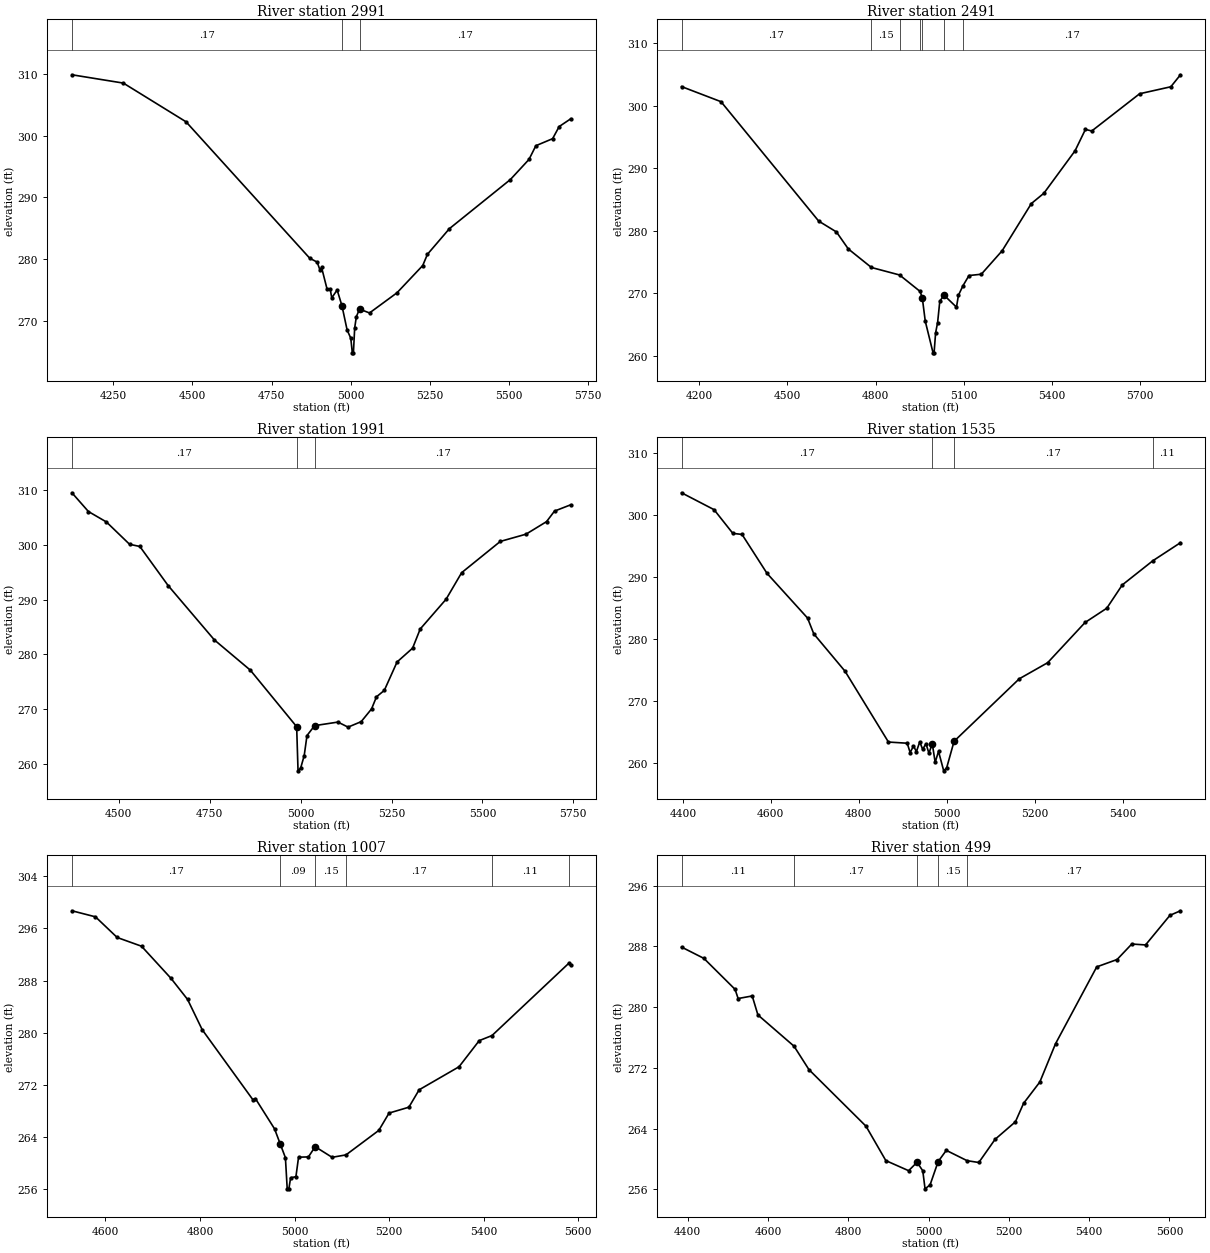
Type RM Length L Ch R = 1 ,2991    ,500,500,500
BEGIN DESCRIPTION:
Conroe Lake 071 6.0
END DESCRIPTION:
XS GIS Cut Line= 3
      3788263.22     10216528.37      3787994.12       10215690.
      3787332.73     10215476.82
#Sta/Elev= 30
  4119.5   309.9  4281.9  308.55  4479.8  302.27  4870.4  280.13  4893.9   279.5
  4902.5  278.24  4907.8  278.63  4925.4  275.06  4934.7  275.19  4939.9   273.7
  4956.9  274.98    4972  272.44  4988.4  268.49    5000  267.15  5004.8  264.78
  5008.3  264.78  5012.3  268.83  5017.6  270.65  5027.6  271.88  5059.1  271.25
  5145.8  274.52  5227.2  278.95    5242  280.77  5311.4  284.93  5503.7  292.89
  5562.6  296.16  5584.4  298.39  5637.2  299.53    5658   301.5  5694.9  302.77
#Mann= 3 , 0 , 0
  4119.5     .17       0    4972     .09       0  5027.6     .17       0
#XS Ineff= 2 , 0
       0  4956.9  274.98               0
Permanent Ineff=
       F       F
Bank Sta=4972,5027.6
XS Rating Curve= 0 ,0
Exp/Cntr=0.3,0.1

Type RM Length L Ch R = 1 ,2491    ,500,500,500
BEGIN DESCRIPTION:
Conroe Lake 071 5.0
END DESCRIPTION:
XS GIS Cut Line= 3
      3788281.99     10216144.48      3788184.44     10215289.93
      3787567.68     10214724.83
#Sta/Elev= 30
  4139.9   303.1  4274.2  300.68  4606.3  281.56  4666.7  279.82    4707   277.1
  4785.6  274.13  4881.3  272.93    4951   270.3  4958.6  269.28  4968.7  265.53
  4995.2  260.46  4998.7  260.46  5003.9  263.67  5010.7  265.31  5018.1  268.72
  5032.3   269.7  5074.8  267.78  5081.6  269.69  5097.1  271.22  5117.4  272.84
  5159.3  273.05  5230.2  276.81  5329.5  284.37  5372.1  286.02  5478.1  292.82
  5513.3  296.24  5534.9  295.99  5697.6  301.95  5803.7  303.07  5836.5  304.99
#Mann= 7 ,-1 , 0
  4139.9     .17       0  4785.6     .15       0  4881.3     .17       0
    4951     .15       0  4958.6     .09       0  5032.3     .15       0
  5097.1     .17       0
Bank Sta=4958.6,5032.3
XS Rating Curve= 0 ,0
Exp/Cntr=0.3,0.1

Type RM Length L Ch R = 1 ,1991    ,456,456,456
BEGIN DESCRIPTION:
Conroe Lake 071 4.0
END DESCRIPTION:
XS GIS Cut Line= 3
      3788924.59     10215468.45      3788475.13     10215028.28
      3787914.81     10214540.03
#Sta/Elev= 30
  4370.9  309.46  4416.3  306.04  4465.7  304.14  4529.4  300.07  4557.7  299.67
  4635.4  292.55  4762.7  282.63  4861.7  277.11    4989  266.81  4992.8  258.76
    5000  259.26  5009.8  261.55  5017.4  265.19  5038.3     267  5102.5  267.65
  5130.4  266.73  5166.5  267.73    5195  270.05  5208.6  272.26  5230.1  273.43
  5265.2  278.61  5307.9  281.13  5328.8  284.62    5400  290.05  5442.8  294.89
  5549.1  300.59  5619.8  301.91  5676.3   304.2  5698.2  306.12  5743.2  307.28
#Mann= 3 , 0 , 0
  4370.9     .17       0    4989     .09       0  5038.3     .17       0
Bank Sta=4989,5038.3
XS Rating Curve= 0 ,0
Exp/Cntr=0.3,0.1

Type RM Length L Ch R = 1 ,1535    ,528,528,528
BEGIN DESCRIPTION:
Conroe Lake 071 3.0
END DESCRIPTION:
XS GIS Cut Line= 3
      3789208.37       10215095.      3788755.31     10214696.92
      3788413.47     10214289.68
#Sta/Elev= 30
  4396.9  303.58  4470.9  300.86  4513.6  297.04  4534.5  296.87  4591.4  290.59
  4683.5   283.4  4697.7  280.85  4768.8  274.83  4867.5  263.42  4910.2  263.23
  4916.9  261.72  4924.5  262.79  4931.1  261.87  4938.7  263.44  4945.4  262.25
  4952.9  263.15  4959.6  261.61  4967.2  263.17  4973.8  260.14  4981.4  261.92
  4993.2  258.78    5000  259.28  5016.8  263.54  5165.1  273.61  5229.6   276.2
  5314.7  282.68  5364.1  284.98  5399.3  288.73  5468.7  292.62  5531.7  295.54
#Mann= 4 ,-1 , 0
  4396.9     .17       0  4967.2     .09       0  5016.8     .17       0
  5468.7     .11       0
Bank Sta=4967.2,5016.8
XS Rating Curve= 0 ,0
Exp/Cntr=0.3,0.1

Type RM Length L Ch R = 1 ,1007    ,508,508,508
BEGIN DESCRIPTION:
Conroe Lake 071 2.0
END DESCRIPTION:
XS GIS Cut Line= 3
      3789333.55     10214911.42      3789137.04     10214483.48
      3788700.74     10214094.83
#Sta/Elev= 30
  4529.1  298.72  4578.9  297.79  4624.8  294.62  4676.3  293.28  4738.6  288.35
  4773.7  285.11  4804.6  280.47  4911.7  269.73  4917.2  269.89  4957.6  265.25
  4969.6  262.94  4980.6  260.82  4984.4  256.04  4987.9  256.04  4991.6  257.74
  5002.8   257.9  5008.4   260.9  5029.3  260.94  5043.5  262.51  5079.3  260.88
  5108.7  261.25  5178.1  265.01  5199.8  267.67  5241.7  268.57  5263.4  271.24
  5347.8  274.78  5390.5  278.79  5417.5  279.57  5579.7  290.65  5584.3  290.33
#Mann= 6 ,-1 , 0
  4529.1     .17       0  4969.6     .09       0  5043.5     .15       0
  5108.7     .17       0  5417.5     .11       0  5579.7     .17       0
Bank Sta=4969.6,5043.5
XS Rating Curve= 0 ,0
Exp/Cntr=0.3,0.1

Type RM Length L Ch R = 1 ,499     ,380,380,380
BEGIN DESCRIPTION:
Conroe Lake 071 1.0
END DESCRIPTION:
XS GIS Cut Line= 3
       3789769.6     10214537.92      3789361.26     10214077.24
      3788741.95     10213976.83
#Sta/Elev= 30
  4384.4  287.91  4440.1  286.42  4517.8  282.34  4525.4  281.13  4560.5  281.47
  4574.7  278.97  4664.7  274.85  4701.8  271.77    4844  264.31  4893.4  259.78
  4950.2  258.45  4971.1  259.56  4985.4  258.44  4991.1  256.06  5003.6  256.58
  5023.7  259.65    5044  261.13  5095.8  259.77    5125  259.53  5165.5  262.58
  5216.2  264.89  5236.5  267.32    5277  270.13  5316.1  275.17  5418.8   285.3
  5469.5  286.27  5506.1  288.31  5540.4  288.19  5601.2  292.09  5627.4  292.69
#Mann= 5 ,-1 , 0
  4384.4     .11       0  4664.7     .17       0  4971.1     .09       0
  5023.7     .15       0  5095.8     .17       0
Bank Sta=4971.1,5023.7
XS Rating Curve= 0 ,0
Exp/Cntr=0.3,0.1

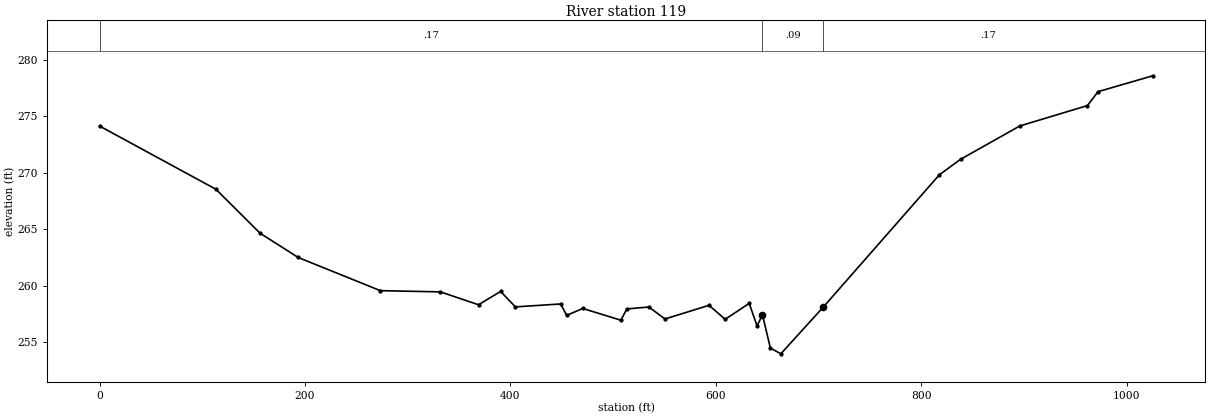
Type RM Length L Ch R = 1 ,119     ,0,0,0
BEGIN DESCRIPTION:
Conroe Lake 071 0.5
END DESCRIPTION:
XS GIS Cut Line= 3
      3789692.67     10214259.89      3789375.43     10213721.77
      3788984.56     10213816.81
#Sta/Elev= 30
       0  274.14   113.4  268.53   156.3  264.64   193.4  262.49   273.4  259.55
   331.9  259.44     369   258.3   390.5  259.48   404.9  258.11     449  258.37
   454.8  257.36   470.5  257.97   507.6  256.93   513.4  257.93   534.9   258.1
   550.5  257.04   593.4  258.25   609.1  257.01   632.5  258.42   640.2  256.42
   645.4  257.42   653.1  254.47   663.3  253.95   704.5  258.08   817.7  269.82
   838.3  271.19   895.9  274.14   961.8  275.95   972.1  277.18  1025.4  278.59
#Mann= 3 , 0 , 0
       0     .17       0   645.4     .09       0   704.5     .17       0
Bank Sta=645.4,704.5
XS Rating Curve= 0 ,0
Exp/Cntr=0.3,0.1

Chan Stop Cuts=-1
Use User Specified Reach Order=0
Composite Channel Slope=5