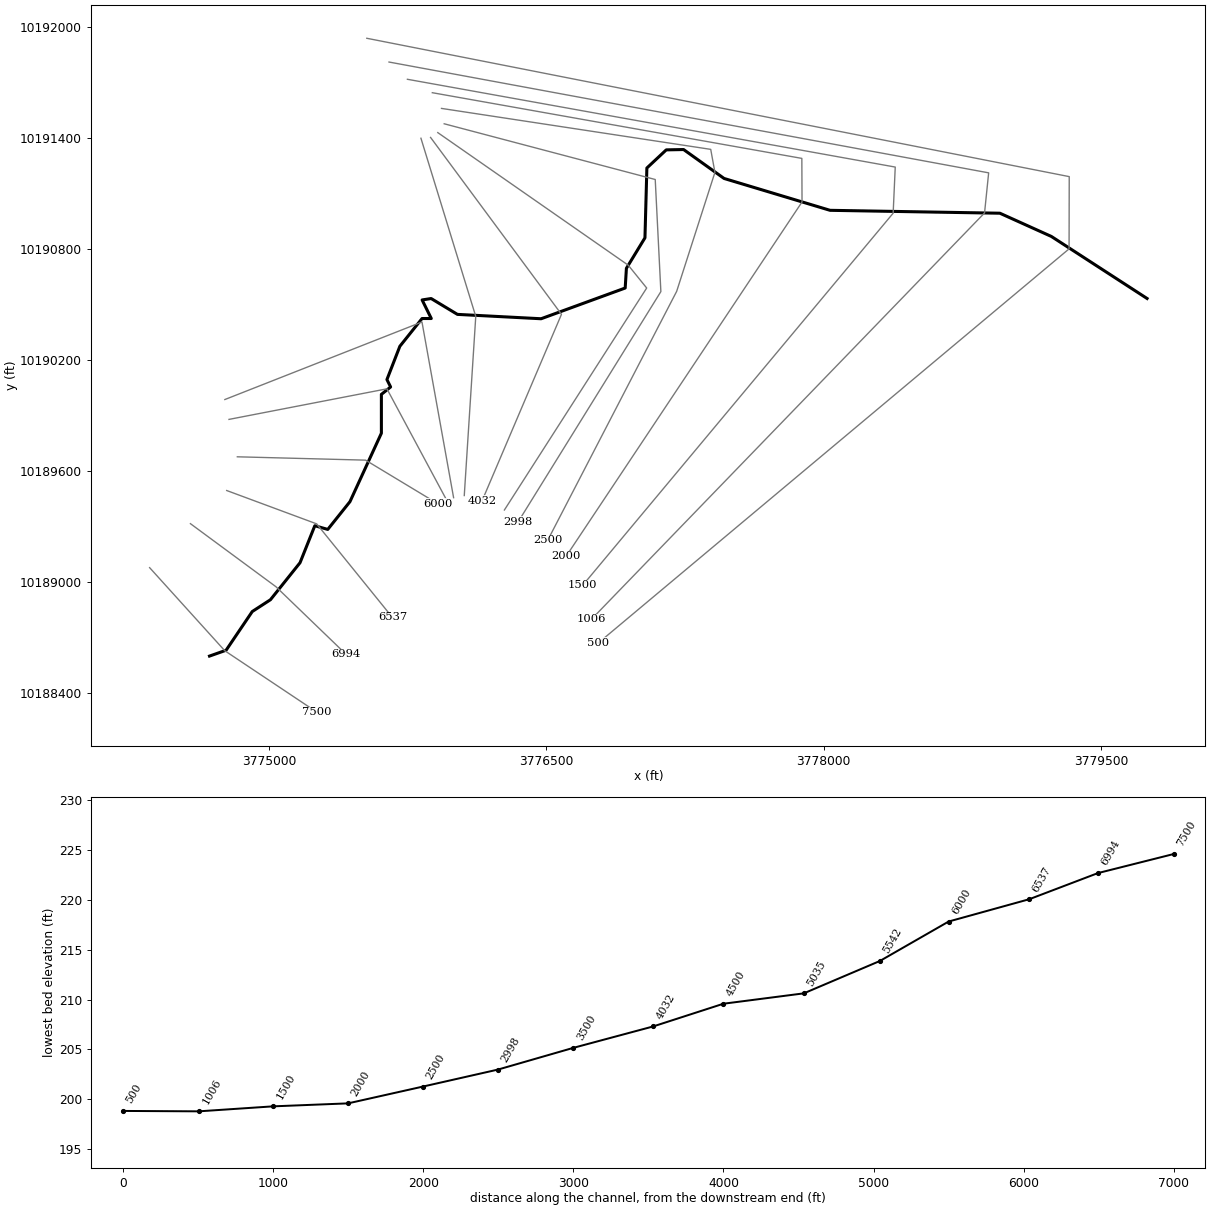
--- Conroe Lake 072.prj (project) ---

Proj Title=Conroe Lake 072 Base Level Engineering
Current Plan=p01
Default Exp/Contr=0.3,0.1
English Units
Geom File=g01
Flow File=f01
Flow File=f02
Plan File=p01
Y Axis Title=Elevation
X Axis Title(PF)=Main Channel Distance
X Axis Title(XS)=Station
BEGIN DESCRIPTION:
Conroe Lake 072
END DESCRIPTION:
DSS Export Rating Curves= 0
DSS Export Rating Curve Sorted= 0
DSS Export Volume Flow Curves= 0
DXF OffsetX= 0
DXF OffsetY= 0
DXF ScaleX= 1
DXF ScaleY= 10

--- Conroe Lake 072.p01 (plan) ---

Plan Title=Multiple Run
Short Identifier=Multiple
Geom File=g01
Flow File=f01
Subcritical Flow
K Sum by GR= 0
Std Step Tol= 0.01
Critical Tol= 0.01
Num of Std Step Trials= 20
Max Error Tol= 0.3
Flow Tol Ratio= 0.001
Split Flow NTrial= 30
Split Flow Tol= 0.02
Split Flow Ratio= 0.02
Log Output Level= 0
Friction Slope Method= 1
Unsteady Friction Slope Method= 2
Unsteady Bridges Friction Slope Method= 1
Parabolic Critical Depth
Global Vel Dist=  1 , 1 , 1
Global Log Level= 0
CheckData=True
Encroach Param= -1, 0, 0, 0
BEGIN DESCRIPTION:
Multiple Run
END DESCRIPTION:

--- Conroe Lake 072.f01 (steady flow) ---

Flow Title=Multiple
Program Version=4.10
Number of Profiles= 7
Profile Names=10-year,25-year,50-year,1pct_min,100-year,1pct_plu,500-year
River Rch & RM=Conroe Lake 072,Reach-1         ,7500
     553     749    1011     450    1359    4104    2535
River Rch & RM=Conroe Lake 072,Reach-1         ,4500
    1204    1670    2292    1032    3117    9413    5965
Boundary for River Rch & Prof#=Conroe Lake 072,Reach-1         , 1
Up Type= 0
Dn Type= 3
Dn Slope=0.001
Boundary for River Rch & Prof#=Conroe Lake 072,Reach-1         , 2
Up Type= 0
Dn Type= 3
Dn Slope=0.001
Boundary for River Rch & Prof#=Conroe Lake 072,Reach-1         , 3
Up Type= 0
Dn Type= 3
Dn Slope=0.001
Boundary for River Rch & Prof#=Conroe Lake 072,Reach-1         , 4
Up Type= 0
Dn Type= 3
Dn Slope=0.001
Boundary for River Rch & Prof#=Conroe Lake 072,Reach-1         , 5
Up Type= 0
Dn Type= 3
Dn Slope=0.001
Boundary for River Rch & Prof#=Conroe Lake 072,Reach-1         , 6
Up Type= 0
Dn Type= 3
Dn Slope=0.001
Boundary for River Rch & Prof#=Conroe Lake 072,Reach-1         , 7
Up Type= 0
Dn Type= 3
Dn Slope=0.001
DSS Import GetInterval= 0
DSS Import GetPeak= 0
DSS Import FillOption= 0

--- Conroe Lake 072.f02 (steady flow) ---

Flow Title=Orig_BLE_Flow
Program Version=4.10
Number of Profiles= 7
Profile Names=10-year,25-year,50-year,1pct_min,100-year,1pct_plu,500-year
River Rch & RM=Conroe Lake 072,Reach-1         ,7500
     553     734     879     346    1045    3156    1474
River Rch & RM=Conroe Lake 072,Reach-1         ,4500
    1204    1637    1993     794    2398    7241    3468
Boundary for River Rch & Prof#=Conroe Lake 072,Reach-1         , 1
Up Type= 0
Dn Type= 3
Dn Slope=0.001
Boundary for River Rch & Prof#=Conroe Lake 072,Reach-1         , 2
Up Type= 0
Dn Type= 3
Dn Slope=0.001
Boundary for River Rch & Prof#=Conroe Lake 072,Reach-1         , 3
Up Type= 0
Dn Type= 3
Dn Slope=0.001
Boundary for River Rch & Prof#=Conroe Lake 072,Reach-1         , 4
Up Type= 0
Dn Type= 3
Dn Slope=0.001
Boundary for River Rch & Prof#=Conroe Lake 072,Reach-1         , 5
Up Type= 0
Dn Type= 3
Dn Slope=0.001
Boundary for River Rch & Prof#=Conroe Lake 072,Reach-1         , 6
Up Type= 0
Dn Type= 3
Dn Slope=0.001
Boundary for River Rch & Prof#=Conroe Lake 072,Reach-1         , 7
Up Type= 0
Dn Type= 3
Dn Slope=0.001
DSS Import GetInterval= 0
DSS Import GetPeak= 0
DSS Import FillOption= 0

--- Conroe Lake 072.g01 (geometry) ---

Geom Title=Existing Conditions
Program Version=4.10

River Reach=Conroe Lake 072 ,Reach-1
Reach XY= 30
      3774678.63     10188602.19      3774768.36     10188633.82
      3774909.86     10188843.02      3775008.23     10188906.84
      3775168.23     10189106.84      3775248.23     10189306.84
      3775318.23     10189286.84      3775438.23     10189436.84
      3775608.23     10189806.84      3775608.23     10190016.84
      3775658.23     10190056.84      3775638.23     10190096.84
      3775708.23     10190276.84      3775828.23     10190426.84
      3775878.23     10190426.84      3775828.56     10190527.28
      3775877.38     10190534.89      3776019.59     10190449.18
      3776472.13     10190425.61      3776926.98     10190591.67
      3776933.57     10190698.37      3777033.85     10190863.02
      3777044.22     10191240.36      3777149.07     10191338.44
      3777242.86     10191340.25      3777461.84      10191183.9
      3778035.03     10191011.71      3778953.63     10190996.04
      3779231.98     10190870.52       3779749.8     10190535.09

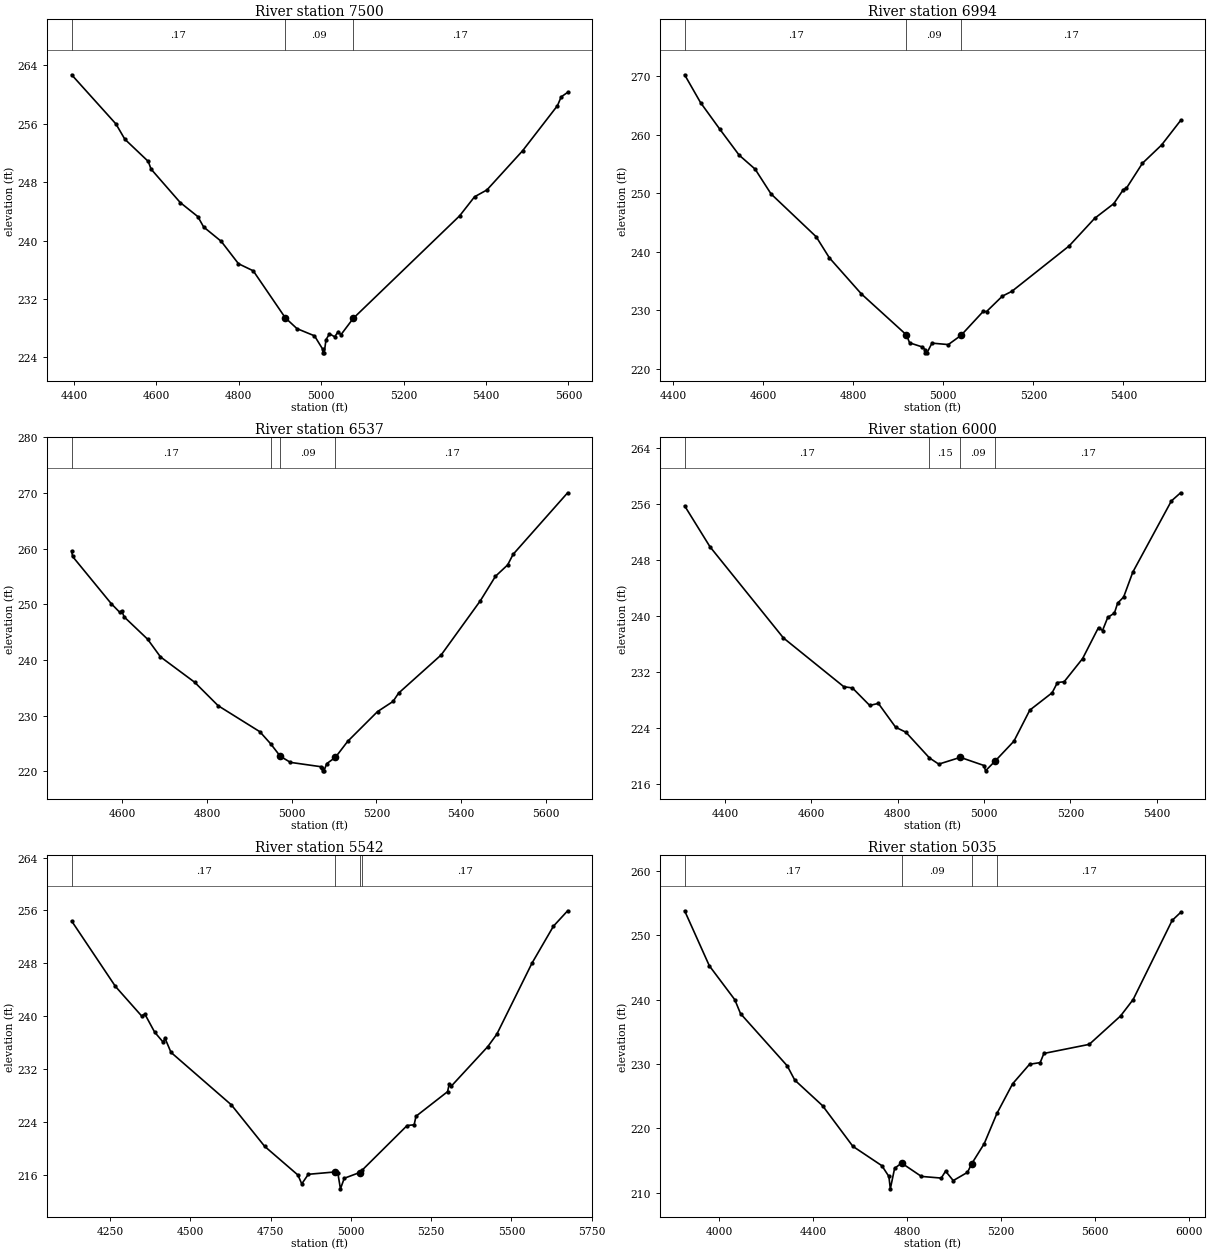
Type RM Length L Ch R = 1 ,7500    ,506,506,506
BEGIN DESCRIPTION:
Conroe Lake 072 15.0
END DESCRIPTION:
XS GIS Cut Line= 3
       3774354.7     10189080.17       3774761.2     10188631.13
      3775258.83     10188299.33
#Sta/Elev= 30
  4394.3  262.72  4501.8  255.98  4523.4  253.89  4580.2  250.85    4587   249.8
  4657.9  245.21  4700.5  243.29  4714.7  241.86  4757.3   239.9  4799.2  236.83
    4835  235.86  4912.7  229.43  4941.1  227.94  4983.7  226.95  5003.6  225.12
  5003.8  224.62  5007.3  224.62  5011.6  226.41    5020  227.23  5032.6  226.82
  5041.6  227.54  5047.6  227.08  5077.7  229.34  5336.1   243.4  5372.1     246
  5402.2  246.94  5488.8  252.31  5573.4  258.49  5582.4  259.69  5598.1  260.31
#Mann= 3 , 0 , 0
  4394.3     .17       0  4912.7     .09       0  5077.7     .17       0
Bank Sta=4912.7,5077.7
XS Rating Curve= 0 ,0
Exp/Cntr=0.3,0.1

Type RM Length L Ch R = 1 ,6994    ,457,457,457
BEGIN DESCRIPTION:
Conroe Lake 072 14.0
END DESCRIPTION:
XS GIS Cut Line= 3
      3774575.45     10189317.93      3775038.23     10188976.84
      3775417.88     10188611.05
#Sta/Elev= 30
  4425.1  270.22  4460.5  265.46  4502.6  260.99  4546.2  256.49  4581.7   254.1
  4617.1  249.86  4717.4  242.54  4746.7  238.94  4817.7  232.78  4917.9  225.77
    4925  224.41  4953.4   223.7  4959.8   223.2  4960.1   222.7  4963.6   222.7
  4974.7  224.36    5011  224.11  5039.3  225.69  5088.7  229.79  5095.9  229.75
  5131.1  232.39  5152.2  233.21  5279.5  240.97  5336.1  245.68  5378.6  248.19
    5400   250.6  5406.9  250.85  5442.4   255.1  5484.8  258.21  5527.2  262.41
#Mann= 3 , 0 , 0
  4425.1     .17       0  4917.9     .09       0  5039.3     .17       0
Bank Sta=4917.9,5039.3
XS Rating Curve= 0 ,0
Exp/Cntr=0.3,0.1

Type RM Length L Ch R = 1 ,6537    ,537,537,537
BEGIN DESCRIPTION:
Conroe Lake 072 13.0
END DESCRIPTION:
XS GIS Cut Line= 3
      3774771.65      10189497.1      3775258.23     10189316.84
      3775667.82      10188811.1
#Sta/Elev= 30
  4481.1  259.59  4483.2   258.6  4574.4  250.12  4594.1  248.59  4599.5  248.74
    4605  247.73  4660.2  243.73  4690.6  240.55  4771.1     236  4826.6  231.78
  4924.9  227.11  4950.4  224.94  4973.2  222.69  4997.1   221.6  5068.1  220.83
  5072.6  220.58  5072.8  220.08  5076.3  220.08  5082.5  221.36  5103.3  222.52
  5132.1  225.38  5202.4  230.72  5239.1  232.55    5252  234.03  5352.7  240.91
    5445  250.64  5480.6  255.03  5509.3  257.07  5522.2  258.97  5650.8  270.03
#Mann= 4 ,-1 , 0
  4481.1     .17       0  4950.4     .15       0  4973.2     .09       0
  5103.3     .17       0
Bank Sta=4973.2,5103.3
XS Rating Curve= 0 ,0
Exp/Cntr=0.3,0.1

Type RM Length L Ch R = 1 ,6000    ,458,458,458
BEGIN DESCRIPTION:
Conroe Lake 072 12.0
END DESCRIPTION:
XS GIS Cut Line= 3
      3774829.05     10189679.36      3775522.72     10189661.33
      3775912.86     10189426.04
#Sta/Elev= 30
  4306.1  255.76  4364.9   249.9    4535  236.86    4675  229.88    4695   229.7
    4735   227.2  4755.1  227.49  4795.1  224.08  4818.8  223.37  4873.6  219.68
  4895.1   218.8  4945.1  219.77    5000   218.6  5003.4  217.84  5026.5  219.29
  5069.2  222.08  5106.1  226.53  5157.8  229.01  5170.2  230.48  5185.7  230.59
  5228.4   233.9  5265.3  238.35  5274.6  237.92  5286.7  239.79  5302.2  240.42
  5309.6  241.83  5323.6  242.72  5344.9  246.29  5434.2  256.46  5455.6  257.63
#Mann= 4 ,-1 , 0
  4306.1     .17       0  4873.6     .15       0  4945.1     .09       0
  5026.5     .17       0
Bank Sta=4945.1,5026.5
XS Rating Curve= 0 ,0
Exp/Cntr=0.3,0.1

Type RM Length L Ch R = 1 ,5542    ,507,507,507
BEGIN DESCRIPTION:
Conroe Lake 072 11.0
END DESCRIPTION:
XS GIS Cut Line= 3
      3774784.07     10189881.58      3775638.23     10190046.84
      3775957.52     10189452.14
#Sta/Elev= 30
    4130   254.4  4266.3  244.51  4347.7  240.05  4357.9  240.33  4388.5  237.59
  4415.4  236.05  4420.5   236.7  4439.4  234.53  4627.6  226.58  4731.2  220.31
  4834.8  215.97  4846.8  214.63  4867.2  216.08  4951.6  216.44  4958.9  216.35
  4967.3  213.88  4979.2  215.48  5027.2  216.35    5035  216.71    5175  223.46
  5196.9  223.57  5202.6  224.86  5300.9  228.58  5306.5  229.78    5313  229.44
  5426.5  235.41  5454.3  237.27  5563.9  248.02  5630.8  253.62    5675  255.95
#Mann= 4 ,-1 , 0
    4130     .17       0  4951.6     .09       0  5027.2     .15       0
    5035     .17       0
Bank Sta=4951.6,5027.2
XS Rating Curve= 0 ,0
Exp/Cntr=0.3,0.1

Type RM Length L Ch R = 1 ,5035    ,535,535,535
BEGIN DESCRIPTION:
Conroe Lake 072 10.0
END DESCRIPTION:
XS GIS Cut Line= 3
      3774761.62     10189988.94      3775827.81     10190408.13
      3775998.86     10189458.44
#Sta/Elev= 30
  3852.9   253.8    3958  245.26  4066.4  239.99  4090.8  237.83  4289.4  229.73
  4321.6  227.51  4439.8  223.54  4568.8  217.23  4692.3  214.22  4722.1  212.55
  4728.2  210.63  4746.5  213.82  4776.3  214.63  4860.3  212.56  4944.9   212.3
  4963.3  213.38  4995.9  211.91  5056.5  213.19 5074.35  214.52  5127.6  217.63
  5181.7  222.33  5248.6  226.94  5320.7  229.97  5365.9  230.23  5381.7  231.65
  5574.7  233.06  5707.9  237.47  5761.5  240.02  5927.4   252.3  5963.5  253.54
#Mann= 4 ,-1 , 0
  3852.9     .17       0  4776.3     .09       0 5074.35     .15       0
  5181.7     .17       0
Bank Sta=4776.3,5074.35
XS Rating Curve= 0 ,0
Exp/Cntr=0.3,0.1

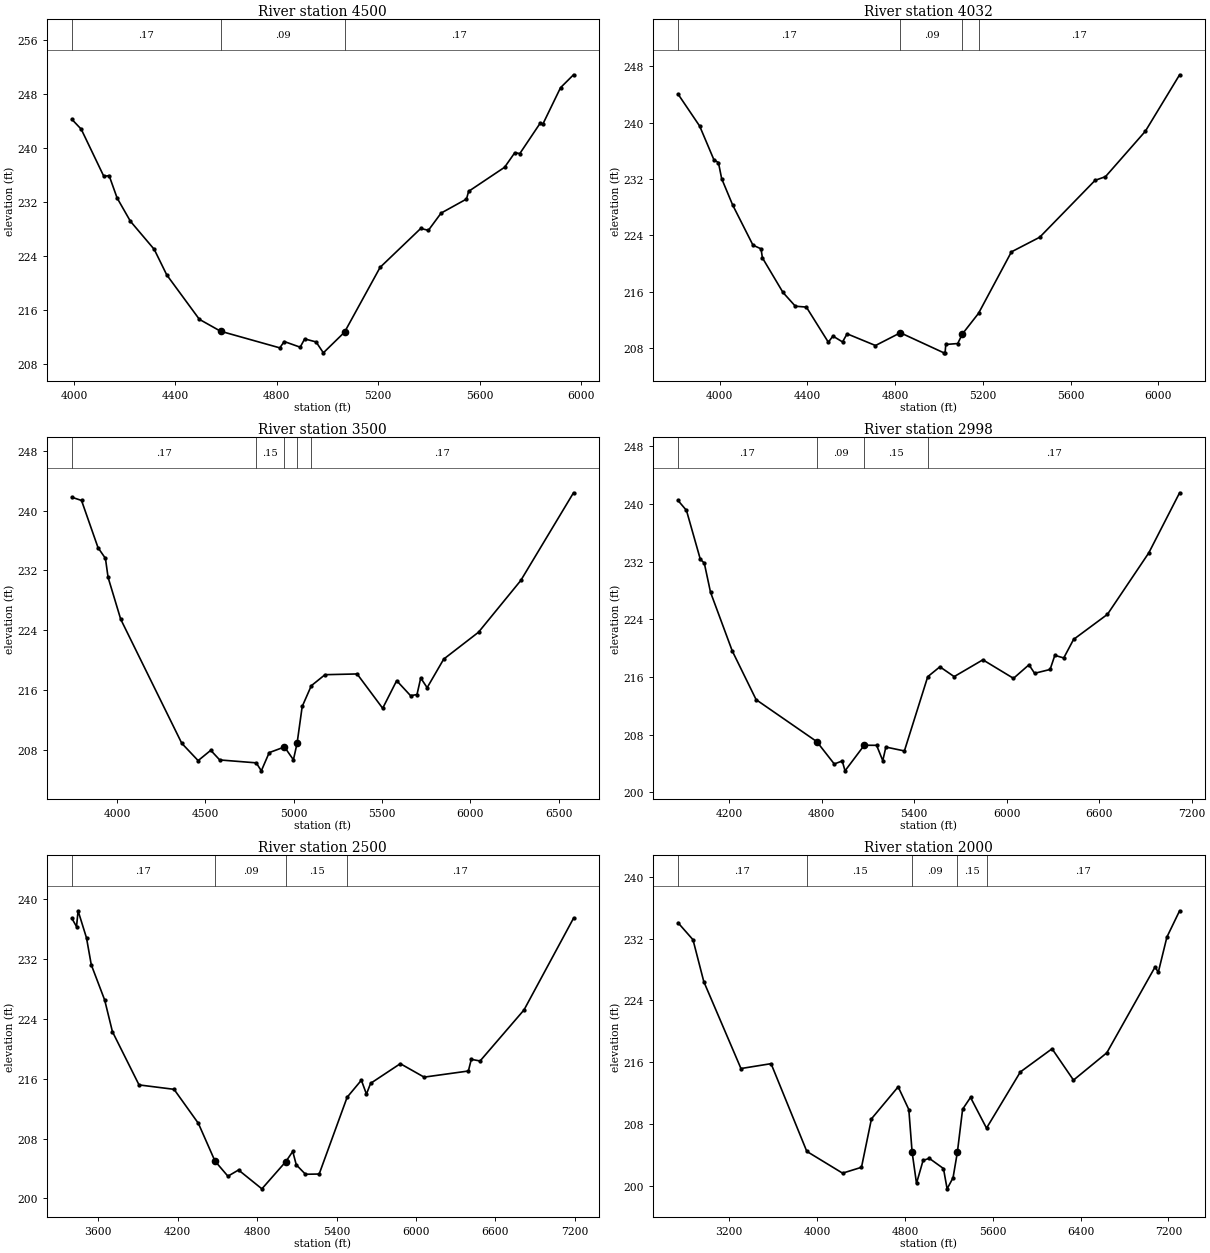
Type RM Length L Ch R = 1 ,4500    ,468,468,468
BEGIN DESCRIPTION:
Conroe Lake 072 9.0
END DESCRIPTION:
XS GIS Cut Line= 3
      3775822.19     10191401.32      3776118.73     10190438.23
      3776056.56     10189469.93
#Sta/Elev= 30
  3992.3  244.27  4028.9  242.82  4118.1  235.81    4139  235.92  4170.4   232.6
  4222.7  229.15  4316.9  224.96  4366.2  221.17  4494.8  214.57  4578.5   212.8
    4812  210.33  4829.6  211.27  4892.4  210.43  4910.1  211.66  4955.2  211.21
  4983.8  209.59  5067.3  212.66  5207.6  222.29  5367.9  228.07    5398  227.79
  5448.1  230.35  5548.3  232.44  5556.6  233.58  5698.6  237.16  5738.7  239.32
  5758.7   239.2  5838.9  243.71  5848.9  243.53  5919.1  248.98  5970.3   250.9
#Mann= 3 , 0 , 0
  3992.3     .17       0  4578.5     .09       0  5067.3     .17       0
Bank Sta=4578.5,5067.3
XS Rating Curve= 0 ,0
Exp/Cntr=0.3,0.1

Type RM Length L Ch R = 1 ,4032    ,532,532,532
BEGIN DESCRIPTION:
Conroe Lake 072 8.0
END DESCRIPTION:
XS GIS Cut Line= 3
      3775874.28     10191405.66      3776582.33     10190449.48
      3776152.44     10189440.44
#Sta/Elev= 30
  3810.2  244.06  3908.9  239.51  3973.6  234.74  3994.5  234.32  4009.1  232.05
  4059.2  228.31  4151.9   222.6  4188.6  222.08  4194.9   220.8  4288.8  215.88
  4345.1  213.93  4395.2  213.81  4495.4  208.82  4516.3  209.69  4560.1  208.86
    4581  210.01  4710.4  208.35  4823.8  210.16  5022.1  207.31  5027.6  207.31
  5030.9   208.5  5085.2  208.63    5107  210.01  5180.1  212.92  5330.1  221.65
  5459.1  223.73  5711.6  231.81  5758.9  232.33  5940.6  238.78  6096.8   246.8
#Mann= 4 ,-1 , 0
  3810.2     .17       0  4823.8     .09       0    5107     .15       0
  5180.1     .17       0
Bank Sta=4823.8,5107
XS Rating Curve= 0 ,0
Exp/Cntr=0.3,0.1

Type RM Length L Ch R = 1 ,3500    ,502,502,502
BEGIN DESCRIPTION:
Conroe Lake 072 7.0
END DESCRIPTION:
XS GIS Cut Line= 4
      3775913.31     10191431.73      3776943.45     10190715.08
      3777043.24     10190591.69      3776273.59     10189391.81
#Sta/Elev= 30
  3745.1  241.81  3799.4  241.38  3892.9  235.05  3934.8  233.62  3949.6  231.09
  4021.2  225.47  4366.8  208.85  4459.4  206.53  4530.9  207.91  4581.6  206.62
  4788.4  206.23  4817.1  205.16  4861.7   207.6  4948.1  208.36  4998.8  206.64
  5019.7  208.87  5048.5  213.78    5100  216.56  5177.6  218.04  5359.3  218.14
    5504  213.54  5583.3  217.24  5661.9  215.23  5698.3  215.38  5719.4   217.6
  5755.7   216.3  5849.6  220.13  6046.5  223.73  6285.7  230.66  6584.2  242.41
#Mann= 5 ,-1 , 0
  3745.1     .17       0  4788.4     .15       0  4948.1     .09       0
  5019.7     .15       0    5100     .17       0
Bank Sta=4948.1,5019.7
XS Rating Curve= 0 ,0
Exp/Cntr=0.3,0.1

Type RM Length L Ch R = 1 ,2998    ,498,498,498
BEGIN DESCRIPTION:
Conroe Lake 072 6.0
END DESCRIPTION:
XS GIS Cut Line= 4
      3775948.01     10191479.47      3777089.45     10191178.29
      3777119.93     10190572.34      3776347.37     10189326.69
#Sta/Elev= 30
  3868.6  240.48  3923.2  239.11  4013.2  232.32  4038.9   231.8  4079.2  227.76
  4220.1  219.62  4375.2  212.85  4768.2  207.04    4882  203.93  4933.7  204.35
  4951.6  202.98  5076.4  206.53  5156.5  206.52  5196.5  204.39  5216.5  206.28
  5336.7  205.74  5488.1  216.04    5567  217.41  5659.5  216.05  5845.7  218.38
  6044.2  215.81  6144.6  217.69  6181.2  216.51  6281.6  217.04  6312.4     219
  6370.2  218.64    6434  221.21  6653.7  224.69  6921.9  233.22  7121.6  241.55
#Mann= 4 ,-1 , 0
  3868.6     .17       0  4768.2     .09       0  5076.4     .15       0
  5488.1     .17       0
Bank Sta=4768.2,5076.4
XS Rating Curve= 0 ,0
Exp/Cntr=0.3,0.1

Type RM Length L Ch R = 1 ,2500    ,500,500,500
BEGIN DESCRIPTION:
Conroe Lake 072 5.0
END DESCRIPTION:
XS GIS Cut Line= 5
      3775933.42     10191562.52      3777389.62     10191341.19
      3777412.31     10191216.76      3777205.36     10190573.64
      3776508.29     10189228.98
#Sta/Elev= 30
  3400.6  237.44  3435.4  236.35    3447  238.47  3510.7  234.84  3546.7  231.25
    3648  226.53  3706.6   222.3  3907.6  215.18  4172.1  214.59  4355.9  210.04
  4481.2     205  4579.1  202.97  4659.3   203.8  4835.8  201.28  5016.5  204.92
    5069  206.28  5095.7  204.49  5165.1  203.23  5268.6  203.26  5479.9  213.53
  5587.4  215.81  5625.8  213.95  5657.3  215.39  5881.7  218.02  6061.5  216.22
  6395.9  217.04    6418   218.6  6484.4  218.38  6816.3  225.21  7190.2  237.47
#Mann= 4 ,-1 , 0
  3400.6     .17       0  4481.2     .09       0  5016.5     .15       0
  5479.9     .17       0
#XS Ineff= 2 , 0
       0                    5069       0  206.28
Permanent Ineff=
       F       F
Bank Sta=4481.2,5016.5
XS Rating Curve= 0 ,0
Exp/Cntr=0.3,0.1

Type RM Length L Ch R = 1 ,2000    ,500,500,500
BEGIN DESCRIPTION:
Conroe Lake 072 4.0
END DESCRIPTION:
XS GIS Cut Line= 4
      3775883.73     10191647.46      3777882.45     10191292.39
      3777883.48      10191056.9      3776607.52      10189141.6
#Sta/Elev= 30
  2734.5  234.05  2870.7  231.85  2969.2  226.42  3307.5  215.17  3581.7   215.8
    3907  204.44  4232.8  201.62  4404.9  202.38  4495.8  208.66    4739   212.8
  4835.8  209.86  4865.8  204.35  4905.8   200.3  4965.8  203.27  5022.1  203.54
  5151.3  202.22  5184.5  199.59  5238.5  201.02 5278.17  204.35  5325.6   209.9
  5397.7  211.43  5543.3  207.45  5851.5  214.73    6140  217.73  6335.3  213.67
  6638.8  217.21  7077.5  228.31  7107.6  227.65  7185.7  232.19  7301.4   235.6
#Mann= 5 ,-1 , 0
  2734.5     .17       0    3907     .15       0  4865.8     .09       0
 5278.17     .15       0  5543.3     .17       0
#XS Ineff= 2 , 0
       0    4739   212.8               0
Permanent Ineff=
       F       F
Bank Sta=4865.8,5278.17
XS Rating Curve= 0 ,0
Exp/Cntr=0.3,0.1

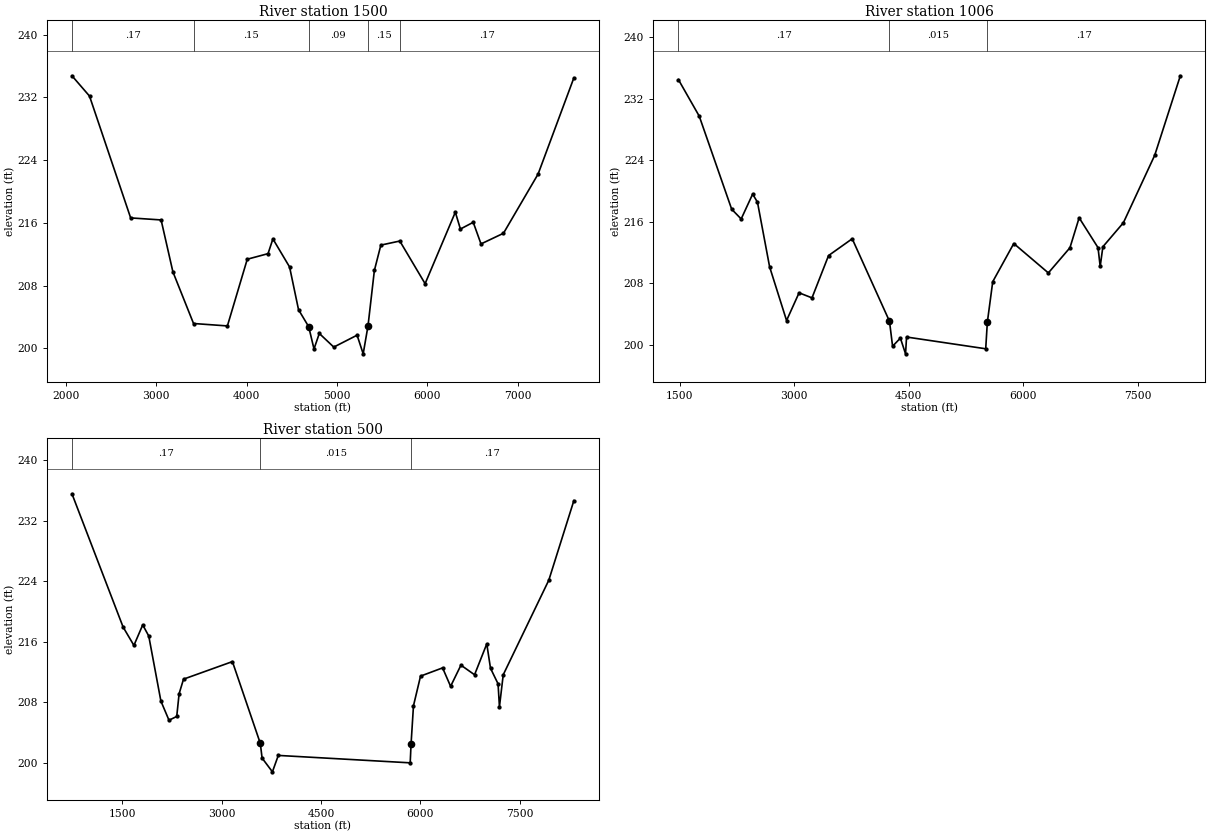
Type RM Length L Ch R = 1 ,1500    ,494,494,494
BEGIN DESCRIPTION:
Conroe Lake 072 3.0
END DESCRIPTION:
XS GIS Cut Line= 4
      3775749.04     10191719.98      3778387.65     10191245.51
      3778376.33      10190996.2      3776697.27     10188984.82
#Sta/Elev= 30
  2069.5  234.76  2263.7  232.17  2718.6  216.63  3055.5  216.37  3185.9  209.75
    3414  203.16  3788.6  202.85  4008.3  211.36  4238.1  212.07  4291.8  213.95
  4476.3  210.37  4575.3  204.92  4687.7  202.75  4746.4  199.91  4804.9  201.89
  4965.1  200.15  5222.8  201.67  5290.3  199.29  5343.8  202.87  5414.1  209.93
  5485.7  213.16  5695.2  213.68    5975  208.24  6309.3  217.36  6365.5  215.21
  6507.3  216.07  6593.2  213.31  6841.8  214.67  7224.5  222.22  7620.1  234.49
#Mann= 5 ,-1 , 0
  2069.5     .17       0    3414     .15       0  4687.7     .09       0
  5343.8     .15       0  5695.2     .17       0
#XS Ineff= 2 , 0
       0  4291.8  213.95               0
Permanent Ineff=
       F       F
Bank Sta=4687.7,5343.8
XS Rating Curve= 0 ,0
Exp/Cntr=0.3,0.1

Type RM Length L Ch R = 1 ,1006    ,506,506,506
BEGIN DESCRIPTION:
Conroe Lake 072 1.0
END DESCRIPTION:
XS GIS Cut Line= 4
      3775649.58     10191813.21      3778892.86     10191214.26
      3778870.68     10190997.62      3776744.16     10188800.75
#Sta/Elev= 30
  1484.1  234.51  1756.9  229.75  2181.6  217.63    2306  216.36  2456.5   219.6
  2519.6  218.54  2678.5  210.12  2900.5  203.13  3064.4  206.74  3233.5  206.08
  3450.4  211.59  3760.2  213.78  4248.3  203.04    4289  199.78  4391.3  200.84
  4458.8  198.79  4472.1  200.98  5508.8  199.45  5529.9  202.89  5600.7  208.19
  5876.4  213.16  6329.2  209.33  6611.9  212.61  6732.3  216.51  6979.7  212.62
    7008  210.17  7043.3  212.74  7312.1  215.87  7722.4  224.66  8057.5  235.01
#Mann= 3 , 0 , 0
  1484.1     .17       0  4248.3    .015       0  5529.9     .17       0
Bank Sta=4248.3,5529.9
XS Rating Curve= 0 ,0
Exp/Cntr=0.3,0.1

Type RM Length L Ch R = 1 ,500     ,0,0,0
BEGIN DESCRIPTION:
Conroe Lake 072 1.5
END DESCRIPTION:
XS GIS Cut Line= 4
      3775529.44     10191941.66      3779328.73     10191193.86
      3779327.85     10190803.35      3776782.18     10188673.58
#Sta/Elev= 30
   737.3  235.58  1510.3  217.96  1673.3  215.54  1806.4  218.25  1897.6  216.78
    2081  208.18  2203.3  205.65  2320.1  206.15  2356.2  209.16  2422.8  211.08
  3161.3   213.4 3582.72  202.59  3609.5  200.65  3765.6  198.83  3854.4     201
  5846.9  200.02  5859.8  202.49  5896.4  207.56  6003.1  211.48  6336.2  212.57
  6457.2  210.13  6613.4  212.93    6819  211.66  7003.7  215.74    7060  212.52
  7174.2  210.46    7195  207.42  7252.3  211.66  7940.7  224.16  8319.1  234.67
#Mann= 3 , 0 , 0
   737.3     .17       0 3582.72    .015       0  5859.8     .17       0
Bank Sta=3582.72,5859.8
XS Rating Curve= 0 ,0
Exp/Cntr=0.3,0.1

Chan Stop Cuts=-1
Use User Specified Reach Order=0
Composite Channel Slope=5