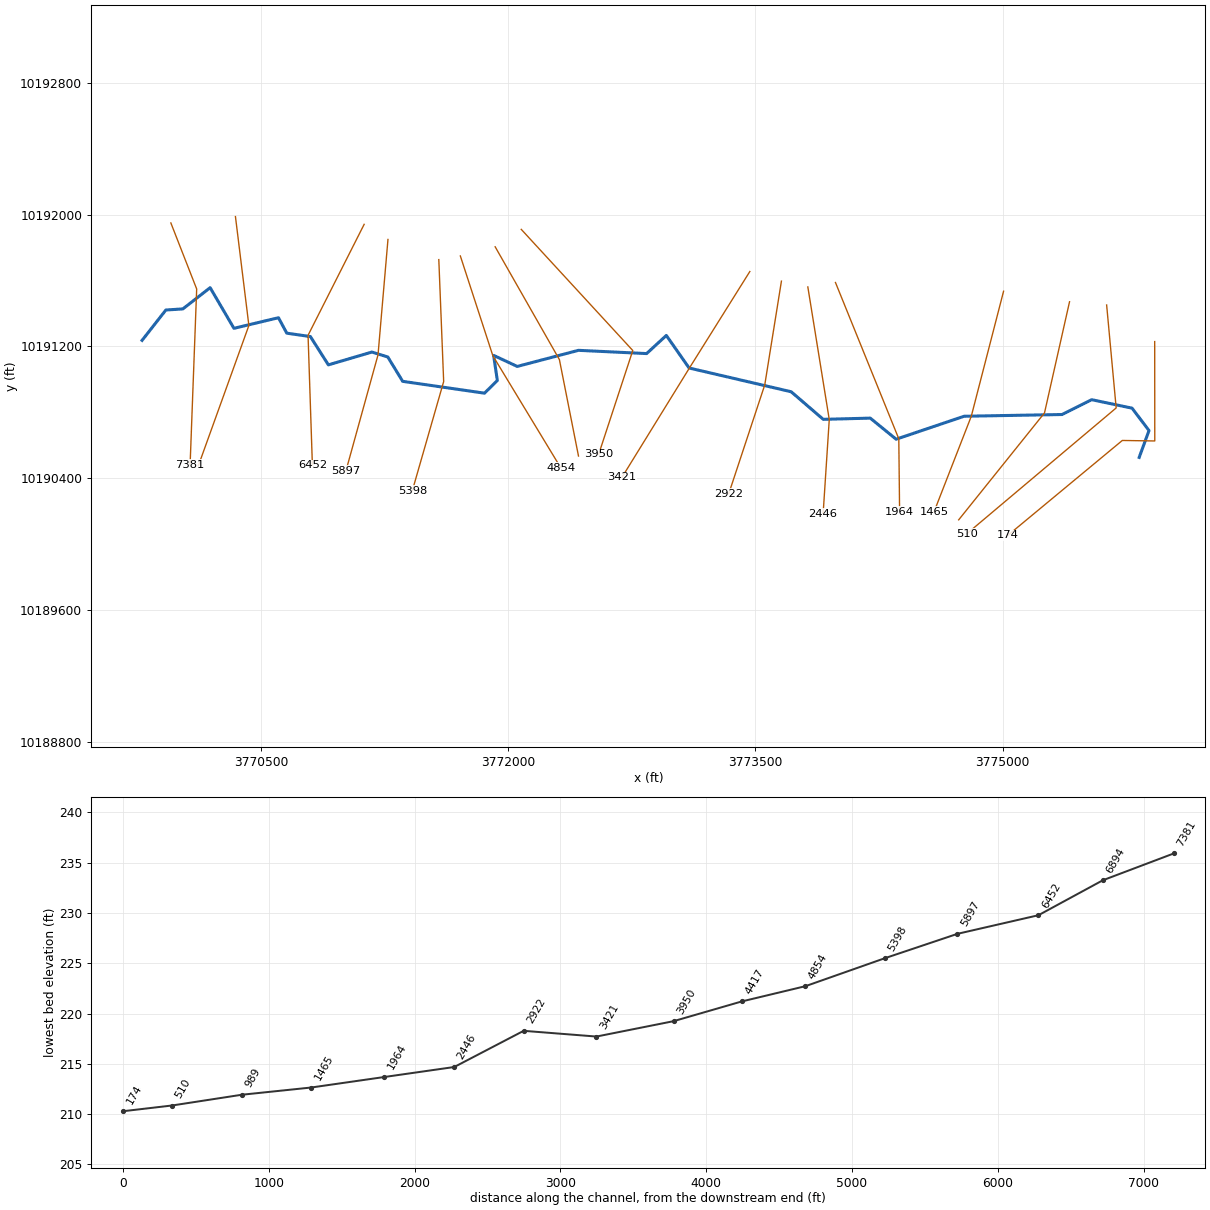
--- Conroe Lake 073.prj (project) ---

Proj Title=Conroe Lake 073 Base Level Engineering
Current Plan=p01
Default Exp/Contr=0.3,0.1
English Units
Geom File=g01
Flow File=f01
Flow File=f02
Plan File=p01
Y Axis Title=Elevation
X Axis Title(PF)=Main Channel Distance
X Axis Title(XS)=Station
BEGIN DESCRIPTION:
Conroe Lake 073
END DESCRIPTION:
DSS Export Rating Curves= 0
DSS Export Rating Curve Sorted= 0
DSS Export Volume Flow Curves= 0
DXF OffsetX= 0
DXF OffsetY= 0
DXF ScaleX= 1
DXF ScaleY= 10

--- Conroe Lake 073.p01 (plan) ---

Plan Title=Multiple Run
Short Identifier=Multiple
Geom File=g01
Flow File=f01
Subcritical Flow
K Sum by GR= 0
Std Step Tol= 0.01
Critical Tol= 0.01
Num of Std Step Trials= 20
Max Error Tol= 0.3
Flow Tol Ratio= 0.001
Split Flow NTrial= 30
Split Flow Tol= 0.02
Split Flow Ratio= 0.02
Log Output Level= 0
Friction Slope Method= 1
Unsteady Friction Slope Method= 2
Unsteady Bridges Friction Slope Method= 1
Parabolic Critical Depth
Global Vel Dist=  1 , 1 , 1
Global Log Level= 0
CheckData=True
Encroach Param= -1, 0, 0, 0
BEGIN DESCRIPTION:
Multiple Run
END DESCRIPTION:

--- Conroe Lake 073.f01 (steady flow) ---

Flow Title=Multiple
Program Version=4.10
Number of Profiles= 7
Profile Names=10-year,25-year,50-year,1pct_min,100-year,1pct_plu,500-year
River Rch & RM=Conroe Lake 073,Reach-1         ,7381
     837    1159    1592     719    2170    6553    4174
River Rch & RM=Conroe Lake 073,Reach-1         ,5897
     931    1283    1755     788    2380    7187    4530
Boundary for River Rch & Prof#=Conroe Lake 073,Reach-1         , 1
Up Type= 0
Dn Type= 3
Dn Slope=0.009
Boundary for River Rch & Prof#=Conroe Lake 073,Reach-1         , 2
Up Type= 0
Dn Type= 3
Dn Slope=0.009
Boundary for River Rch & Prof#=Conroe Lake 073,Reach-1         , 3
Up Type= 0
Dn Type= 3
Dn Slope=0.009
Boundary for River Rch & Prof#=Conroe Lake 073,Reach-1         , 4
Up Type= 0
Dn Type= 3
Dn Slope=0.009
Boundary for River Rch & Prof#=Conroe Lake 073,Reach-1         , 5
Up Type= 0
Dn Type= 3
Dn Slope=0.009
Boundary for River Rch & Prof#=Conroe Lake 073,Reach-1         , 6
Up Type= 0
Dn Type= 3
Dn Slope=0.009
Boundary for River Rch & Prof#=Conroe Lake 073,Reach-1         , 7
Up Type= 0
Dn Type= 3
Dn Slope=0.009
DSS Import GetInterval= 0
DSS Import GetPeak= 0
DSS Import FillOption= 0

--- Conroe Lake 073.f02 (steady flow) ---

Flow Title=Orig_BLE_Flow
Program Version=4.10
Number of Profiles= 7
Profile Names=10-year,25-year,50-year,1pct_min,100-year,1pct_plu,500-year
River Rch & RM=Conroe Lake 073,Reach-1         ,7381
     837    1136    1384     553    1669    5042    2427
River Rch & RM=Conroe Lake 073,Reach-1         ,5897
     931    1258    1526     606    1831    5529    2634
Boundary for River Rch & Prof#=Conroe Lake 073,Reach-1         , 1
Up Type= 0
Dn Type= 3
Dn Slope=0.015
Boundary for River Rch & Prof#=Conroe Lake 073,Reach-1         , 2
Up Type= 0
Dn Type= 3
Dn Slope=0.015
Boundary for River Rch & Prof#=Conroe Lake 073,Reach-1         , 3
Up Type= 0
Dn Type= 3
Dn Slope=0.015
Boundary for River Rch & Prof#=Conroe Lake 073,Reach-1         , 4
Up Type= 0
Dn Type= 3
Dn Slope=0.015
Boundary for River Rch & Prof#=Conroe Lake 073,Reach-1         , 5
Up Type= 0
Dn Type= 3
Dn Slope=0.015
Boundary for River Rch & Prof#=Conroe Lake 073,Reach-1         , 6
Up Type= 0
Dn Type= 3
Dn Slope=0.015
Boundary for River Rch & Prof#=Conroe Lake 073,Reach-1         , 7
Up Type= 0
Dn Type= 3
Dn Slope=0.015
DSS Import GetInterval= 0
DSS Import GetPeak= 0
DSS Import FillOption= 0

--- Conroe Lake 073.g01 (geometry) ---

Geom Title=Existing Conditions
Program Version=4.10

River Reach=Conroe Lake 073 ,Reach-1
Reach XY= 30
      3769778.23     10191236.84      3769922.76     10191421.11
      3770025.79     10191427.72      3770191.33      10191556.6
      3770335.77     10191310.05      3770606.01     10191374.23
      3770656.35     10191280.63      3770799.65     10191259.98
      3770908.73     10191088.28      3771173.02     10191166.08
      3771269.32     10191136.11      3771359.62     10190988.36
      3771856.02     10190916.59      3771933.94     10190993.72
      3771911.31     10191145.94      3772054.53     10191078.81
      3772426.22     10191176.55      3772839.64      10191156.8
      3772959.25     10191266.86       3773097.4     10191069.33
       3773716.6     10190925.26      3773911.53     10190757.86
      3774196.63     10190765.24      3774353.54     10190637.34
      3774766.11     10190776.62      3775360.28     10190787.15
      3775540.17     10190877.07      3775784.93     10190825.79
      3775887.88     10190689.75      3775828.23     10190526.84

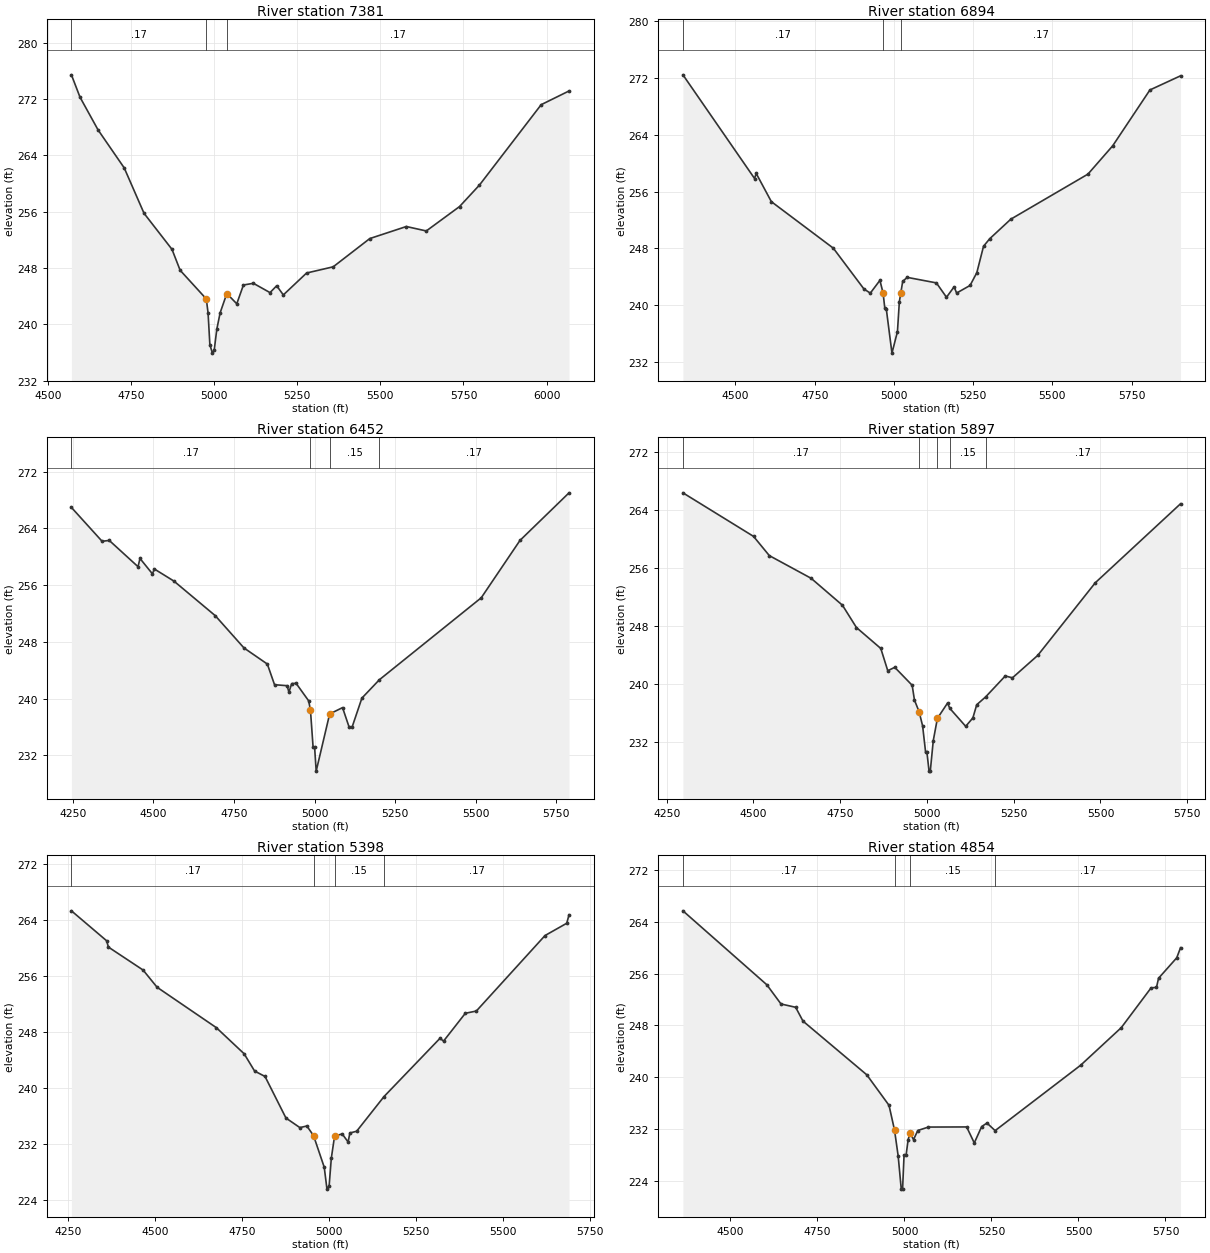
Type RM Length L Ch R = 1 ,7381    ,487,487,487
BEGIN DESCRIPTION:
Conroe Lake 073 15.0
END DESCRIPTION:
XS GIS Cut Line= 3
      3769953.01     10191949.15      3770109.67      10191548.7
      3770069.73     10190481.75
#Sta/Elev= 30
    4570  275.43  4595.9  272.25  4650.2  267.61  4728.9  262.22  4788.6  255.77
  4872.7  250.66  4897.2  247.69    4976  243.62  4981.3  241.62  4986.7  237.13
  4994.3  235.93    5000  236.43  5007.6  239.33  5017.6  241.65  5037.7  244.39
  5067.7  242.93  5087.7   245.6  5117.7  245.84  5167.7  244.52  5187.8  245.49
  5207.8  244.19  5277.8   247.3  5357.9  248.18    5468  252.19    5578   253.9
  5638.1  253.27  5738.1  256.73  5798.2  259.79  5983.8  271.19  6067.7  273.14
#Mann= 3 , 0 , 0
    4570     .17       0    4976     .07       0  5037.7     .17       0
Bank Sta=4976,5037.7
XS Rating Curve= 0 ,0
Exp/Cntr=0.3,0.1

Type RM Length L Ch R = 1 ,6894    ,442,442,442
BEGIN DESCRIPTION:
Conroe Lake 073 14.0
END DESCRIPTION:
XS GIS Cut Line= 3
      3770344.87     10191988.06      3770426.38     10191327.17
      3770119.76     10190476.23
#Sta/Elev= 30
  4334.1  272.45  4560.2  257.85  4565.3  258.57  4613.2  254.59  4808.7  248.04
  4905.4  242.29  4925.5  241.71  4955.8  243.51  4965.8  241.72    4971  239.67
  4976.1  239.42  4993.8  233.26  5011.1  236.29  5017.1  240.49 5021.72  241.74
  5027.7  243.36  5041.8  243.93    5134  243.15  5165.9  241.13    5190   242.6
  5197.8  241.72  5240.3  242.79  5261.6  244.59  5282.8  248.31  5302.1  249.36
  5368.8  252.12  5612.4  258.47  5690.5  262.46  5807.9  270.32  5904.5  272.31
#Mann= 3 , 0 , 0
  4334.1     .17       0  4965.8     .07       0 5021.72     .17       0
#XS Ineff= 2 , 0
       0  4955.8  243.51  5041.8       0  243.93
Permanent Ineff=
       F       F
Bank Sta=4965.8,5021.72
XS Rating Curve= 0 ,0
Exp/Cntr=0.3,0.1

Type RM Length L Ch R = 1 ,6452    ,555,555,555
BEGIN DESCRIPTION:
Conroe Lake 073 13.0
END DESCRIPTION:
XS GIS Cut Line= 3
      3771125.83     10191940.86      3770785.45     10191267.72
      3770811.77     10190478.96
#Sta/Elev= 30
  4245.7  266.94  4340.8  262.17  4363.1  262.29  4452.3  258.59  4458.4  259.75
  4496.8  257.59  4503.2  258.26  4563.7  256.56  4691.8  251.69  4780.9  247.14
  4853.4  244.87  4875.7  241.96  4914.7  241.82  4920.3  240.91    4929  242.11
  4942.5  242.16  4981.5  239.69  4987.1   238.4  4995.3  233.17    5000  233.17
  5004.9  229.78  5046.7  237.84  5086.7  238.73  5106.7  236.03  5116.7  236.04
  5146.7  240.07  5200.7  242.65  5516.9  254.21    5637  262.29  5789.2     269
#Mann= 4 ,-1 , 0
  4245.7     .17       0  4987.1     .07       0  5046.7     .15       0
  5200.7     .17       0
#XS Ineff= 2 , 0
       0  4942.5  242.16               0
Permanent Ineff=
       F       F
Bank Sta=4987.1,5046.7
XS Rating Curve= 0 ,0
Exp/Cntr=0.3,0.1

Type RM Length L Ch R = 1 ,5897    ,499,499,499
BEGIN DESCRIPTION:
Conroe Lake 073 12.0
END DESCRIPTION:
XS GIS Cut Line= 3
      3771270.33     10191849.09       3771209.9     10191148.59
      3771015.08     10190444.44
#Sta/Elev= 30
  4296.9  266.32  4500.4  260.31  4545.8  257.66  4666.3  254.53  4756.6  250.81
  4796.8  247.74    4867  244.85  4887.1  241.78  4907.2  242.25  4957.4  239.77
    4964  237.73  4977.4  236.12  4987.5  234.17  4996.2   230.5    5000   230.5
    5006  227.93  5009.6  227.93  5018.2  232.14  5030.1  235.21  5059.2  237.31
    5066  236.58  5111.6  234.11  5132.3  235.27  5143.4  237.09  5169.1  238.17
  5225.7  241.06  5246.3   240.8  5319.1  243.89  5485.1  253.92  5730.6  264.81
#Mann= 5 ,-1 , 0
  4296.9     .17       0  4977.4     .07       0  5030.1     .17       0
    5066     .15       0  5169.1     .17       0
Bank Sta=4977.4,5030.1
XS Rating Curve= 0 ,0
Exp/Cntr=0.3,0.1

Type RM Length L Ch R = 1 ,5398    ,544,544,544
BEGIN DESCRIPTION:
Conroe Lake 073 11.0
END DESCRIPTION:
XS GIS Cut Line= 3
      3771578.81     10191726.85      3771608.27     10190987.03
      3771418.01     10190324.72
#Sta/Elev= 30
  4259.6  265.35  4360.8  261.06  4365.8  260.16  4465.5  256.87  4505.6  254.41
  4675.7  248.63  4755.8  244.88  4785.8  242.41  4815.8  241.63  4875.9  235.68
  4915.9  234.31  4935.9  234.54  4955.1  233.17  4985.9  228.63  4993.7   225.5
    5000     226  5006.2  229.93  5015.5  233.07  5037.4  233.41  5054.4  232.25
  5059.6  233.54    5079  233.79  5157.7  238.76  5318.3  247.09  5328.7   246.7
  5391.2  250.68  5422.8     251  5620.1  261.81  5682.5  263.57  5689.1  264.78
#Mann= 4 ,-1 , 0
  4259.6     .17       0  4955.1     .07       0  5015.5     .15       0
  5157.7     .17       0
Bank Sta=4955.1,5015.5
XS Rating Curve= 0 ,0
Exp/Cntr=0.3,0.1

Type RM Length L Ch R = 1 ,4854    ,437,437,437
BEGIN DESCRIPTION:
Conroe Lake 073 10.0
END DESCRIPTION:
XS GIS Cut Line= 3
      3771709.44     10191749.04      3771906.64     10191143.86
       3772317.8     10190465.54
#Sta/Elev= 30
  4363.5  265.68  4604.5  254.27  4645.3   251.3  4687.4  250.79  4708.4  248.66
  4891.7  240.37  4955.6  235.66  4971.4  231.85  4981.9  227.85  4990.8  222.72
  4994.6  222.72  4998.8  227.93  5004.6  227.93  5010.6  230.38  5016.4  231.37
    5026  230.36  5038.3  231.77  5068.7   232.3  5178.7  232.32  5200.6  229.85
  5221.9  232.38  5237.1  232.92  5260.5  231.75  5506.1  241.84    5623  247.65
  5708.6  253.79  5724.1  253.86    5730  255.27  5782.3  258.43  5793.2  259.99
#Mann= 4 ,-1 , 0
  4363.5     .17       0  4971.4     .07       0  5016.4     .15       0
  5260.5     .17       0
Bank Sta=4971.4,5016.4
XS Rating Curve= 0 ,0
Exp/Cntr=0.3,0.1

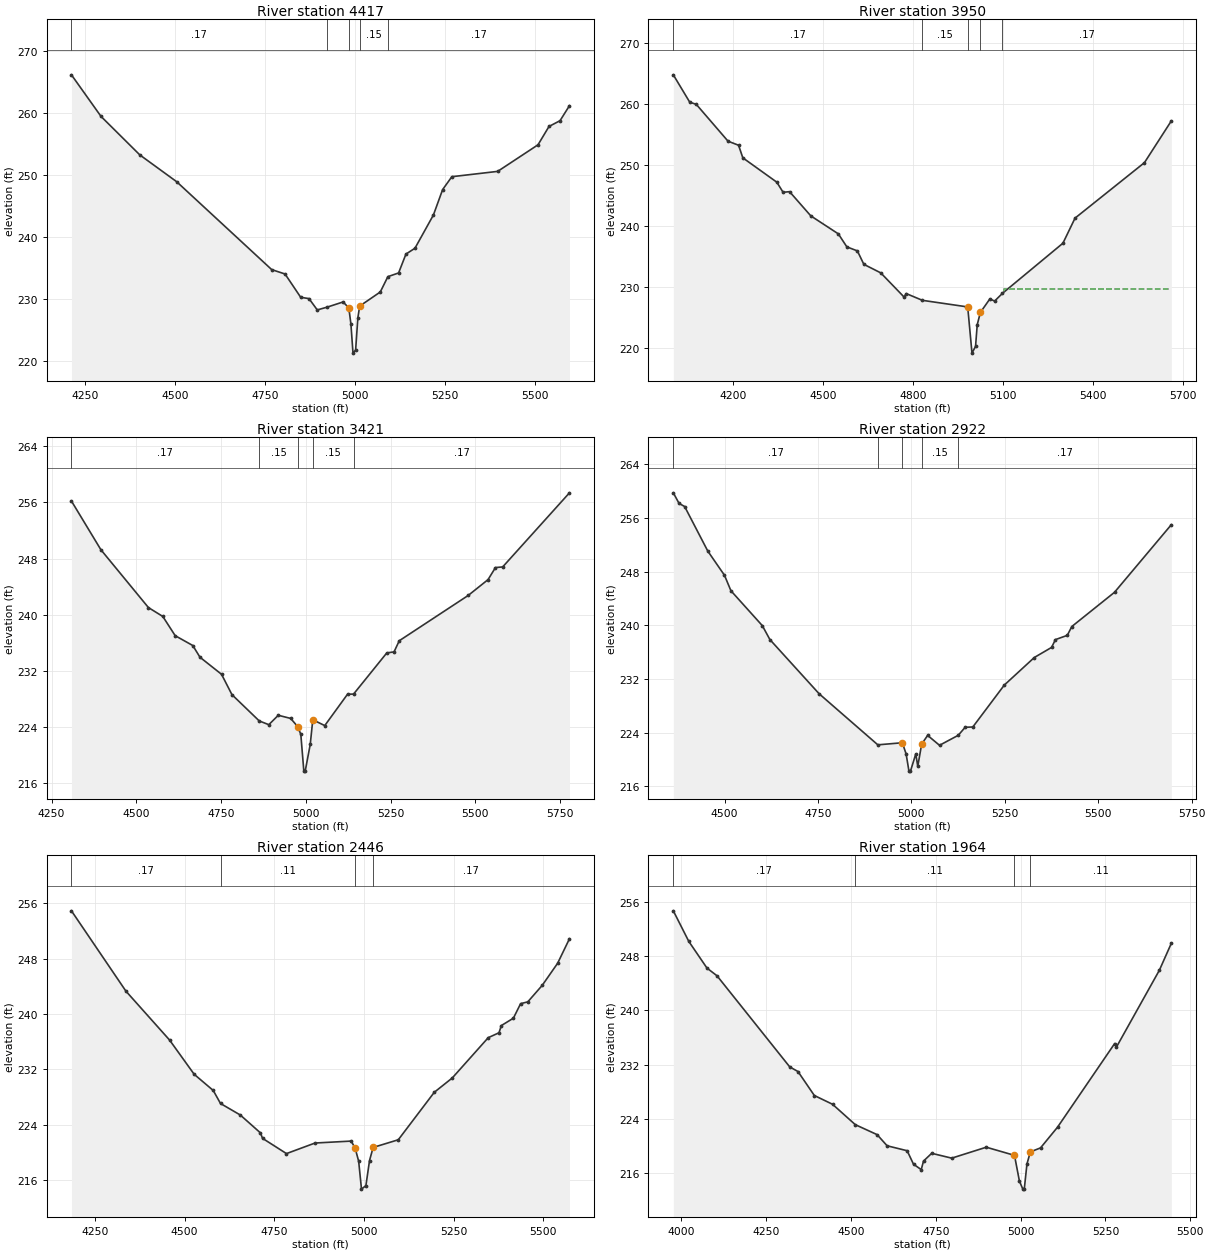
Type RM Length L Ch R = 1 ,4417    ,467,467,467
BEGIN DESCRIPTION:
Conroe Lake 073 9.0
END DESCRIPTION:
XS GIS Cut Line= 3
      3771920.65     10191804.64      3772310.47     10191120.28
       3772426.3     10190535.34
#Sta/Elev= 30
  4212.4  266.22  4294.5   259.5  4402.5  253.26  4504.8  248.93  4768.9  234.71
    4806     234  4849.5  230.23  4872.5  230.02  4895.5  228.19    4923  228.64
  4967.4  229.48  4983.2  228.51    4989  225.92  4994.8   221.2  5002.1   221.7
  5008.3  226.91  5013.4  228.81  5070.6  231.09  5091.7  233.57  5121.5  234.17
  5141.9  237.22    5167  238.17  5218.3  243.55  5243.9  247.66  5269.5  249.74
  5396.8   250.6  5508.9   254.9  5539.5  257.87  5570.1   258.8  5596.3  261.23
#Mann= 5 ,-1 , 0
  4212.4     .17       0    4923     .15       0  4983.2     .07       0
  5013.4     .15       0  5091.7     .17       0
Bank Sta=4983.2,5013.4
XS Rating Curve= 0 ,0
Exp/Cntr=0.3,0.1

Type RM Length L Ch R = 1 ,3950    ,529,529,529
BEGIN DESCRIPTION:
Conroe Lake 073 8.0
END DESCRIPTION:
XS GIS Cut Line= 3
      3772079.08     10191910.23      3772755.72     10191175.41
      3772548.79     10190545.85
#Sta/Elev= 30
  4001.1  264.84    4056  260.35  4077.6  260.01  4183.6  253.97  4218.8   253.3
    4233  251.24  4346.4  247.25  4367.4  245.59  4388.9   245.7  4459.8  241.73
  4551.7  238.78  4580.1  236.65  4615.2  235.99  4636.8  233.79  4693.2  232.39
  4771.2  228.42    4778     229  4832.2  227.89  4983.3  226.81  4997.6  219.24
  5009.5  220.35  5015.1   223.9  5025.6  225.91  5057.2  228.12  5073.1  227.77
  5099.1  229.03    5301  237.25  5341.4  241.36    5573  250.45  5662.7  257.29
#Mann= 5 ,-1 , 0
  4001.1     .17       0  4832.2     .15       0  4983.3     .07       0
  5025.6     .15       0  5099.1     .17       0
#XS Ineff= 2 , 0
       0                  5104.9       0  229.81
Permanent Ineff=
       F       F
Bank Sta=4983.3,5025.6
XS Rating Curve= 0 ,0
Exp/Cntr=0.3,0.1

Type RM Length L Ch R = 1 ,3421    ,499,499,499
BEGIN DESCRIPTION:
Conroe Lake 073 7.0
END DESCRIPTION:
XS GIS Cut Line= 3
      3773465.88     10191654.59      3773098.97      10191068.7
      3772690.46      10190406.7
#Sta/Elev= 30
  4308.7   256.2  4395.6  249.26  4535.8  241.02  4578.3  239.75  4614.8  237.01
  4666.7  235.61  4687.9  233.94  4751.5  231.51  4782.2  228.61  4862.8  224.86
    4891  224.33  4918.9  225.67  4955.5  225.22  4976.7  224.02  4985.4  222.94
  4994.3  217.71  4998.3  217.71  5013.2  221.52  5020.7  225.03    5056   224.2
  5123.2  228.67    5141  228.69  5239.1  234.56  5260.4   234.7  5275.8  236.29
    5479  242.74  5537.7     245  5559.6  246.72  5580.9  246.81  5777.9  257.37
#Mann= 5 ,-1 , 0
  4308.7     .17       0  4862.8     .15       0  4976.7     .07       0
  5020.7     .15       0    5141     .17       0
#XS Ineff= 2 , 0
       0                  5123.2       0  228.67
Permanent Ineff=
       F       F
Bank Sta=4976.7,5020.7
XS Rating Curve= 0 ,0
Exp/Cntr=0.3,0.1

Type RM Length L Ch R = 1 ,2922    ,476,476,476
BEGIN DESCRIPTION:
Conroe Lake 073 6.0
END DESCRIPTION:
XS GIS Cut Line= 3
      3773657.63     10191596.23      3773556.57      10190967.1
      3773338.04     10190306.72
#Sta/Elev= 30
  4362.8  259.77  4378.2  258.19  4393.1  257.73    4455  251.09  4499.7  247.48
    4517  245.17    4601  239.97  4621.2   237.9  4752.9  229.82  4910.1   222.2
  4975.7  222.51  4985.8  220.85  4993.4  218.28  4997.5  218.28  5011.7  220.85
    5017     219  5027.4   222.3  5043.4  223.61  5075.2  222.13  5125.3  223.62
  5143.9  224.82  5164.3  224.86  5248.6  231.11  5328.9  235.22    5375  236.72
  5385.5  237.89  5417.1  238.52  5429.3  239.84  5543.5  244.94  5695.6  255.02
#Mann= 5 ,-1 , 0
  4362.8     .17       0  4910.1     .15       0  4975.7     .07       0
  5027.4     .15       0  5125.3     .17       0
Bank Sta=4975.7,5027.4
XS Rating Curve= 0 ,0
Exp/Cntr=0.3,0.1

Type RM Length L Ch R = 1 ,2446    ,482,482,482
BEGIN DESCRIPTION:
Conroe Lake 073 5.0
END DESCRIPTION:
XS GIS Cut Line= 3
      3773817.85     10191561.07      3773947.89     10190756.51
      3773910.58     10190185.22
#Sta/Elev= 30
    4185  254.94  4336.8  243.32  4458.5  236.24    4527  231.29  4580.1  228.95
  4600.3  227.07  4655.5   225.4  4711.7  222.81  4717.3  222.03  4784.1  219.82
  4863.7  221.35  4964.2  221.63  4975.1  220.66  4985.2  218.72  4993.1  214.68
  5005.4  215.19  5015.5  218.82  5025.5  220.71  5095.6  221.82  5195.9  228.69
    5246  230.76  5346.2  236.59  5376.2   237.3  5382.7  238.34  5416.3  239.41
  5436.4  241.51  5456.4  241.77  5496.5  244.15  5539.6  247.36  5572.5   250.9
#Mann= 4 ,-1 , 0
    4185     .17       0  4600.3     .11       0  4975.1     .07       0
  5025.5     .17       0
Bank Sta=4975.1,5025.5
XS Rating Curve= 0 ,0
Exp/Cntr=0.3,0.1

Type RM Length L Ch R = 1 ,1964    ,499,499,499
BEGIN DESCRIPTION:
Conroe Lake 073 4.0
END DESCRIPTION:
XS GIS Cut Line= 3
      3773985.57     10191587.86      3774369.78     10190639.75
      3774374.64     10190195.78
#Sta/Elev= 30
    3977  254.64  4022.6  250.14  4076.2  246.21  4105.7  245.08  4320.1  231.66
  4344.2  230.99  4392.4  227.46    4446  226.17    4513  223.17  4577.3   221.7
  4606.8  220.06  4665.8  219.33  4684.5  217.35  4707.3  216.55    4714  217.81
  4738.1  218.95  4797.1  218.24  4898.9  219.85    4982  218.65  4996.6  214.84
  5006.6  213.68  5010.8  213.68  5018.7  217.38  5028.7  219.16  5058.7  219.75
  5108.7  222.79  5277.1  235.11  5282.1  234.57  5408.7  245.89    5444  249.86
#Mann= 4 ,-1 , 0
    3977     .17       0    4513     .11       0    4982     .07       0
  5028.7     .11       0
Bank Sta=4982,5028.7
XS Rating Curve= 0 ,0
Exp/Cntr=0.3,0.1

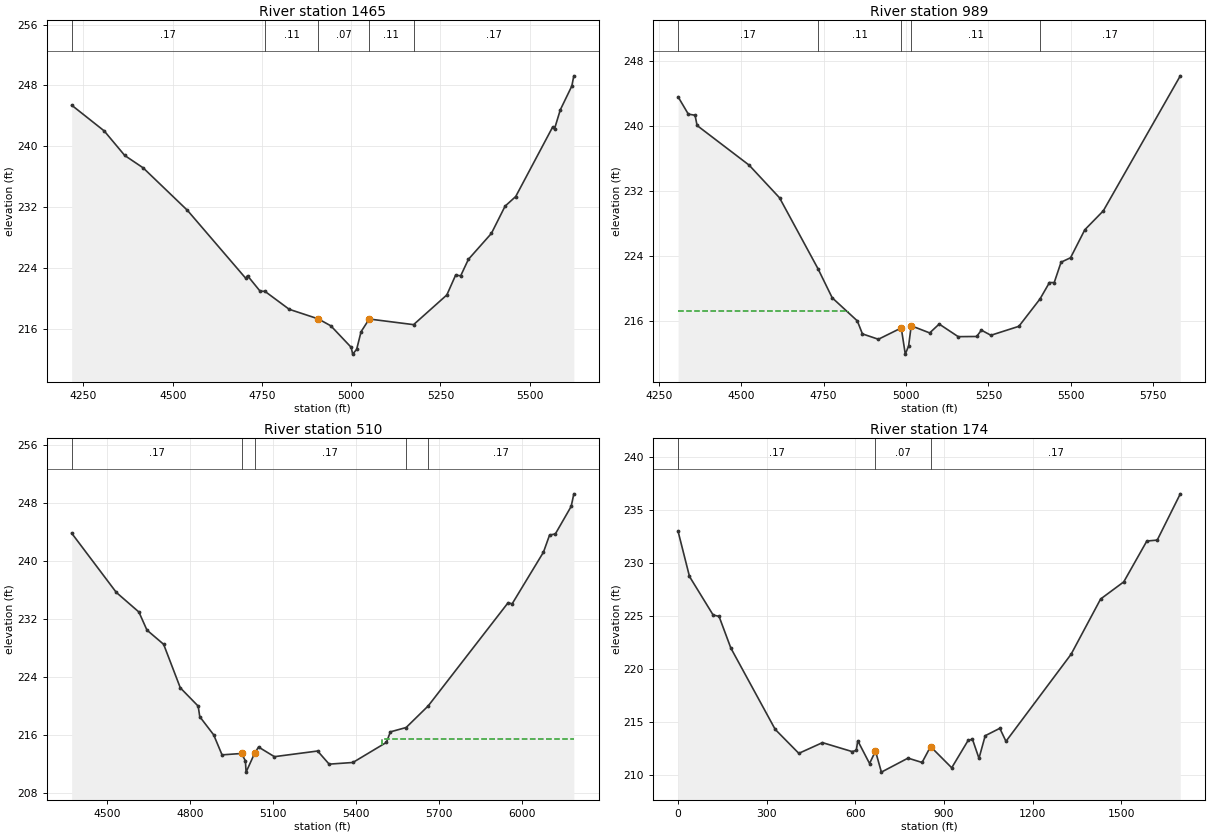
Type RM Length L Ch R = 1 ,1465    ,476,476,476
BEGIN DESCRIPTION:
Conroe Lake 073 3.0
END DESCRIPTION:
XS GIS Cut Line= 3
      3775005.51     10191535.04      3774809.67     10190776.82
       3774583.2      10190195.8
#Sta/Elev= 30
  4216.9   245.4  4308.1  242.01  4365.6  238.78  4417.2  237.15  4541.2  231.56
  4704.3  222.63  4709.5  222.96    4745  220.91  4758.1  220.91  4826.3  218.54
  4907.6  217.28    4943  216.36    5000  213.53    5004  212.64  5015.2  213.26
  5027.6  215.59  5050.4  217.26  5174.7  216.52  5267.9  220.43  5292.4  223.03
  5306.7  222.95  5328.2  225.11  5392.6  228.52    5431  232.11  5460.8  233.38
  5564.2  242.52  5569.6   242.3  5585.7  244.79  5617.9  247.91  5623.6  249.26
#Mann= 5 ,-1 , 0
  4216.9     .17       0  4758.1     .11       0  4907.6     .07       0
  5050.4     .11       0  5174.7     .17       0
Bank Sta=4907.6,5050.4
XS Rating Curve= 0 ,0
Exp/Cntr=0.3,0.1

Type RM Length L Ch R = 1 ,989     ,479,479,479
BEGIN DESCRIPTION:
Conroe Lake 073 2.0
END DESCRIPTION:
XS GIS Cut Line= 3
      3775405.72     10191471.18      3775253.83     10190796.98
      3774733.17     10190148.28
#Sta/Elev= 30
  4308.9  243.57  4339.8  241.45  4360.3  241.31  4366.4  240.05  4524.3  235.17
  4616.5  231.15  4732.9  222.44  4776.2  218.85  4852.3  216.01  4867.8  214.41
  4916.2  213.75  4985.6  215.14  4997.8  211.92  5007.8  212.91  5015.8  215.41
  5071.8  214.53  5100.6  215.62  5158.2  214.07  5214.2  214.09  5228.6  214.87
  5257.4  214.24  5342.2  215.34  5406.2   218.7    5435  220.73  5449.4  220.72
  5470.2  223.23    5499  223.78  5542.2  227.22  5598.3  229.55  5831.8  246.16
#Mann= 5 ,-1 , 0
  4308.9     .17       0  4732.9     .11       0  4985.6     .07       0
  5015.8     .11       0  5406.2     .17       0
#XS Ineff= 2 , 0
       0  4824.6  217.22               0
Permanent Ineff=
       F       F
Bank Sta=4985.6,5015.8
XS Rating Curve= 0 ,0
Exp/Cntr=0.3,0.1

Type RM Length L Ch R = 1 ,510     ,336,336,336
BEGIN DESCRIPTION:
Conroe Lake 073 1.0
END DESCRIPTION:
XS GIS Cut Line= 3
      3775630.82     10191451.72      3775688.65     10190826.99
      3774781.64     10190063.15
#Sta/Elev= 30
  4372.6  243.79  4533.9  235.62  4615.4  232.92  4644.4  230.43  4704.7  228.47
  4764.9  222.47  4829.4  219.95  4835.2  218.49  4885.4  215.99  4915.6  213.23
  4985.9  213.42    5000   212.4  5002.4  210.85  5033.1  213.44  5047.4  214.31
  5104.6  212.98  5260.7  213.76  5302.3  211.95  5388.1  212.18  5509.1  214.95
  5523.4   216.4  5580.3     217  5659.8  219.97  5948.6  234.21  5962.9  234.04
  6076.1  241.17  6098.2  243.53    6119  243.68  6176.2  247.48  6185.8  249.21
#Mann= 5 ,-1 , 0
  4372.6     .17       0  4985.9     .07       0  5033.1     .17       0
  5580.3     .15       0  5659.8     .17       0
#XS Ineff= 2 , 0
       0                  5494.8       0  215.37
Permanent Ineff=
       F       F
Bank Sta=4985.9,5033.1
XS Rating Curve= 0 ,0
Exp/Cntr=0.3,0.1

Type RM Length L Ch R = 1 ,174     ,0,0,0
BEGIN DESCRIPTION:
Conroe Lake 073 0.5
END DESCRIPTION:
XS GIS Cut Line= 4
       3775922.4     10191229.62      3775922.92     10190626.75
      3775725.94     10190629.78      3775032.76      10190055.3
#Sta/Elev= 30
       0  232.96    38.5  228.72   118.5  225.09   138.5  224.96   178.5  221.97
   328.5  214.31   408.5  212.05   488.5  213.06   588.5  212.22   602.9  212.32
   607.9  213.24   647.9  211.09   667.9  212.27   687.9  210.28     778   211.6
   825.6  211.19   854.3  212.69   925.9  210.69   981.9  213.29   996.2  213.37
  1018.2  211.58  1039.2  213.71  1088.7  214.41  1109.5  213.18  1329.9  221.39
  1429.9   226.6  1508.1  228.21  1586.2  232.06  1621.4  232.15  1699.5  236.51
#Mann= 3 , 0 , 0
       0     .17       0   667.9     .07       0   854.3     .17       0
Bank Sta=667.9,854.3
XS Rating Curve= 0 ,0
Exp/Cntr=0.3,0.1

Chan Stop Cuts=-1
Use User Specified Reach Order=0
Composite Channel Slope=5