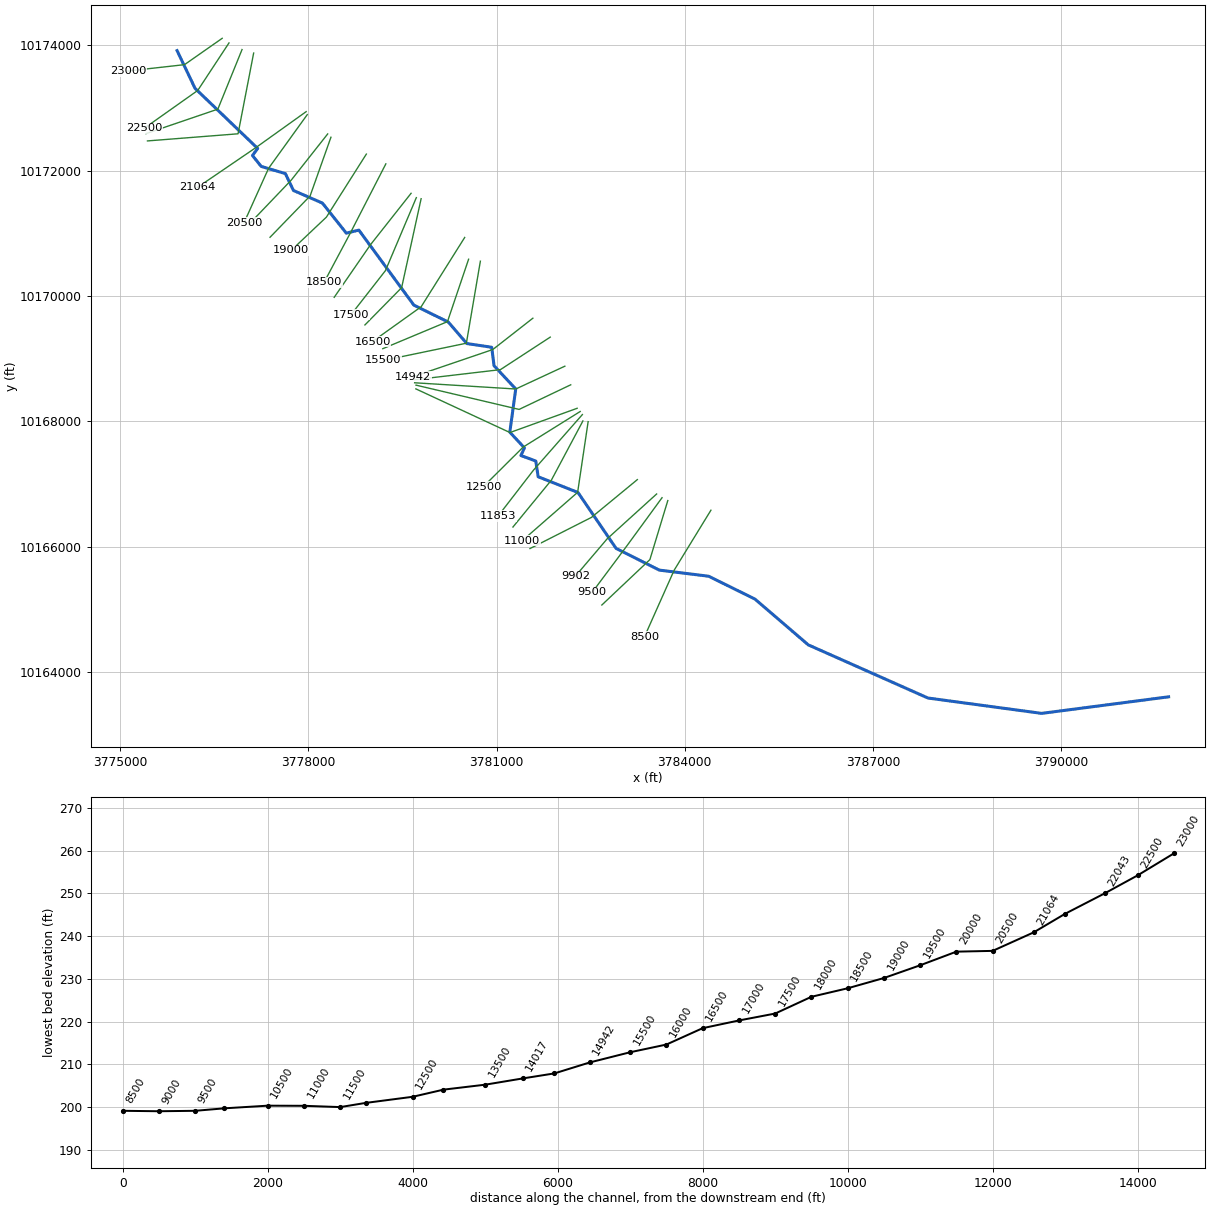
--- Conroe Lake 077.prj (project) ---

Proj Title=Conroe Lake 077 Base Level Engineering
Current Plan=p01
Default Exp/Contr=0.3,0.1
English Units
Geom File=g01
Flow File=f01
Flow File=f02
Plan File=p01
Y Axis Title=Elevation
X Axis Title(PF)=Main Channel Distance
X Axis Title(XS)=Station
BEGIN DESCRIPTION:
Conroe Lake 077
END DESCRIPTION:
DSS Export Rating Curves= 0
DSS Export Rating Curve Sorted= 0
DSS Export Volume Flow Curves= 0
DXF OffsetX= 0
DXF OffsetY= 0
DXF ScaleX= 1
DXF ScaleY= 10

--- Conroe Lake 077.p01 (plan) ---

Plan Title=Multiple Run
Short Identifier=Multiple
Geom File=g01
Flow File=f01
Subcritical Flow
K Sum by GR= 0
Std Step Tol= 0.01
Critical Tol= 0.01
Num of Std Step Trials= 20
Max Error Tol= 0.3
Flow Tol Ratio= 0.001
Split Flow NTrial= 30
Split Flow Tol= 0.02
Split Flow Ratio= 0.02
Log Output Level= 0
Friction Slope Method= 1
Unsteady Friction Slope Method= 2
Unsteady Bridges Friction Slope Method= 1
Parabolic Critical Depth
Global Vel Dist=  1 , 1 , 1
Global Log Level= 0
CheckData=True
Encroach Param= -1, 0, 0, 0
BEGIN DESCRIPTION:
Multiple Run
END DESCRIPTION:

--- Conroe Lake 077.f01 (steady flow) ---

Flow Title=Multiple
Program Version=4.10
Number of Profiles= 7
Profile Names=10-year,25-year,50-year,1pct_min,100-year,1pct_plu,500-year
River Rch & RM=Conroe Lake 077,Reach-1         ,23000
     230     294     383     165     499    1507     874
River Rch & RM=Conroe Lake 077,Reach-1         ,22043
     671     906    1221     541    1634    4935    3027
River Rch & RM=Conroe Lake 077,Reach-1         ,14017
     939    1280    1737     773    2334    7049    4362
River Rch & RM=Conroe Lake 077,Reach-1         ,8500
    1035    1415    1923     857    2587    7813    4847
River Rch & RM=Conroe Lake 077,Reach-1         ,2500
    1354    1874    2566    1152    3478   10503    6610
Boundary for River Rch & Prof#=Conroe Lake 077,Reach-1         , 1
Up Type= 0
Dn Type= 3
Dn Slope=0.005
Boundary for River Rch & Prof#=Conroe Lake 077,Reach-1         , 2
Up Type= 0
Dn Type= 3
Dn Slope=0.005
Boundary for River Rch & Prof#=Conroe Lake 077,Reach-1         , 3
Up Type= 0
Dn Type= 3
Dn Slope=0.005
Boundary for River Rch & Prof#=Conroe Lake 077,Reach-1         , 4
Up Type= 0
Dn Type= 3
Dn Slope=0.005
Boundary for River Rch & Prof#=Conroe Lake 077,Reach-1         , 5
Up Type= 0
Dn Type= 3
Dn Slope=0.005
Boundary for River Rch & Prof#=Conroe Lake 077,Reach-1         , 6
Up Type= 0
Dn Type= 3
Dn Slope=0.005
Boundary for River Rch & Prof#=Conroe Lake 077,Reach-1         , 7
Up Type= 0
Dn Type= 3
Dn Slope=0.005
DSS Import GetInterval= 0
DSS Import GetPeak= 0
DSS Import FillOption= 0

--- Conroe Lake 077.f02 (steady flow) ---

Flow Title=Orig_BLE_Flow
Program Version=4.10
Number of Profiles= 7
Profile Names=10-year,25-year,50-year,1pct_min,100-year,1pct_plu,500-year
River Rch & RM=Conroe Lake 077,Reach-1         ,23000
     230     288     333     127     384    1161     508
River Rch & RM=Conroe Lake 077,Reach-1         ,22043
     671     888    1062     416    1257    3796    1760
River Rch & RM=Conroe Lake 077,Reach-1         ,14017
     939    1255    1510     594    1795    5421    2536
River Rch & RM=Conroe Lake 077,Reach-1         ,8500
    1035    1387    1672     659    1990    6009    2818
River Rch & RM=Conroe Lake 077,Reach-1         ,2500
    1354    1837    2231     886    2675    8079    3843
Boundary for River Rch & Prof#=Conroe Lake 077,Reach-1         , 1
Up Type= 0
Dn Type= 3
Dn Slope=0.005
Boundary for River Rch & Prof#=Conroe Lake 077,Reach-1         , 2
Up Type= 0
Dn Type= 3
Dn Slope=0.005
Boundary for River Rch & Prof#=Conroe Lake 077,Reach-1         , 3
Up Type= 0
Dn Type= 3
Dn Slope=0.005
Boundary for River Rch & Prof#=Conroe Lake 077,Reach-1         , 4
Up Type= 0
Dn Type= 3
Dn Slope=0.005
Boundary for River Rch & Prof#=Conroe Lake 077,Reach-1         , 5
Up Type= 0
Dn Type= 3
Dn Slope=0.005
Boundary for River Rch & Prof#=Conroe Lake 077,Reach-1         , 6
Up Type= 0
Dn Type= 3
Dn Slope=0.005
Boundary for River Rch & Prof#=Conroe Lake 077,Reach-1         , 7
Up Type= 0
Dn Type= 3
Dn Slope=0.005
DSS Import GetInterval= 0
DSS Import GetPeak= 0
DSS Import FillOption= 0

--- Conroe Lake 077.g01 (geometry) ---

Geom Title=Existing Conditions
Program Version=4.10

River Reach=Conroe Lake 077 ,Reach-1
Reach XY= 30
      3775908.23     10173911.84      3776194.58     10173310.59
      3777193.06     10172351.88      3777109.82     10172239.22
      3777249.56     10172065.13      3777634.51     10171950.63
      3777763.33      10171681.3      3778224.66     10171480.39
      3778605.95     10171000.47      3778805.93     10171049.24
      3779682.63     10169852.74      3780232.12     10169582.11
      3780526.62     10169239.87      3780923.55     10169180.39
      3780960.84      10168886.1      3781306.58     10168515.25
       3781212.3     10167826.37      3781444.88     10167574.55
      3781389.14     10167453.11      3781626.04     10167365.52
      3781663.87     10167114.68      3782298.92     10166863.84
      3782906.11     10165971.98      3783594.92     10165625.58
      3784381.27     10165528.04      3785119.85     10165163.72
      3785969.91     10164433.11      3787877.74     10163585.06
      3789690.24     10163340.27      3791714.24     10163604.45

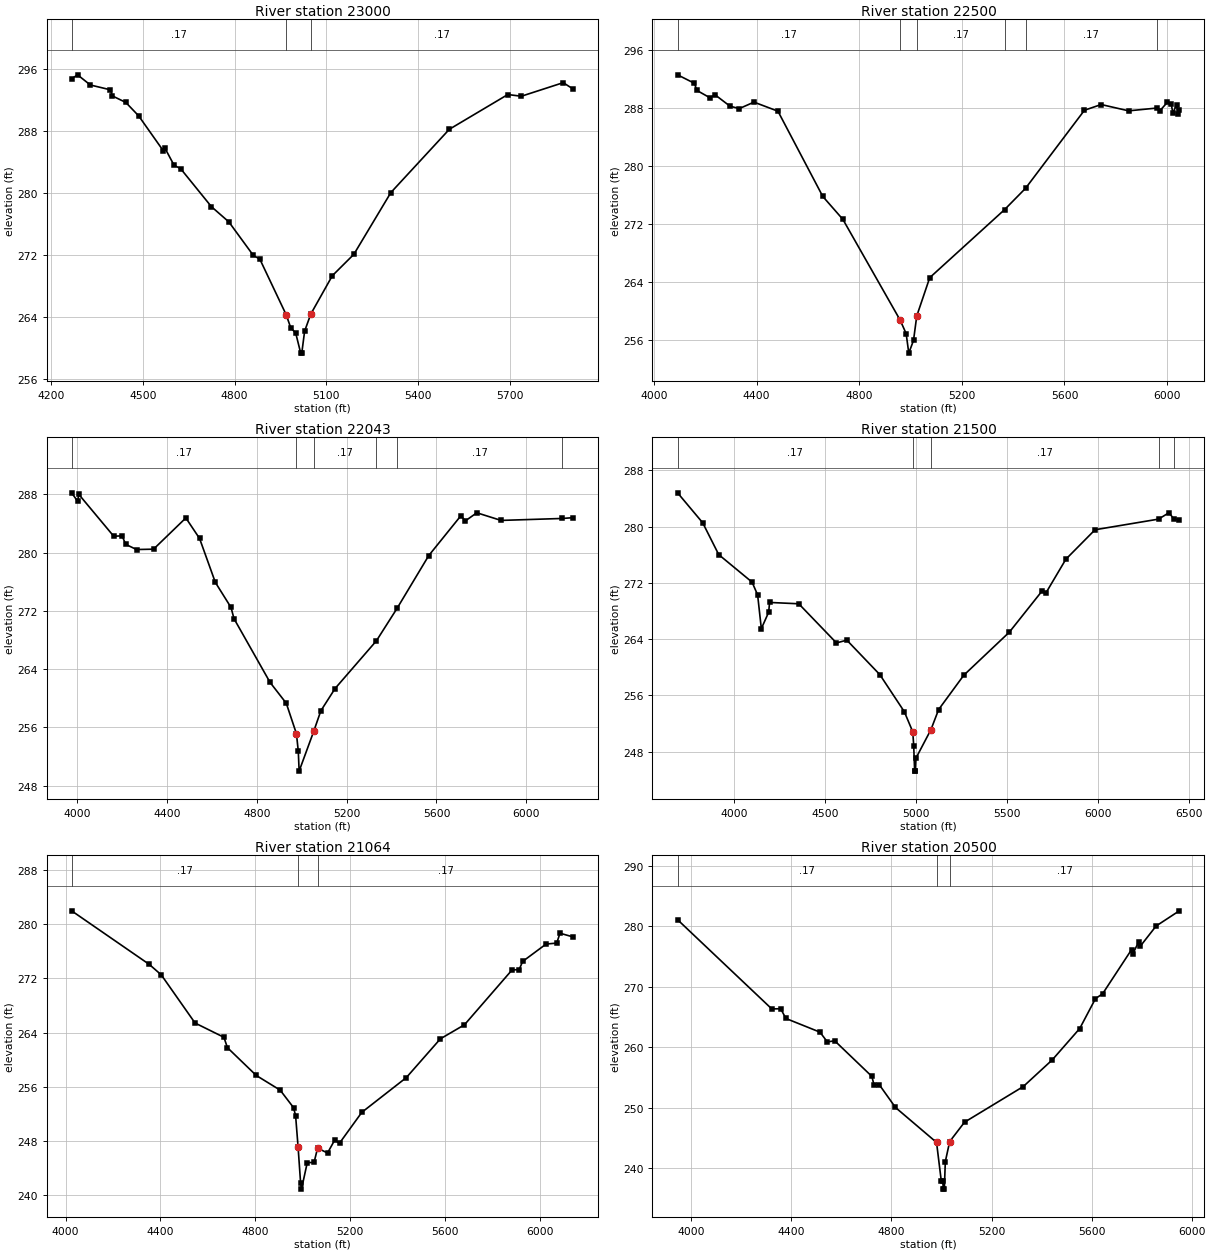
Type RM Length L Ch R = 1 ,23000   ,500,500,500
BEGIN DESCRIPTION:
Conroe Lake 077 46.0
END DESCRIPTION:
XS GIS Cut Line= 3
      3776627.05     10174108.35      3776026.79     10173688.54
        3775125.      10173586.9
#Sta/Elev= 30
  4267.5  294.71  4286.9  295.22  4328.7  293.91  4394.1  293.29  4400.8   292.5
  4444.7  291.66  4486.6  289.93  4566.8  285.45  4572.9  285.74  4602.6  283.55
  4623.5  283.14  4724.6  278.22  4781.3  276.27  4861.5  271.94  4882.5  271.48
  4968.8   264.3  4983.6  262.63    5000  261.93  5016.3  259.35  5019.8  259.35
  5029.1  262.18  5049.2  264.38  5119.7  269.33  5190.1  272.09  5310.9  280.04
  5502.1   288.2  5693.3  292.68  5737.5  292.46  5874.4  294.21  5907.5  293.37
#Mann= 3 , 0 , 0
  4267.5     .17       0  4968.8     .09       0  5049.2     .17       0
Bank Sta=4968.8,5049.2
XS Rating Curve= 0 ,0
Exp/Cntr=0.3,0.1

Type RM Length L Ch R = 1 ,22500   ,457,457,457
BEGIN DESCRIPTION:
Conroe Lake 077 45.0
END DESCRIPTION:
XS GIS Cut Line= 3
      3776735.95     10174035.65      3776237.44     10173276.85
      3775382.32     10172671.51
#Sta/Elev= 30
  4092.1  292.54  4157.9  291.37    4167   290.4  4217.2   289.4  4239.3  289.76
  4296.5  288.22  4332.7  287.89  4389.9  288.78  4483.3  287.53  4658.1  275.79
  4736.4  272.63  4959.4  258.77    4983   256.9  4993.3  254.21  5011.7  255.96
  5024.4  259.33  5074.9   264.6  5366.8  273.98  5448.6  276.92  5677.9  287.66
  5743.2  288.45  5850.2  287.58    5959  287.96  5972.1   287.6  6001.6  288.77
  6016.4  288.49  6022.5   287.3  6037.3  288.39  6043.4  287.19  6047.7  287.76
#Mann= 6 ,-1 , 0
  4092.1     .17       0  4959.4     .09       0  5024.4     .17       0
  5366.8     .11       0  5448.6     .17       0    5959     .11       0
Bank Sta=4959.4,5024.4
XS Rating Curve= 0 ,0
Exp/Cntr=0.3,0.1

Type RM Length L Ch R = 1 ,22043   ,543,543,543
BEGIN DESCRIPTION:
Conroe Lake 077 44.0
END DESCRIPTION:
XS GIS Cut Line= 3
      3776943.52     10173929.35      3776558.08     10172978.83
      3775412.99     10172588.16
#Sta/Elev= 30
  3974.3  288.21  4001.1  287.05  4006.4  287.99  4161.8  282.25  4199.1   282.3
  4215.4  281.13  4263.6  280.42  4339.3  280.47  4483.3  284.76  4544.4  281.94
  4614.6  275.91  4684.6  272.46  4697.7  270.93  4858.5  262.17  4930.8   259.3
    4976  255.12  4984.3  252.71    4988  249.98  5053.1  255.45  5084.8  258.27
  5148.2  261.33  5332.3  267.88  5424.2  272.33  5565.8   279.6  5708.2  285.04
  5729.3  284.37  5779.8  285.47  5887.8  284.42    6161  284.69  6209.9   284.8
#Mann= 6 ,-1 , 0
  3974.3     .17       0    4976     .09       0  5053.1     .17       0
  5332.3     .11       0  5424.2     .17       0    6161     .11       0
Bank Sta=4976,5053.1
XS Rating Curve= 0 ,0
Exp/Cntr=0.3,0.1

Type RM Length L Ch R = 1 ,21500   ,436,436,436
BEGIN DESCRIPTION:
Conroe Lake 077 43.0
END DESCRIPTION:
XS GIS Cut Line= 3
      3777128.71     10173873.48      3776880.12     10172585.65
      3775435.81     10172471.74
#Sta/Elev= 30
  3688.4  284.81  3826.6  280.55  3914.9  276.02  4098.2  272.11  4128.8  270.29
  4149.2  265.49  4189.5  267.83  4194.6  269.22  4355.2  269.03  4562.6  263.46
  4619.5  263.86    4801  258.96  4935.7  253.69  4982.4  250.82  4987.5  248.86
  4992.7  245.23  4996.2  245.23  4999.8  247.07  5082.5  251.14  5124.7  253.99
  5263.1  258.87  5513.9     265  5694.4  270.87  5714.5  270.55  5824.8  275.37
  5985.3  279.56  6334.5  281.07  6392.7  281.99  6420.2  281.02  6448.8  281.01
#Mann= 5 ,-1 , 0
  3688.4     .17       0  4982.4     .09       0  5082.5     .17       0
  6334.5     .11       0  6420.2     .17       0
Bank Sta=4982.4,5082.5
XS Rating Curve= 0 ,0
Exp/Cntr=0.3,0.1

Type RM Length L Ch R = 1 ,21064   ,564,564,564
BEGIN DESCRIPTION:
Conroe Lake 077 42.0
END DESCRIPTION:
XS GIS Cut Line= 3
       3777965.9     10172938.94      3777173.62     10172372.05
      3776231.31     10171729.04
#Sta/Elev= 30
  4025.8  281.99  4353.2  274.07  4403.6  272.53  4546.1  265.41  4667.8   263.3
  4682.5  261.77  4804.1  257.66  4904.9  255.49  4961.4   252.9    4970   251.7
 4980.55  247.03  4990.9  241.82  4994.8  240.86  5019.1  244.78  5047.7   244.8
  5062.6  246.92  5104.6   246.2  5134.4  248.09  5155.4  247.67  5249.1  252.21
  5436.6  257.34  5580.2  263.07  5681.8  265.15  5882.3  273.25  5912.2   273.3
  5927.1  274.51  6025.9  277.08  6070.7  277.22  6084.5  278.68  6140.8  278.12
#Mann= 3 , 0 , 0
  4025.8     .17       0 4980.55     .09       0  5062.6     .17       0
Bank Sta=4980.55,5062.6
XS Rating Curve= 0 ,0
Exp/Cntr=0.3,0.1

Type RM Length L Ch R = 1 ,20500   ,500,500,500
BEGIN DESCRIPTION:
Conroe Lake 077 41.0
END DESCRIPTION:
XS GIS Cut Line= 3
      3777983.26     10172891.18       3777366.7     10172034.98
      3776976.33     10171168.12
#Sta/Elev= 30
  3944.9  281.07  4321.5  266.33  4357.1  266.36    4378  264.75  4514.2  262.49
  4543.6  260.88  4573.1  261.06  4721.6  255.18  4730.2  253.78    4751  253.82
  4816.1  250.04  4980.2  244.27  4999.3  237.85  5004.7  237.85  5007.8  236.55
  5011.3  236.55  5015.3   241.1  5032.7  244.41    5092  247.61  5326.9   253.5
  5442.6   257.9  5552.6  263.09  5615.6  268.03  5644.2  268.84  5759.9  276.13
  5765.4  275.47  5788.6  277.45  5794.1  276.66    5858  280.03  5950.7  282.54
#Mann= 3 , 0 , 0
  3944.9     .17       0  4980.2     .09       0  5032.7     .17       0
#XS Ineff= 2 , 0
       0                    5092       0  247.61
Permanent Ineff=
       F       F
Bank Sta=4980.2,5032.7
XS Rating Curve= 0 ,0
Exp/Cntr=0.3,0.1

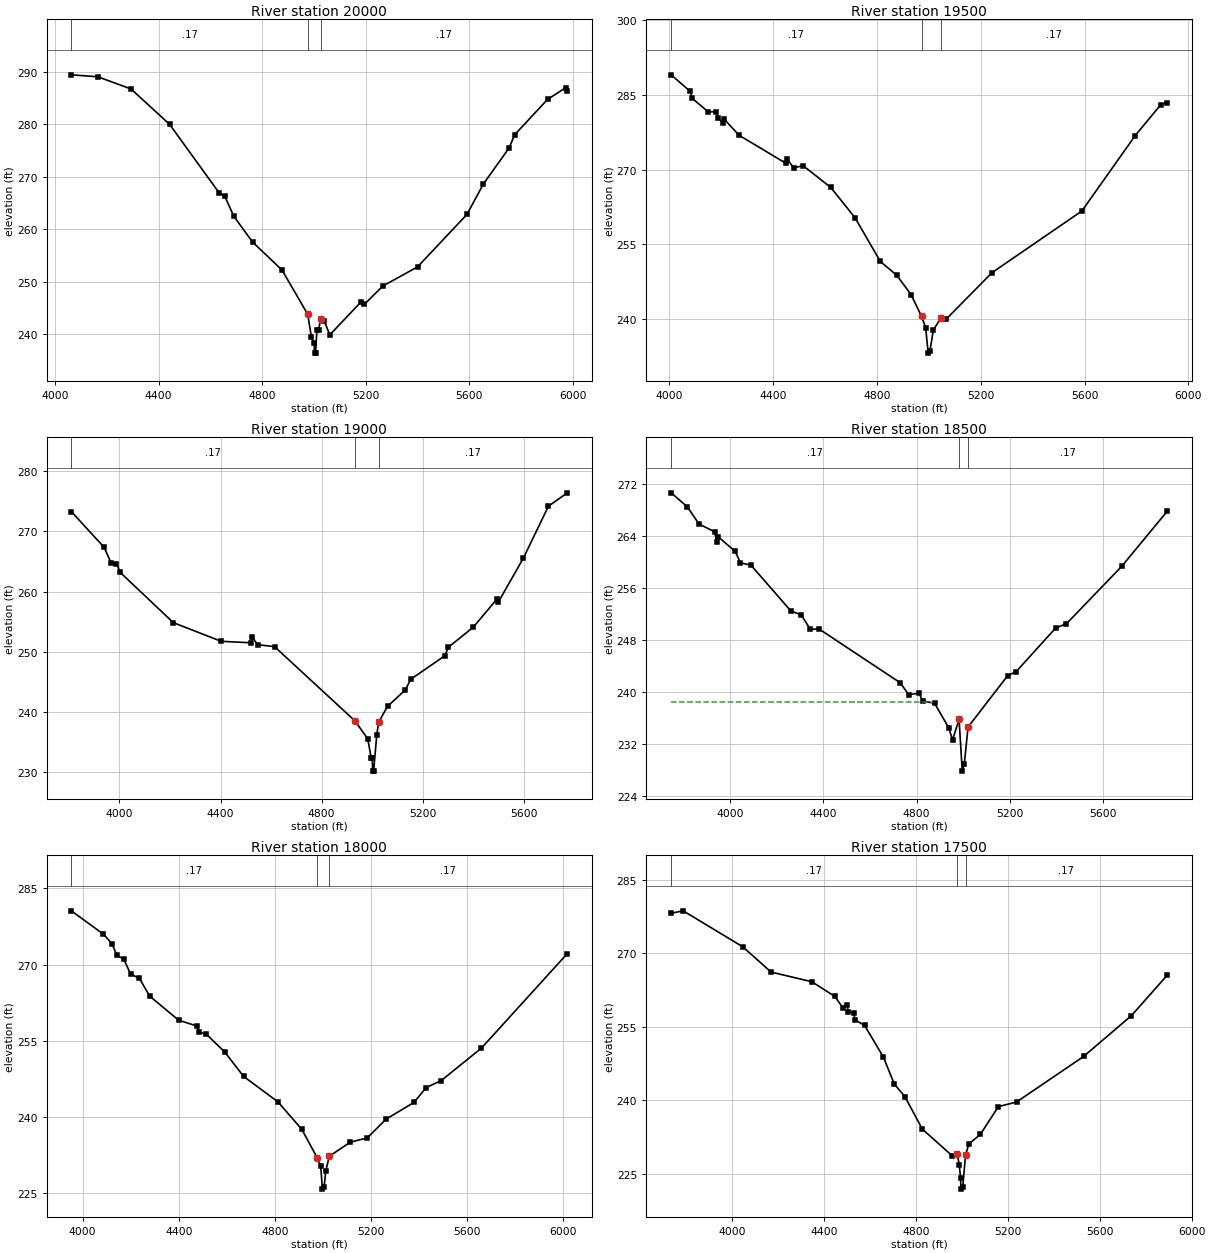
Type RM Length L Ch R = 1 ,20000   ,500,500,500
BEGIN DESCRIPTION:
Conroe Lake 077 40.0
END DESCRIPTION:
XS GIS Cut Line= 3
      3778308.83     10172583.08      3777728.31     10171847.06
      3777051.48     10171139.16
#Sta/Elev= 30
  4062.6  289.37  4164.9     289  4293.2  286.68  4442.3  279.94  4634.7  266.83
  4655.5  266.24  4690.7  262.42  4762.9  257.53  4876.8  252.19  4976.2  243.76
  4990.6  239.35    5000  238.38  5002.9  236.37  5006.4  236.37  5011.6  240.76
  5018.8  240.85  5025.7  242.85  5039.9  242.54  5061.3  239.84  5181.4  246.08
  5195.5  245.68  5266.3  249.14  5400.6   252.8  5591.5  262.79  5655.4  268.61
  5754.4  275.44  5775.5  277.93  5902.9  284.69  5973.6  286.93  5979.4  286.24
#Mann= 3 , 0 , 0
  4062.6     .17       0  4976.2     .09       0  5025.7     .17       0
#XS Ineff= 2 , 0
       0                  5266.3       0  249.14
Permanent Ineff=
       F       F
Bank Sta=4976.2,5025.7
XS Rating Curve= 0 ,0
Exp/Cntr=0.3,0.1

Type RM Length L Ch R = 1 ,19500   ,500,500,500
BEGIN DESCRIPTION:
Conroe Lake 077 39.0
END DESCRIPTION:
XS GIS Cut Line= 3
      3778360.88     10172530.96      3778028.63     10171594.45
       3777389.8     10170934.91
#Sta/Elev= 30
  4006.3     289  4080.5  285.66  4087.9  284.27  4149.7  281.56  4180.6  281.61
  4186.6  280.31  4206.1  279.37  4211.4  280.09  4267.9  276.89  4447.8  271.29
  4453.1   272.1  4478.6  270.37  4515.5  270.76  4621.6  266.42    4715  260.36
  4812.9  251.56  4876.3  248.79  4931.1  244.93  4971.7  240.57  4987.5  238.29
  4997.4  233.18  5004.2  233.68  5017.2  237.81  5045.5  240.17  5066.6  239.99
  5243.3  249.32  5589.8  261.69  5795.1   276.8  5894.1  283.02  5918.2  283.43
#Mann= 3 , 0 , 0
  4006.3     .17       0  4971.7     .09       0  5045.5     .17       0
Bank Sta=4971.7,5045.5
XS Rating Curve= 0 ,0
Exp/Cntr=0.3,0.1

Type RM Length L Ch R = 1 ,19000   ,500,500,500
BEGIN DESCRIPTION:
Conroe Lake 077 38.0
END DESCRIPTION:
XS GIS Cut Line= 3
      3778925.12     10172261.86      3778288.37     10171256.32
      3777727.57     10170725.76
#Sta/Elev= 30
  3809.8  273.27  3939.9  267.32    3967  264.75  3988.3  264.62  4003.5  263.16
  4213.2  254.84  4402.6  251.74  4519.7   251.5  4525.6  252.42  4546.8  251.18
  4613.7  250.86  4932.4  238.51  4982.5  235.56  4995.8  232.44    5000  232.44
  5002.2   230.2  5005.7   230.2  5018.1   236.2  5025.4   238.3  5060.6  240.94
  5131.4  243.69  5152.4  245.43  5287.1  249.34  5301.3  250.75    5400  254.09
  5492.2  258.68  5499.1  258.25  5598.2  265.55  5697.3  274.16    5772  276.38
#Mann= 3 , 0 , 0
  3809.8     .17       0  4932.4     .09       0  5025.4     .17       0
Bank Sta=4932.4,5025.4
XS Rating Curve= 0 ,0
Exp/Cntr=0.3,0.1

Type RM Length L Ch R = 1 ,18500   ,500,500,500
BEGIN DESCRIPTION:
Conroe Lake 077 37.0
END DESCRIPTION:
XS GIS Cut Line= 3
      3779235.88     10172105.61      3778663.99      10170991.3
      3778253.23     10170220.18
#Sta/Elev= 30
  3747.5  270.62  3817.1  268.47  3867.1  265.82  3933.7  264.63  3943.7  263.07
  3950.3  263.83  4022.5   261.6  4044.8  259.84  4089.8  259.49  4260.9  252.45
  4305.3  251.83  4344.1  249.64  4382.1  249.66  4730.5  241.38  4765.7  239.56
  4810.1  239.78  4826.7  238.57  4876.7  238.26  4937.6  234.47  4954.2  232.61
    4982  235.77  4995.6   227.8  5004.2  228.84  5020.5  234.58  5190.5   242.5
  5226.9  243.12  5396.8  249.85  5442.1  250.47  5678.7  259.29  5873.7  267.76
#Mann= 3 ,-1 , 0
  3747.5     .17       0    4982     .09       0  5020.5     .17       0
#XS Ineff= 2 , 0
       0  4865.4  238.41               0
Permanent Ineff=
       F       F
Bank Sta=4982,5020.5
XS Rating Curve= 0 ,0
Exp/Cntr=0.3,0.1

Type RM Length L Ch R = 1 ,18000   ,500,500,500
BEGIN DESCRIPTION:
Conroe Lake 077 36.0
END DESCRIPTION:
XS GIS Cut Line= 3
      3779638.68     10171636.89       3778990.4     10170814.98
      3778412.99     10169977.18
#Sta/Elev= 30
  3953.2  280.57  4086.7  275.97  4121.9  274.13  4142.8  271.83  4171.6  271.05
  4200.5  268.07  4235.8  267.34    4279   263.8  4399.3  259.06  4477.9  257.87
  4484.2  256.67  4513.1  256.38  4591.7  252.79  4670.3  247.98    4813  242.99
  4912.4  237.58  4976.5  231.97    4991  230.39  4998.2  225.81  5005.4  226.31
  5012.1  229.37  5026.9  232.28  5113.5  235.03  5185.2   235.9  5262.9  239.57
  5379.3  242.87  5429.8  245.78  5492.9  247.18  5659.9  253.55  6017.5  272.16
#Mann= 3 , 0 , 0
  3953.2     .17       0  4976.5     .09       0  5026.9     .17       0
#XS Ineff= 2 , 0
       0                  5155.4       0  235.53
Permanent Ineff=
       F       F
Bank Sta=4976.5,5026.9
XS Rating Curve= 0 ,0
Exp/Cntr=0.3,0.1

Type RM Length L Ch R = 1 ,17500   ,500,500,500
BEGIN DESCRIPTION:
Conroe Lake 077 35.0
END DESCRIPTION:
XS GIS Cut Line= 3
      3779721.99     10171567.41      3779230.07     10170403.27
      3778680.35      10169699.4
#Sta/Elev= 30
  3736.2  278.22  3788.6  278.71  4047.4  271.38  4171.3   266.2  4348.1  264.24
  4448.3  261.23  4482.9  258.93  4501.1  259.55  4506.6  258.12  4530.3  257.91
  4535.7  256.45  4577.7  255.32  4659.6  248.82    4707  243.33  4752.7  240.79
  4828.7  234.14    4959  228.68  4980.7  229.07  4989.5  226.79  4994.9   224.2
  4996.7  221.89  5004.6  222.39  5016.8  228.91  5031.2   231.1    5081  233.07
  5159.7  238.74  5238.3  239.67  5530.5  248.99  5737.6   257.3  5893.1  265.53
#Mann= 3 , 0 , 0
  3736.2     .17       0  4980.7     .09       0  5016.8     .17       0
Bank Sta=4980.7,5016.8
XS Rating Curve= 0 ,0
Exp/Cntr=0.3,0.1

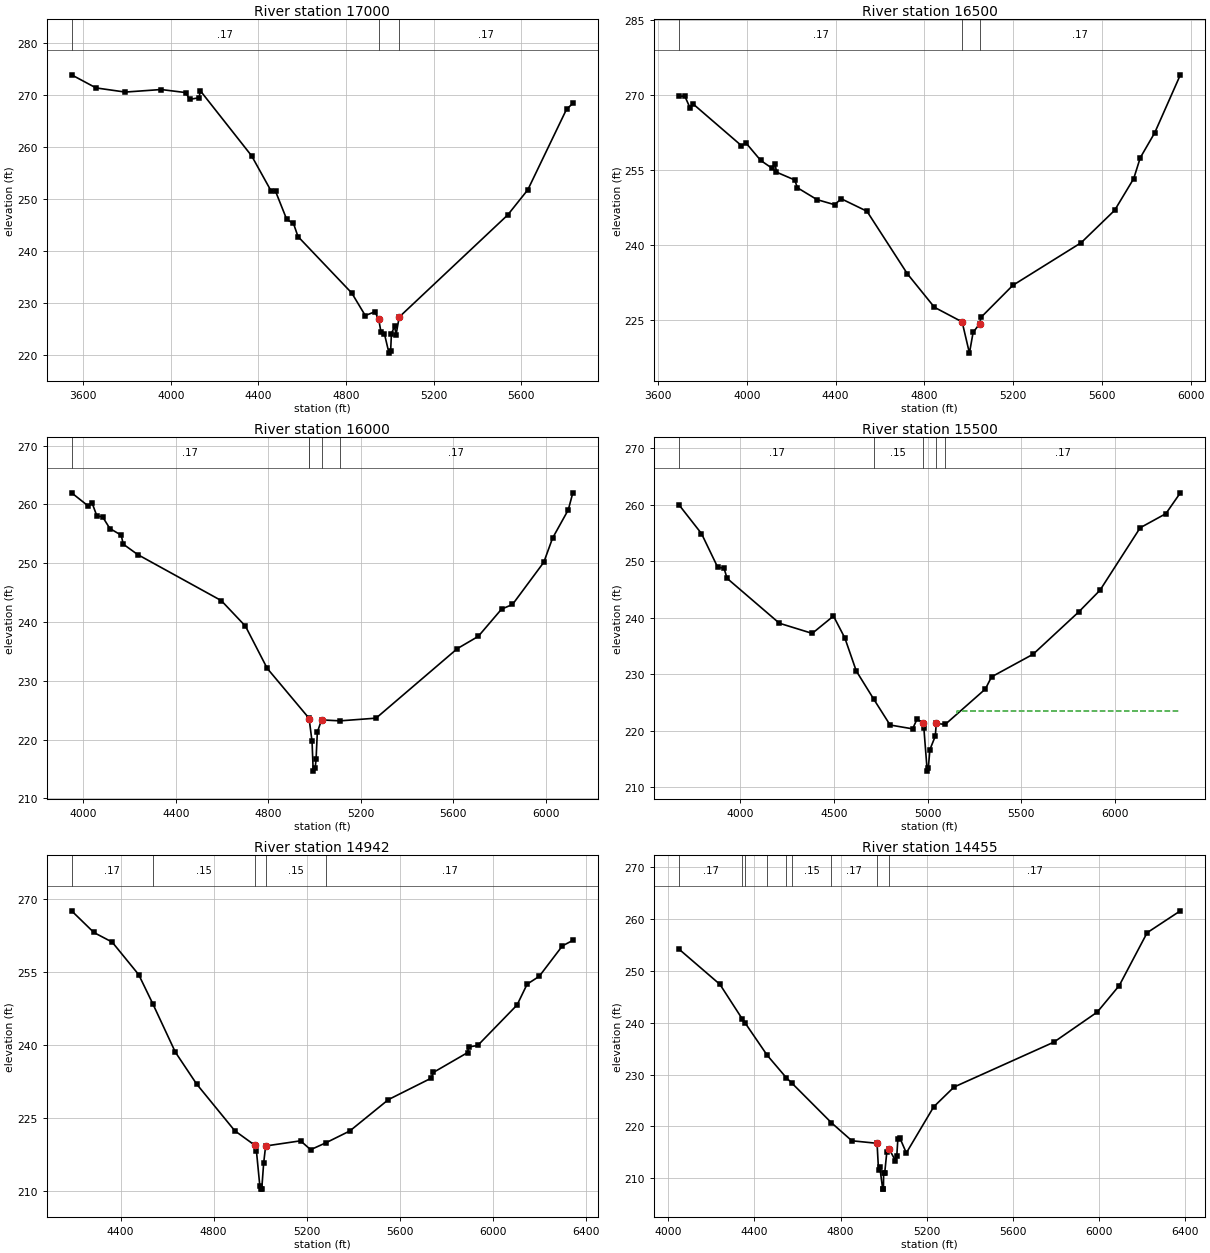
Type RM Length L Ch R = 1 ,17000   ,500,500,500
BEGIN DESCRIPTION:
Conroe Lake 077 34.0
END DESCRIPTION:
XS GIS Cut Line= 3
      3779798.39     10171550.09      3779487.56     10170131.24
      3778902.67     10169536.29
#Sta/Elev= 30
  3547.5  273.85  3659.1  271.33  3792.2  270.53    3956  271.02  4068.6  270.43
  4085.7  269.12  4129.5  269.44  4134.6   270.8  4369.2  258.24  4456.9  251.56
  4478.1  251.43  4529.3     246    4560  245.24  4580.4  242.72  4826.1  231.83
  4887.6   227.5  4931.1  228.23    4949   226.8  4959.2  224.31  4974.9     224
  4995.8  220.27  5003.4  220.77    5007  224.04  5021.1  225.41  5028.3  223.84
  5042.3  227.21  5537.3  246.86  5629.3  251.72    5806  267.22  5834.3  268.33
#Mann= 3 , 0 , 0
  3547.5     .17       0    4949     .09       0  5042.3     .17       0
Bank Sta=4949,5042.3
XS Rating Curve= 0 ,0
Exp/Cntr=0.3,0.1

Type RM Length L Ch R = 1 ,16500   ,500,500,500
BEGIN DESCRIPTION:
Conroe Lake 077 33.0
END DESCRIPTION:
XS GIS Cut Line= 3
      3780492.81     10170931.98      3779799.17     10169826.71
      3779024.06     10169272.27
#Sta/Elev= 30
  3695.1  269.68  3719.8  269.79  3743.4  267.46  3756.3  268.24  3975.4  259.87
  3996.6  260.37  4062.2  256.92  4112.1   255.4  4127.4  256.22  4133.3  254.58
  4215.6  253.02  4227.6  251.47  4315.9   249.1  4394.9  248.09  4425.5  249.26
  4540.9  246.78  4723.3  234.28  4844.9  227.62  4969.8   224.7  5002.7  218.47
  5019.2   222.6  5048.7  224.33  5054.8  225.61  5198.3     232  5505.7  240.49
  5656.8  246.96  5742.8  253.29  5772.3  257.45  5837.4  262.43    5953     274
#Mann= 3 , 0 , 0
  3695.1     .17       0  4969.8     .09       0  5048.7     .17       0
Bank Sta=4969.8,5048.7
XS Rating Curve= 0 ,0
Exp/Cntr=0.3,0.1

Type RM Length L Ch R = 1 ,16000   ,500,500,500
BEGIN DESCRIPTION:
Conroe Lake 077 32.0
END DESCRIPTION:
XS GIS Cut Line= 3
      3780555.31     10170584.74      3780218.46     10169589.08
      3779187.26     10169157.69
#Sta/Elev= 30
  3948.9  261.97  4020.2  259.75  4037.2  260.28  4058.3  258.04  4083.1  257.88
  4114.5   255.9  4163.9  254.76  4172.1  253.25    4235  251.47  4596.7  243.64
  4701.2   239.3  4795.6  232.11  4974.2  223.74  4976.8  223.58  4989.5  219.69
  4994.6  214.64    5003  215.14  5006.9  216.62  5012.4  221.26  5030.7  223.35
  5110.5  223.19  5266.6  223.65  5618.5  235.48    5709  237.56  5809.6  242.19
    5857  242.98  5992.5  250.16  6030.4  254.26  6098.5  259.08  6117.8  261.92
#Mann= 5 ,-1 , 0
  3948.9     .17       0  4974.2     .15       0  4976.8     .09       0
  5030.7     .15       0  5110.5     .17       0
Bank Sta=4976.8,5030.7
XS Rating Curve= 0 ,0
Exp/Cntr=0.3,0.1

Type RM Length L Ch R = 1 ,15500   ,558,558,558
BEGIN DESCRIPTION:
Conroe Lake 077 31.0
END DESCRIPTION:
XS GIS Cut Line= 3
      3780742.83     10170553.53      3780519.69     10169245.12
      3779197.67      10168970.2
#Sta/Elev= 30
  3672.7  259.96  3791.7  254.92  3878.1  248.97    3912  248.78  3928.8  246.98
  4207.8  239.04  4383.3  237.24  4496.9  240.31  4557.8  236.42  4618.6  230.59
  4712.6  225.56  4799.4  221.01  4919.8  220.33  4943.2  222.04  4973.7  221.43
    4980  220.41  4997.8  212.84  5003.5  213.34  5012.1  216.65    5041  219.05
  5046.1  221.29  5093.8  221.11  5308.3  227.38  5341.6  229.54  5563.6  233.55
  5808.8  241.09  5921.1  244.89  6135.6  255.95  6272.9  258.45  6350.3  262.14
#Mann= 5 ,-1 , 0
  3672.7     .17       0  4712.6     .15       0  4973.7     .09       0
  5046.1     .15       0  5093.8     .17       0
#XS Ineff= 2 , 0
       0                  5155.1       0  223.45
Permanent Ineff=
       F       F
Bank Sta=4973.7,5046.1
XS Rating Curve= 0 ,0
Exp/Cntr=0.3,0.1

Type RM Length L Ch R = 1 ,14942   ,487,487,487
BEGIN DESCRIPTION:
Conroe Lake 077 30.0
END DESCRIPTION:
XS GIS Cut Line= 3
      3781579.62      10169643.8      3780941.63     10169144.59
      3779671.67     10168711.41
#Sta/Elev= 30
  4189.9   267.6  4285.5  263.15  4364.1  261.18  4478.1  254.49  4538.2  248.55
  4635.4  238.58  4726.8  232.03  4890.5  222.44  4977.2  219.44  4983.6  218.27
    4998  211.18  5002.9  210.45  5006.4  210.45  5014.6   215.8  5023.1  219.31
    5173  220.37  5216.4  218.55    5283  219.99  5384.4  222.39  5550.5  228.84
    5733  233.21  5743.8  234.43    5890  238.48  5895.2  239.65  5933.8  239.95
  6102.8  248.27  6145.9  252.54  6197.9  254.15  6297.3   260.4  6341.8  261.52
#Mann= 5 ,-1 , 0
  4189.9     .17       0  4538.2     .15       0  4977.2     .09       0
  5023.1     .15       0    5283     .17       0
Bank Sta=4977.2,5023.1
XS Rating Curve= 0 ,0
Exp/Cntr=0.3,0.1

Type RM Length L Ch R = 1 ,14455   ,438,438,438
BEGIN DESCRIPTION:
Conroe Lake 077 29.0
END DESCRIPTION:
XS GIS Cut Line= 3
      3781856.68     10169342.14      3781061.97      10168823.3
      3779694.78     10168662.49
#Sta/Elev= 30
    4051  254.16  4239.9   247.4  4344.5  240.67  4357.1  239.94  4459.5  233.71
  4548.1  229.38  4574.5  228.32  4757.1  220.71  4852.2  217.22  4969.2  216.73
  4975.9  211.62  4981.9  212.14  4995.3  207.89  4998.8  207.89  4999.6  211.04
  5004.7  211.04  5014.3     215  5024.4  215.72  5054.6  213.35  5060.8  214.35
  5065.8  217.64  5074.7   217.8  5104.9  214.87    5232  223.77  5326.4  227.59
  5789.6  236.25    5991  242.05    6093  247.16  6222.6  257.37  6376.7  261.59
#Mann= 9 ,-1 , 0
    4051     .17       0  4344.5     .15       0  4357.1     .17       0
  4459.5     .15       0  4548.1     .17       0  4574.5     .15       0
  4757.1     .17       0  4969.2     .09       0  5024.4     .17       0
Bank Sta=4969.2,5024.4
XS Rating Curve= 0 ,0
Exp/Cntr=0.3,0.1

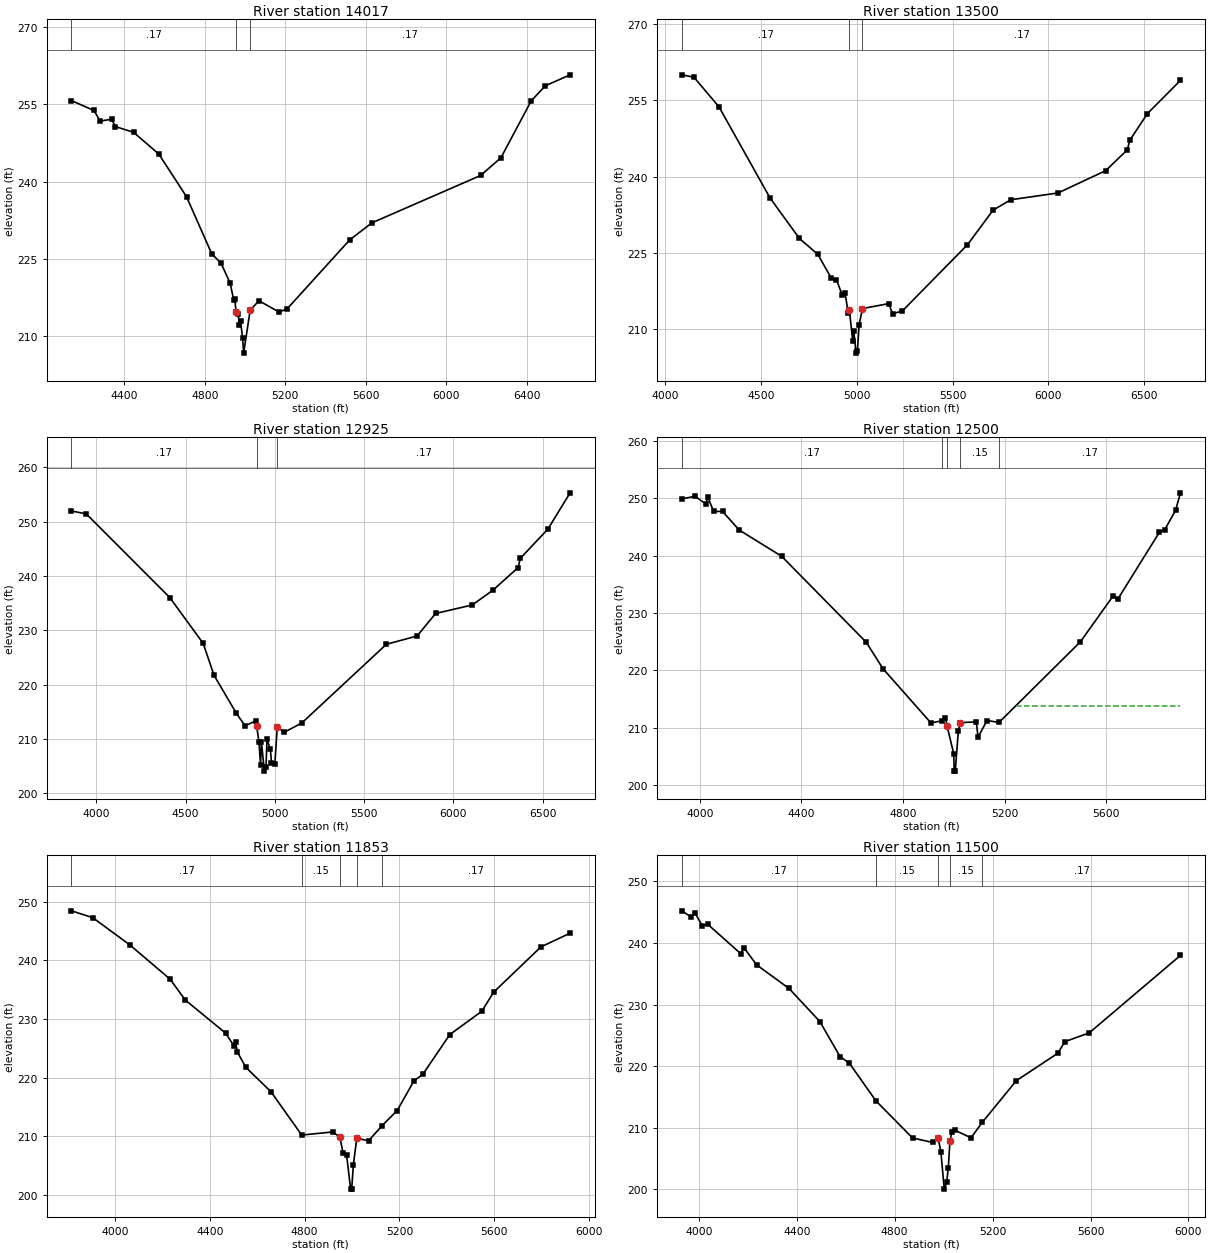
Type RM Length L Ch R = 1 ,14017   ,517,517,517
BEGIN DESCRIPTION:
Conroe Lake 077 28.0
END DESCRIPTION:
XS GIS Cut Line= 3
       3782088.8     10168878.19      3781306.76     10168514.43
      3779694.83     10168613.97
#Sta/Elev= 30
  4137.5  255.75  4248.8  253.84  4280.6  251.77  4337.4  252.14  4354.8  250.72
  4446.3  249.59  4571.7  245.36  4709.1  237.09  4834.5  225.99  4880.3   224.2
    4926  220.27  4943.4  217.08  4948.9  217.31  4954.7  214.75  4965.7  214.34
  4971.8  212.17  4977.3  212.91  4987.8  209.66  4992.9  206.71  5025.3  215.05
    5069  216.88  5169.2  214.69  5209.3  215.32  5519.9   228.7  5630.1  232.01
  6171.1  241.23  6271.3  244.66  6421.6   255.7  6491.8  258.63    6615  260.76
#Mann= 3 , 0 , 0
  4137.5     .17       0  4954.7     .09       0  5025.3     .17       0
Bank Sta=4954.7,5025.3
XS Rating Curve= 0 ,0
Exp/Cntr=0.3,0.1

Type RM Length L Ch R = 1 ,13500   ,575,575,575
BEGIN DESCRIPTION:
Conroe Lake 077 27.0
END DESCRIPTION:
XS GIS Cut Line= 3
      3782183.16     10168581.64       3781360.3     10168188.87
      3779716.71     10168576.15
#Sta/Elev= 30
  4088.2  260.01  4151.3  259.54  4281.9  253.71  4548.4  235.76  4701.3  227.81
  4797.6  224.68  4865.7  220.12  4893.9  219.73  4925.1  216.65  4939.3  217.02
  4956.5  213.13    4962  213.79  4979.1  207.67  4984.7  209.69  4996.8  205.25
  5003.8  205.75  5012.8  210.79  5029.8  214.02  5167.1  214.99  5187.4  212.99
  5238.8  213.57  5577.8  226.58  5711.4  233.39  5803.9  235.43  6050.4  236.77
    6299  241.17    6410   245.2    6426  247.23  6515.9  252.37  6688.6  258.92
#Mann= 3 , 0 , 0
  4088.2     .17       0    4962     .09       0  5029.8     .17       0
#XS Ineff= 2 , 0
       0  4939.3  217.02               0
Permanent Ineff=
       F       F
Bank Sta=4962,5029.8
XS Rating Curve= 0 ,0
Exp/Cntr=0.3,0.1

Type RM Length L Ch R = 1 ,12925   ,425,425,425
BEGIN DESCRIPTION:
Conroe Lake 077 26.0
END DESCRIPTION:
XS GIS Cut Line= 3
      3782285.59     10168206.89      3781214.42     10167819.99
      3779714.56      10168516.5
#Sta/Elev= 30
  3861.1  251.94  3943.8  251.41  4411.6  236.02  4598.5   227.6  4659.9  221.69
  4783.7  214.78  4833.2  212.42  4894.6  213.36 4898.44  212.32  4911.3  209.45
  4919.9  205.16  4925.2  209.38  4941.4  204.09  4950.6  204.78  4955.9  209.97
  4975.1  208.09  4981.2  205.62    5000  205.38  5013.6  212.24  5051.3  211.22
  5150.6  212.93  5624.7  227.42  5796.8  228.95  5900.3  233.09  6105.4  234.65
  6219.9  237.33  6362.8  241.54  6374.4  243.22  6528.6  248.58  6653.7  255.28
#Mann= 3 , 0 , 0
  3861.1     .17       0 4898.44     .09       0  5013.6     .17       0
Bank Sta=4898.44,5013.6
XS Rating Curve= 0 ,0
Exp/Cntr=0.3,0.1

Type RM Length L Ch R = 1 ,12500   ,647,647,647
BEGIN DESCRIPTION:
Conroe Lake 077 25.0
END DESCRIPTION:
XS GIS Cut Line= 3
      3782334.05     10168155.64      3781425.64     10167588.54
      3780792.46     10166959.11
#Sta/Elev= 30
  3929.1   249.9  3981.3  250.36  4023.8     249  4030.7  250.27  4054.3  247.72
  4089.7  247.71  4154.7  244.48  4322.2  239.89  4655.5  224.89  4720.9   220.3
  4909.6  210.85  4955.6   211.2  4967.4  211.73  4973.8  210.22    5000  205.42
  5001.6  202.42  5005.9  202.42  5017.9  209.38  5024.9  210.88  5088.6  211.01
  5095.6  208.35    5131  211.25  5178.1  210.91  5498.7  224.98    5626  232.88
  5647.2  232.51  5809.8  244.08    5831  244.54  5873.4   247.9  5892.8  250.96
#Mann= 5 ,-1 , 0
  3929.1     .17       0  4955.6     .15       0  4973.8     .09       0
  5024.9     .15       0  5178.1     .17       0
#XS Ineff= 2 , 0
       0                  5244.1       0  213.86
Permanent Ineff=
       F       F
Bank Sta=4973.8,5024.9
XS Rating Curve= 0 ,0
Exp/Cntr=0.3,0.1

Type RM Length L Ch R = 1 ,11853   ,353,353,353
BEGIN DESCRIPTION:
Conroe Lake 077 24.0
END DESCRIPTION:
XS GIS Cut Line= 3
      3782369.12     10168107.11      3781588.22      10167218.2
      3781026.55     10166489.55
#Sta/Elev= 30
  3816.8  248.45  3906.7  247.28  4063.2  242.63  4233.1  236.78  4296.7  233.24
  4466.5  227.61  4502.6  225.39  4509.2     226  4516.8  224.35  4551.9  221.77
  4658.2   217.6    4788  210.21  4920.1  210.75  4948.6  209.81  4962.8   207.1
    4977  206.88  4994.3  200.99  4998.7  200.99  5005.7  205.13  5020.2  209.65
  5070.1  209.24  5126.9  211.82  5190.5  214.38  5261.5  219.46  5298.4  220.55
  5412.5  227.35  5547.5  231.32  5597.3  234.57  5796.6  242.29    5920  244.64
#Mann= 5 ,-1 , 0
  3816.8     .17       0    4788     .15       0  4948.6     .09       0
  5020.2     .15       0  5126.9     .17       0
Bank Sta=4948.6,5020.2
XS Rating Curve= 0 ,0
Exp/Cntr=0.3,0.1

Type RM Length L Ch R = 1 ,11500   ,500,500,500
BEGIN DESCRIPTION:
Conroe Lake 077 23.0
END DESCRIPTION:
XS GIS Cut Line= 3
      3782377.25     10168004.73      3781874.93     10167060.98
      3781261.97     10166312.69
#Sta/Elev= 30
  3930.9  245.22    3969  244.22  3984.4  244.89  4014.3  242.79    4037  243.02
  4170.8  238.28  4184.3  239.24  4236.7  236.43  4368.6  232.61  4494.7  227.23
  4576.9  221.54  4614.7  220.49  4723.5  214.35  4873.2  208.32  4954.6   207.6
  4977.2  208.39  4988.7  206.12  5002.6  200.01  5012.7  201.23  5019.2  203.49
  5025.7  207.79  5033.5  209.29  5047.9  209.55  5111.8  208.35  5158.6  210.89
  5296.9  217.63  5466.3  222.08    5495  223.97  5594.5  225.39  5967.3  237.98
#Mann= 5 ,-1 , 0
  3930.9     .17       0  4723.5     .15       0  4977.2     .09       0
  5025.7     .15       0  5158.6     .17       0
Bank Sta=4977.2,5025.7
XS Rating Curve= 0 ,0
Exp/Cntr=0.3,0.1

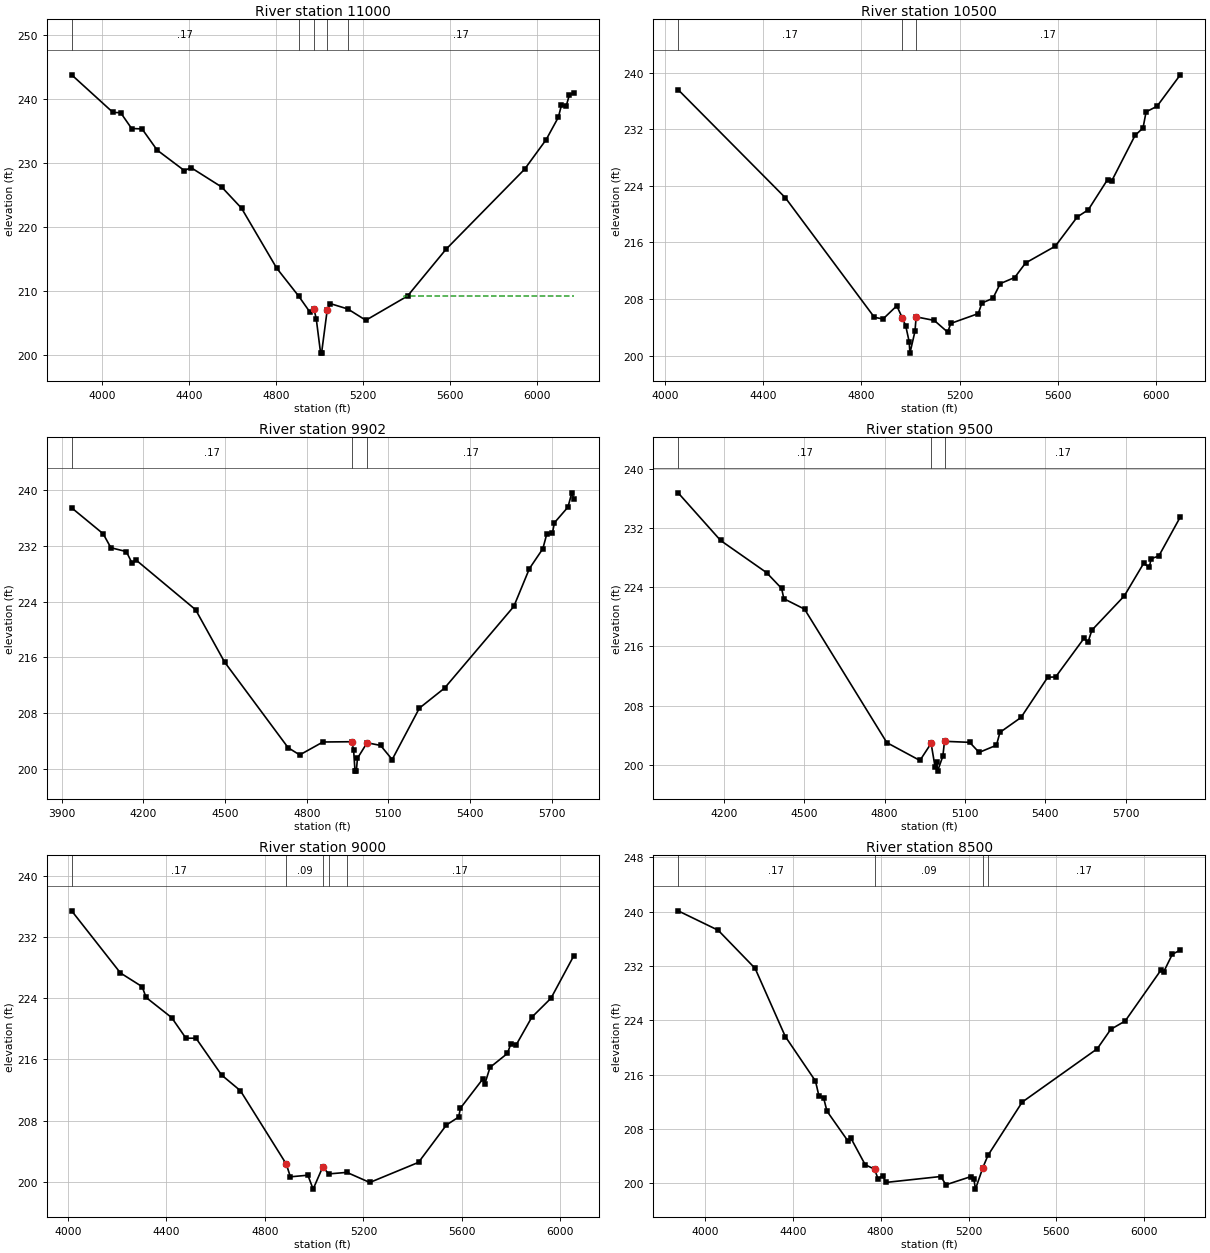
Type RM Length L Ch R = 1 ,11000   ,500,500,500
BEGIN DESCRIPTION:
Conroe Lake 077 22.0
END DESCRIPTION:
XS GIS Cut Line= 3
      3782460.81     10167993.96      3782293.17     10166866.15
      3781412.49     10166096.34
#Sta/Elev= 30
  3859.8  243.75  4049.8  237.88  4085.1  237.84  4135.7  235.37  4183.6  235.31
    4253     232  4378.3   228.8  4408.6  229.27  4550.2  226.23  4641.2  222.93
    4803  213.57  4903.8  209.22  4954.6  206.77  4974.8  207.13  4984.9  205.66
  5004.9  200.31  5009.3  200.31  5035.4  207.07  5049.6  208.04  5130.1   207.2
  5212.9  205.44  5404.6  209.22  5581.2   216.5  5942.8     229  6042.5  233.64
  6098.5  237.13  6112.7  239.02  6134.5  238.87  6148.8  240.58  6169.7  240.91
#Mann= 5 ,-1 , 0
  3859.8     .17       0  4903.8     .15       0  4974.8     .09       0
  5035.4     .15       0  5130.1     .17       0
#XS Ineff= 2 , 0
       0                  5390.4       0  209.28
Permanent Ineff=
       F       F
Bank Sta=4974.8,5035.4
XS Rating Curve= 0 ,0
Exp/Cntr=0.3,0.1

Type RM Length L Ch R = 1 ,10500   ,598,598,598
BEGIN DESCRIPTION:
Conroe Lake 077 21.0
END DESCRIPTION:
XS GIS Cut Line= 3
      3783245.31     10167069.21      3782514.23     10166466.81
       3781533.4     10165969.28
#Sta/Elev= 30
  4052.7  237.59    4490   222.3  4852.8   205.4  4888.1  205.17  4944.1  207.03
  4966.3  205.34  4980.6  204.18  4994.4  201.98  4997.7  200.34  5018.2  203.42
 5022.99  205.47  5096.9  204.96  5151.8   203.3  5164.1  204.54  5276.3  205.93
    5291  207.43  5335.6  208.08    5366  210.17  5424.6  211.03  5469.2  213.09
  5590.2  215.46  5679.9   219.6  5724.8  220.61  5803.3  224.88  5819.8  224.66
  5915.4  231.13  5947.8  232.17  5960.3  234.45  6005.1  235.25  6099.8  239.69
#Mann= 3 , 0 , 0
  4052.7     .17       0  4966.3     .09       0 5022.99     .17       0
Bank Sta=4966.3,5022.99
XS Rating Curve= 0 ,0
Exp/Cntr=0.3,0.1

Type RM Length L Ch R = 1 ,9902    ,402,402,402
BEGIN DESCRIPTION:
Conroe Lake 077 20.0
END DESCRIPTION:
XS GIS Cut Line= 3
      3783552.64     10166840.06      3782764.76     10166125.27
       3782258.6     10165529.84
#Sta/Elev= 30
  3936.2  237.41  4051.9   233.7  4080.3   231.7    4137  231.15  4158.7  229.46
  4172.2  229.96  4391.8  222.82  4497.9  215.35  4731.7  203.07  4774.3  202.04
  4859.5  203.89  4965.6  203.93  4972.3  202.71  4977.4  199.72  4982.1  199.72
  4986.5  201.57  5021.8  203.78  5071.2   203.4    5114  201.38    5214  208.74
  5306.3   211.6    5561   223.3  5618.2  228.71  5667.6  231.56  5681.9  233.64
  5702.7  233.83  5710.4  235.29  5759.8  237.51  5774.1  239.56  5781.5  238.67
#Mann= 3 ,-1 , 0
  3936.2     .17       0  4965.6     .09       0  5021.8     .17       0
Bank Sta=4965.6,5021.8
XS Rating Curve= 0 ,0
Exp/Cntr=0.3,0.1

Type RM Length L Ch R = 1 ,9500    ,500,500,500
BEGIN DESCRIPTION:
Conroe Lake 077 19.0
END DESCRIPTION:
XS GIS Cut Line= 3
      3783638.93     10166780.77      3783066.26       10165996.
      3782525.52     10165271.06
#Sta/Elev= 30
  4028.5  236.75  4187.2  230.31  4358.7  225.97  4415.1  223.83  4423.5  222.44
  4500.8  221.03  4808.2  202.99  4931.8  200.58  4973.5  202.89  4988.2  199.73
  4994.4  200.34  4997.6  199.14  5017.4  201.16  5023.6  203.17  5117.5  203.03
  5152.9  201.67  5217.6  202.64  5230.7  204.38  5309.3  206.39  5409.4  211.84
  5438.6  211.86  5544.9   217.1  5559.5  216.55  5574.1  218.19    5695  222.81
  5767.2   227.2  5788.8   226.7  5795.1  227.84  5824.3  228.22  5904.4  233.49
#Mann= 3 , 0 , 0
  4028.5     .17       0  4973.5     .09       0  5023.6     .17       0
Bank Sta=4973.5,5023.6
XS Rating Curve= 0 ,0
Exp/Cntr=0.3,0.1

Type RM Length L Ch R = 1 ,9000    ,500,500,500
BEGIN DESCRIPTION:
Conroe Lake 077 18.0
END DESCRIPTION:
XS GIS Cut Line= 3
      3783730.57     10166734.91      3783445.08     10165793.23
      3782679.17     10165068.85
#Sta/Elev= 30
    4016  235.44  4214.1  227.31  4302.1  225.52  4318.1  224.11    4422  221.47
  4479.8  218.78  4520.7  218.78  4624.7  213.96    4701  211.91  4887.3  202.31
  4903.6  200.65  4974.7  200.86  4996.1  199.04  5035.1  201.94  5059.3  201.03
    5133  201.23    5226  199.91  5423.8  202.54  5537.1  207.43  5586.9  208.47
  5593.7  209.62  5685.6  213.48  5692.8  212.78  5713.9  214.96  5784.7  216.79
  5798.8  218.08  5820.3  217.91  5883.8  221.53  5961.5  224.01  6054.2  229.57
#Mann= 5 ,-1 , 0
    4016     .17       0  4887.3     .09       0  5035.1     .17       0
  5059.3     .15       0    5133     .17       0
Bank Sta=4887.3,5035.1
XS Rating Curve= 0 ,0
Exp/Cntr=0.3,0.1

Type RM Length L Ch R = 1 ,8500    ,500,500,500
BEGIN DESCRIPTION:
Conroe Lake 077 17.0
END DESCRIPTION:
XS GIS Cut Line= 3
      3784418.06     10166581.29      3783832.34     10165625.01
      3783358.54     10164562.02
#Sta/Elev= 30
  3878.6  240.14  4060.8  237.28    4229  231.66  4366.4  221.62  4503.7  215.06
  4519.2  212.89  4540.5  212.61  4555.9  210.63  4650.7  206.26  4664.5  206.67
    4730  202.73  4772.6  202.08  4788.1  200.67  4809.3  201.12  4824.8  200.13
    5074     201  5097.2  199.78  5212.3     201  5224.3  200.64  5231.7  199.14
  5265.3  202.31  5288.5  204.11  5444.3  211.96  5785.9  219.82  5847.3  222.68
    5913  223.91  6075.7  231.41  6088.2  231.15  6127.6  233.75  6163.8  234.35
#Mann= 4 ,-1 , 0
  3878.6     .17       0  4772.6     .09       0  5265.3     .15       0
  5288.5     .17       0
Bank Sta=4772.6,5265.3
XS Rating Curve= 0 ,0
Exp/Cntr=0.3,0.1