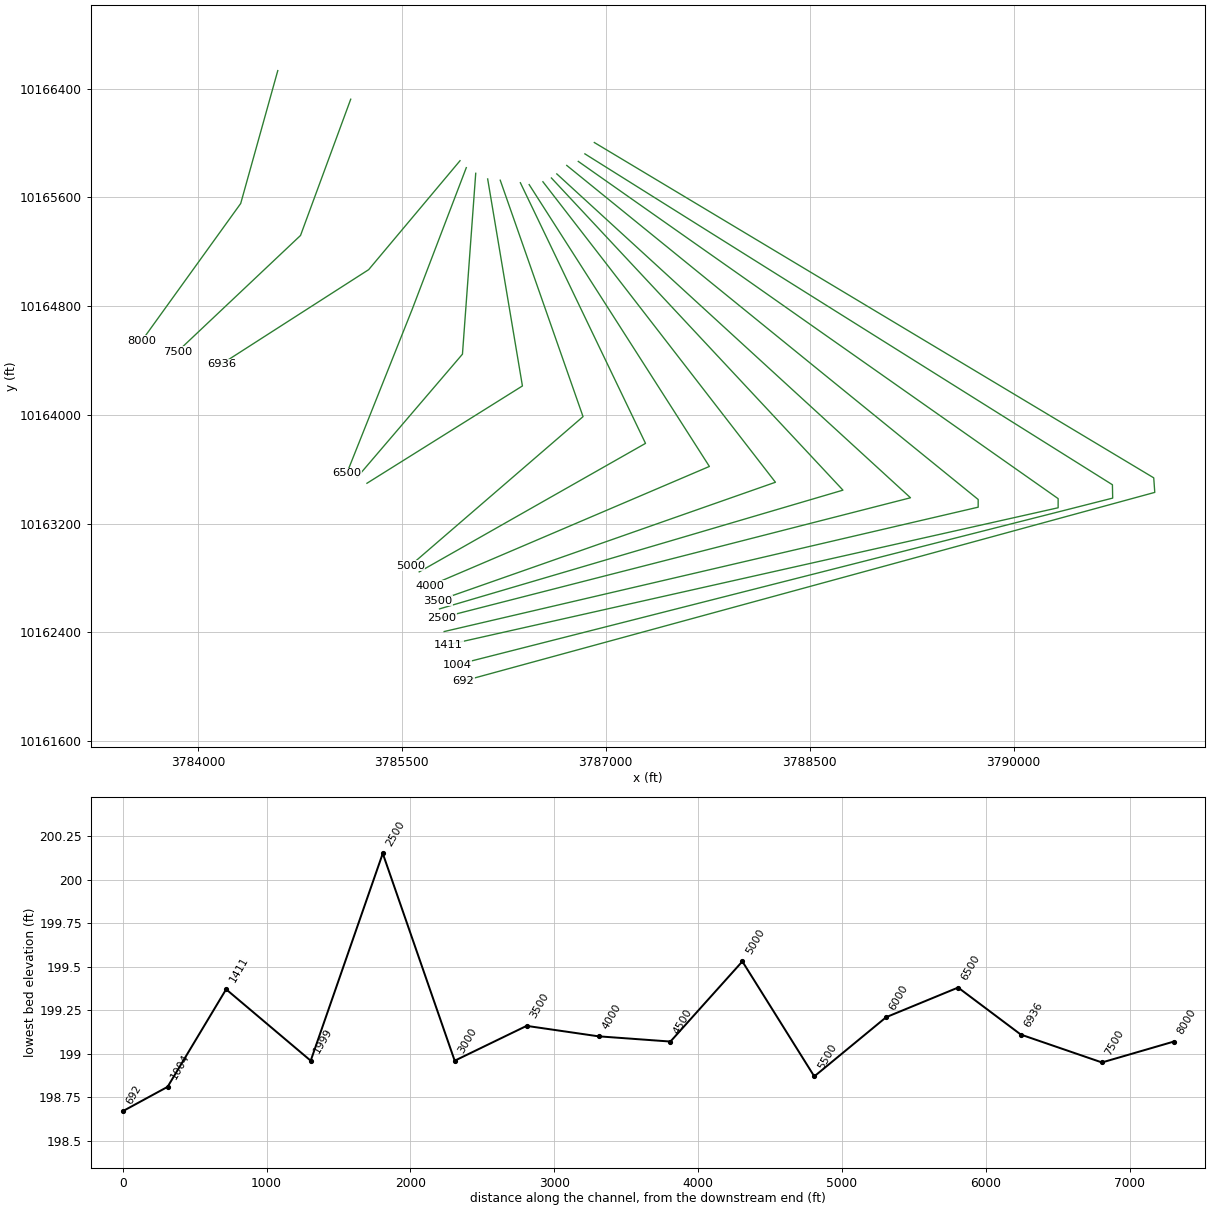
HEC-RAS study Conroe Lake 077.prj: Conroe Lake 077 Base Level Engineering

--- Conroe Lake 077.g01 (geometry) --- (continued)

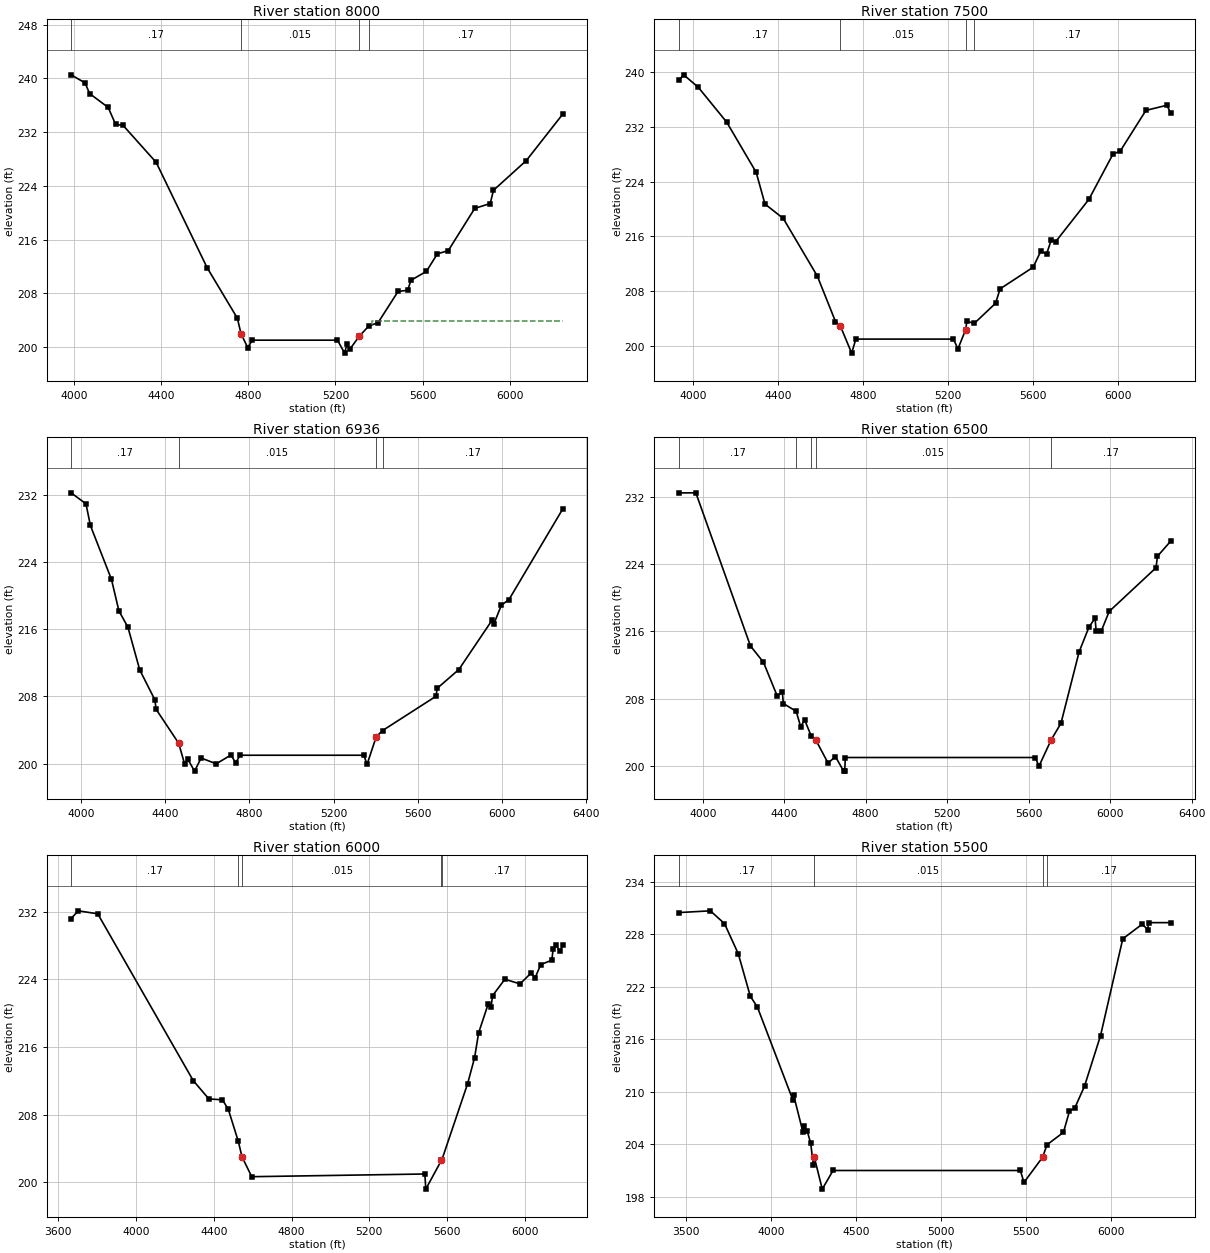
Type RM Length L Ch R = 1 ,8000    ,500,500,500
BEGIN DESCRIPTION:
Conroe Lake 077 16.0
END DESCRIPTION:
XS GIS Cut Line= 3
      3784587.88     10166532.76      3784315.16      10165555.5
      3783587.77     10164545.95
#Sta/Elev= 30
  3985.4  240.54  4049.4  239.34  4070.2  237.75  4155.7  235.68  4189.9  233.14
    4224  233.01  4376.3  227.49  4610.1  211.81  4749.2  204.27  4765.8  201.98
    4797  199.87  4817.5     201    5209     201  5242.1  199.07    5252  200.37
  5265.5  199.63  5309.6   201.6  5353.4  203.12  5395.5   203.6  5487.6  208.27
  5531.8  208.43  5546.5  209.92  5617.7  211.25    5668  213.86  5718.3  214.35
  5839.8  220.64    5911  221.36  5925.7  223.33  6076.6  227.76  6244.3  234.69
#Mann= 4 ,-1 , 0
  3985.4     .17       0  4765.8    .015       0  5309.6     .11       0
  5353.4     .17       0
#XS Ineff= 2 , 0
       0                  5366.1       0  203.92
Permanent Ineff=
       F       F
Bank Sta=4765.8,5309.6
XS Rating Curve= 0 ,0
Exp/Cntr=0.3,0.1

Type RM Length L Ch R = 1 ,7500    ,564,564,564
BEGIN DESCRIPTION:
Conroe Lake 077 15.0
END DESCRIPTION:
XS GIS Cut Line= 3
      3785124.36     10166322.43      3784755.21     10165320.36
      3783849.79     10164465.53
#Sta/Elev= 30
  3932.1  238.81  3954.9  239.61  4023.7  237.78  4157.3  232.69  4295.9  225.36
  4337.3  220.73  4423.3  218.63  4583.6   210.2  4668.9  203.57  4692.1   202.9
    4745  198.95  4764.8     201    5224     201  5245.1  199.57  5280.7  202.33
  5287.5  203.59  5322.2   203.3  5422.3  206.24  5443.3  208.34    5599   211.5
  5634.2   213.8  5662.6  213.47    5684  215.47    5705  215.24  5860.8   221.4
  5973.7  227.98  6009.3   228.5  6129.4  234.41  6228.5  235.17  6245.2  234.03
#Mann= 4 ,-1 , 0
  3932.1     .17       0  4692.1    .015       0  5280.7     .11       0
  5322.2     .17       0
#XS Ineff= 2 , 0
       0                  5287.5       0  203.59
Permanent Ineff=
       F       F
Bank Sta=4692.1,5280.7
XS Rating Curve= 0 ,0
Exp/Cntr=0.3,0.1

Type RM Length L Ch R = 1 ,6936    ,436,436,436
BEGIN DESCRIPTION:
Conroe Lake 077 14.0
END DESCRIPTION:
XS GIS Cut Line= 3
      3785928.28     10165869.99      3785256.43     10165068.81
       3784172.8     10164373.36
#Sta/Elev= 30
  3954.4   232.2  4024.9  230.89  4045.8  228.32  4145.9   221.9  4181.1  218.17
    4224  216.22  4279.9  211.15  4351.5   207.6    4358  206.45  4464.7  202.43
  4493.3  199.93  4507.6  200.55  4540.1  199.11  4571.4  200.67  4642.9  199.98
  4713.2  201.03  4735.3  200.09  4756.1     201  5343.6     201  5358.8  199.91
  5402.3   203.2  5432.2  203.93  5685.8  208.01  5691.8  208.96  5794.4  211.19
  5952.1  217.06  5960.8  216.63  5996.4  218.85  6032.1   219.5  6287.6  230.29
#Mann= 4 ,-1 , 0
  3954.4     .17       0  4464.7    .015       0  5402.3     .11       0
  5432.2     .17       0
Bank Sta=4464.7,5402.3
XS Rating Curve= 0 ,0
Exp/Cntr=0.3,0.1

Type RM Length L Ch R = 1 ,6500    ,500,500,500
BEGIN DESCRIPTION:
Conroe Lake 077 13.0
END DESCRIPTION:
XS GIS Cut Line= 3
       3785974.5     10165819.07      3785575.98     10164775.58
      3785095.85     10163571.58
#Sta/Elev= 30
    3883  232.46  3966.4  232.47  4234.1  214.28  4298.3  212.32    4366   208.3
  4390.7  208.76  4396.1  207.42  4458.8  206.49  4480.9  204.67  4500.3  205.47
  4533.2  203.52  4555.1  203.09  4615.2  200.34  4651.6   201.1  4691.8  199.38
    4697  199.38  4700.1     201    5632     201  5650.8  199.98  5710.2  203.09
  5758.5  205.07  5847.7  213.57  5896.2  216.52  5925.8  217.56  5931.2  216.05
  5955.5  215.99  5995.3  218.37    6225  223.56  6232.2  224.93  6296.2   226.7
#Mann= 5 ,-1 , 0
    3883     .17       0  4458.8     .15       0  4533.2     .11       0
  4555.1    .015       0  5710.2     .17       0
Bank Sta=4555.1,5710.2
XS Rating Curve= 0 ,0
Exp/Cntr=0.3,0.1

Type RM Length L Ch R = 1 ,6000    ,500,500,500
BEGIN DESCRIPTION:
Conroe Lake 077 12.0
END DESCRIPTION:
XS GIS Cut Line= 3
      3786043.88      10165777.5      3785946.26     10164447.18
      3785169.82     10163539.19
#Sta/Elev= 30
  3666.1  231.21  3702.6  232.12  3802.9  231.77  4294.2  212.04  4374.4  209.88
  4444.6  209.77  4474.7  208.63  4525.9  204.86  4544.9  203.03    4595  200.68
  5485.3     201  5490.2  199.21  5570.9  202.63    5572  202.62  5705.4  211.69
  5741.1  214.75  5761.9  217.69  5811.3  221.12  5825.6  220.71  5833.3  222.08
  5896.9  224.03  5974.9  223.48    6032  224.77  6052.8  224.22  6081.4  225.77
  6138.4  226.28    6145   227.6  6159.3  228.03  6180.1  227.38  6194.7  228.03
#Mann= 5 ,-1 , 0
  3666.1     .17       0  4525.9     .15       0  4544.9    .015       0
  5570.9     .11       0    5572     .17       0
Bank Sta=4544.9,5570.9
XS Rating Curve= 0 ,0
Exp/Cntr=0.3,0.1

Type RM Length L Ch R = 1 ,5500    ,500,500,500
BEGIN DESCRIPTION:
Conroe Lake 077 11.0
END DESCRIPTION:
XS GIS Cut Line= 3
      3786131.74     10165735.87      3786387.36     10164213.38
      3785243.81     10163497.58
#Sta/Elev= 30
  3456.2  230.49  3641.3  230.69  3724.7  229.23  3805.8  225.78  3876.8  220.91
  3917.4  219.73  4126.2  209.11  4131.3  209.63  4186.8  205.35  4191.9  206.09
  4211.4  205.51  4231.7  204.14  4247.5  201.64  4252.5  202.57  4299.9  198.87
  4363.5     201  5465.4     201    5487  199.64  5596.6  202.52  5622.1  203.94
  5719.1  205.36  5754.6  207.79  5785.2  208.12    5843  210.64  5937.3  216.42
  6068.2  227.49  6183.7  229.18  6214.3  228.53  6220.2  229.34  6349.1  229.34
#Mann= 4 ,-1 , 0
  3456.2     .17       0  4252.5    .015       0  5596.6     .11       0
  5622.1     .17       0
Bank Sta=4252.5,5596.6
XS Rating Curve= 0 ,0
Exp/Cntr=0.3,0.1

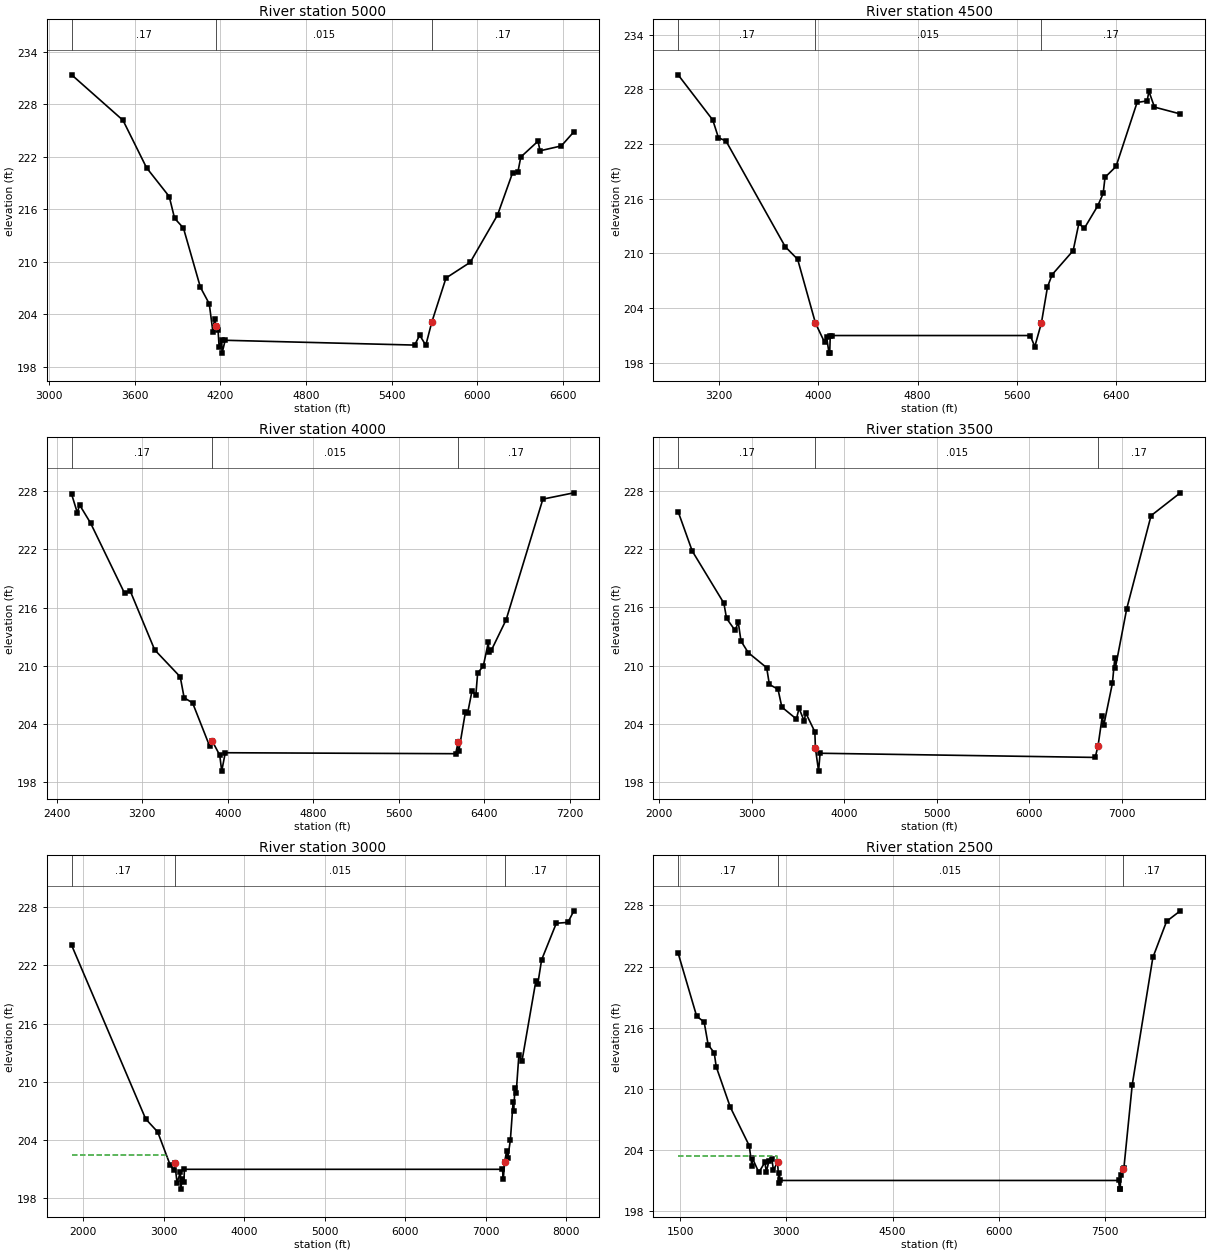
Type RM Length L Ch R = 1 ,5000    ,500,500,500
BEGIN DESCRIPTION:
Conroe Lake 077 10.0
END DESCRIPTION:
XS GIS Cut Line= 3
      3786224.23     10165726.63      3786833.26     10163987.69
      3785562.94      10162891.8
#Sta/Elev= 30
  3157.5  231.36  3517.4  226.16  3682.6  220.73  3841.5  217.44    3879  214.95
    3941  213.84  4059.8  207.07  4121.9  205.18  4147.6  201.98  4159.4  203.47
    4170  202.63  4183.9  202.14  4191.2  200.24  4209.6     201  4212.1  199.53
  4233.5     201  5561.8  200.45  5597.2  201.58    5640  200.43  5681.7  203.06
  5781.5  208.12  5951.5  209.92  6142.9  215.33  6248.9  220.18    6285   220.2
  6305.9  221.96  6426.6  223.77  6440.8  222.67    6590  223.23  6677.7  224.84
#Mann= 3 , 0 , 0
  3157.5     .17       0    4170    .015       0  5681.7     .17       0
#XS Ineff= 2 , 0
       0  4159.4  203.47               0
Permanent Ineff=
       F       F
Bank Sta=4170,5681.7
XS Rating Curve= 0 ,0
Exp/Cntr=0.3,0.1

Type RM Length L Ch R = 1 ,4500    ,500,500,500
BEGIN DESCRIPTION:
Conroe Lake 077 9.0
END DESCRIPTION:
XS GIS Cut Line= 3
      3786372.23      10165708.1       3787292.8     10163790.96
      3785628.11     10162845.79
#Sta/Elev= 30
  2873.3  229.59  3152.4  224.63  3197.7  222.69  3258.3  222.34  3735.3  210.74
  3835.1  209.36  3978.7  202.35  4052.2  200.25  4068.1  200.86  4087.4  199.07
  4093.1  199.07  4097.5  200.99  4112.4     201  5707.2     201  5743.2  199.78
  5796.6  202.38  5845.6  206.33  5883.1  207.68  6052.1  210.31    6098  213.29
  6141.2  212.74  6249.4  215.21  6293.6  216.58  6308.5  218.35  6397.1  219.54
  6566.6  226.56  6647.4  226.73  6661.6  227.78  6706.5  226.05  6914.3   225.3
#Mann= 3 , 0 , 0
  2873.3     .17       0  3978.7    .015       0  5796.6     .17       0
Bank Sta=3978.7,5796.6
XS Rating Curve= 0 ,0
Exp/Cntr=0.3,0.1

Type RM Length L Ch R = 1 ,4000    ,500,500,500
BEGIN DESCRIPTION:
Conroe Lake 077 8.0
END DESCRIPTION:
XS GIS Cut Line= 3
      3786436.97     10165694.23       3787762.6     10163621.25
      3785704.77     10162743.02
#Sta/Elev= 30
  2539.4   227.7    2592  225.81  2614.4  226.59  2716.3  224.73  3034.3  217.48
  3085.9  217.75    3316  211.63  3555.3  208.84  3591.7  206.68  3670.8  206.15
  3831.1  201.66  3852.2  202.25  3924.9  200.75  3943.2   199.1  3976.5     201
  6132.3   200.9  6155.9  202.16  6161.4  201.18  6222.9   205.2  6244.6  205.14
  6284.8  207.39  6320.7  206.96  6337.5  209.24  6390.2  209.94  6437.4   212.4
  6442.8  211.45  6466.4   211.6  6603.4  214.72  6947.7   227.2  7237.4  227.85
#Mann= 3 , 0 , 0
  2539.4     .17       0  3852.2    .015       0  6155.9     .17       0
Bank Sta=3852.2,6155.9
XS Rating Curve= 0 ,0
Exp/Cntr=0.3,0.1

Type RM Length L Ch R = 1 ,3500    ,500,500,500
BEGIN DESCRIPTION:
Conroe Lake 077 7.0
END DESCRIPTION:
XS GIS Cut Line= 3
      3786538.13     10165715.26      3788248.42       10163505.
      3785761.58     10162632.35
#Sta/Elev= 30
  2205.3  225.87    2358  221.81  2700.3  216.44    2729  214.88  2820.7  213.65
    2856  214.47    2885  212.55  2963.8  211.35    3163   209.8    3192  208.08
  3285.3  207.59  3326.9  205.75  3484.5  204.52  3512.9  205.63  3569.6  204.29
  3584.1  205.17  3683.7  203.21    3690  201.51  3724.2  199.16  3740.5     201
  6715.2  200.57  6746.2  201.77  6791.6  204.79  6808.2  203.89  6901.2   208.2
  6926.9  210.78  6932.2  209.73  7056.6  215.89  7319.2  225.45  7635.5   227.8
#Mann= 3 , 0 , 0
  2205.3     .17       0    3690    .015       0  6746.2     .17       0
Bank Sta=3690,6746.2
XS Rating Curve= 0 ,0
Exp/Cntr=0.3,0.1

Type RM Length L Ch R = 1 ,3000    ,500,500,500
BEGIN DESCRIPTION:
Conroe Lake 077 6.0
END DESCRIPTION:
XS GIS Cut Line= 3
       3786600.6     10165743.06      3788745.03     10163446.91
      3785777.69     10162573.53
#Sta/Elev= 30
  1858.2  224.06  2777.7  206.18  2926.2  204.85  3081.5  201.44  3131.4  200.88
  3138.2  201.68  3166.5  199.63    3209   200.7  3212.9  198.96    3230  199.99
  3251.5  199.66  3258.4     201    7207     201  7217.4  199.96  7233.6  201.73
  7259.1  202.91  7272.2  202.12  7305.5  204.04  7338.9  207.89  7344.1  206.98
  7363.3  209.35  7377.4  208.88  7410.8  212.76  7449.3  212.15  7621.3  220.37
  7644.8  220.05  7693.2  222.57  7875.5  226.33  8020.1  226.42  8093.2  227.61
#Mann= 3 , 0 , 0
  1858.2     .17       0  3138.2    .015       0  7233.6     .17       0
#XS Ineff= 2 , 0
       0  3046.4  202.45  7259.1       0  202.91
Permanent Ineff=
       F       F
Bank Sta=3138.2,7233.6
XS Rating Curve= 0 ,0
Exp/Cntr=0.3,0.1

Type RM Length L Ch R = 1 ,2500    ,501,501,501
BEGIN DESCRIPTION:
Conroe Lake 077 5.0
END DESCRIPTION:
XS GIS Cut Line= 3
      3786640.34     10165772.98      3789241.88     10163390.86
      3785792.55     10162508.88
#Sta/Elev= 30
  1472.6  223.32  1734.1  217.13  1840.2  216.55  1896.9  214.31    1982  213.54
  2010.4  212.16  2208.3  208.21  2477.2   204.4  2512.9  202.46  2519.7  203.21
  2611.6  201.79  2696.7  202.78  2717.7  201.87  2753.4  202.87    2796   203.1
  2816.9  202.04 2876.86  202.77  2894.6  200.77    2902   201.7  2908.8     201
  7688.3     201  7704.3  200.15  7712.7  200.15  7718.8  201.55  7749.7  202.11
  7764.8  202.27  7882.1  210.41    8173  222.89  8366.8  226.44  8560.3  227.47
#Mann= 3 , 0 , 0
  1472.6     .17       0 2876.86    .015       0  7749.7     .17       0
#XS Ineff= 2 , 0
       0  2873.7  203.42               0
Permanent Ineff=
       F       F
Bank Sta=2876.86,7749.7
XS Rating Curve= 0 ,0
Exp/Cntr=0.3,0.1

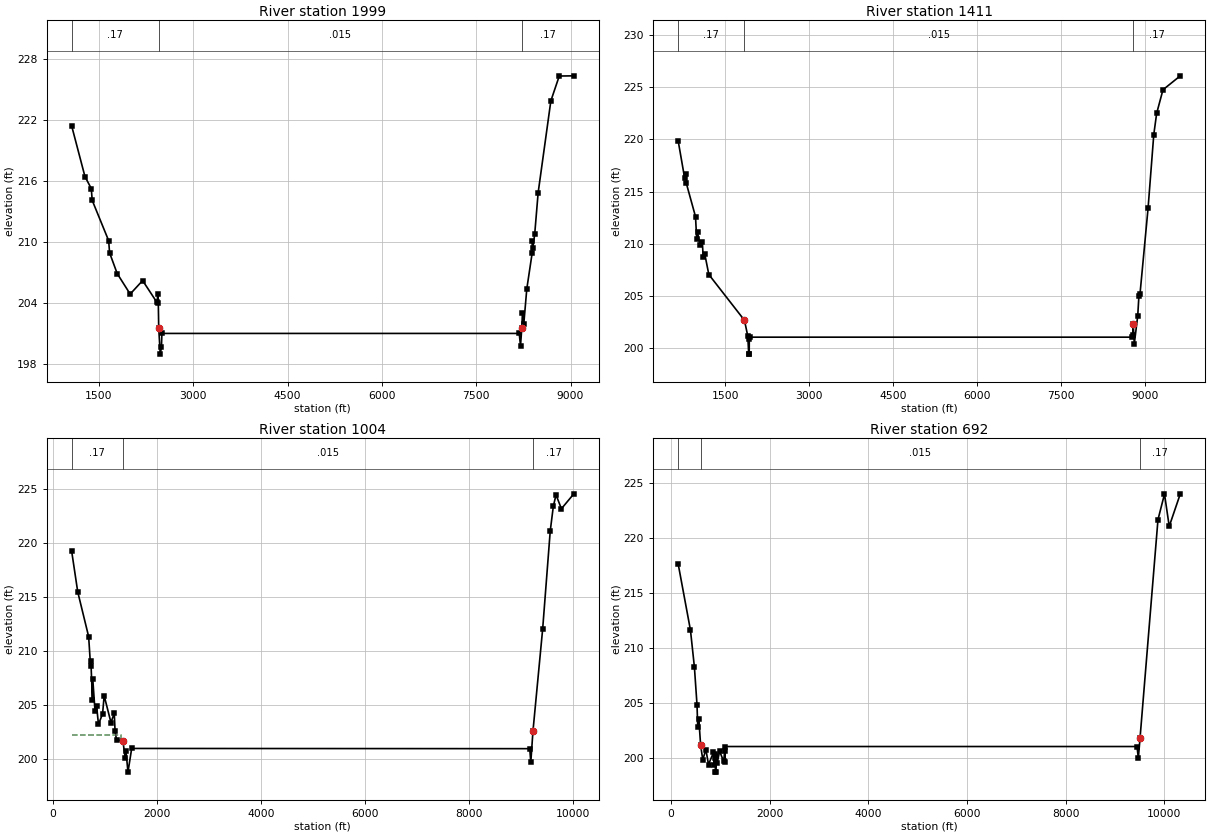
Type RM Length L Ch R = 1 ,1999    ,588,588,588
BEGIN DESCRIPTION:
Conroe Lake 077 4.0
END DESCRIPTION:
XS GIS Cut Line= 4
      3786713.47     10165835.41      3789739.75      10163378.1
      3789739.75     10163321.68       3785811.8     10162406.84
#Sta/Elev= 30
    1065  221.46  1276.7  216.46  1377.3  215.28  1391.7  214.12  1653.8  210.14
  1668.2  208.95  1789.6   206.9  1995.8  204.88    2194  206.21  2422.5  204.05
  2436.1  204.89  2443.3  203.98  2449.8  201.55  2474.3  198.96  2492.9  199.63
  2500.5     201  8184.1     201  8204.6  199.79  8225.2  201.54  8235.4  203.05
    8256  201.89  8304.5  205.39  8389.5  208.91  8394.8  210.12  8399.9   209.4
  8430.5   210.8    8485  214.87  8687.2  223.92  8820.7  226.37  9052.8  226.39
#Mann= 3 , 0 , 0
    1065     .17       0  2449.8    .015       0  8225.2     .17       0
#XS Ineff= 2 , 0
       0                  8235.4       0  203.05
Permanent Ineff=
       F       F
Bank Sta=2449.8,8225.2
XS Rating Curve= 0 ,0
Exp/Cntr=0.3,0.1

Type RM Length L Ch R = 1 ,1411    ,407,407,407
BEGIN DESCRIPTION:
Conroe Lake 077 3.0
END DESCRIPTION:
XS GIS Cut Line= 4
      3786798.35     10165864.91      3790327.86     10163384.61
      3790327.86     10163317.34      3785845.44      10162311.1
#Sta/Elev= 30
   656.3   219.9   773.9  216.26   794.8  216.71   802.4   215.8   967.4  212.58
   988.3   210.4  1003.1  211.08  1046.8  209.86  1089.3  210.15  1104.1  208.72
  1132.4  208.99  1205.2  207.02  1842.2  202.62  1901.4   201.1    1918  199.37
  1926.6  199.37  1928.4  200.85  1937.1     201    8768     201  8785.2  201.19
  8790.3  202.29    8809  200.36  8870.5  203.05    8891  204.91  8911.5  205.18
    9055  213.38  9157.5  220.48  9208.7  222.51  9321.5  224.78  9631.4  226.12
#Mann= 3 , 0 , 0
   656.3     .17       0  1842.2    .015       0  8790.3     .17       0
#XS Ineff= 2 , 0
       0  1842.2  202.62  8790.3       0  202.29
Permanent Ineff=
       F       F
Bank Sta=1842.2,8790.3
XS Rating Curve= 0 ,0
Exp/Cntr=0.3,0.1

Type RM Length L Ch R = 1 ,1004    ,312,312,312
BEGIN DESCRIPTION:
Conroe Lake 077 2.0
END DESCRIPTION:
XS GIS Cut Line= 4
        3786847.     10165920.43      3790727.16     10163486.61
      3790729.12     10163388.43      3785906.23     10162163.54
#Sta/Elev= 30
     357  219.25   474.1  215.48   683.9  211.34   720.4  208.61   726.3  209.12
   756.9  205.47   762.8  207.44   806.6  204.42   835.9  204.96   872.4  203.23
   951.4   204.2     982  205.88  1112.8   203.4  1176.4  204.27  1191.7  202.57
  1219.7  201.81  1343.7  201.65  1386.2  200.15  1401.5  200.74  1439.7  198.81
  1511.1     201  9163.8  200.98    9184  199.71    9225  202.57  9411.4  212.01
  9557.7  221.11  9617.8  223.42  9669.3  224.45  9772.5  223.17 10011.5  224.55
#Mann= 3 , 0 , 0
     357     .17       0  1343.7    .015       0    9225     .17       0
#XS Ineff= 2 , 0
       0  1307.2  202.23               0
Permanent Ineff=
       F       F
Bank Sta=1343.7,9225
XS Rating Curve= 0 ,0
Exp/Cntr=0.3,0.1

Type RM Length L Ch R = 1 ,692     ,0,0,0
BEGIN DESCRIPTION:
Conroe Lake 077 1.0
END DESCRIPTION:
XS GIS Cut Line= 4
      3786916.44     10166003.77      3791031.03     10163537.48
      3791038.67     10163430.47      3785951.23     10162042.45
#Sta/Elev= 30
   145.4  217.64   395.7  211.58   475.5  208.23   527.9  204.82   543.4  202.76
   564.9  203.49   601.7  201.12   644.6  199.81   708.7  200.71   761.2  199.36
   862.3  200.46   877.9  199.34   883.7  200.33   899.3  199.97   900.7  198.67
   909.4  198.67   914.8   200.1   936.2  199.46   986.5  200.58  1068.1  199.64
  1089.8  200.58  1095.6  199.59  1103.1     201  9445.6     201  9472.6  199.94
  9507.1  201.77  9870.6  221.64 10002.8  223.97 10098.7  221.03 10323.2  223.99
#Mann= 3 , 0 , 0
   145.4     .17       0   601.7    .015       0  9507.1     .17       0
Bank Sta=601.7,9507.1
XS Rating Curve= 0 ,0
Exp/Cntr=0.3,0.1

Chan Stop Cuts=-1
Use User Specified Reach Order=0
Composite Channel Slope=5