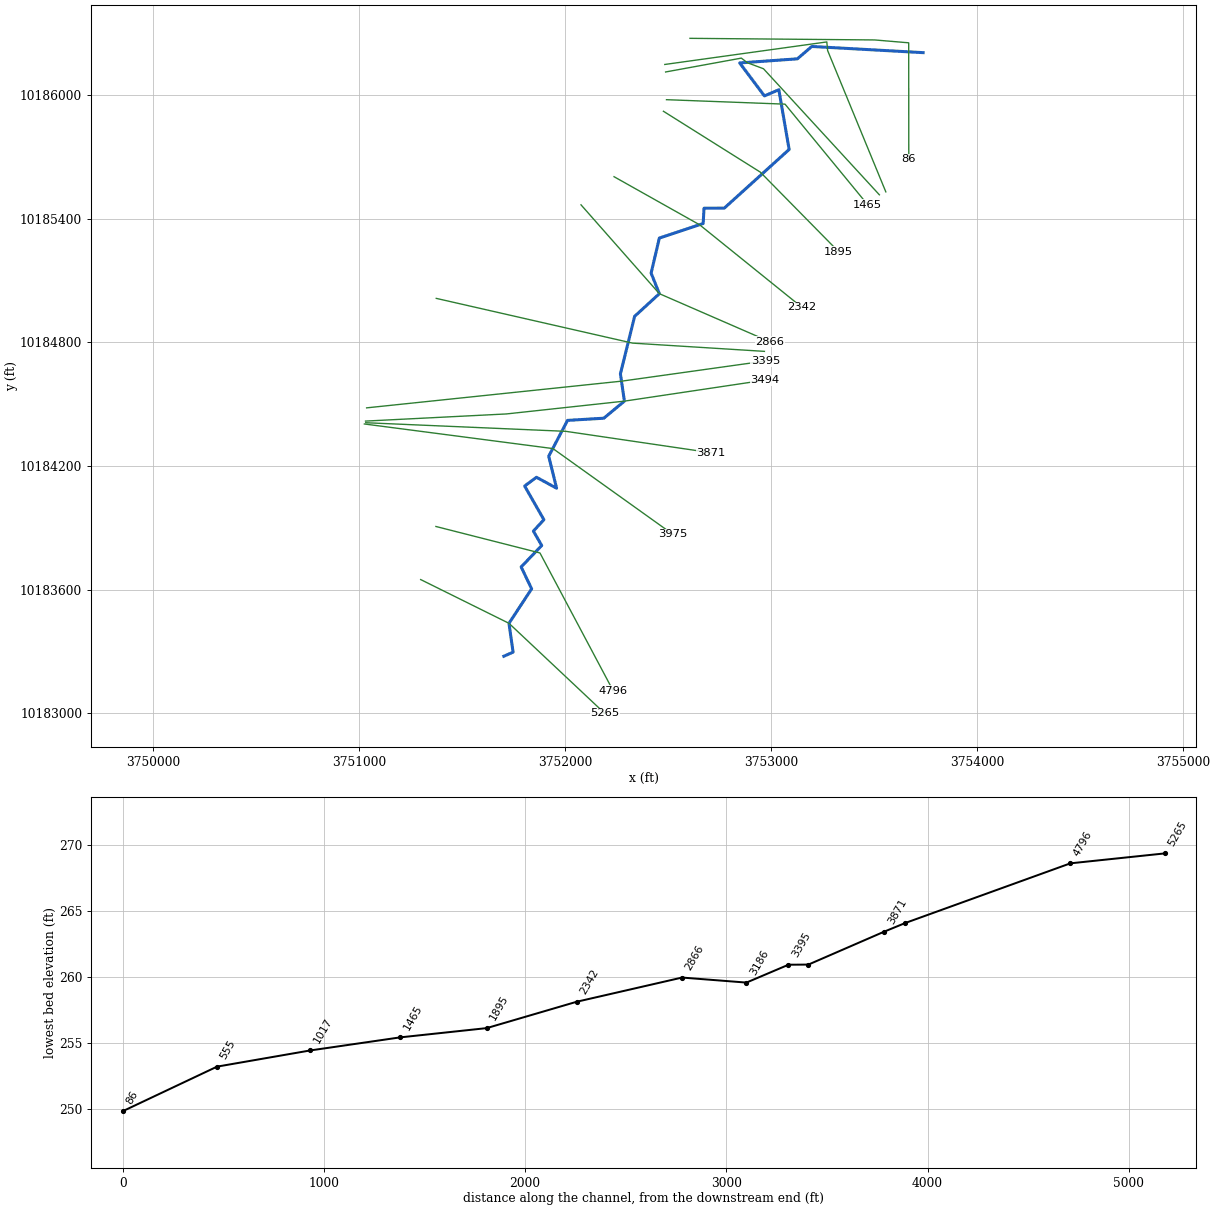
--- Conroe Lake 082.prj (project) ---

Proj Title=Conroe Lake 082 Base Level Engineering
Current Plan=p01
Default Exp/Contr=0.3,0.1
English Units
Geom File=g01
Flow File=f01
Flow File=f02
Plan File=p01
Y Axis Title=Elevation
X Axis Title(PF)=Main Channel Distance
X Axis Title(XS)=Station
BEGIN DESCRIPTION:
Conroe Lake 082
END DESCRIPTION:
DSS File=dss
DSS Export Rating Curves= 0
DSS Export Rating Curve Sorted= 0
DSS Export Volume Flow Curves= 0
DXF OffsetX= 0
DXF OffsetY= 0
DXF ScaleX= 1
DXF ScaleY= 10

--- Conroe Lake 082.p01 (plan) ---

Plan Title=Multiple Run
Program Version=4.10
Short Identifier=Multiple Run
Geom File=g01
Flow File=f01
Subcritical Flow
K Sum by GR= 0
Std Step Tol= 0.01
Critical Tol= 0.01
Num of Std Step Trials= 20
Max Error Tol= 0.3
Flow Tol Ratio= 0.001
Split Flow NTrial= 30
Split Flow Tol= 0.02
Split Flow Ratio= 0.02
Log Output Level= 0
Friction Slope Method= 1
Unsteady Friction Slope Method= 2
Unsteady Bridges Friction Slope Method= 1
Parabolic Critical Depth
Global Vel Dist= 1 , 1 , 1
Global Log Level= 0
CheckData=True
Encroach Param=-1 ,0,0, 0
BEGIN DESCRIPTION:
Multiple Run
END DESCRIPTION:
Computation Interval=1HOUR
Output Interval=1HOUR
Run HTab= 0
Run UNet= 0
Run PostProcess= 0
Run WQNet= 0
UNET Theta= 1
UNET Theta Warmup= 1
UNET ZTol= 0.02
UNET ZSATol= 0.05
UNET MxIter= 20
UNET MaxInSteps= 0
UNET DtIC= 0
UNET DtMin= 0
UNET MaxCRTS= 20
UNET WFStab= 2
UNET SFStab= 1
UNET WFX= 1
UNET SFX= 1
UNET DSS MLevel= 4
UNET DZMax Abort= 100
UNET Convert EG Bridges= 0
UNET Use Existing IB Tables=-1
UNET Froude Reduction=False
UNET Froude Limit= 1
UNET Froude Power= 10
UNET Time Slicing=0,0, 5
UNET Junction Losses=0
Instantaneous Interval=1HOUR
DSS File=dss
Write IC File= 0
Write IC File at Sim End=0
Echo Input=False
Echo Parameters=False
Echo Output=False
Write Detailed= 0
WQ AD Non Conservative
WQ ULTIMATE=-1
WQ Max Comp Step=1HOUR
WQ Output Interval=15MIN
WQ Output Selected Increments= 0
WQ Output face flow=0
WQ Output face velocity=0
WQ Output face area=0
WQ Output face dispersion=0
WQ Output cell volume=0
WQ Output cell surface area=0
WQ Output cell continuity=0
WQ Output cumulative cell continuity=0
WQ Output face conc=0
WQ Output face dconc_dx=0
WQ Output face courant=0
WQ Output face peclet=0
WQ Output face adv mass=0
WQ Output face disp mass=0
WQ Output cell mass=0
WQ Output cell source sink temp=0
WQ Output cell source sink nsm=0
WQ Output MaxMinRange=-1
WQ Daily Max Min Mean=-1
WQ Daily Range=0
WQ Daily Time=0
WQ Create Restart=0
WQ Fixed Restart=0
WQ System Summary=0
WQ Use Fixed Temperature=0
Sorting and Armoring Iterations= 10
XS Update Threshold= 0.02
Hydraulics Update Threshold= 0.02
Energy Slope Method= 1
Volume Change Method= 0
XS Weighting Method= 0
Number of US Weighted Cross Sections= 1
Number of DS Weighted Cross Sections= 1
Upstream XS Weight=0.25
Main XS Weight=0.5
Downstream XS Weight=0.25
Number of DS XS's Weighted with US Boundary= 1
Upstream Boundary Weight= 1
Weight of XSs Associated with US Boundary= 0
Number of US XS's Weighted with DS Boundary= 1
Downstream Boundary Weight= 0.5
Weight of XSs Associated with DS Boundary= 0.5
Sediment Output Level= 4
Mass or Volume Output= 0
Output Increment Type= 1
Profile and TS Output Increment= 10
XS Output Flag= 0
XS Output Increment= 10
Disregard all LS=0
Disregard all Conn=0
Disregard all Breaches=0
Disregard all Pumps=0

--- Conroe Lake 082.f01 (steady flow) ---

Flow Title=Multiple
Program Version=4.10
Number of Profiles= 7
Profile Names=10-year,25-year,50-year,1pct_min,100-year,1pct_plu,500-year
River Rch & RM=Conroe Lake 082,Reach-1         ,5265
     408     537     710     310     936    2827    1677
River Rch & RM=Conroe Lake 082,Reach-1         ,3975
     616     828    1114     492    1487    4491    2743
Boundary for River Rch & Prof#=Conroe Lake 082,Reach-1         , 1
Up Type= 0
Dn Type= 3
Dn Slope=0.006
Boundary for River Rch & Prof#=Conroe Lake 082,Reach-1         , 2
Up Type= 0
Dn Type= 3
Dn Slope=0.006
Boundary for River Rch & Prof#=Conroe Lake 082,Reach-1         , 3
Up Type= 0
Dn Type= 3
Dn Slope=0.006
Boundary for River Rch & Prof#=Conroe Lake 082,Reach-1         , 4
Up Type= 0
Dn Type= 3
Dn Slope=0.006
Boundary for River Rch & Prof#=Conroe Lake 082,Reach-1         , 5
Up Type= 0
Dn Type= 3
Dn Slope=0.006
Boundary for River Rch & Prof#=Conroe Lake 082,Reach-1         , 6
Up Type= 0
Dn Type= 3
Dn Slope=0.006
Boundary for River Rch & Prof#=Conroe Lake 082,Reach-1         , 7
Up Type= 0
Dn Type= 3
Dn Slope=0.006
DSS Import GetInterval= 0
DSS Import GetPeak= 0
DSS Import FillOption= 0

--- Conroe Lake 082.f02 (steady flow) ---

Flow Title=Orig_BLE_Flow
Program Version=4.10
Number of Profiles= 7
Profile Names=10-year,25-year,50-year,1pct_min,100-year,1pct_plu,500-year
River Rch & RM=Conroe Lake 082,Reach-1         ,5265
     408     526     617     238     720    2173     975
River Rch & RM=Conroe Lake 082,Reach-1         ,3975
     616     812     969     379    1144    3456    1595
Boundary for River Rch & Prof#=Conroe Lake 082,Reach-1         , 1
Up Type= 0
Dn Type= 3
Dn Slope=0.005
Boundary for River Rch & Prof#=Conroe Lake 082,Reach-1         , 2
Up Type= 0
Dn Type= 3
Dn Slope=0.005
Boundary for River Rch & Prof#=Conroe Lake 082,Reach-1         , 3
Up Type= 0
Dn Type= 3
Dn Slope=0.005
Boundary for River Rch & Prof#=Conroe Lake 082,Reach-1         , 4
Up Type= 0
Dn Type= 3
Dn Slope=0.005
Boundary for River Rch & Prof#=Conroe Lake 082,Reach-1         , 5
Up Type= 0
Dn Type= 3
Dn Slope=0.005
Boundary for River Rch & Prof#=Conroe Lake 082,Reach-1         , 6
Up Type= 0
Dn Type= 3
Dn Slope=0.005
Boundary for River Rch & Prof#=Conroe Lake 082,Reach-1         , 7
Up Type= 0
Dn Type= 3
Dn Slope=0.005
DSS Import GetInterval= 0
DSS Import GetPeak= 0
DSS Import FillOption= 0

--- Conroe Lake 082.g01 (geometry) ---

Geom Title=Existing Conditions
Program Version=4.10

River Reach=Conroe Lake 082 ,Reach-1
Reach XY= 30
      3751703.23     10183276.84      3751748.23     10183296.84
      3751728.23     10183436.84      3751838.33     10183604.13
      3751787.36     10183710.32      3751887.18     10183814.38
      3751846.83     10183884.47       3751897.8     10183939.69
      3751804.35     10184103.22       3751861.7     10184145.69
      3751959.39      10184092.6      3751921.16     10184247.63
      3752012.48     10184421.78      3752188.75      10184432.4
      3752288.57     10184515.23      3752269.21     10184647.83
      3752338.23     10184926.84      3752458.23     10185036.84
      3752418.23     10185136.84      3752458.23     10185306.84
      3752670.85     10185377.47       3752675.1     10185451.81
      3752773.59      10185452.2      3753088.23     10185736.84
      3753038.23     10186026.84      3752968.23     10185996.84
      3752848.23     10186156.84      3753128.23     10186176.84
      3753198.23     10186236.84      3753738.23     10186206.84

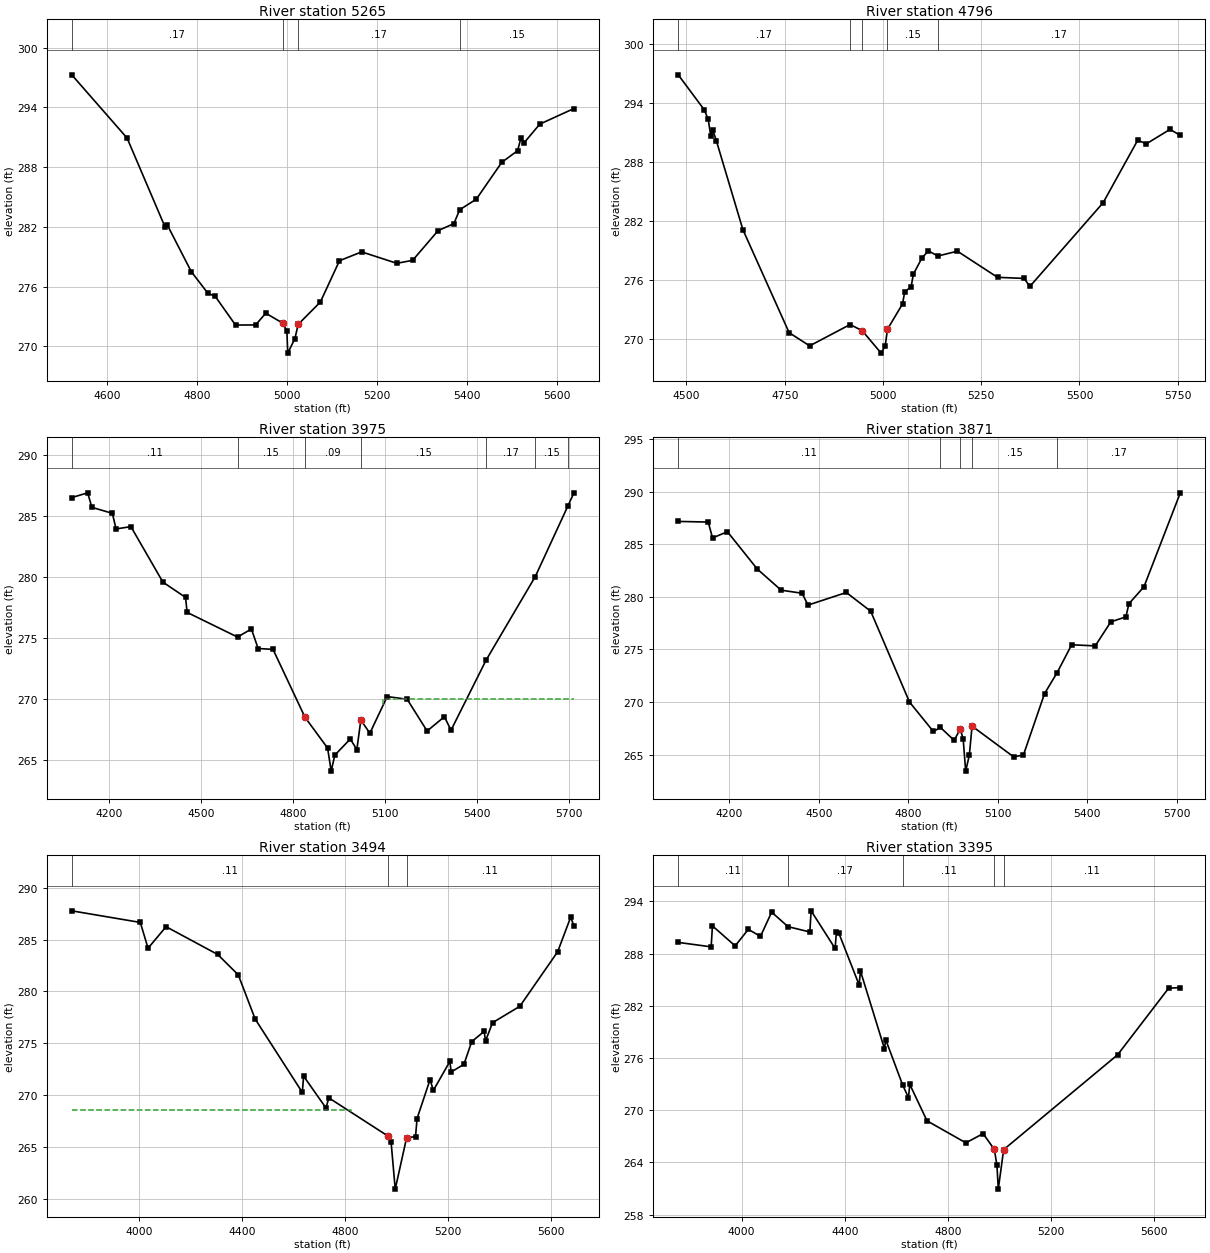
Type RM Length L Ch R = 1 ,5265    ,469,469,469
BEGIN DESCRIPTION:
Conroe Lake 082 9.0
END DESCRIPTION:
XS GIS Cut Line= 3
      3751299.63     10183649.16      3751728.23     10183436.84
      3752193.11      10182999.6
#Sta/Elev= 30
  4521.7  297.28  4644.7  290.93  4728.8  282.03  4734.4  282.18  4787.5  277.51
  4824.1  275.36  4840.9  275.02  4885.8  272.15  4930.6  272.16    4953  273.34
  4990.9  272.34    5000  271.56    5002  269.33  5017.9  270.79  5025.2  272.22
  5074.5  274.46    5117  278.61  5166.4   279.5  5244.5  278.35  5279.7  278.65
  5336.3  281.63  5371.5  282.34  5384.3  283.73  5421.3  284.79  5477.9  288.49
  5513.1  289.66  5520.4  290.91  5527.3  290.44  5562.5  292.33  5638.2  293.89
#Mann= 4 ,-1 , 0
  4521.7     .17       0  4990.9     .09       0  5025.2     .17       0
  5384.3     .15       0
Bank Sta=4990.9,5025.2
XS Rating Curve= 0 ,0
Exp/Cntr=0.3,0.1

Type RM Length L Ch R = 1 ,4796    ,821,821,821
BEGIN DESCRIPTION:
Conroe Lake 082 8.0
END DESCRIPTION:
XS GIS Cut Line= 3
      3751373.78     10183906.76      3751878.69     10183778.28
       3752233.6     10183110.09
#Sta/Elev= 30
    4479  296.89  4545.1  293.34  4555.4  292.35  4561.7  290.67  4566.9  291.28
  4576.1  290.17  4643.6  281.13  4761.2  270.66  4813.4  269.32  4916.4  271.49
  4947.5  270.85  4995.2  268.58  5005.7  269.31  5011.4  271.01  5049.7  273.58
  5055.3  274.81  5071.6  275.33  5077.3  276.61  5099.3  278.27  5115.6  278.98
  5139.7  278.46  5189.3  278.95  5291.5  276.29  5359.2  276.18  5373.7  275.36
  5560.2  283.88  5648.2  290.24  5670.1  289.87  5730.4  291.34  5756.6  290.73
#Mann= 5 ,-1 , 0
    4479     .17       0  4916.4     .15       0  4947.5     .09       0
  5011.4     .15       0  5139.7     .17       0
Bank Sta=4947.5,5011.4
XS Rating Curve= 0 ,0
Exp/Cntr=0.3,0.1

Type RM Length L Ch R = 1 ,3975    ,104,104,104
BEGIN DESCRIPTION:
Conroe Lake 082 7.0
END DESCRIPTION:
XS GIS Cut Line= 3
      3751026.43     10184404.39      3751941.67     10184284.92
      3752524.03     10183868.55
#Sta/Elev= 30
    4077  286.49  4128.9  286.88  4142.6  285.69  4209.5   285.2  4221.6  283.92
    4270  284.11  4374.5  279.56  4448.4  278.31  4453.5  277.08    4618  275.06
  4663.4  275.72  4685.3  274.12  4733.9  274.05  4838.2  268.49  4912.1  265.96
  4923.8  264.07  4935.6  265.38  4986.1   266.7  5007.6  265.84  5020.6  268.25
  5050.1  267.18  5106.6  270.18  5171.8  269.96  5236.9  267.36  5293.4  268.53
  5314.9  267.42  5429.5  273.17  5590.1  280.02  5697.2  285.84  5715.9  286.86
#Mann= 7 ,-1 , 0
    4077     .11       0    4618     .15       0  4838.2     .09       0
  5020.6     .15       0  5429.5     .17       0  5590.1     .15       0
  5697.2     .17       0
#XS Ineff= 2 , 0
       0                  5093.7       0  269.98
Permanent Ineff=
       F       F
Bank Sta=4838.2,5020.6
XS Rating Curve= 0 ,0
Exp/Cntr=0.3,0.1

Type RM Length L Ch R = 1 ,3871    ,377,377,377
BEGIN DESCRIPTION:
Mapping XS 0353349f
END DESCRIPTION:
XS GIS Cut Line= 3
      3751032.98     10184410.42      3752003.99     10184368.69
      3752708.39     10184264.97
#Sta/Elev= 30
  4028.1  287.17  4128.7  287.11  4143.1   285.6  4193.1  286.19  4293.2  282.64
  4373.3  280.63  4443.4  280.34  4463.4  279.21  4591.8  280.41  4673.6  278.63
  4803.7  269.99  4883.8  267.19  4907.6  267.57  4953.8  266.34  4973.8  267.44
  4983.8  266.46  4992.1  263.42  5004.5  264.95  5013.5   267.7  5152.9  264.78
  5185.8  264.95  5256.6  270.79  5298.9  272.79  5347.6  275.44  5426.6  275.33
    5479  277.62  5529.5  278.09  5539.6  279.34  5590.2  280.96    5712  289.89
#Mann= 5 ,-1 , 0
  4028.1     .11       0  4907.6     .15       0  4973.8     .09       0
  5013.5     .15       0  5298.9     .17       0
Bank Sta=4973.8,5013.5
XS Rating Curve= 0 ,0
Exp/Cntr=0.3,0.1

Type RM Length L Ch R = 1 ,3494    ,99,99,99
BEGIN DESCRIPTION:
Conroe Lake 082 6.0
END DESCRIPTION:
XS GIS Cut Line= 4
      3751032.01     10184418.37      3751716.03     10184453.09
      3752288.57     10184515.23       3752970.1     10184617.11
#Sta/Elev= 30
  3739.2  287.78  4005.4  286.66  4035.4  284.17  4105.5  286.25  4305.8  283.57
  4385.9   281.6  4451.4  277.34  4634.6  270.26  4639.6  271.83  4726.2  268.77
  4737.7  269.73  4969.1  266.02  4979.2  265.51  4995.4  260.93  5039.7   265.9
  5074.2  265.99  5080.2  267.74  5130.7   271.5  5143.4  270.45  5207.6  273.25
  5212.6  272.23  5262.2  272.97  5292.5  275.16  5340.9  276.15    5346  275.22
  5373.4  276.99  5479.4  278.57  5626.2  283.83  5676.7  287.16  5689.1  286.36
#Mann= 3 , 0 , 0
  3739.2     .11       0  4969.1     .09       0  5039.7     .11       0
#XS Ineff= 2 , 0
       0  4822.9  268.55               0
Permanent Ineff=
       F       F
Bank Sta=4969.1,5039.7
XS Rating Curve= 0 ,0
Exp/Cntr=0.3,0.1

Type RM Length L Ch R = 1 ,3395    ,209,209,209
BEGIN DESCRIPTION:
Conroe Lake 082 5.0
END DESCRIPTION:
XS GIS Cut Line= 3
      3751037.22     10184482.61      3752276.74     10184612.41
      3752972.93     10184710.03
#Sta/Elev= 30
  3753.7  289.28  3881.5  288.77  3886.5  291.18  3974.7  288.88  4025.8  290.78
    4073  289.97  4116.3  292.76  4179.9  291.09  4264.6  290.48  4269.6  292.91
  4362.8  288.58  4367.9  290.52  4377.7  290.31  4456.1  284.39  4461.1     286
  4554.4  277.06  4559.4  278.09  4625.1  272.88  4647.6  271.44  4652.7  272.96
  4719.6  268.77  4870.4  266.24  4937.4   267.3    4981  265.48  4991.1  263.65
  4996.3  260.92 5017.11  265.46  5459.5  276.36  5657.5  284.01    5703  284.09
#Mann= 5 ,-1 , 0
  3753.7     .11       0  4179.9     .17       0  4625.1     .11       0
    4981     .09       0 5017.11     .11       0
#XS Ineff= 2 , 0
       0  4937.4   267.3               0
Permanent Ineff=
       F       F
Bank Sta=4981,5017.11
XS Rating Curve= 0 ,0
Exp/Cntr=0.3,0.1

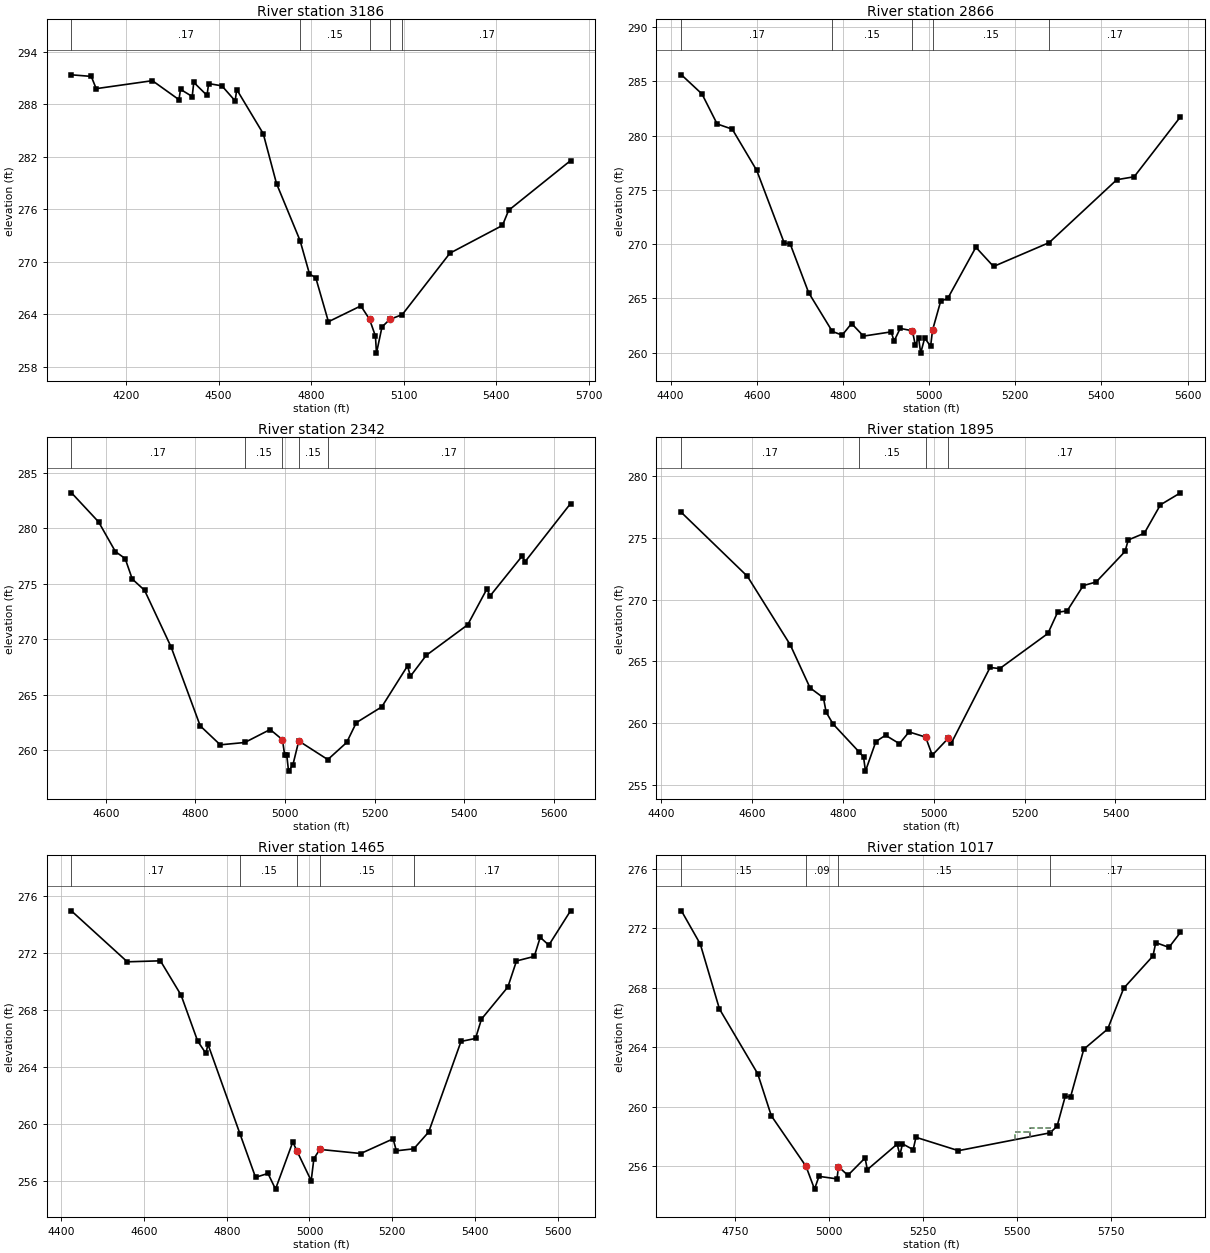
Type RM Length L Ch R = 1 ,3186    ,320,320,320
BEGIN DESCRIPTION:
Mapping XS 8934e964
END DESCRIPTION:
XS GIS Cut Line= 3
      3751375.37     10185014.03      3752328.23     10184796.84
      3752968.18     10184756.83
#Sta/Elev= 30
  4022.7  291.39  4086.8  291.21  4102.8  289.81  4285.1  290.72  4371.2  288.55
  4376.3  289.73  4414.2  288.91  4419.3  290.53  4462.3  289.03  4467.4  290.39
  4510.5  290.13  4553.5  288.41  4558.6  289.71  4644.6  284.66  4687.6  278.96
    4764  272.44  4794.5  268.63    4815  268.18    4856  263.16  4961.1  264.97
  4989.4  263.44  5008.5  261.51  5011.8  259.57  5029.7  262.56 5054.72  263.42
  5095.6  263.98  5250.1     271  5420.4  274.17  5440.5   275.9  5641.2  281.58
#Mann= 5 ,-1 , 0
  4022.7     .17       0    4764     .15       0  4989.4     .09       0
 5054.72     .15       0  5095.6     .17       0
Bank Sta=4989.4,5054.72
XS Rating Curve= 0 ,0
Exp/Cntr=0.3,0.1

Type RM Length L Ch R = 1 ,2866    ,524,524,524
BEGIN DESCRIPTION:
Conroe Lake 082 4.0
END DESCRIPTION:
XS GIS Cut Line= 3
      3752077.94     10185468.12      3752458.23     10185036.84
      3752993.37       10184804.
#Sta/Elev= 30
    4425  285.61  4472.8  283.84  4507.9  281.08    4543   280.6  4599.9  276.79
  4663.5  270.12  4677.7     270  4720.4  265.52  4775.3  261.95  4798.2  261.61
    4820  262.68  4847.7  261.52    4912  261.91  4918.7  261.06  4932.9  262.23
  4961.3  262.01    4968  260.68  4975.6  261.36  4980.5  259.95  4989.8  261.35
  5003.5  260.57 5007.96  262.06  5026.9  264.74  5043.2  264.99  5108.6  269.71
  5149.6  267.94  5278.8  270.14  5435.8  275.94  5476.1  276.21  5583.6  281.74
#Mann= 5 ,-1 , 0
    4425     .17       0  4775.3     .15       0  4961.3     .09       0
 5007.96     .15       0  5278.8     .17       0
Bank Sta=4961.3,5007.96
XS Rating Curve= 0 ,0
Exp/Cntr=0.3,0.1

Type RM Length L Ch R = 1 ,2342    ,447,447,447
BEGIN DESCRIPTION:
Conroe Lake 082 3.0
END DESCRIPTION:
XS GIS Cut Line= 3
       3752238.3     10185604.67      3752653.86      10185371.1
      3753150.14      10184970.8
#Sta/Elev= 30
  4523.3   283.2  4583.8  280.58  4621.4   277.9  4643.1  277.28    4659  275.43
  4686.4  274.42  4745.7  269.31  4810.7   262.2  4855.5  260.49  4910.2   260.7
  4966.9  261.87  4994.4  260.95  4999.4  259.53    5004  259.53    5008  258.12
  5017.7  258.69  5030.8  260.84  5095.6  259.16  5137.7   260.7  5159.3  262.49
  5216.1  263.91  5273.6   267.6  5280.1  266.67  5315.3  268.55    5408  271.31
  5451.2  274.56  5457.6  273.89  5529.5   277.5    5536  276.99  5637.6  282.23
#Mann= 5 ,-1 , 0
  4523.3     .17       0  4910.2     .15       0  4994.4     .09       0
  5030.8     .15       0  5095.6     .17       0
Bank Sta=4994.4,5030.8
XS Rating Curve= 0 ,0
Exp/Cntr=0.3,0.1

Type RM Length L Ch R = 1 ,1895    ,430,430,430
BEGIN DESCRIPTION:
Conroe Lake 082 2.0
END DESCRIPTION:
XS GIS Cut Line= 3
      3752478.14     10185922.25      3752948.23     10185626.84
      3753329.12     10185239.84
#Sta/Elev= 30
  4444.8  277.04    4590  271.88  4684.3  266.34  4727.9  262.86  4757.3  262.06
  4763.3  260.89  4778.5  259.94  4835.3   257.7  4845.6  257.27  4849.8  256.13
  4872.7  258.52  4893.9  259.03  4924.5  258.35  4945.7   259.3  4982.2  258.88
  4996.8  257.42  5032.1  258.79  5039.1  258.42    5124  264.51  5145.3  264.42
  5251.3  267.26  5272.6  268.97  5293.7  269.09  5329.1  271.13  5357.4  271.42
    5421  273.89  5428.1  274.82  5463.4  275.36  5498.9  277.66    5543  278.63
#Mann= 4 ,-1 , 0
  4444.8     .17       0  4835.3     .15       0  4982.2     .09       0
  5032.1     .17       0
Bank Sta=4982.2,5032.1
XS Rating Curve= 0 ,0
Exp/Cntr=0.3,0.1

Type RM Length L Ch R = 1 ,1465    ,448,448,448
BEGIN DESCRIPTION:
Conroe Lake 082 1.0
END DESCRIPTION:
XS GIS Cut Line= 3
      3752492.94     10185978.47      3753068.23     10185956.84
      3753469.14     10185469.05
#Sta/Elev= 30
  4424.3  274.96  4559.3  271.39  4639.4  271.46  4689.4  269.05  4729.4  265.83
  4749.4  264.96  4754.4   265.6  4831.6  259.33  4869.5  256.26  4899.6  256.53
  4917.8  255.43  4959.6  258.74  4969.6  258.11  5004.1  256.02  5010.6  257.57
    5025  258.22    5124  257.93  5202.2  258.96  5210.1  258.12  5252.2  258.26
  5288.3  259.44  5366.5   265.8  5401.6  266.01    5416  267.37  5479.8  269.62
  5500.7  271.45  5543.7  271.77  5558.1  273.11  5578.9  272.56  5631.4  274.97
#Mann= 5 ,-1 , 0
  4424.3     .17       0  4831.6     .15       0  4969.6     .09       0
    5025     .15       0  5252.2     .17       0
Bank Sta=4969.6,5025
XS Rating Curve= 0 ,0
Exp/Cntr=0.3,0.1

Type RM Length L Ch R = 1 ,1017    ,462,462,462
BEGIN DESCRIPTION:
Conroe Lake 082 2.5
END DESCRIPTION:
XS GIS Cut Line= 5
      3752488.55     10186113.01      3752856.15     10186180.27
       3752885.5     10186157.91      3752963.81     10186128.63
      3753526.29     10185516.67
#Sta/Elev= 30
  4608.1  273.18  4658.2  270.94  4709.1  266.57  4810.7  262.21  4846.8  259.38
 4938.89  255.98  4961.6  254.44  4973.4   255.3  5021.3  255.13  5025.2  255.95
  5050.2  255.37  5095.9  256.54  5101.8  255.75    5181  257.47  5188.4  256.74
  5195.2  257.49  5223.6   257.1    5231  257.93  5343.8  257.03  5587.2  258.23
  5605.8  258.68  5627.4  260.68  5641.6  260.65  5676.7  263.86  5740.2  265.22
  5782.8  267.97  5860.5  270.14  5867.9  271.04    5903  270.72  5933.5  271.73
#Mann= 4 ,-1 , 0
  4608.1     .15       0 4938.89     .09       0  5025.2     .15       0
  5587.2     .17       0
#XS Ineff= 2 ,-1
  5492.9 5534.77  258.32  5534.9  5590.3  258.54
Permanent Ineff=
       F       F
Bank Sta=4938.89,5025.2
XS Rating Curve= 0 ,0
Exp/Cntr=0.3,0.1

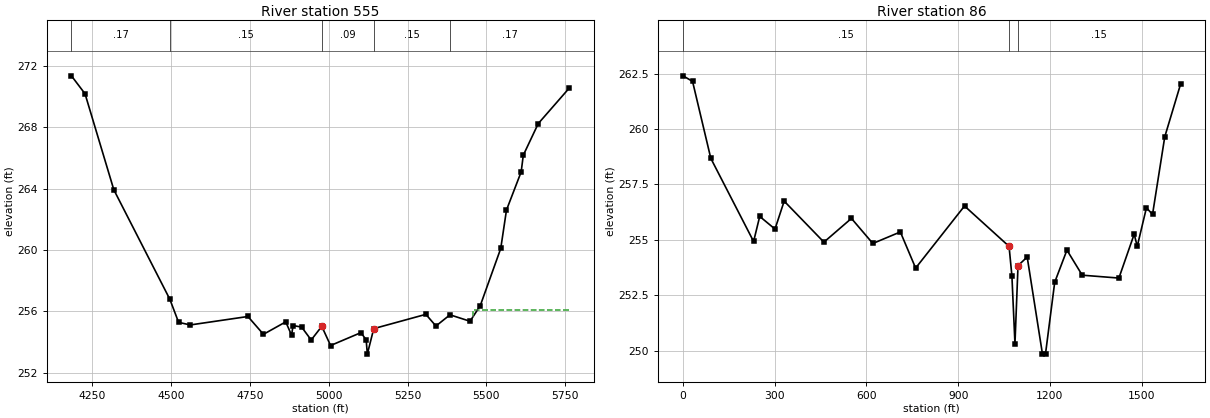
Type RM Length L Ch R = 1 ,555     ,469,469,469
BEGIN DESCRIPTION:
Conroe Lake 082 1.5
END DESCRIPTION:
XS GIS Cut Line= 4
      3752484.66     10186149.47       3753271.1     10186258.84
        3753275.     10186217.18      3753557.54     10185531.02
#Sta/Elev= 30
  4183.9  271.34  4227.1  270.17  4318.4  263.92  4496.1  256.79  4523.8  255.29
  4560.7  255.12  4743.7  255.67  4792.9  254.51  4863.6  255.32    4882  254.46
    4887  255.08  4914.1  254.98  4944.3  254.14  4977.9  255.03  5005.8  253.78
  5102.1  254.62  5118.7  254.15  5122.4  253.22  5142.7  254.88    5308  255.81
    5340  255.05  5384.5  255.78  5448.1  255.36  5480.6  256.38  5545.5   260.1
  5563.7   262.6  5610.3  265.09    5617  266.17  5664.4  268.23  5761.8  270.52
#Mann= 5 ,-1 , 0
  4183.9     .17       0  4496.1     .15       0  4977.9     .09       0
  5142.7     .15       0  5384.5     .17       0
#XS Ineff= 2 , 0
       0                  5457.1       0  256.08
Permanent Ineff=
       F       F
Bank Sta=4977.9,5142.7
XS Rating Curve= 0 ,0
Exp/Cntr=0.3,0.1

Type RM Length L Ch R = 1 ,86      ,0,0,0
BEGIN DESCRIPTION:
Conroe Lake 082 0.5
END DESCRIPTION:
XS GIS Cut Line= 4
      3752606.94      10186276.3      3753503.64     10186268.49
      3753668.57      10186254.6        3753669.      10185689.5
#Sta/Elev= 30
       0   262.4    31.2  262.15    90.9  258.68   230.9  254.93   250.9  256.06
   300.9  255.49   330.9  256.75   460.9   254.9   550.9  255.97   620.9  254.84
   710.9  255.36   760.9  253.73   920.8  256.53  1066.5  254.71  1075.8  253.38
  1085.8  250.32  1095.8  253.84  1125.8  254.23  1175.8  249.85  1185.8  249.87
  1215.8  253.09  1255.8  254.54  1305.8  253.41  1425.8  253.28  1475.8  255.26
  1485.8  254.71  1515.8  256.45  1535.8  256.15  1575.8  259.65  1627.4  262.02
#Mann= 3 , 0 , 0
       0     .15       0  1066.5     .09       0  1095.8     .15       0
Bank Sta=1066.5,1095.8
XS Rating Curve= 0 ,0
Exp/Cntr=0.3,0.1

Chan Stop Cuts=-1
Use User Specified Reach Order=0
Composite Channel Slope=5