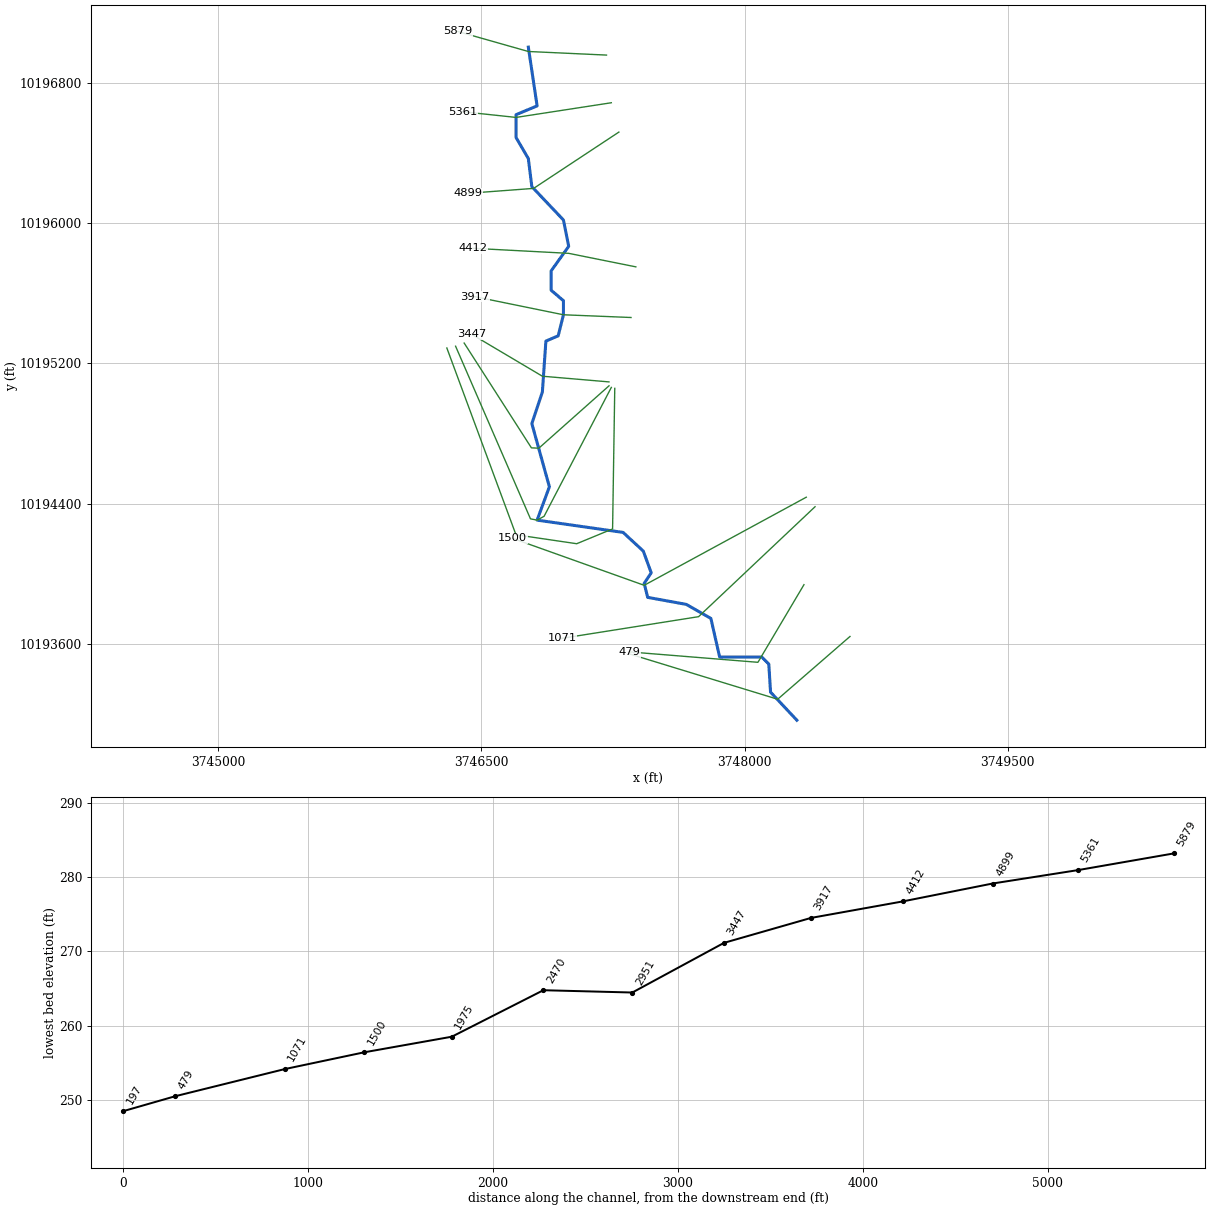
--- Conroe Lake 084.prj (project) ---

Proj Title=Conroe Lake 084 Base Level Engineering
Current Plan=p01
Default Exp/Contr=0.3,0.1
English Units
Geom File=g01
Flow File=f01
Flow File=f02
Plan File=p01
Y Axis Title=Elevation
X Axis Title(PF)=Main Channel Distance
X Axis Title(XS)=Station
BEGIN DESCRIPTION:
Conroe Lake 084
END DESCRIPTION:
DSS Export Rating Curves= 0
DSS Export Rating Curve Sorted= 0
DSS Export Volume Flow Curves= 0
DXF OffsetX= 0
DXF OffsetY= 0
DXF ScaleX= 1
DXF ScaleY= 10

--- Conroe Lake 084.p01 (plan) ---

Plan Title=Multiple Run
Short Identifier=Multiple
Geom File=g01
Flow File=f01
Subcritical Flow
K Sum by GR= 0
Std Step Tol= 0.01
Critical Tol= 0.01
Num of Std Step Trials= 20
Max Error Tol= 0.3
Flow Tol Ratio= 0.001
Split Flow NTrial= 30
Split Flow Tol= 0.02
Split Flow Ratio= 0.02
Log Output Level= 0
Friction Slope Method= 1
Unsteady Friction Slope Method= 2
Unsteady Bridges Friction Slope Method= 1
Parabolic Critical Depth
Global Vel Dist=  1 , 1 , 1
Global Log Level= 0
CheckData=True
Encroach Param= -1, 0, 0, 0
BEGIN DESCRIPTION:
Multiple Run
END DESCRIPTION:

--- Conroe Lake 084.f01 (steady flow) ---

Flow Title=Multiple
Program Version=4.10
Number of Profiles= 7
Profile Names=10-year,25-year,50-year,1pct_min,100-year,1pct_plu,500-year
River Rch & RM=Conroe Lake 084,Reach-1         ,5879
     437     578     769     337    1019    3077    1846
River Rch & RM=Conroe Lake 084,Reach-1         ,4899
     467     619     825     362    1092    3298    1981
River Rch & RM=Conroe Lake 084,Reach-1         ,1500
     913    1262    1728     778    2350    7097    4494
Boundary for River Rch & Prof#=Conroe Lake 084,Reach-1         , 1
Up Type= 0
Dn Type= 3
Dn Slope=0.005
Boundary for River Rch & Prof#=Conroe Lake 084,Reach-1         , 2
Up Type= 0
Dn Type= 3
Dn Slope=0.005
Boundary for River Rch & Prof#=Conroe Lake 084,Reach-1         , 3
Up Type= 0
Dn Type= 3
Dn Slope=0.005
Boundary for River Rch & Prof#=Conroe Lake 084,Reach-1         , 4
Up Type= 0
Dn Type= 3
Dn Slope=0.005
Boundary for River Rch & Prof#=Conroe Lake 084,Reach-1         , 5
Up Type= 0
Dn Type= 3
Dn Slope=0.005
Boundary for River Rch & Prof#=Conroe Lake 084,Reach-1         , 6
Up Type= 0
Dn Type= 3
Dn Slope=0.005
Boundary for River Rch & Prof#=Conroe Lake 084,Reach-1         , 7
Up Type= 0
Dn Type= 3
Dn Slope=0.005
DSS Import GetInterval= 0
DSS Import GetPeak= 0
DSS Import FillOption= 0

--- Conroe Lake 084.f02 (steady flow) ---

Flow Title=Orig_BLE_Flow
Program Version=4.10
Number of Profiles= 7
Profile Names=10-year,25-year,50-year,1pct_min,100-year,1pct_plu,500-year
River Rch & RM=Conroe Lake 084,Reach-1         ,5879
     437     567     669     260     784    2367    1073
River Rch & RM=Conroe Lake 084,Reach-1         ,4899
     467     607     717     278     840    2538    1152
River Rch & RM=Conroe Lake 084,Reach-1         ,1500
     913    1237    1503     599    1808    5459    2613
Boundary for River Rch & Prof#=Conroe Lake 084,Reach-1         , 1
Up Type= 0
Dn Type= 3
Dn Slope=0.005
Boundary for River Rch & Prof#=Conroe Lake 084,Reach-1         , 2
Up Type= 0
Dn Type= 3
Dn Slope=0.005
Boundary for River Rch & Prof#=Conroe Lake 084,Reach-1         , 3
Up Type= 0
Dn Type= 3
Dn Slope=0.005
Boundary for River Rch & Prof#=Conroe Lake 084,Reach-1         , 4
Up Type= 0
Dn Type= 3
Dn Slope=0.005
Boundary for River Rch & Prof#=Conroe Lake 084,Reach-1         , 5
Up Type= 0
Dn Type= 3
Dn Slope=0.005
Boundary for River Rch & Prof#=Conroe Lake 084,Reach-1         , 6
Up Type= 0
Dn Type= 3
Dn Slope=0.005
Boundary for River Rch & Prof#=Conroe Lake 084,Reach-1         , 7
Up Type= 0
Dn Type= 3
Dn Slope=0.005
DSS Import GetInterval= 0
DSS Import GetPeak= 0
DSS Import FillOption= 0

--- Conroe Lake 084.g01 (geometry) ---

Geom Title=Existing Conditions
Program Version=4.10

River Reach=Conroe Lake 084 ,Reach-1
Reach XY= 30
      3746768.23     10197001.84      3746818.23     10196666.84
      3746698.23     10196616.84      3746698.23     10196486.84
      3746768.23     10196366.84      3746788.23     10196206.84
      3746968.23     10196016.84      3746998.23     10195866.84
      3746898.23     10195726.84      3746898.23     10195616.84
      3746968.23     10195556.84      3746968.23     10195476.84
      3746938.23     10195356.84      3746868.23     10195326.84
      3746848.23     10195036.84      3746788.23     10194856.84
      3746888.23     10194496.84      3746818.23     10194306.84
      3747308.23     10194236.84       3747423.3     10194130.36
      3747468.23     10194006.84      3747428.23     10193946.84
      3747448.23     10193866.84      3747668.23     10193826.84
      3747808.23     10193746.84      3747858.23     10193526.84
      3748098.23     10193526.84      3748138.23     10193486.84
      3748148.23     10193326.84      3748298.23     10193166.84

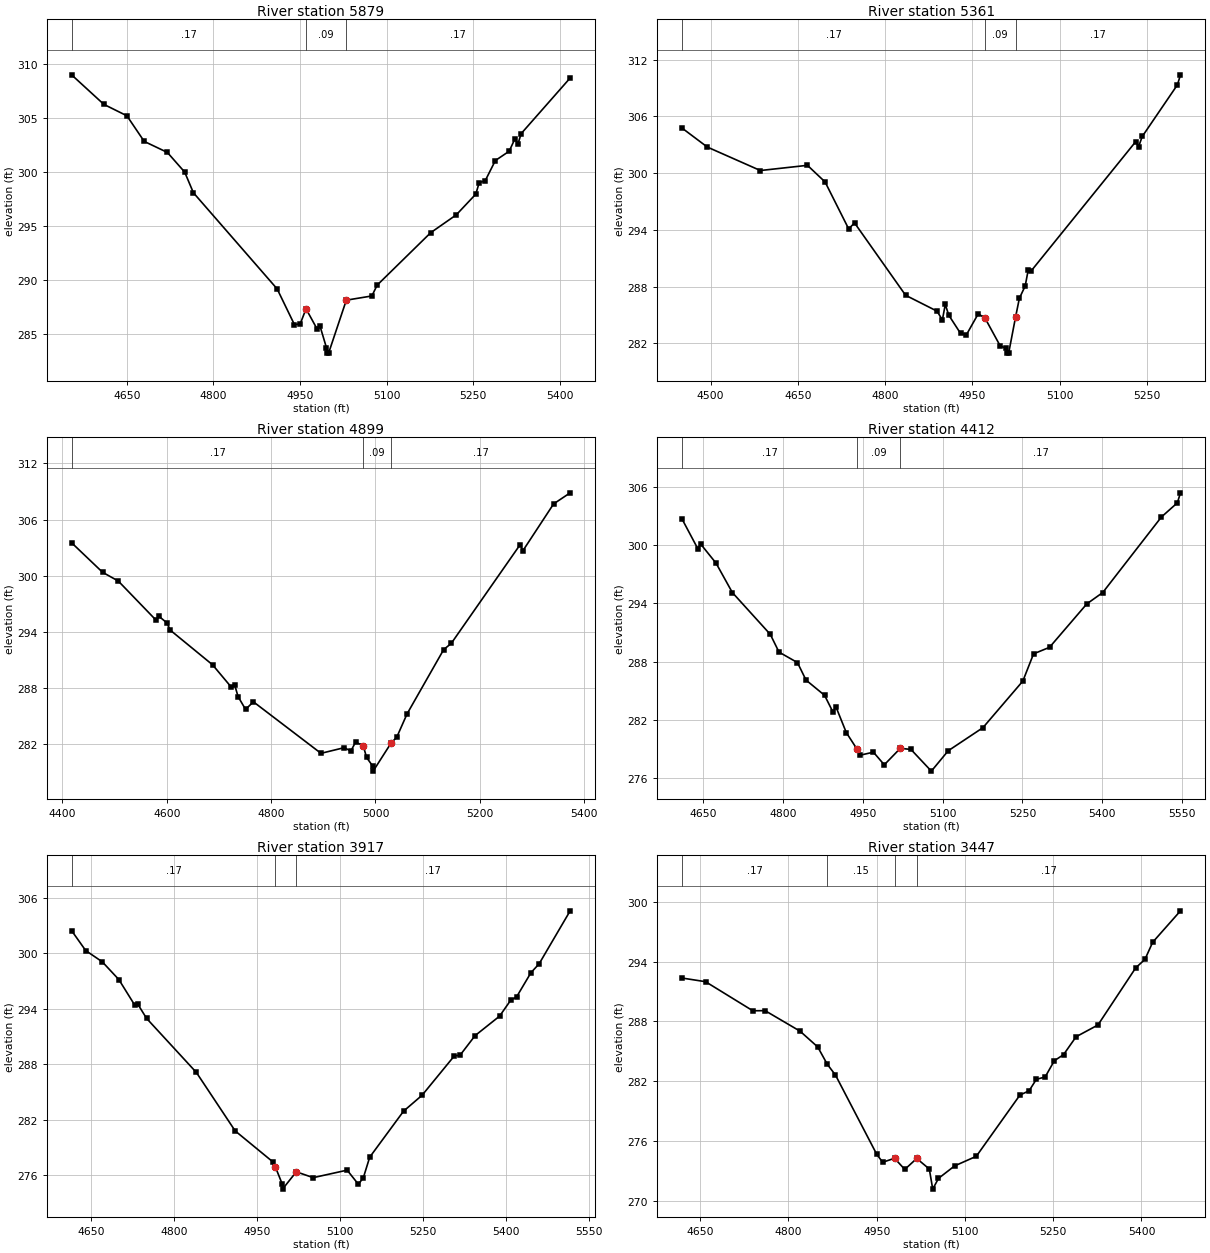
Type RM Length L Ch R = 1 ,5879    ,518,518,518
BEGIN DESCRIPTION:
Conroe Lake 084 10.0
END DESCRIPTION:
XS GIS Cut Line= 3
      3747213.56     10196956.39      3746768.23     10196976.84
      3746366.19     10197090.88
#Sta/Elev= 30
  4554.2  308.96    4610  306.23    4650  305.17    4680   302.8  4720.1  301.78
  4750.1  299.96  4765.2  298.05  4910.3  289.15  4940.3  285.84  4950.3  285.92
  4960.3  287.31  4979.2  285.47  4984.3  285.75  4995.7  283.71  4995.9  283.21
  4999.4  283.21  5030.1  288.11  5074.4   288.5  5083.5   289.5  5176.2  294.35
  5220.5     296  5254.4  297.92  5260.3  298.99  5270.6  299.15  5288.3  301.03
  5312.2  301.89  5322.2  303.04  5327.4  302.56    5333  303.52  5417.9  308.67
#Mann= 3 , 0 , 0
  4554.2     .17       0  4960.3     .09       0  5030.1     .17       0
Bank Sta=4960.3,5030.1
XS Rating Curve= 0 ,0
Exp/Cntr=0.3,0.1

Type RM Length L Ch R = 1 ,5361    ,462,462,462
BEGIN DESCRIPTION:
Conroe Lake 084 9.0
END DESCRIPTION:
XS GIS Cut Line= 3
      3747241.03     10196684.79      3746698.23     10196601.22
      3746392.57     10196633.84
#Sta/Elev= 30
  4450.8  304.77  4494.5  302.75  4585.6  300.27  4666.5  300.82  4696.8  299.06
  4737.3   294.1  4747.4  294.73  4835.1  287.08  4889.1   285.4  4898.3  284.47
  4903.3  286.11  4909.3  284.97  4929.6  283.04  4939.7  282.91  4959.9  285.12
  4971.6  284.66  4997.7  281.72  5008.4  281.46  5008.7  280.96  5012.2  280.96
 5023.94  284.74  5030.6  286.76  5040.6  288.06  5045.7  289.73  5050.7  289.64
  5230.4  303.32  5235.5  302.81  5241.7  303.87  5302.1  309.33  5307.4  310.39
#Mann= 3 , 0 , 0
  4450.8     .17       0  4971.6     .09       0 5023.94     .17       0
Bank Sta=4971.6,5023.94
XS Rating Curve= 0 ,0
Exp/Cntr=0.3,0.1

Type RM Length L Ch R = 1 ,4899    ,487,487,487
BEGIN DESCRIPTION:
Conroe Lake 084 8.0
END DESCRIPTION:
XS GIS Cut Line= 3
      3747284.08     10196517.64      3746798.23     10196196.84
      3746426.27     10196169.02
#Sta/Elev= 30
  4417.8  303.53  4477.1  300.38  4507.3  299.44  4579.5  295.27  4585.5  295.66
  4600.6  294.97  4606.6  294.21  4687.9   290.5    4724   288.1    4730  288.39
  4736.8   287.1  4751.1  285.74  4766.1  286.55  4895.6  281.05  4940.5  281.66
  4952.7  281.28  4961.8  282.24  4976.5  281.88  4982.9  280.61  4995.2  279.65
  4995.5  279.15  5030.5   282.2  5040.5  282.74  5060.5  285.26  5130.7  292.13
  5145.1  292.78  5277.3  303.34  5282.3  302.67  5341.3  307.68    5373  308.86
#Mann= 3 , 0 , 0
  4417.8     .17       0  4976.5     .09       0  5030.5     .17       0
Bank Sta=4976.5,5030.5
XS Rating Curve= 0 ,0
Exp/Cntr=0.3,0.1

Type RM Length L Ch R = 1 ,4412    ,495,495,495
BEGIN DESCRIPTION:
Conroe Lake 084 7.0
END DESCRIPTION:
XS GIS Cut Line= 3
      3747380.76     10195749.87      3746998.23     10195826.84
      3746451.99     10195855.59
#Sta/Elev= 30
  4609.8   302.7  4639.8  299.61  4644.9  300.11    4674  298.13  4704.6  295.11
    4776   290.8  4792.3  288.98    4827   287.9  4843.1   286.1    4878  284.53
    4894  282.78  4899.1  283.38  4918.8   280.7  4939.2  278.97  4944.8  278.37
  4969.8  278.68  4990.2  277.38  5020.4  279.08  5040.4  278.96  5078.7  276.73
  5110.5  278.83  5175.6   281.2  5250.7     286  5270.8   288.8  5300.8  289.47
  5370.9  293.94  5400.9  295.11  5511.1  302.88  5541.1  304.34    5547  305.37
#Mann= 3 ,-1 , 0
  4609.8     .17       0  4939.2     .09       0  5020.4     .17       0
Bank Sta=4939.2,5020.4
XS Rating Curve= 0 ,0
Exp/Cntr=0.3,0.1

Type RM Length L Ch R = 1 ,3917    ,470,470,470
BEGIN DESCRIPTION:
Conroe Lake 084 6.0
END DESCRIPTION:
XS GIS Cut Line= 3
      3747353.32      10195461.3      3746968.23     10195476.84
      3746462.77     10195580.13
#Sta/Elev= 30
  4614.6  302.43  4640.1  300.28  4670.1  299.06  4700.1  297.14    4729  294.36
    4734  294.51  4750.2  292.95  4840.2  287.11  4910.3   280.8  4978.1  277.47
  4983.1  276.89  4995.7  275.01  4995.9  274.51  5020.8  276.38  5051.4  275.75
  5112.7  276.56  5133.1  275.03  5142.1  275.76  5153.5  277.96  5214.7  282.93
  5248.2  284.65  5306.6  288.91  5316.8  288.97    5344  291.09  5388.2  293.19
  5408.7  294.94  5418.9  295.26    5445  297.89  5459.7  298.84  5515.9  304.57
#Mann= 3 , 0 , 0
  4614.6     .17       0  4983.1     .09       0  5020.8     .17       0
Bank Sta=4983.1,5020.8
XS Rating Curve= 0 ,0
Exp/Cntr=0.3,0.1

Type RM Length L Ch R = 1 ,3447    ,496,496,496
BEGIN DESCRIPTION:
Conroe Lake 084 5.0
END DESCRIPTION:
XS GIS Cut Line= 3
      3747227.95     10195094.39      3746848.23     10195126.84
      3746447.14     10195364.67
#Sta/Elev= 30
  4618.9  292.36  4659.1  291.99  4739.4  289.07  4760.3  289.08  4819.7  287.02
  4849.8  285.43  4865.9   283.7  4879.9  282.61  4950.2  274.63  4960.2  273.85
  4980.3  274.25  4997.7  273.13    5018  274.23  5039.4  273.17  5045.2  271.15
    5055  272.23  5082.3  273.48  5119.3  274.45  5193.4   280.6    5209  281.03
  5221.3  282.18  5236.3  282.42  5251.9  284.05  5267.5  284.66  5288.9  286.46
    5326  287.64  5390.3  293.39  5405.9  294.23    5419  295.95  5466.3  299.11
#Mann= 4 ,-1 , 0
  4618.9     .17       0  4865.9     .15       0  4980.3     .09       0
    5018     .17       0
Bank Sta=4980.3,5018
XS Rating Curve= 0 ,0
Exp/Cntr=0.3,0.1

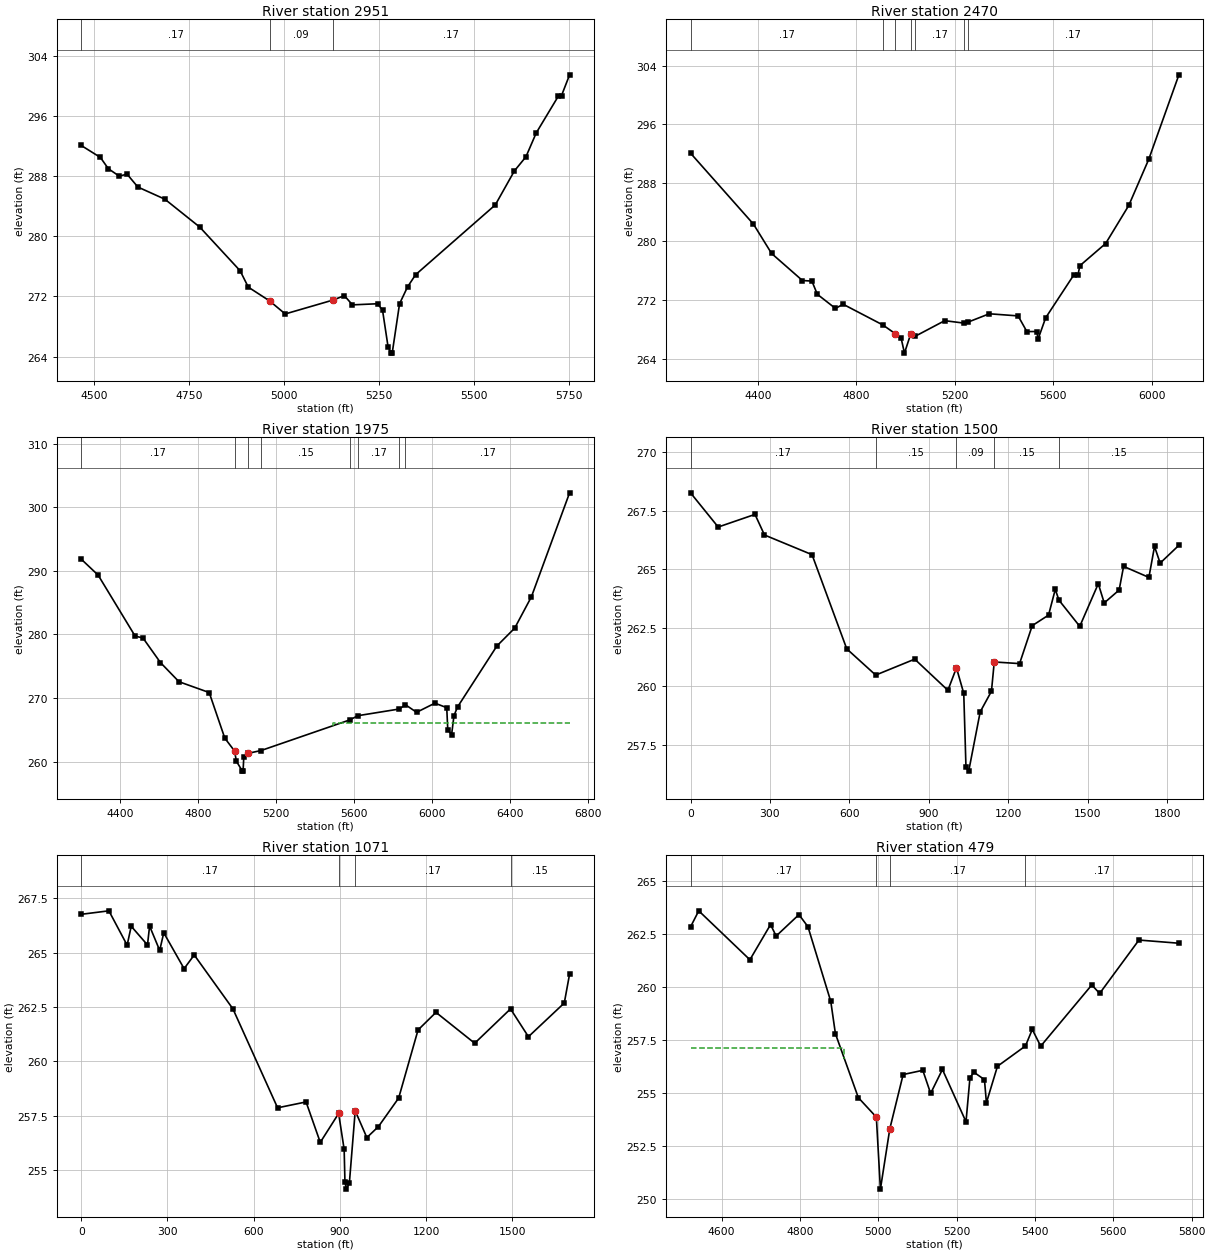
Type RM Length L Ch R = 1 ,2951    ,481,481,481
BEGIN DESCRIPTION:
Conroe Lake 084 4.0
END DESCRIPTION:
XS GIS Cut Line= 4
      3747227.93     10195072.16      3746828.23     10194716.84
      3746785.81     10194718.61      3746402.63     10195315.79
#Sta/Elev= 30
  4465.2  292.12  4515.8  290.52  4536.7  289.02  4565.2  288.04  4586.1  288.29
  4614.5  286.58  4685.6  284.96  4777.6  281.24  4883.8  275.43  4905.5  273.24
  4961.5  271.41  5002.7  269.67  5128.6  271.52  5158.6  272.11  5179.8  270.88
  5246.5  271.03  5259.2  270.15  5273.6  265.33  5281.1  264.45  5284.6  264.45
    5304  271.03  5325.1  273.28  5346.3   274.9  5556.3   284.2  5606.6  288.73
    5637  290.61  5664.1  293.79  5722.6  298.71  5730.8  298.77    5752  301.53
#Mann= 3 , 0 , 0
  4465.2     .17       0  4961.5     .09       0  5128.6     .17       0
Bank Sta=4961.5,5128.6
XS Rating Curve= 0 ,0
Exp/Cntr=0.3,0.1

Type RM Length L Ch R = 1 ,2470    ,495,495,495
BEGIN DESCRIPTION:
Conroe Lake 084 3.0
END DESCRIPTION:
XS GIS Cut Line= 5
      3747241.04     10195063.08      3746858.03     10194328.86
      3746818.23     10194306.84      3746780.42     10194314.27
      3746353.84     10195297.71
#Sta/Elev= 30
  4126.4  292.05  4382.2  282.36  4455.8  278.36    4581  274.67  4619.5  274.59
  4641.6  272.79  4715.2  270.86  4746.4  271.43    4908   268.6  4957.4  267.43
  4982.1  266.79  4995.6  264.76  5020.8  267.36  5040.2  267.08  5159.2  269.19
  5238.7  268.85  5252.1  268.97  5340.2  270.13  5457.2  269.84  5492.9   267.7
    5533  267.71  5538.5  266.68  5569.2  269.58  5684.7  275.49    5700  275.38
  5708.2  276.69  5812.9  279.72  5906.8  284.91  5988.1  291.22  6110.5  302.74
#Mann= 7 ,-1 , 0
  4126.4     .17       0    4908     .15       0  4957.4     .09       0
  5020.8     .15       0  5040.2     .17       0  5238.7     .15       0
  5252.1     .17       0
#XS Ineff= 2 , 0
       0                  5159.2       0  269.19
Permanent Ineff=
       F       F
Bank Sta=4957.4,5020.8
XS Rating Curve= 0 ,0
Exp/Cntr=0.3,0.1

Type RM Length L Ch R = 1 ,1975    ,475,475,475
BEGIN DESCRIPTION:
Conroe Lake 084 2.0
END DESCRIPTION:
XS GIS Cut Line= 5
      3747260.61     10195057.85      3747248.23     10194256.84
      3747043.85     10194172.52      3746697.83     10194223.45
      3746304.03     10195287.48
#Sta/Elev= 30
  4198.9  291.83  4285.7  289.32  4475.7  279.72  4515.7  279.44  4605.7  275.56
  4700.8  272.55  4855.8  270.85  4935.8  263.68  4985.8  261.66  4995.4  260.04
  5026.1  258.49  5029.6  258.49  5033.3  260.69  5057.2   261.3    5122  261.73
  5577.8  266.55  5619.1  267.21  5831.5  268.26    5863  268.93  5920.2  267.74
  6014.1  269.18  6074.9  268.47  6080.2  264.99  6099.9  264.25  6112.1  267.22
  6130.3  268.58  6332.5  278.18  6423.7  280.98  6509.6  285.92  6705.4  302.26
#Mann= 8 ,-1 , 0
  4198.9     .17       0  4985.8     .09       0  5057.2     .17       0
    5122     .15       0  5577.8     .11       0  5619.1     .17       0
  5831.5     .15       0    5863     .17       0
#XS Ineff= 2 , 0
       0                    5490       0  266.09
Permanent Ineff=
       F       F
Bank Sta=4985.8,5057.2
XS Rating Curve= 0 ,0
Exp/Cntr=0.3,0.1

Type RM Length L Ch R = 1 ,1500    ,429,429,429
BEGIN DESCRIPTION:
Conroe Lake 084 3.5
END DESCRIPTION:
XS GIS Cut Line= 3
      3748351.79     10194437.52      3747428.23      10193935.6
      3746679.41     10194202.89
#Sta/Elev= 30
       0  268.26   104.5   266.8   243.5  267.34   279.3  266.46   458.9  265.62
     590   261.6   699.3  260.48   846.7  261.16     972  259.83  1004.3  260.79
  1031.9   259.7  1040.2  256.57  1050.6  256.38    1094  258.91  1136.5  259.79
  1147.1  261.04  1242.7  260.97  1290.5  262.59  1352.1  263.04  1377.6  264.14
  1391.3  263.68    1470  262.56    1540  264.38  1562.4  263.56  1618.7  264.11
  1635.5  265.12  1731.1  264.65  1752.3  265.97  1773.6  265.26  1844.4  266.02
#Mann= 5 ,-1 , 0
       0     .17       0   699.3     .15       0  1004.3     .09       0
  1147.1     .15       0  1391.3     .15       0
Bank Sta=1004.3,1147.1
XS Rating Curve= 0 ,0
Exp/Cntr=0.3,0.1

Type RM Length L Ch R = 1 ,1071    ,592,592,592
BEGIN DESCRIPTION:
Conroe Lake 084 1.0
END DESCRIPTION:
XS GIS Cut Line= 3
       3748401.7     10194383.27      3747738.23     10193756.84
      3746959.36     10193633.45
#Sta/Elev= 30
       0  266.76    96.3  266.92   159.8  265.34     174  266.21   230.6  265.35
   237.9  266.22   273.1   265.1   287.2  265.91     358  264.26   393.2  264.89
   527.9  262.41   683.3  257.86   782.4  258.13   831.8  256.27   895.7   257.6
   914.9  255.95   917.7  254.43     923  254.12   933.1  254.41   953.4  257.72
   993.9  256.49  1034.4     257  1104.6  258.31    1172  261.44  1234.4  262.25
  1369.1  260.83  1493.8  262.41  1556.1  261.13  1680.8  262.68  1699.3  264.01
#Mann= 4 ,-1 , 0
       0     .17       0   895.7     .09       0   953.4     .17       0
  1493.8     .15       0
Bank Sta=895.7,953.4
XS Rating Curve= 0 ,0
Exp/Cntr=0.3,0.1

Type RM Length L Ch R = 1 ,479     ,282,282,282
BEGIN DESCRIPTION:
Conroe Lake 084 2.5
END DESCRIPTION:
XS GIS Cut Line= 3
      3748338.55     10193939.17      3748076.38     10193496.83
      3747346.17     10193556.01
#Sta/Elev= 30
  4520.7  262.84  4541.7   263.6  4672.3  261.29    4725  262.95  4739.3  262.41
  4797.5  263.42  4820.5  262.85  4878.8  259.32  4890.6   257.8  4949.1  254.78
  4995.1  253.86  5005.5  250.46  5029.5  253.31  5063.5  255.87  5113.7  256.07
  5133.7  254.98  5163.8  256.11    5224  253.64  5234.1  255.72  5244.1  255.98
  5271.1  255.63  5276.1  254.54  5304.3  256.26  5375.8  257.22  5393.2     258
  5414.7  257.21  5545.1   260.1  5565.2   259.7  5665.5  262.22  5767.5  262.07
#Mann= 4 ,-1 , 0
  4520.7     .17       0  4995.1     .09       0  5029.5     .17       0
  5375.8     .17       0
#XS Ineff= 2 , 0
       0  4913.7   257.1  5393.2       0     258
Permanent Ineff=
       F       F
Bank Sta=4995.1,5029.5
XS Rating Curve= 0 ,0
Exp/Cntr=0.3,0.1

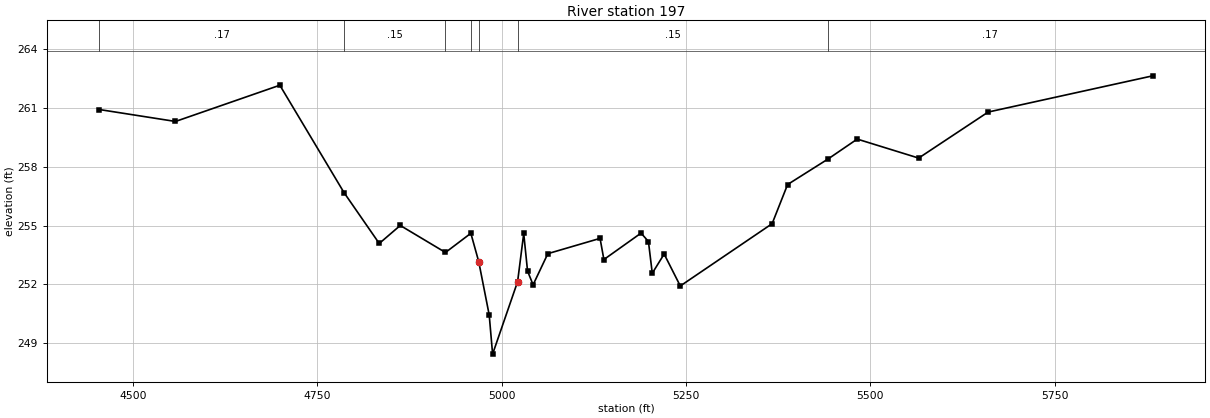
Type RM Length L Ch R = 1 ,197     ,0,0,0
BEGIN DESCRIPTION:
Conroe Lake 084 1.5
END DESCRIPTION:
XS GIS Cut Line= 3
      3748600.71     10193644.04      3748188.64     10193286.43
      3747344.37     10193544.73
#Sta/Elev= 30
  4454.4  260.93  4557.8  260.32  4699.3  262.17  4786.3  256.69  4834.1  254.09
  4862.6  255.01  4923.9  253.63  4958.3  254.61    4969  253.16  4983.2  250.44
  4987.8  248.44  5021.7  252.14    5030   254.6  5035.2  252.68  5042.7  251.98
  5062.7  253.57  5133.5  254.35  5138.7  253.27  5189.1  254.62  5199.1  254.19
  5204.3  252.57  5220.4  253.55  5242.3  251.92  5366.8   255.1  5387.8   257.1
  5442.5   258.4  5482.2  259.42  5565.5  258.45  5659.7   260.8  5882.9  262.65
#Mann= 7 ,-1 , 0
  4454.4     .17       0  4786.3     .15       0  4923.9     .17       0
  4958.3     .15       0    4969     .09       0  5021.7     .15       0
  5442.5     .17       0
Bank Sta=4969,5021.7
XS Rating Curve= 0 ,0
Exp/Cntr=0.3,0.1

Chan Stop Cuts=-1
Use User Specified Reach Order=0
Composite Channel Slope=5