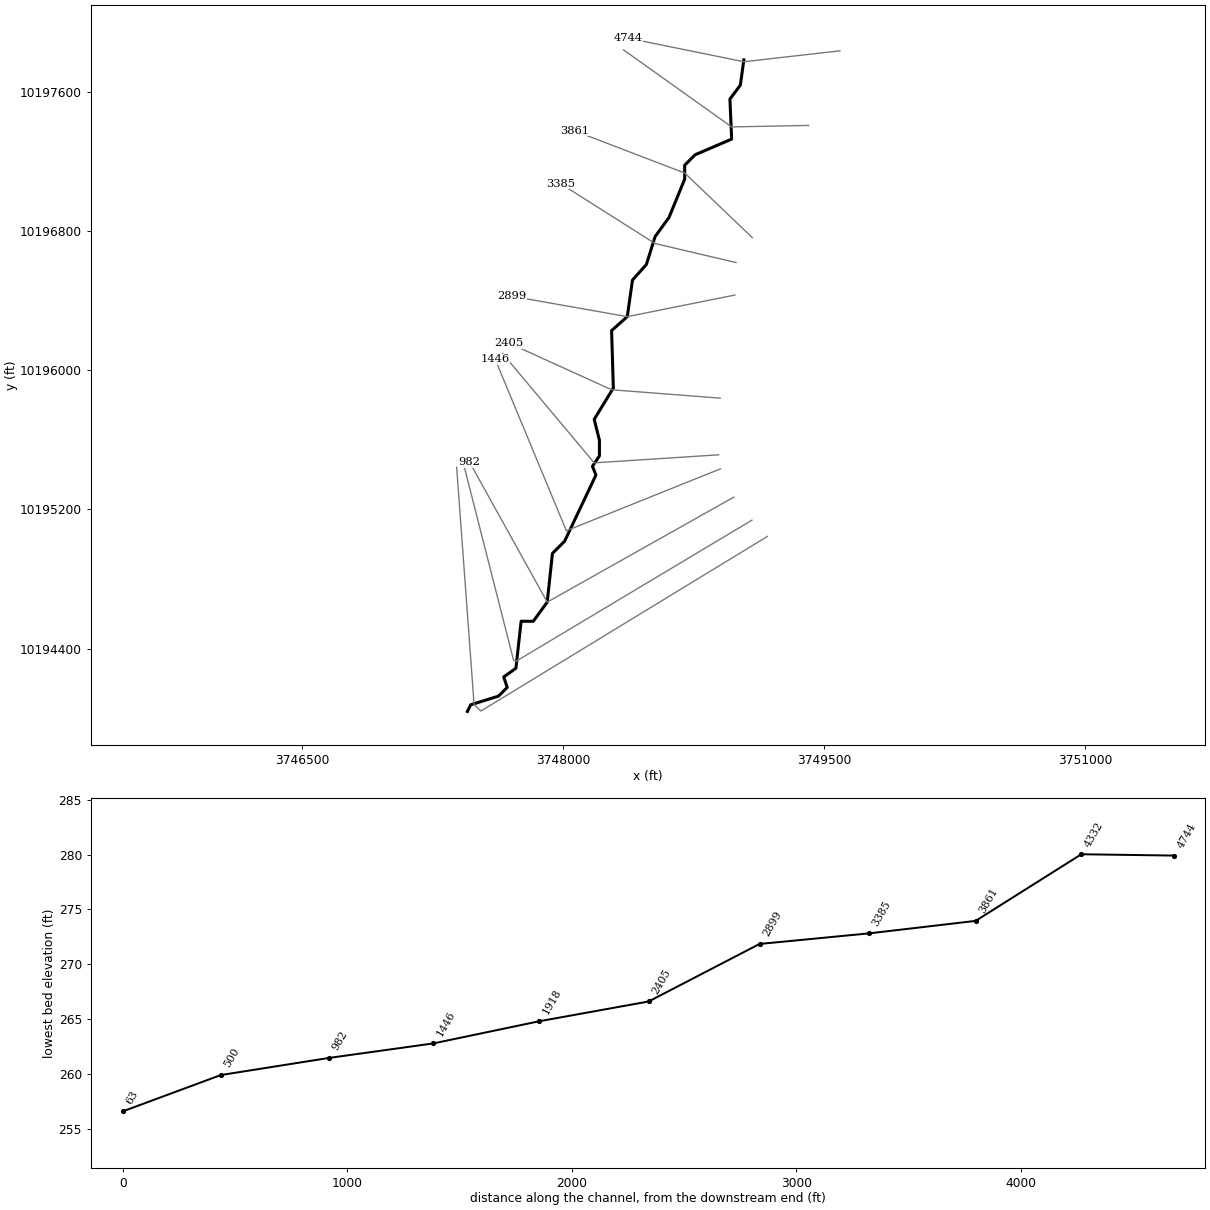
--- Conroe Lake 085.prj (project) ---

Proj Title=Conroe Lake 085 Base Level Engineering
Current Plan=p01
Default Exp/Contr=0.3,0.1
English Units
Geom File=g01
Flow File=f01
Flow File=f02
Plan File=p01
Y Axis Title=Elevation
X Axis Title(PF)=Main Channel Distance
X Axis Title(XS)=Station
BEGIN DESCRIPTION:
Conroe Lake 085
END DESCRIPTION:
DSS Export Rating Curves= 0
DSS Export Rating Curve Sorted= 0
DSS Export Volume Flow Curves= 0
DXF OffsetX= 0
DXF OffsetY= 0
DXF ScaleX= 1
DXF ScaleY= 10

--- Conroe Lake 085.p01 (plan) ---

Plan Title=Multiple Run
Short Identifier=Multiple
Geom File=g01
Flow File=f01
Subcritical Flow
K Sum by GR= 0
Std Step Tol= 0.01
Critical Tol= 0.01
Num of Std Step Trials= 20
Max Error Tol= 0.3
Flow Tol Ratio= 0.001
Split Flow NTrial= 30
Split Flow Tol= 0.02
Split Flow Ratio= 0.02
Log Output Level= 0
Friction Slope Method= 1
Unsteady Friction Slope Method= 2
Unsteady Bridges Friction Slope Method= 1
Parabolic Critical Depth
Global Vel Dist=  1 , 1 , 1
Global Log Level= 0
CheckData=True
Encroach Param= -1, 0, 0, 0
BEGIN DESCRIPTION:
Multiple Run
END DESCRIPTION:

--- Conroe Lake 085.f01 (steady flow) ---

Flow Title=Multiple
Program Version=4.10
Number of Profiles= 7
Profile Names=10-year,25-year,50-year,1pct_min,100-year,1pct_plu,500-year
River Rch & RM=Conroe Lake 085,Reach-1         ,4744
     532     716     963     427    1290    3896    2389
River Rch & RM=Conroe Lake 085,Reach-1         ,3385
     619     839    1136     506    1529    4618    2860
Boundary for River Rch & Prof#=Conroe Lake 085,Reach-1         , 1
Up Type= 0
Dn Type= 3
Dn Slope=0.011
Boundary for River Rch & Prof#=Conroe Lake 085,Reach-1         , 2
Up Type= 0
Dn Type= 3
Dn Slope=0.011
Boundary for River Rch & Prof#=Conroe Lake 085,Reach-1         , 3
Up Type= 0
Dn Type= 3
Dn Slope=0.011
Boundary for River Rch & Prof#=Conroe Lake 085,Reach-1         , 4
Up Type= 0
Dn Type= 3
Dn Slope=0.011
Boundary for River Rch & Prof#=Conroe Lake 085,Reach-1         , 5
Up Type= 0
Dn Type= 3
Dn Slope=0.011
Boundary for River Rch & Prof#=Conroe Lake 085,Reach-1         , 6
Up Type= 0
Dn Type= 3
Dn Slope=0.011
Boundary for River Rch & Prof#=Conroe Lake 085,Reach-1         , 7
Up Type= 0
Dn Type= 3
Dn Slope=0.011
DSS Import GetInterval= 0
DSS Import GetPeak= 0
DSS Import FillOption= 0

--- Conroe Lake 085.f02 (steady flow) ---

Flow Title=Orig_BLE_Flow
Program Version=4.10
Number of Profiles= 7
Profile Names=10-year,25-year,50-year,1pct_min,100-year,1pct_plu,500-year
River Rch & RM=Conroe Lake 085,Reach-1         ,4744
     532     702     837     329     992    2996    1389
River Rch & RM=Conroe Lake 085,Reach-1         ,3385
     619     823     988     389    1176    3551    1663
Boundary for River Rch & Prof#=Conroe Lake 085,Reach-1         , 1
Up Type= 0
Dn Type= 3
Dn Slope=0.0085
Boundary for River Rch & Prof#=Conroe Lake 085,Reach-1         , 2
Up Type= 0
Dn Type= 3
Dn Slope=0.0085
Boundary for River Rch & Prof#=Conroe Lake 085,Reach-1         , 3
Up Type= 0
Dn Type= 3
Dn Slope=0.0085
Boundary for River Rch & Prof#=Conroe Lake 085,Reach-1         , 4
Up Type= 0
Dn Type= 3
Dn Slope=0.0085
Boundary for River Rch & Prof#=Conroe Lake 085,Reach-1         , 5
Up Type= 0
Dn Type= 3
Dn Slope=0.0085
Boundary for River Rch & Prof#=Conroe Lake 085,Reach-1         , 6
Up Type= 0
Dn Type= 3
Dn Slope=0.0085
Boundary for River Rch & Prof#=Conroe Lake 085,Reach-1         , 7
Up Type= 0
Dn Type= 3
Dn Slope=0.0085
DSS Import GetInterval= 0
DSS Import GetPeak= 0
DSS Import FillOption= 0

--- Conroe Lake 085.g01 (geometry) ---

Geom Title=Existing Conditions
Program Version=4.10

River Reach=Conroe Lake 085 ,Reach-1
Reach XY= 30
      3749038.23     10197781.84      3749018.23     10197636.84
      3748958.23     10197556.84      3748968.23     10197326.84
      3748758.23     10197236.84      3748698.23     10197176.84
      3748698.23     10197096.84      3748608.23     10196876.84
      3748528.23     10196766.84      3748478.23     10196606.84
      3748398.23     10196516.84      3748368.23     10196306.84
      3748278.23     10196226.84      3748288.23     10195896.84
      3748178.23     10195716.84      3748208.23     10195596.84
      3748208.23     10195506.84      3748168.23     10195446.84
      3748188.23     10195396.84      3748008.23     10195016.84
      3747938.23     10194946.84      3747908.23     10194666.84
      3747828.23     10194556.84      3747758.23     10194556.84
      3747728.23     10194286.84      3747658.23     10194236.84
      3747678.23     10194176.84      3747628.23     10194126.84
      3747468.23     10194076.84      3747449.46     10194038.59

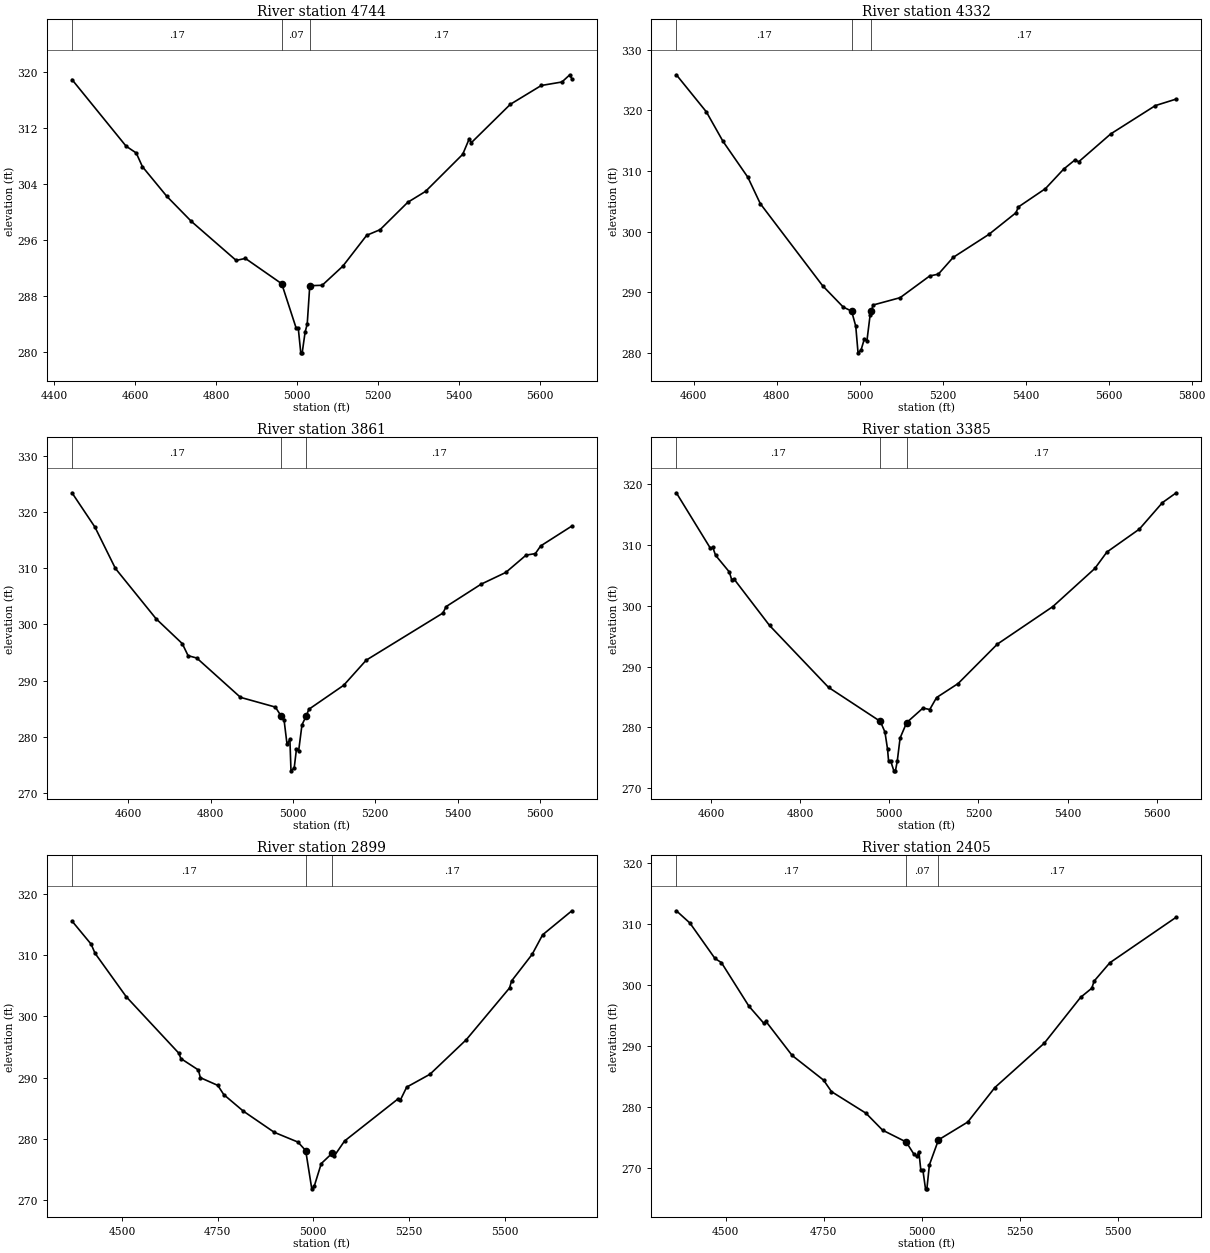
Type RM Length L Ch R = 1 ,4744    ,412,412,412
BEGIN DESCRIPTION:
Conroe Lake 085 8.5
END DESCRIPTION:
XS GIS Cut Line= 3
       3749590.6      10197833.9      3749038.23     10197771.39
      3748373.88     10197906.27
#Sta/Elev= 30
  4444.1  318.95  4577.7  309.43  4602.7  308.46    4618   306.5  4678.3  302.26
  4738.7  298.69  4849.4  293.11    4872   293.4  4961.8  289.78  4997.7  283.39
  5002.7  283.39  5008.8  279.91  5012.3  279.91  5019.6  282.91  5024.7     284
    5031   289.5  5061.6  289.56  5112.6  292.29  5171.5   296.7  5204.5   297.5
  5272.8  301.41  5316.7  302.97  5408.5  308.27  5424.7   310.5  5429.8  309.93
    5526  315.41  5602.4   318.1  5653.4   318.6  5672.8  319.63  5677.9  319.04
#Mann= 3 , 0 , 0
  4444.1     .17       0  4961.8     .07       0    5031     .17       0
Bank Sta=4961.8,5031
XS Rating Curve= 0 ,0
Exp/Cntr=0.3,0.1

Type RM Length L Ch R = 1 ,4332    ,471,471,471
BEGIN DESCRIPTION:
Conroe Lake 085 8.0
END DESCRIPTION:
XS GIS Cut Line= 3
      3749410.15     10197405.42      3748968.23     10197396.84
      3748346.82     10197839.42
#Sta/Elev= 30
    4558  325.86  4630.3  319.75  4670.3   314.9  4730.3  308.97  4760.3  304.62
  4910.4   291.1  4960.4  287.56  4980.4  286.91  4990.4  284.42  4995.9  280.03
  5003.3  280.53  5011.3  282.36  5017.4  282.05    5025  286.25 5027.98  286.91
  5032.1  287.91  5097.3  289.12  5168.6   292.7  5189.5     293  5225.2  295.76
  5311.2  299.55  5376.4  303.11  5382.5  304.08  5447.7   307.1  5491.5  310.31
    5519  311.84  5527.6  311.51  5605.1  316.12  5712.5  320.78  5762.9  321.86
#Mann= 3 , 0 , 0
    4558     .17       0  4980.4     .07       0 5027.98     .17       0
Bank Sta=4980.4,5027.98
XS Rating Curve= 0 ,0
Exp/Cntr=0.3,0.1

Type RM Length L Ch R = 1 ,3861    ,476,476,476
BEGIN DESCRIPTION:
Conroe Lake 085 7.0
END DESCRIPTION:
XS GIS Cut Line= 3
       3749086.8     10196760.89      3748698.23     10197132.12
      3748064.95     10197374.29
#Sta/Elev= 30
  4462.6  323.38  4518.5  317.27  4568.2  309.93  4667.2  300.98  4730.8  296.57
  4744.9  294.43    4766  294.01  4872.3  287.02  4957.2  285.29  4971.4  283.66
  4978.3  282.97  4985.5  278.67  4992.4  279.57  4995.1  273.96  5002.9  274.46
  5008.4  277.85  5013.8  277.55  5021.8  282.14  5032.5  283.77  5038.5   284.9
  5123.3  289.17    5178  293.63  5364.4     302  5372.4  303.16  5457.2  307.13
  5517.3  309.22  5566.7   312.3  5589.2  312.57  5602.1  313.93    5678  317.47
#Mann= 3 , 0 , 0
  4462.6     .17       0  4971.4     .07       0  5032.5     .17       0
Bank Sta=4971.4,5032.5
XS Rating Curve= 0 ,0
Exp/Cntr=0.3,0.1

Type RM Length L Ch R = 1 ,3385    ,486,486,486
BEGIN DESCRIPTION:
Conroe Lake 085 6.0
END DESCRIPTION:
XS GIS Cut Line= 3
      3748993.49     10196617.66      3748528.23     10196726.84
      3747984.39     10197071.21
#Sta/Elev= 30
  4522.1  318.61  4598.7  309.45  4603.8  309.64  4610.1  308.32  4640.9  305.58
  4646.2  304.31  4651.4  304.42  4731.1  296.77  4863.5  286.57  4979.8  280.96
  4990.1  279.21  4995.9   276.4  4998.3  274.39  5003.2  274.39  5010.1  272.82
  5013.6  272.82  5017.7  274.39  5024.1  278.23  5038.9  280.77  5075.4  283.16
  5090.6  282.92  5105.9  284.89  5154.3   287.2  5242.3  293.69  5366.9  299.88
    5461  306.15  5488.1  308.86    5561  312.64  5612.7     317  5643.7  318.62
#Mann= 3 , 0 , 0
  4522.1     .17       0  4979.8     .07       0  5038.9     .17       0
Bank Sta=4979.8,5038.9
XS Rating Curve= 0 ,0
Exp/Cntr=0.3,0.1

Type RM Length L Ch R = 1 ,2899    ,494,494,494
BEGIN DESCRIPTION:
Conroe Lake 085 5.0
END DESCRIPTION:
XS GIS Cut Line= 3
      3748986.99     10196431.03      3748368.23     10196306.84
      3747702.54     10196424.46
#Sta/Elev= 30
  4368.9  315.54    4419  311.76  4429.2  310.28  4510.8  303.19  4648.3  293.98
  4653.6  293.11  4699.3  291.25  4704.6  289.99  4750.2  288.73  4765.8  287.23
  4816.8  284.54  4897.8  281.08  4959.6  279.49    4980  278.11  4995.9  271.86
  5002.7  272.36  5020.7  275.98  5049.6  277.69  5054.6  277.21  5081.6  279.66
  5222.1  286.56  5227.2   286.3  5244.1  288.45    5305  290.55  5399.7  296.17
    5513  304.62  5518.3  305.76  5572.2  310.11  5599.5  313.29    5676  317.21
#Mann= 3 , 0 , 0
  4368.9     .17       0    4980     .07       0  5049.6     .17       0
Bank Sta=4980,5049.6
XS Rating Curve= 0 ,0
Exp/Cntr=0.3,0.1

Type RM Length L Ch R = 1 ,2405    ,487,487,487
BEGIN DESCRIPTION:
Conroe Lake 085 4.0
END DESCRIPTION:
XS GIS Cut Line= 3
      3748902.37     10195838.58      3748278.23     10195886.84
      3747687.08     10196155.41
#Sta/Elev= 30
    4374  312.15  4408.6  310.14  4472.5  304.34  4488.9  303.67  4559.1  296.53
  4597.5   293.7  4602.6  294.03  4669.4  288.46  4749.6  284.42  4769.7  282.54
  4857.6  279.01  4900.1  276.23  4960.3  274.29  4980.3  272.27  4987.7  271.94
  4992.7  272.71  4997.7  269.65    5003  269.65  5009.6  266.62  5013.1  266.62
  5019.6  270.56  5042.7  274.64  5117.4  277.56  5186.6  283.21  5312.9  290.49
  5405.2  297.97  5433.8  299.47  5439.8  300.64  5479.9  303.64  5649.3   311.1
#Mann= 3 , 0 , 0
    4374     .17       0  4960.3     .07       0  5042.7     .17       0
Bank Sta=4960.3,5042.7
XS Rating Curve= 0 ,0
Exp/Cntr=0.3,0.1

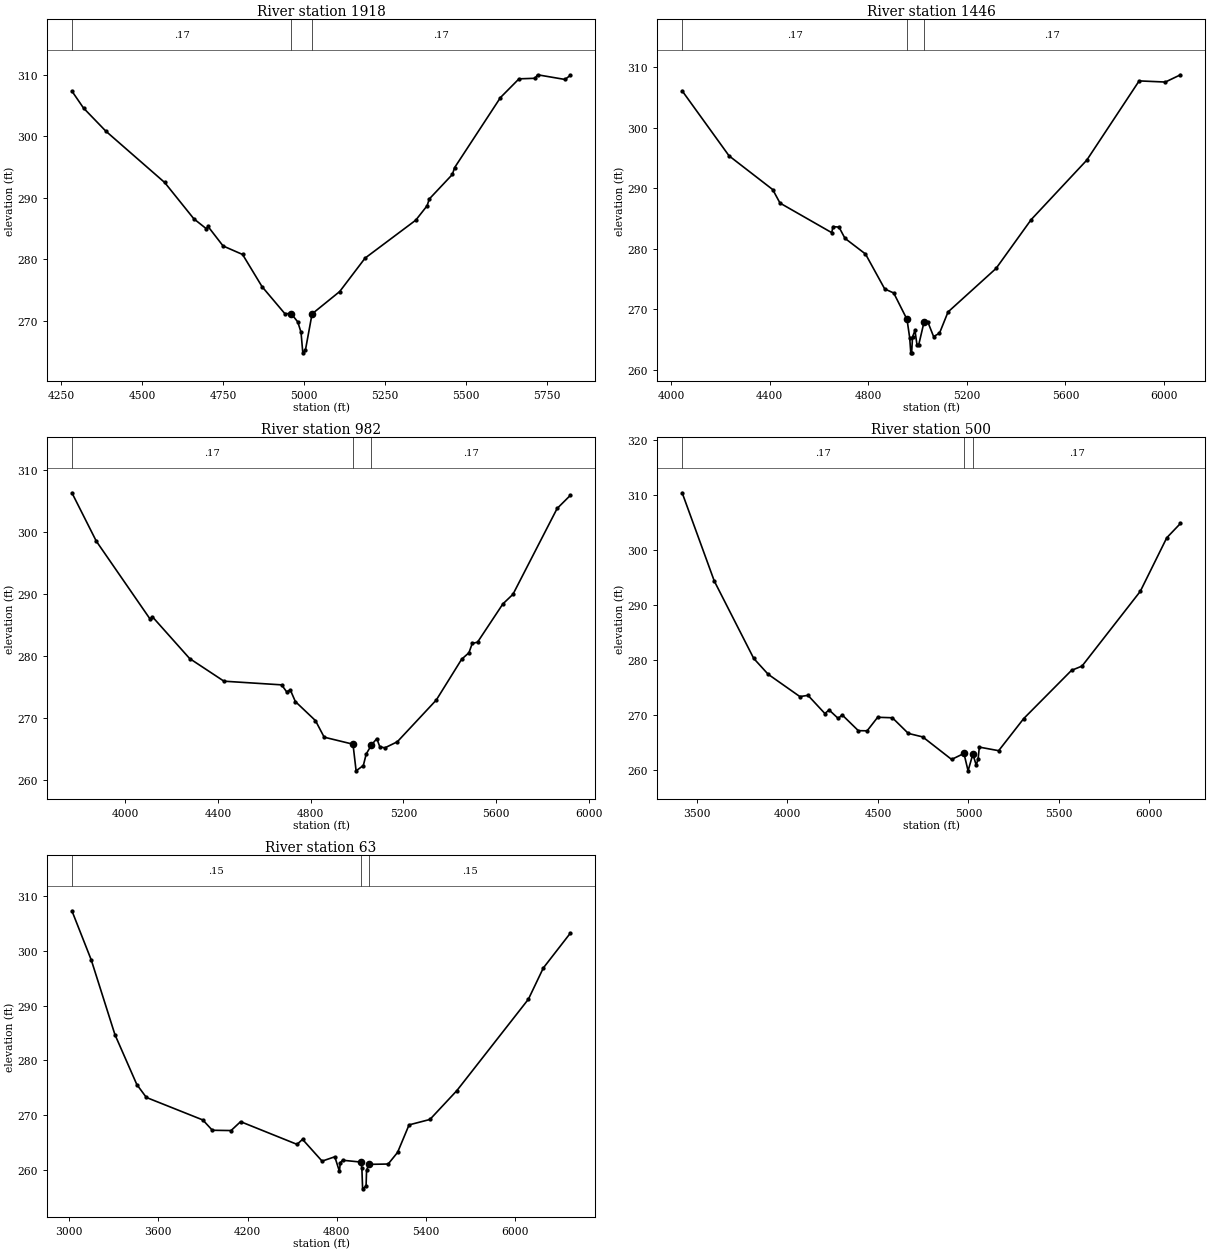
Type RM Length L Ch R = 1 ,1918    ,472,472,472
BEGIN DESCRIPTION:
Conroe Lake 085 3.0
END DESCRIPTION:
XS GIS Cut Line= 3
      3748893.64     10195513.05      3748178.23     10195466.84
      3747650.51     10196096.42
#Sta/Elev= 30
  4283.1  307.37    4319  304.61  4387.8  300.86  4569.5  292.51  4659.7   286.6
  4698.2  284.99  4703.2  285.37  4749.9  282.19    4810  280.81  4870.1  275.58
  4940.3   271.2  4960.3  271.18  4980.3  269.85  4990.4  268.17  4995.9  264.82
  5004.2  265.32  5024.5  271.15  5109.9  274.79  5188.2  280.22  5344.5  286.38
  5379.7  288.73  5386.2  289.82  5457.7  293.82  5464.3  294.91  5606.1  306.32
  5663.3  309.36  5712.8  309.45  5720.6  310.02  5805.1  309.26  5821.5  309.91
#Mann= 3 , 0 , 0
  4283.1     .17       0  4960.3     .07       0  5024.5     .17       0
Bank Sta=4960.3,5024.5
XS Rating Curve= 0 ,0
Exp/Cntr=0.3,0.1

Type RM Length L Ch R = 1 ,1446    ,464,464,464
BEGIN DESCRIPTION:
Conroe Lake 085 2.5
END DESCRIPTION:
XS GIS Cut Line= 3
      3748904.53     10195432.77      3748018.23     10195076.84
      3747608.93     10196062.11
#Sta/Elev= 30
  4044.9  306.07  4235.3  295.33  4412.4  289.76    4442  287.53  4651.7  282.65
  4657.1  283.65  4681.3  283.56  4705.5  281.71  4788.8  279.12  4866.8  273.35
  4903.4  272.68  4957.3  268.32  4968.1  265.29  4972.6   262.8  4976.1   262.8
  4979.7  265.44  4989.6   266.5  4997.5  264.17    5005  264.17  5026.2  267.86
  5041.3  267.94  5065.1  265.49    5089  266.04  5123.7  269.55  5318.6  276.74
    5461   284.8  5686.6  294.62  5899.1  307.71  6005.4  307.52  6066.9  308.72
#Mann= 3 , 0 , 0
  4044.9     .17       0  4957.3     .07       0  5026.2     .17       0
Bank Sta=4957.3,5026.2
XS Rating Curve= 0 ,0
Exp/Cntr=0.3,0.1

Type RM Length L Ch R = 1 ,982     ,482,482,482
BEGIN DESCRIPTION:
Conroe Lake 085 1.0
END DESCRIPTION:
XS GIS Cut Line= 3
      3748980.43     10195269.98      3747908.23     10194666.84
      3747462.09     10195470.52
#Sta/Elev= 30
  3769.8  306.27    3875  298.48  4107.7  285.89    4117   286.3  4277.6  279.57
  4425.7  275.92  4674.3  275.33    4696  274.21  4711.9  274.51  4733.6  272.64
  4820.3  269.57  4857.9   266.9  4982.2  265.77  4995.6  261.48  5026.8  262.34
  5039.1  264.18    5062  265.66  5084.9  266.67  5097.8  265.36  5119.5  265.18
  5173.3  266.16  5341.5  272.89  5450.9  279.46  5482.2   280.5  5496.6     282
  5519.5  282.21  5628.7  288.37  5672.2  289.92  5862.6  303.74  5919.2  305.84
#Mann= 3 , 0 , 0
  3769.8     .17       0  4982.2     .07       0    5062     .17       0
Bank Sta=4982.2,5062
XS Rating Curve= 0 ,0
Exp/Cntr=0.3,0.1

Type RM Length L Ch R = 1 ,500     ,437,437,437
BEGIN DESCRIPTION:
Conroe Lake 085 1.5
END DESCRIPTION:
XS GIS Cut Line= 4
      3749084.61     10195137.61       3747727.3     10194325.91
      3747714.33     10194334.17      3747428.81     10195454.49
#Sta/Elev= 30
  3418.5  310.43  3596.1  294.39  3813.9  280.34  3893.7  277.46  4068.8  273.41
  4113.8  273.63    4207  270.33  4230.3  270.98  4280.8  269.43  4302.2  270.09
  4391.7  267.22  4440.3  267.19  4498.6  269.65  4579.9  269.56  4667.9  266.72
  4747.6  266.08  4907.1  261.99  4975.2  263.08  4998.1  259.92  5024.5  262.97
  5043.1  260.94  5053.5  262.11  5060.2  264.23    5167  263.58  5305.5  269.42
  5569.4  278.17  5627.5  278.95  5949.4  292.53  6095.7  302.26  6171.5  304.87
#Mann= 3 , 0 , 0
  3418.5     .17       0  4975.2     .07       0  5024.5     .17       0
Bank Sta=4975.2,5024.5
XS Rating Curve= 0 ,0
Exp/Cntr=0.3,0.1

Type RM Length L Ch R = 1 ,63      ,0,0,0
BEGIN DESCRIPTION:
Conroe Lake 085 2.0
END DESCRIPTION:
XS GIS Cut Line= 4
      3749173.62     10195044.31      3747527.27      10194041.2
      3747487.92     10194077.43      3747387.58     10195441.48
#Sta/Elev= 30
  3019.5  307.27  3149.9  298.29  3308.8   284.7  3455.9  275.61  3519.9  273.26
  3899.4  269.16  3963.4  267.28  4089.2  267.23  4153.2  268.85  4532.7  264.71
  4569.5  265.63  4700.8  261.66  4786.4  262.45  4817.4  259.79  4823.2  261.36
  4838.7  261.82  4960.8  261.49  4968.2  260.44  4973.2  256.61  4996.5  257.12
  4999.9  259.99  5014.5  261.07  5144.9  261.13  5208.2  263.25  5285.3  268.26
  5425.6  269.25  5606.1  274.49  6087.4  291.16  6187.7  296.85  6368.6  303.17
#Mann= 3 , 0 , 0
  3019.5     .15       0  4960.8     .06       0  5014.5     .15       0
Bank Sta=4960.8,5014.5
XS Rating Curve= 0 ,0
Exp/Cntr=0.3,0.1

Chan Stop Cuts=-1
Use User Specified Reach Order=0
Composite Channel Slope=5