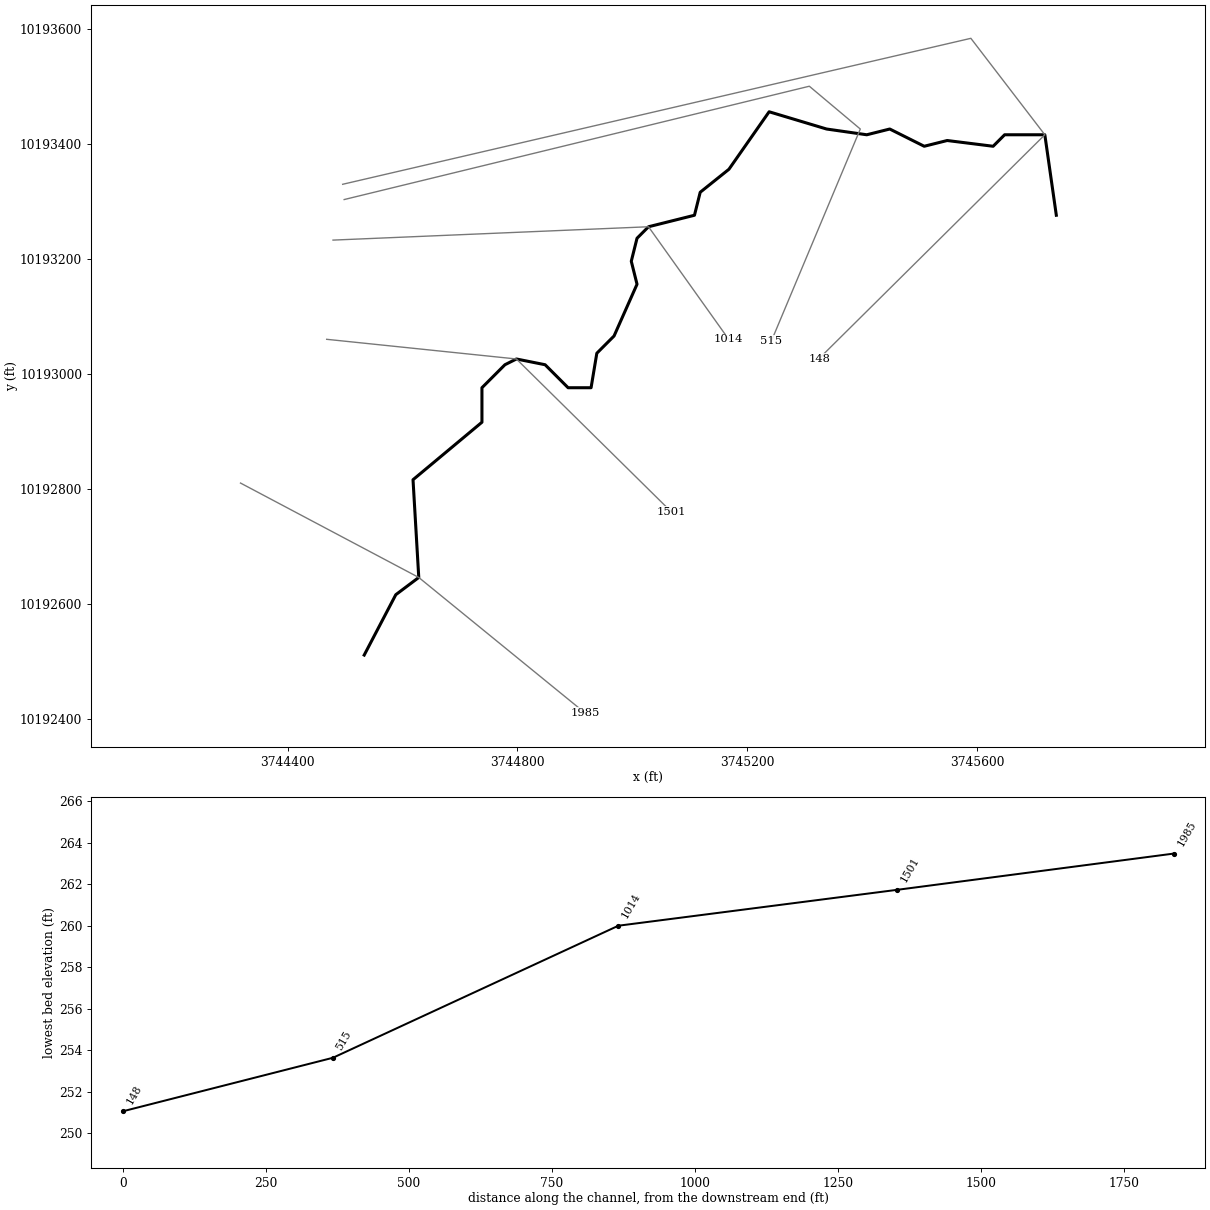
--- Conroe Lake 086.prj (project) ---

Proj Title=Conroe Lake 086 Base Level Engineering
Current Plan=p01
Default Exp/Contr=0.3,0.1
English Units
Geom File=g01
Flow File=f01
Flow File=f02
Plan File=p01
Y Axis Title=Elevation
X Axis Title(PF)=Main Channel Distance
X Axis Title(XS)=Station
BEGIN DESCRIPTION:
Conroe Lake 086
END DESCRIPTION:
DSS Export Rating Curves= 0
DSS Export Rating Curve Sorted= 0
DSS Export Volume Flow Curves= 0
DXF OffsetX= 0
DXF OffsetY= 0
DXF ScaleX= 1
DXF ScaleY= 10

--- Conroe Lake 086.p01 (plan) ---

Plan Title=Multiple Run
Short Identifier=Multiple
Geom File=g01
Flow File=f01
Subcritical Flow
K Sum by GR= 0
Std Step Tol= 0.01
Critical Tol= 0.01
Num of Std Step Trials= 20
Max Error Tol= 0.3
Flow Tol Ratio= 0.001
Split Flow NTrial= 30
Split Flow Tol= 0.02
Split Flow Ratio= 0.02
Log Output Level= 0
Friction Slope Method= 1
Unsteady Friction Slope Method= 2
Unsteady Bridges Friction Slope Method= 1
Parabolic Critical Depth
Global Vel Dist=  1 , 1 , 1
Global Log Level= 0
CheckData=True
Encroach Param= -1, 0, 0, 0
BEGIN DESCRIPTION:
Multiple Run
END DESCRIPTION:

--- Conroe Lake 086.f01 (steady flow) ---

Flow Title=Multiple
Program Version=4.10
Number of Profiles= 7
Profile Names=10-year,25-year,50-year,1pct_min,100-year,1pct_plu,500-year
River Rch & RM=Conroe Lake 086,Reach-1         ,1985
     428     566     754     331    1000    3020    1813
River Rch & RM=Conroe Lake 086,Reach-1         ,148
    4200    6121    8685    4025   12156   36711   24665
Boundary for River Rch & Prof#=Conroe Lake 086,Reach-1         , 1
Up Type= 0
Dn Type= 3
Dn Slope=0.005
Boundary for River Rch & Prof#=Conroe Lake 086,Reach-1         , 2
Up Type= 0
Dn Type= 3
Dn Slope=0.005
Boundary for River Rch & Prof#=Conroe Lake 086,Reach-1         , 3
Up Type= 0
Dn Type= 3
Dn Slope=0.005
Boundary for River Rch & Prof#=Conroe Lake 086,Reach-1         , 4
Up Type= 0
Dn Type= 3
Dn Slope=0.005
Boundary for River Rch & Prof#=Conroe Lake 086,Reach-1         , 5
Up Type= 0
Dn Type= 3
Dn Slope=0.005
Boundary for River Rch & Prof#=Conroe Lake 086,Reach-1         , 6
Up Type= 0
Dn Type= 3
Dn Slope=0.005
Boundary for River Rch & Prof#=Conroe Lake 086,Reach-1         , 7
Up Type= 0
Dn Type= 3
Dn Slope=0.005
DSS Import GetInterval= 0
DSS Import GetPeak= 0
DSS Import FillOption= 0

--- Conroe Lake 086.f02 (steady flow) ---

Flow Title=Orig_BLE_Flow
Program Version=4.10
Number of Profiles= 7
Profile Names=10-year,25-year,50-year,1pct_min,100-year,1pct_plu,500-year
River Rch & RM=Conroe Lake 086,Reach-1         ,1985
     428     555     656     255     769    2321    1054
River Rch & RM=Conroe Lake 086,Reach-1         ,148
    4200    6001    7552    3097    9351   28240   14340
Boundary for River Rch & Prof#=Conroe Lake 086,Reach-1         , 1
Up Type= 0
Dn Type= 3
Dn Slope=0.005
Boundary for River Rch & Prof#=Conroe Lake 086,Reach-1         , 2
Up Type= 0
Dn Type= 3
Dn Slope=0.005
Boundary for River Rch & Prof#=Conroe Lake 086,Reach-1         , 3
Up Type= 0
Dn Type= 3
Dn Slope=0.005
Boundary for River Rch & Prof#=Conroe Lake 086,Reach-1         , 4
Up Type= 0
Dn Type= 3
Dn Slope=0.005
Boundary for River Rch & Prof#=Conroe Lake 086,Reach-1         , 5
Up Type= 0
Dn Type= 3
Dn Slope=0.005
Boundary for River Rch & Prof#=Conroe Lake 086,Reach-1         , 6
Up Type= 0
Dn Type= 3
Dn Slope=0.005
Boundary for River Rch & Prof#=Conroe Lake 086,Reach-1         , 7
Up Type= 0
Dn Type= 3
Dn Slope=0.005
DSS Import GetInterval= 0
DSS Import GetPeak= 0
DSS Import FillOption= 0

--- Conroe Lake 086.g01 (geometry) ---

Geom Title=Existing Conditions
Program Version=4.10

River Reach=Conroe Lake 086 ,Reach-1
Reach XY= 30
      3744533.23     10192511.84      3744588.23     10192616.84
      3744628.23     10192646.84      3744618.23     10192816.84
      3744738.23     10192916.84      3744738.23     10192976.84
      3744778.23     10193016.84      3744798.23     10193026.84
      3744848.23     10193016.84      3744888.23     10192976.84
      3744928.23     10192976.84      3744938.23     10193036.84
      3744968.23     10193066.84      3745008.23     10193156.84
      3744998.23     10193196.84      3745008.23     10193236.84
      3745028.23     10193256.84      3745108.23     10193276.84
      3745118.23     10193316.84      3745168.23     10193356.84
      3745238.23     10193456.84      3745338.23     10193426.84
      3745408.23     10193416.84      3745448.23     10193426.84
      3745508.23     10193396.84      3745548.23     10193406.84
      3745628.23     10193396.84      3745648.23     10193416.84
      3745718.23     10193416.84      3745738.23     10193276.84

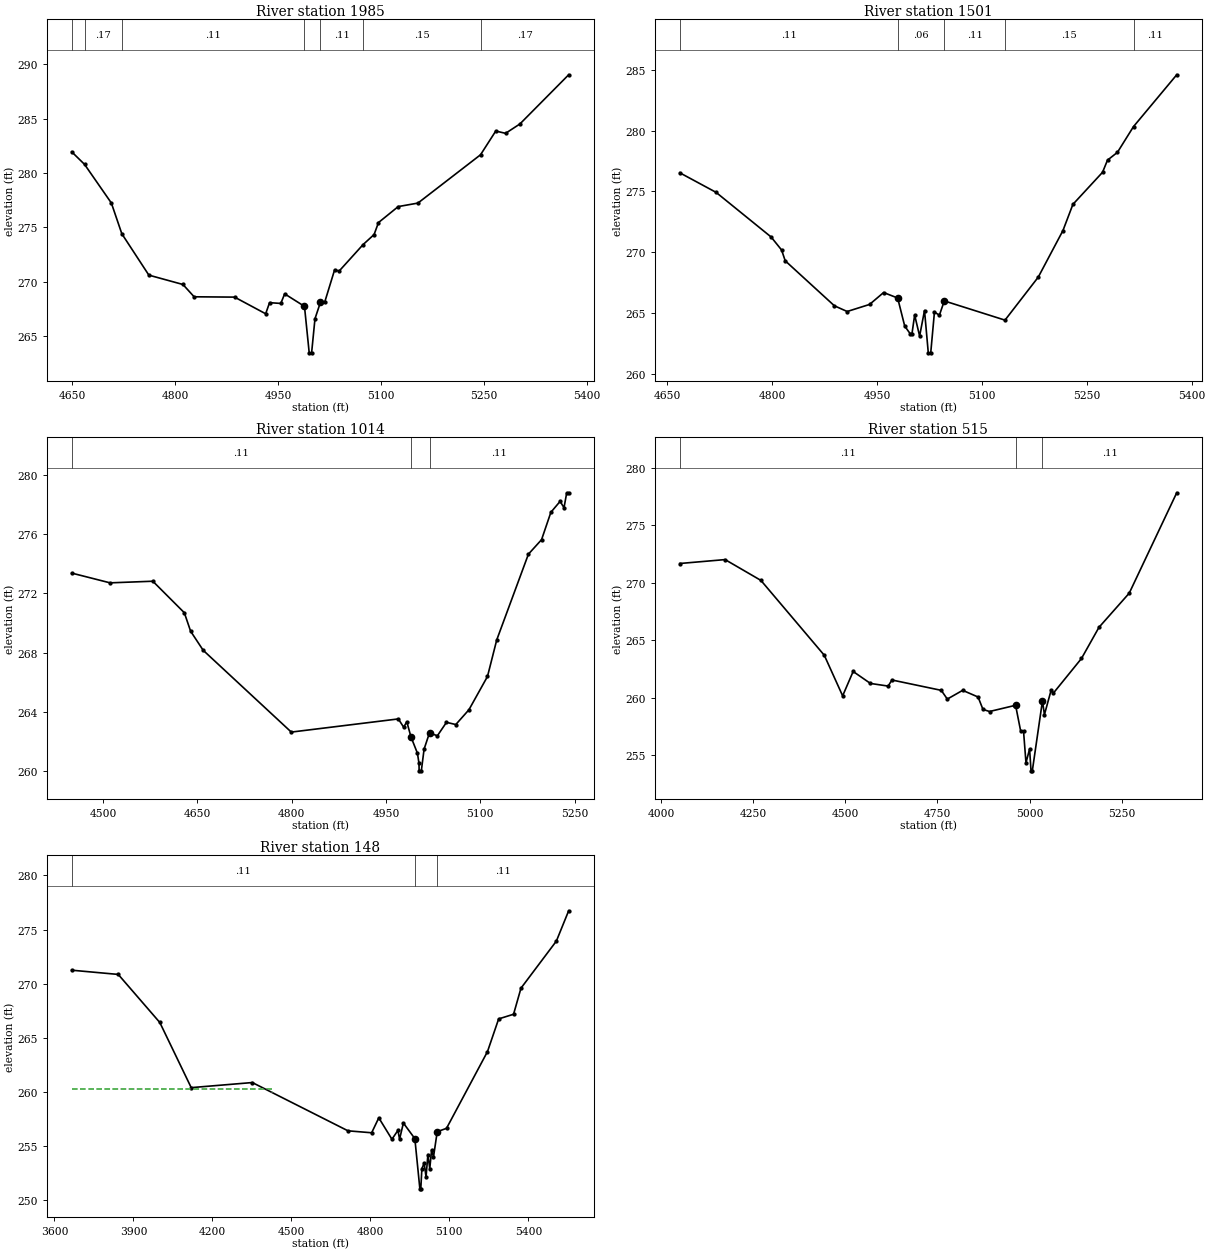
Type RM Length L Ch R = 1 ,1985    ,484,484,484
BEGIN DESCRIPTION:
Conroe Lake 086 4.0
END DESCRIPTION:
XS GIS Cut Line= 3
      3744317.89     10192811.05      3744628.23     10192646.84
      3744917.89     10192411.04
#Sta/Elev= 30
  4648.9  281.95  4667.6   280.8  4706.7  277.25    4722  274.42  4761.4  270.62
  4811.1  269.76  4827.4  268.63  4886.4   268.6  4931.7  267.07  4937.4  268.09
  4953.8  268.02  4959.4   268.9  4988.3  267.75  4995.2  263.48  4998.7  263.48
  5003.6  266.61  5011.5  268.11    5018  268.18  5032.3  271.12  5038.8  270.99
  5073.8  273.43  5089.8  274.35  5096.2  275.45    5125  276.92  5153.7  277.24
    5245  281.68  5267.2  283.86  5281.5  283.65  5302.4  284.51  5373.5  289.03
#Mann= 7 ,-1 , 0
  4648.9     .11       0  4667.6     .17       0    4722     .11       0
  4988.3     .06       0  5011.5     .11       0  5073.8     .15       0
    5245     .17       0
Bank Sta=4988.3,5011.5
XS Rating Curve= 0 ,0
Exp/Cntr=0.3,0.1

Type RM Length L Ch R = 1 ,1501    ,487,487,487
BEGIN DESCRIPTION:
Conroe Lake 086 3.0
END DESCRIPTION:
XS GIS Cut Line= 3
       3744467.9     10193061.07      3744798.23     10193026.84
      3745067.86     10192761.07
#Sta/Elev= 30
  4667.9  276.54  4719.8  274.93  4798.5  271.26  4813.5  270.19  4818.7   269.3
    4889   265.6  4907.3  265.13  4939.3  265.71  4959.4  266.69  4979.5  266.24
  4989.6  263.93  4997.3  263.31    5000  263.31  5003.8  264.84  5010.9  263.11
  5017.9  265.21  5023.3  261.73  5026.8  261.73  5032.1  265.08  5039.2  264.83
  5046.2     266    5133  264.42  5180.6  267.96  5215.9  271.79  5230.1  273.94
  5272.5  276.58  5279.6  277.58  5293.8  278.22  5316.8  280.34  5378.6   284.6
#Mann= 5 ,-1 , 0
  4667.9     .11       0  4979.5     .06       0  5046.2     .11       0
    5133     .15       0  5316.8     .11       0
Bank Sta=4979.5,5046.2
XS Rating Curve= 0 ,0
Exp/Cntr=0.3,0.1

Type RM Length L Ch R = 1 ,1014    ,499,499,499
BEGIN DESCRIPTION:
Conroe Lake 086 2.0
END DESCRIPTION:
XS GIS Cut Line= 3
      3744478.92     10193233.62      3745028.23     10193256.84
      3745167.87     10193061.04
#Sta/Elev= 30
  4450.2  273.37  4511.2  272.71  4579.2  272.82  4629.3  270.69  4639.3  269.44
  4659.3  268.15  4799.4  262.62  4969.6  263.51  4978.1  262.95  4983.1  263.32
  4989.6  262.31    5000  261.19  5002.5   260.5  5002.7     260  5006.2     260
  5010.6  261.47  5019.2  262.57  5031.7  262.37  5046.2  263.28    5061  263.13
  5081.9  264.13  5111.4  266.38  5126.1  268.85  5176.5  274.65  5197.4  275.63
  5212.2  277.48  5226.9  278.22  5233.1  277.79  5237.4   278.8  5240.5   278.8
#Mann= 3 , 0 , 0
  4450.2     .11       0  4989.6     .06       0  5019.2     .11       0
Bank Sta=4989.6,5019.2
XS Rating Curve= 0 ,0
Exp/Cntr=0.3,0.1

Type RM Length L Ch R = 1 ,515     ,367,367,367
BEGIN DESCRIPTION:
Conroe Lake 086 1.0
END DESCRIPTION:
XS GIS Cut Line= 4
      3744498.36     10193304.15      3745308.21     10193501.27
      3745396.93     10193426.84      3745242.39     10193058.66
#Sta/Elev= 30
  4050.7  271.66  4173.7     272  4270.9  270.19  4442.9  263.68  4492.7  260.15
  4521.2  262.27  4568.1  261.23  4616.2     261  4626.5  261.53  4760.3  260.63
  4776.7  259.87  4818.4  260.63  4860.2  260.05  4873.5  258.97  4891.3  258.79
    4962  259.33  4975.9  257.07  4983.6  257.07  4990.2  254.33    5000  255.53
  5003.9  253.63  5007.4  253.63  5034.9  259.71  5040.3  258.52  5058.6  260.66
  5064.1  260.37  5140.8   263.4  5188.3  266.11  5270.4  269.08  5399.3  277.81
#Mann= 3 , 0 , 0
  4050.7     .11       0    4962     .06       0  5034.9     .11       0
#XS Ineff= 2 ,-1
  4521.2  4459.1  262.27  4626.5  4562.9  261.53
Permanent Ineff=
       F       F
Bank Sta=4962,5034.9
XS Rating Curve= 0 ,0
Exp/Cntr=0.3,0.1

Type RM Length L Ch R = 1 ,148     ,0,0,0
BEGIN DESCRIPTION:
Conroe Lake 086 1.5
END DESCRIPTION:
XS GIS Cut Line= 4
      3744495.73      10193330.7      3745589.46      10193584.6
      3745718.23     10193416.84      3745325.27     10193027.61
#Sta/Elev= 30
  3665.7  271.25  3842.4  270.86  4000.3  266.42  4119.6   260.4  4351.7  260.87
    4715  256.41  4804.9  256.23    4832  257.61  4881.9  255.63  4904.6  256.45
  4910.9  255.64  4925.4  257.13  4968.9  255.69    4988  251.05  4991.5  251.05
  4995.6  252.91  5004.3  253.43  5011.4  252.15  5018.5  254.22  5025.6  252.92
  5032.6  254.65  5039.7  253.99  5053.9  256.33  5089.2  256.64  5244.8  263.73
  5287.2  266.75  5343.8  267.18    5372  269.59  5506.4  273.94  5553.1  276.74
#Mann= 3 , 0 , 0
  3665.7     .11       0  4968.9     .06       0  5053.9     .11       0
#XS Ineff= 2 , 0
       0  4427.6  260.23               0
Permanent Ineff=
       F       F
Bank Sta=4968.9,5053.9
XS Rating Curve= 0 ,0
Exp/Cntr=0.3,0.1

Chan Stop Cuts=-1
Use User Specified Reach Order=0
Composite Channel Slope=5