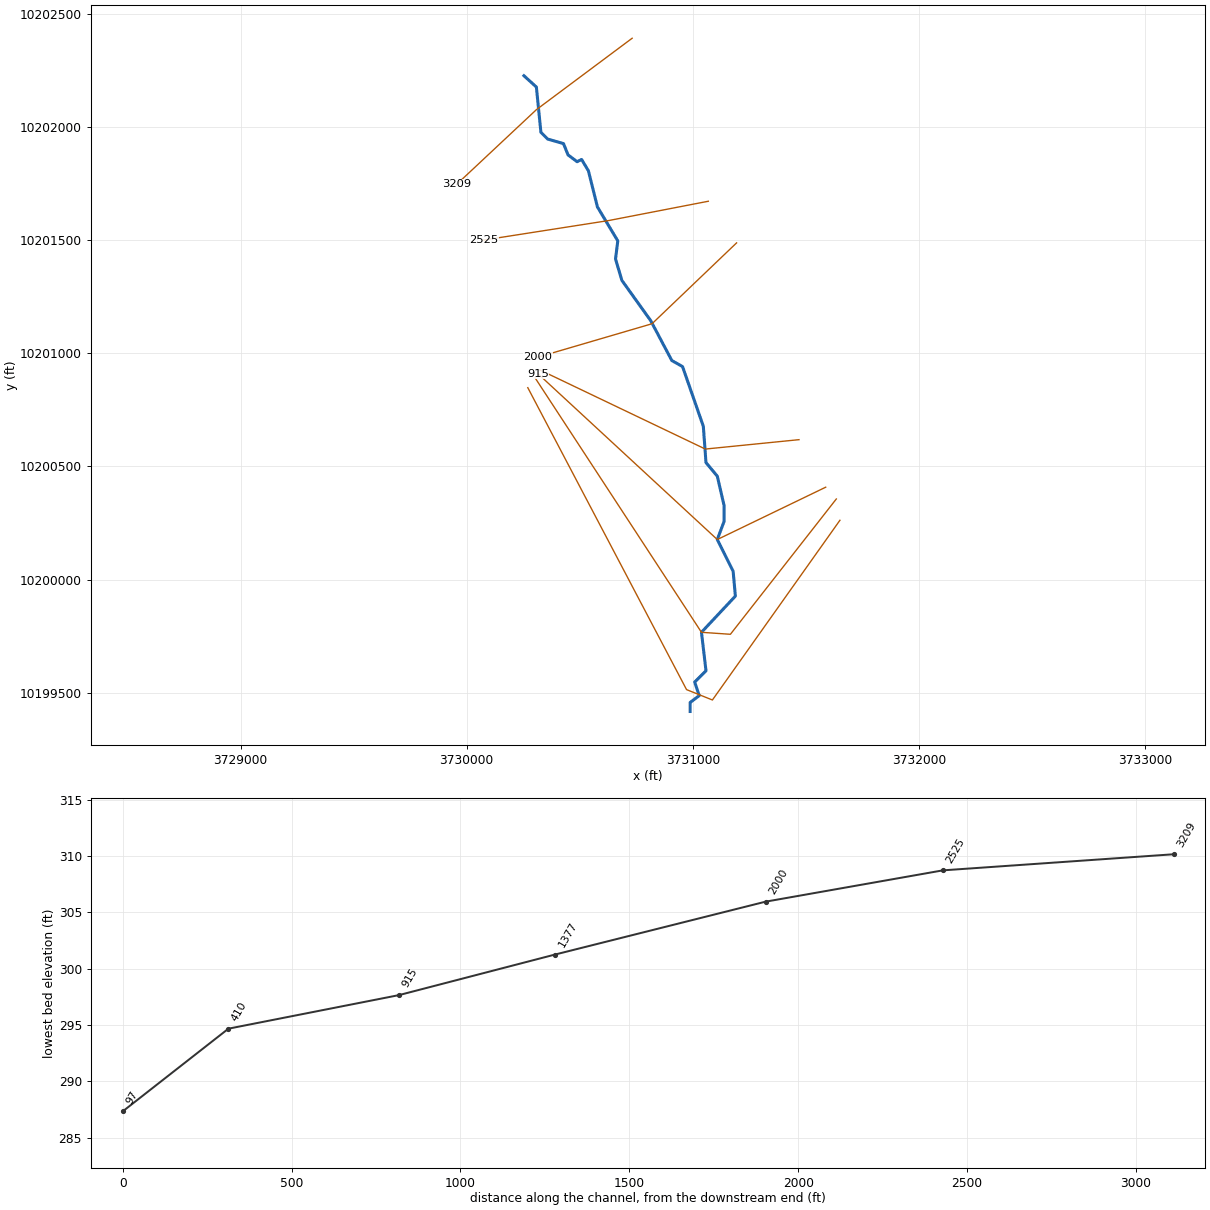
--- Conroe Lake 088.prj (project) ---

Proj Title=Conroe Lake 088 Base Level Engineering
Current Plan=p01
Default Exp/Contr=0.3,0.1
English Units
Geom File=g01
Flow File=f01
Flow File=f02
Plan File=p01
Y Axis Title=Elevation
X Axis Title(PF)=Main Channel Distance
X Axis Title(XS)=Station
BEGIN DESCRIPTION:
Conroe Lake 088
END DESCRIPTION:
DSS File=dss
DSS Export Rating Curves= 0
DSS Export Rating Curve Sorted= 0
DSS Export Volume Flow Curves= 0
DXF OffsetX= 0
DXF OffsetY= 0
DXF ScaleX= 1
DXF ScaleY= 10

--- Conroe Lake 088.p01 (plan) ---

Plan Title=Multiple Run
Program Version=4.10
Short Identifier=Multiple Run
Geom File=g01
Flow File=f01
Subcritical Flow
K Sum by GR= 0
Std Step Tol= 0.01
Critical Tol= 0.01
Num of Std Step Trials= 20
Max Error Tol= 0.3
Flow Tol Ratio= 0.001
Split Flow NTrial= 30
Split Flow Tol= 0.02
Split Flow Ratio= 0.02
Log Output Level= 0
Friction Slope Method= 1
Unsteady Friction Slope Method= 2
Unsteady Bridges Friction Slope Method= 1
Parabolic Critical Depth
Global Vel Dist= 1 , 1 , 1
Global Log Level= 0
CheckData=True
Encroach Param=-1 ,0,0, 0
BEGIN DESCRIPTION:
Multiple Run
END DESCRIPTION:
Computation Interval=1HOUR
Output Interval=1HOUR
Run HTab= 0
Run UNet= 0
Run PostProcess= 0
Run WQNet= 0
UNET Theta= 1
UNET Theta Warmup= 1
UNET ZTol= 0.02
UNET ZSATol= 0.05
UNET MxIter= 20
UNET MaxInSteps= 0
UNET DtIC= 0
UNET DtMin= 0
UNET MaxCRTS= 20
UNET WFStab= 2
UNET SFStab= 1
UNET WFX= 1
UNET SFX= 1
UNET DSS MLevel= 4
UNET DZMax Abort= 100
UNET Convert EG Bridges= 0
UNET Use Existing IB Tables=-1
UNET Froude Reduction=False
UNET Froude Limit= 1
UNET Froude Power= 10
UNET Time Slicing=0,0, 5
UNET Junction Losses=0
Instantaneous Interval=1HOUR
DSS File=dss
Write IC File= 0
Write IC File at Sim End=0
Echo Input=False
Echo Parameters=False
Echo Output=False
Write Detailed= 0
WQ AD Non Conservative
WQ ULTIMATE=-1
WQ Max Comp Step=1HOUR
WQ Output Interval=15MIN
WQ Output Selected Increments= 0
WQ Output face flow=0
WQ Output face velocity=0
WQ Output face area=0
WQ Output face dispersion=0
WQ Output cell volume=0
WQ Output cell surface area=0
WQ Output cell continuity=0
WQ Output cumulative cell continuity=0
WQ Output face conc=0
WQ Output face dconc_dx=0
WQ Output face courant=0
WQ Output face peclet=0
WQ Output face adv mass=0
WQ Output face disp mass=0
WQ Output cell mass=0
WQ Output cell source sink temp=0
WQ Output cell source sink nsm=0
WQ Output MaxMinRange=-1
WQ Daily Max Min Mean=-1
WQ Daily Range=0
WQ Daily Time=0
WQ Create Restart=0
WQ Fixed Restart=0
WQ System Summary=0
WQ Use Fixed Temperature=0
Sorting and Armoring Iterations= 10
XS Update Threshold= 0.02
Hydraulics Update Threshold= 0.02
Energy Slope Method= 1
Volume Change Method= 0
XS Weighting Method= 0
Number of US Weighted Cross Sections= 1
Number of DS Weighted Cross Sections= 1
Upstream XS Weight=0.25
Main XS Weight=0.5
Downstream XS Weight=0.25
Number of DS XS's Weighted with US Boundary= 1
Upstream Boundary Weight= 1
Weight of XSs Associated with US Boundary= 0
Number of US XS's Weighted with DS Boundary= 1
Downstream Boundary Weight= 0.5
Weight of XSs Associated with DS Boundary= 0.5
Sediment Output Level= 4
Mass or Volume Output= 0
Output Increment Type= 1
Profile and TS Output Increment= 10
XS Output Flag= 0
XS Output Increment= 10
Disregard all LS=0
Disregard all Conn=0
Disregard all Breaches=0
Disregard all Pumps=0

--- Conroe Lake 088.f01 (steady flow) ---

Flow Title=Multiple
Program Version=4.10
Number of Profiles= 7
Profile Names=10-year,25-year,50-year,1pct_min,100-year,1pct_plu,500-year
River Rch & RM=Conroe Lake 088,Reach-1         ,3209
     523     705     950     422    1274    3847    2367
River Rch & RM=Conroe Lake 088,Reach-1         ,2525
     603     818    1107     493    1489    4497    2785
Boundary for River Rch & Prof#=Conroe Lake 088,Reach-1         , 1
Up Type= 0
Dn Type= 3
Dn Slope=0.018
Boundary for River Rch & Prof#=Conroe Lake 088,Reach-1         , 2
Up Type= 0
Dn Type= 3
Dn Slope=0.018
Boundary for River Rch & Prof#=Conroe Lake 088,Reach-1         , 3
Up Type= 0
Dn Type= 3
Dn Slope=0.018
Boundary for River Rch & Prof#=Conroe Lake 088,Reach-1         , 4
Up Type= 0
Dn Type= 3
Dn Slope=0.018
Boundary for River Rch & Prof#=Conroe Lake 088,Reach-1         , 5
Up Type= 0
Dn Type= 3
Dn Slope=0.018
Boundary for River Rch & Prof#=Conroe Lake 088,Reach-1         , 6
Up Type= 0
Dn Type= 3
Dn Slope=0.018
Boundary for River Rch & Prof#=Conroe Lake 088,Reach-1         , 7
Up Type= 0
Dn Type= 3
Dn Slope=0.018
DSS Import GetInterval= 0
DSS Import GetPeak= 0
DSS Import FillOption= 0

--- Conroe Lake 088.f02 (steady flow) ---

Flow Title=Orig_BLE_Flow
Program Version=4.10
Number of Profiles= 7
Profile Names=10-year,25-year,50-year,1pct_min,100-year,1pct_plu,500-year
River Rch & RM=Conroe Lake 088,Reach-1         ,3209
     523     691     826     324     980    2959    1376
River Rch & RM=Conroe Lake 088,Reach-1         ,2525
     603     802     963     379    1145    3459    1619
Boundary for River Rch & Prof#=Conroe Lake 088,Reach-1         , 1
Up Type= 0
Dn Type= 3
Dn Slope=0.018
Boundary for River Rch & Prof#=Conroe Lake 088,Reach-1         , 2
Up Type= 0
Dn Type= 3
Dn Slope=0.018
Boundary for River Rch & Prof#=Conroe Lake 088,Reach-1         , 3
Up Type= 0
Dn Type= 3
Dn Slope=0.018
Boundary for River Rch & Prof#=Conroe Lake 088,Reach-1         , 4
Up Type= 0
Dn Type= 3
Dn Slope=0.018
Boundary for River Rch & Prof#=Conroe Lake 088,Reach-1         , 5
Up Type= 0
Dn Type= 3
Dn Slope=0.018
Boundary for River Rch & Prof#=Conroe Lake 088,Reach-1         , 6
Up Type= 0
Dn Type= 3
Dn Slope=0.018
Boundary for River Rch & Prof#=Conroe Lake 088,Reach-1         , 7
Up Type= 0
Dn Type= 3
Dn Slope=0.018
DSS Import GetInterval= 0
DSS Import GetPeak= 0
DSS Import FillOption= 0

--- Conroe Lake 088.g01 (geometry) ---

Geom Title=Existing Conditions
Program Version=4.10

River Reach=Conroe Lake 088 ,Reach-1
Reach XY= 30
      3730253.23     10202226.84      3730308.23     10202176.84
      3730328.23     10201976.84      3730358.23     10201946.84
      3730428.23     10201926.84      3730448.23     10201876.84
      3730488.23     10201846.84      3730508.23     10201856.84
      3730538.23     10201806.84      3730578.23     10201646.84
      3730668.23     10201496.84      3730658.22     10201416.84
      3730686.34     10201322.17      3730813.78     10201144.34
      3730907.14     10200967.99      3730954.56     10200941.32
      3731046.44     10200677.54      3731058.23     10200516.84
      3731108.23     10200456.84      3731138.23     10200326.84
      3731138.23     10200256.84      3731108.23     10200176.84
      3731178.23     10200036.84      3731188.23     10199926.84
      3731038.23     10199766.84      3731058.23     10199596.84
      3731008.23     10199546.84      3731028.23     10199486.84
      3730988.23     10199456.84      3730988.23     10199416.84

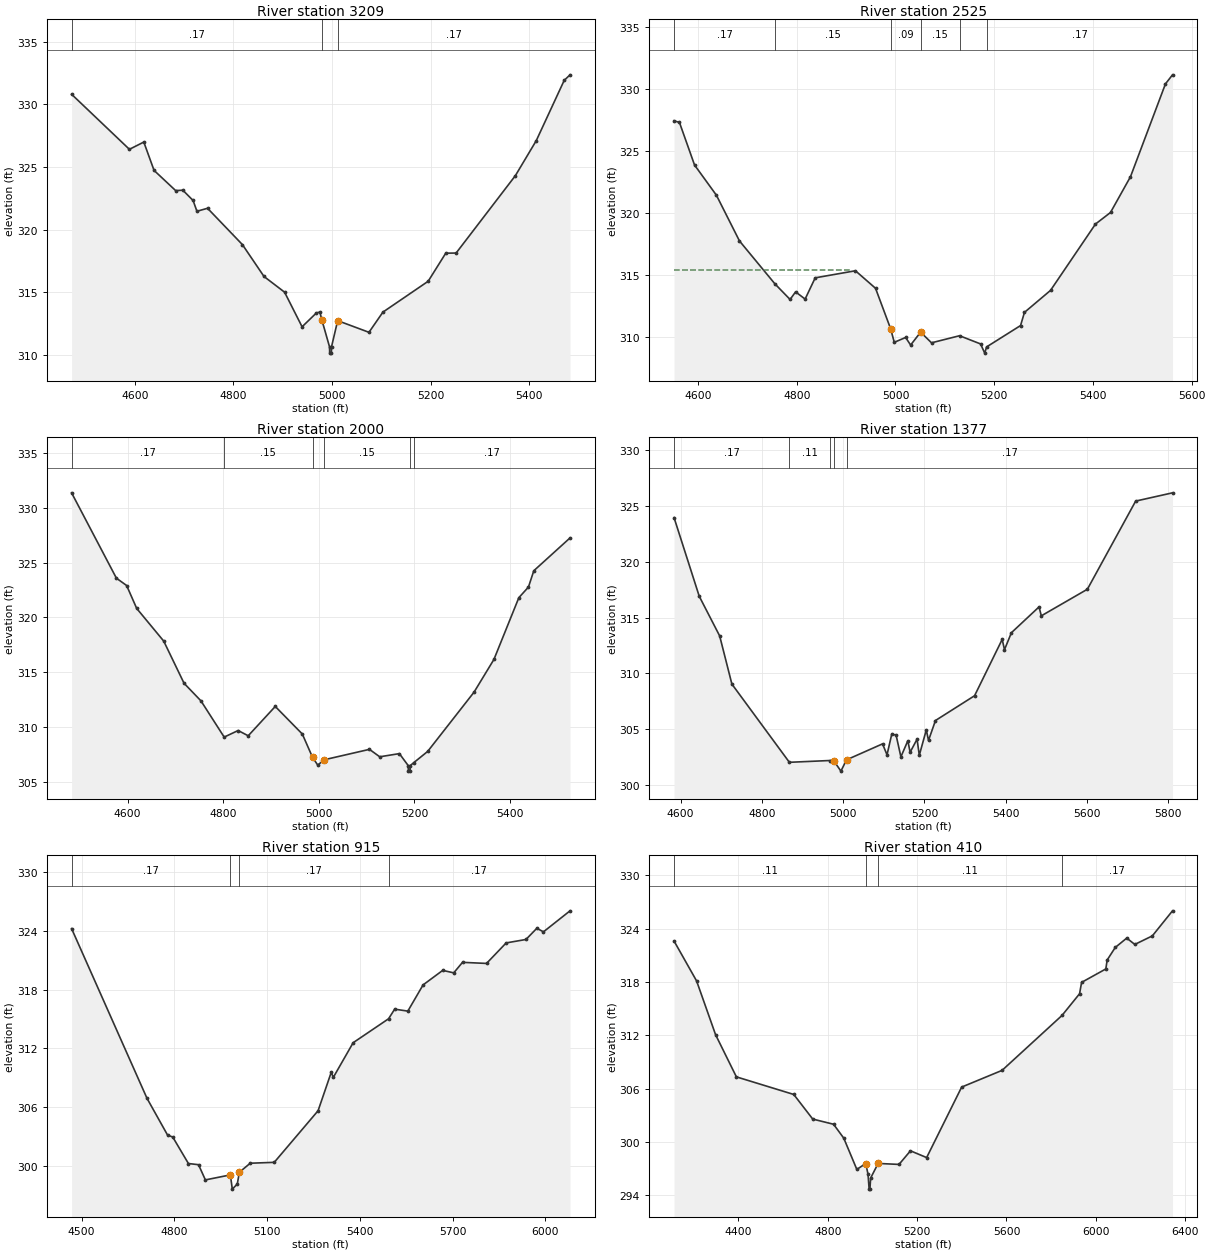
Type RM Length L Ch R = 1 ,3209    ,684,684,684
BEGIN DESCRIPTION:
Conroe Lake 088 7.0
END DESCRIPTION:
XS GIS Cut Line= 3
      3730731.69     10202392.56      3730308.23     10202076.84
      3729955.65     10201746.72
#Sta/Elev= 30
  4471.8   330.8  4589.1  326.41  4618.3  326.99  4639.1  324.73  4682.9  323.12
  4697.5  323.15  4718.3  322.33  4726.1  321.47  4747.6  321.71  4818.4  318.81
  4862.2  316.27  4903.9  315.02  4939.4  312.26  4968.6  313.37  4975.5  313.43
 4979.51  312.81  4995.1  310.66  4995.4  310.16  4998.9  310.16  4999.1  310.66
  5011.6  312.75  5075.1  311.82  5103.4  313.43  5195.2  315.89  5230.9  318.13
  5251.9  318.14  5372.1  324.31  5414.6  327.11  5471.2  331.91    5483  332.35
#Mann= 3 , 0 , 0
  4471.8     .17       0 4979.51     .09       0  5011.6     .17       0
Bank Sta=4979.51,5011.6
XS Rating Curve= 0 ,0
Exp/Cntr=0.3,0.1

Type RM Length L Ch R = 1 ,2525    ,525,525,525
BEGIN DESCRIPTION:
Conroe Lake 088 5.0
END DESCRIPTION:
XS GIS Cut Line= 3
      3731068.55     10201672.11      3730628.23     10201586.84
      3730073.75     10201500.23
#Sta/Elev= 30
  4551.5  327.43  4562.4   327.3    4593  323.87  4637.3  321.44    4684  317.76
  4755.7  314.31  4786.5  313.05  4797.7  313.66    4817  313.08  4837.4  314.79
  4918.9  315.36  4959.6  313.95  4990.2  310.69  4997.6   309.6  5020.6  309.99
  5030.7  309.38    5051  310.42    5073  309.56  5129.8  310.13  5172.4  309.47
  5180.8  308.73  5184.6  309.23  5253.4  310.95  5261.3  312.01  5314.1  313.78
  5405.2  319.12  5435.6  320.05  5476.1  322.93  5546.9   330.4  5561.2  331.13
#Mann= 6 ,-1 , 0
  4551.5     .17       0  4755.7     .15       0  4990.2     .09       0
    5051     .15       0  5129.8     .17       0  5184.6     .17       0
#XS Ineff= 2 , 0
       0  4908.7   315.4               0
Permanent Ineff=
       F       F
Bank Sta=4990.2,5051
XS Rating Curve= 0 ,0
Exp/Cntr=0.3,0.1

Type RM Length L Ch R = 1 ,2000    ,623,623,623
BEGIN DESCRIPTION:
Conroe Lake 088 4.0
END DESCRIPTION:
XS GIS Cut Line= 3
      3731193.55     10201488.09      3730819.61     10201130.63
       3730315.1     10200982.88
#Sta/Elev= 30
  4482.7  331.38  4576.5  323.58  4597.9  322.91  4618.9  320.82  4675.5  317.83
    4718  313.98  4753.4  312.37    4802  309.06  4831.2  309.66  4852.3  309.18
  4908.9  311.86  4965.5  309.34  4986.9  307.21  4997.8   306.5  5011.6  306.99
    5106  307.94  5127.5  307.26  5168.6  307.55  5187.2  306.45  5187.4  305.95
  5190.9  305.95  5191.2  306.45  5198.3  306.71  5227.8  307.75  5324.9  313.17
  5366.5  316.16  5418.6   321.8  5438.7  322.77  5449.9  324.26  5525.7  327.26
#Mann= 6 ,-1 , 0
  4482.7     .17       0    4802     .15       0  4986.9     .09       0
  5011.6     .15       0  5191.2     .15       0  5198.3     .17       0
#XS Ineff= 2 , 0
       0  4908.9  311.86               0
Permanent Ineff=
       F       F
Bank Sta=4986.9,5011.6
XS Rating Curve= 0 ,0
Exp/Cntr=0.3,0.1

Type RM Length L Ch R = 1 ,1377    ,462,462,462
BEGIN DESCRIPTION:
Conroe Lake 088 3.0
END DESCRIPTION:
XS GIS Cut Line= 3
      3731469.56     10200618.28      3731055.33     10200576.77
      3730323.72     10200926.49
#Sta/Elev= 30
  4583.7  323.95  4645.7  316.91    4696  313.36  4726.1  309.05  4867.6  302.05
  4967.2  302.21  4977.4  302.16  4994.5  301.26  5008.3  302.27    5097   303.7
    5108  302.72  5119.5  304.54  5130.2  304.51  5142.2  302.54  5159.3  303.98
  5164.9  302.95    5182  304.12  5187.5  302.68  5204.7  304.95  5210.2  304.01
  5227.3  305.79  5323.6  308.01  5391.6  313.05  5397.2  312.13  5414.3  313.65
  5482.3  315.96  5487.9  315.16  5601.3  317.54  5720.2  325.43  5810.9  326.17
#Mann= 5 ,-1 , 0
  4583.7     .17       0  4867.6     .11       0  4967.2     .17       0
  4977.4     .09       0  5008.3     .17       0
#XS Ineff= 2 , 0
       0                  5119.5       0  304.54
Permanent Ineff=
       F       F
Bank Sta=4977.4,5008.3
XS Rating Curve= 0 ,0
Exp/Cntr=0.3,0.1

Type RM Length L Ch R = 1 ,915     ,505,505,505
BEGIN DESCRIPTION:
Conroe Lake 088 2.0
END DESCRIPTION:
XS GIS Cut Line= 3
      3731587.62     10200408.21      3731108.23     10200176.84
      3730315.04     10200909.97
#Sta/Elev= 30
  4467.7  324.21  4711.7  306.91  4778.3  303.16  4794.9  302.97  4845.6  300.27
  4878.3  300.15  4900.5   298.6  4981.3  299.11  4987.6  297.66  5003.7  298.18
  5010.5  299.38  5045.6   300.3  5123.3  300.39  5265.1  305.65  5307.6  309.56
  5314.4  309.05  5378.5  312.58  5493.1  315.02  5512.8     316  5555.4   315.8
  5604.7  318.47  5668.2  319.95  5703.9   319.7  5732.3  320.77    5810  320.66
  5873.5  322.75  5937.5   323.1  5972.7  324.24  5994.2  323.88  6080.1  326.02
#Mann= 4 ,-1 , 0
  4467.7     .17       0  4981.3     .07       0  5010.5     .17       0
  5493.1     .17       0
Bank Sta=4981.3,5010.5
XS Rating Curve= 0 ,0
Exp/Cntr=0.3,0.1

Type RM Length L Ch R = 1 ,410     ,313,313,313
BEGIN DESCRIPTION:
Conroe Lake 088 1.0
END DESCRIPTION:
XS GIS Cut Line= 4
      3731634.54     10200356.17      3731166.17     10199758.08
      3731038.23     10199766.84      3730302.89     10200890.88
#Sta/Elev= 30
  4112.1  322.59    4213   318.1    4298  312.05  4391.1  307.31  4647.9  305.33
  4732.9  302.56    4826  301.98  4871.8  300.41  4930.2   296.9  4970.3  297.56
  4980.3  296.34  4985.3  294.68  4988.8  294.68    4992  295.93  5025.5  297.57
    5119  297.46  5170.3  298.99  5242.7  298.23  5399.4  306.16  5580.3  308.04
  5848.6  314.22  5927.2  316.66  5936.3  317.94  6044.7  319.45  6050.8  320.46
    6087  321.87  6138.3  322.92  6174.5  322.21  6252.9  323.17  6343.2  325.99
#Mann= 4 ,-1 , 0
  4112.1     .11       0  4970.3     .06       0  5025.5     .11       0
  5848.6     .17       0
#XS Ineff= 2 , 0
       0                  5170.3       0  298.99
Permanent Ineff=
       F       F
Bank Sta=4970.3,5025.5
XS Rating Curve= 0 ,0
Exp/Cntr=0.3,0.1

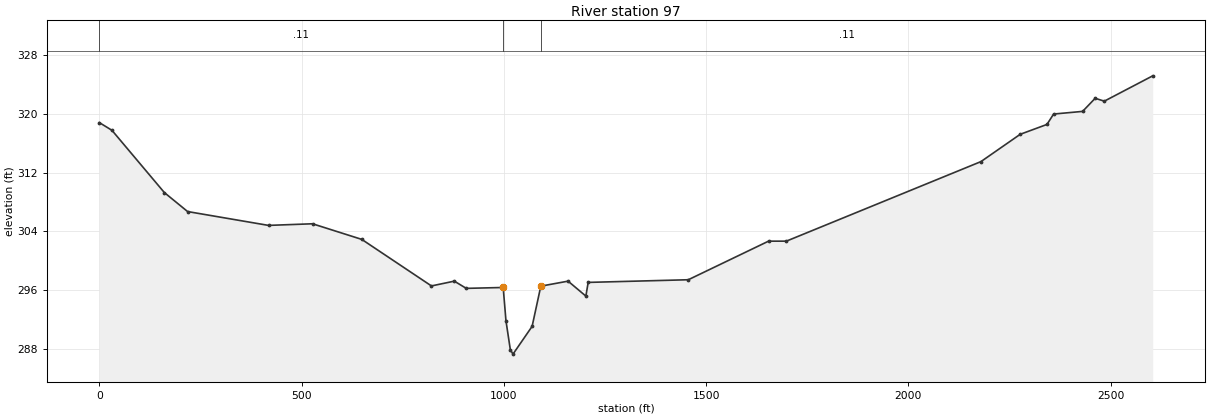
Type RM Length L Ch R = 1 ,97      ,0,0,0
XS GIS Cut Line= 4
      3731650.54      10200262.1      3731086.64     10199467.65
      3730972.32     10199513.49      3730270.33     10200848.04
#Sta/Elev= 30
       0  318.78    31.2  317.73   160.7  309.28   218.2   306.7   418.2  304.82
     527  305.04   648.8  302.92     821   296.6   877.6  297.25   907.1  296.27
   998.4  296.39  1005.2  291.89    1016  287.96  1022.6  287.34  1069.9  291.11
  1091.4  296.57  1158.8  297.25  1202.8  295.22  1208.5  297.08    1456  297.44
  1654.4  302.68  1698.4  302.68  2179.4  313.48  2276.6  317.19  2342.7  318.53
  2359.1  319.94  2430.8   320.3  2461.9  322.08  2484.5  321.69  2604.2  325.13
#Mann= 3 , 0 , 0
       0     .11       0   998.4     .06       0  1091.4     .11       0
Bank Sta=998.4,1091.4
XS Rating Curve= 0 ,0
Exp/Cntr=0.3,0.1

Chan Stop Cuts=-1
Use User Specified Reach Order=0
Composite Channel Slope=5