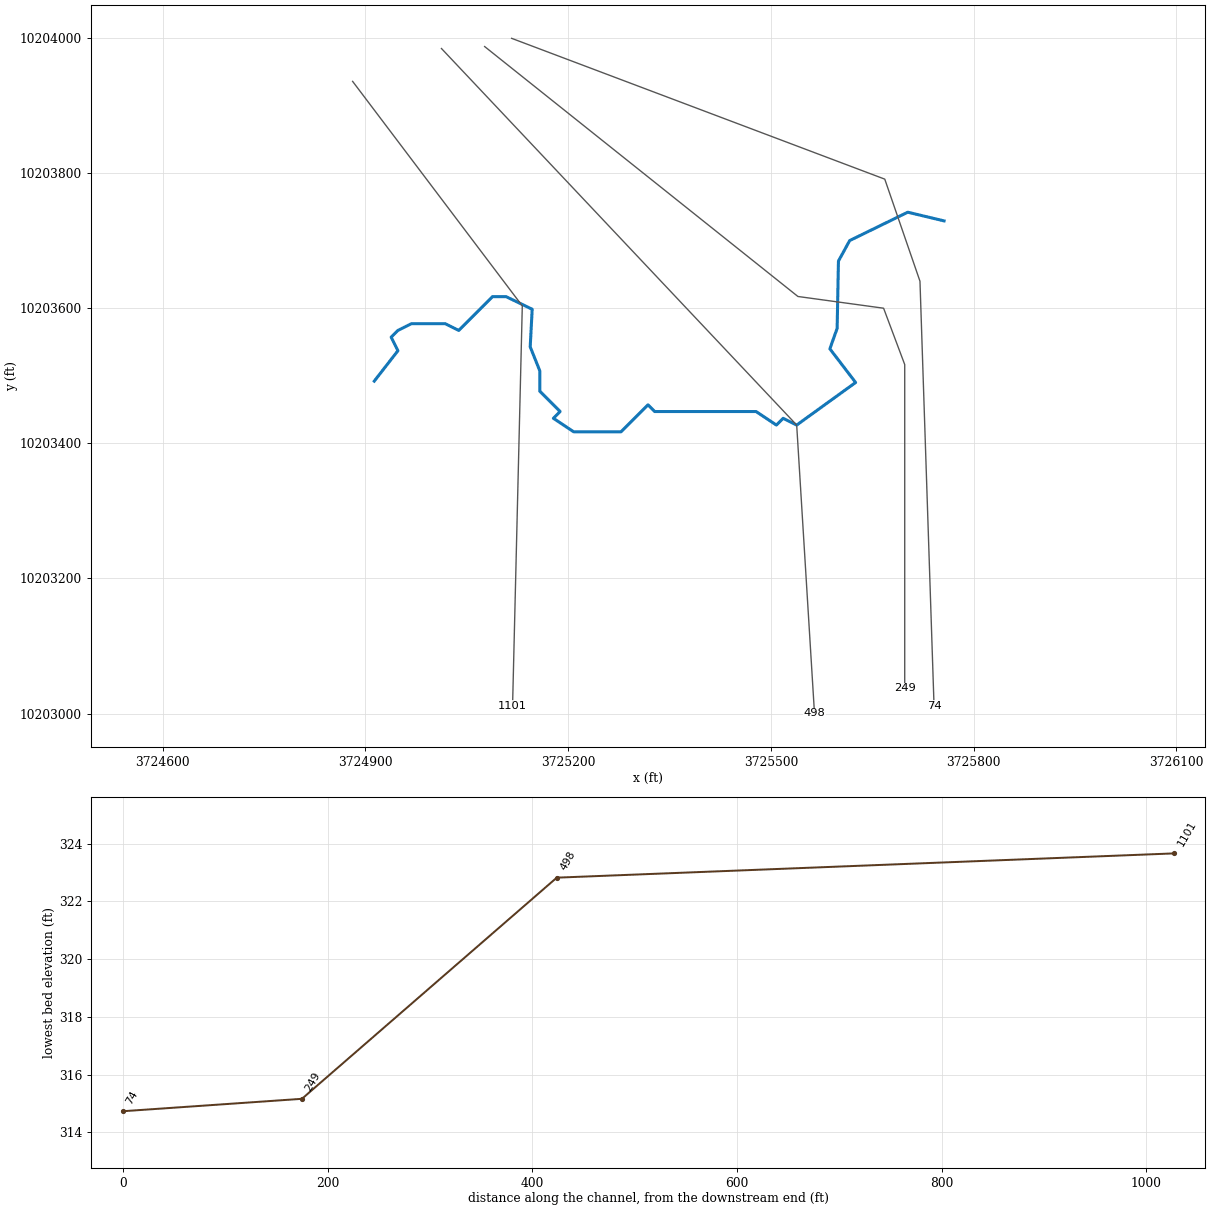
--- Conroe Lake 089.prj (project) ---

Proj Title=Conroe Lake 089 Base Level Engineering
Current Plan=p01
Default Exp/Contr=0.3,0.1
English Units
Geom File=g01
Flow File=f01
Flow File=f02
Plan File=p01
Y Axis Title=Elevation
X Axis Title(PF)=Main Channel Distance
X Axis Title(XS)=Station
BEGIN DESCRIPTION:
Conroe Lake 089
END DESCRIPTION:
DSS Export Rating Curves= 0
DSS Export Rating Curve Sorted= 0
DSS Export Volume Flow Curves= 0
DXF OffsetX= 0
DXF OffsetY= 0
DXF ScaleX= 1
DXF ScaleY= 10

--- Conroe Lake 089.p01 (plan) ---

Plan Title=Multiple Run
Short Identifier=Multiple
Geom File=g01
Flow File=f01
Subcritical Flow
K Sum by GR= 0
Std Step Tol= 0.01
Critical Tol= 0.01
Num of Std Step Trials= 20
Max Error Tol= 0.3
Flow Tol Ratio= 0.001
Split Flow NTrial= 30
Split Flow Tol= 0.02
Split Flow Ratio= 0.02
Log Output Level= 0
Friction Slope Method= 1
Unsteady Friction Slope Method= 2
Unsteady Bridges Friction Slope Method= 1
Parabolic Critical Depth
Global Vel Dist=  1 , 1 , 1
Global Log Level= 0
CheckData=True
Encroach Param= -1, 0, 0, 0
BEGIN DESCRIPTION:
Multiple Run
END DESCRIPTION:

--- Conroe Lake 089.f01 (steady flow) ---

Flow Title=Multiple
Program Version=4.10
Number of Profiles= 7
Profile Names=10-year,25-year,50-year,1pct_min,100-year,1pct_plu,500-year
River Rch & RM=Conroe Lake 089,Reach-1         ,1101
     456     608     813     359    1083    3271    1985
Boundary for River Rch & Prof#=Conroe Lake 089,Reach-1         , 1
Up Type= 0
Dn Type= 3
Dn Slope=0.02
Boundary for River Rch & Prof#=Conroe Lake 089,Reach-1         , 2
Up Type= 0
Dn Type= 3
Dn Slope=0.02
Boundary for River Rch & Prof#=Conroe Lake 089,Reach-1         , 3
Up Type= 0
Dn Type= 3
Dn Slope=0.02
Boundary for River Rch & Prof#=Conroe Lake 089,Reach-1         , 4
Up Type= 0
Dn Type= 3
Dn Slope=0.02
Boundary for River Rch & Prof#=Conroe Lake 089,Reach-1         , 5
Up Type= 0
Dn Type= 3
Dn Slope=0.02
Boundary for River Rch & Prof#=Conroe Lake 089,Reach-1         , 6
Up Type= 0
Dn Type= 3
Dn Slope=0.02
Boundary for River Rch & Prof#=Conroe Lake 089,Reach-1         , 7
Up Type= 0
Dn Type= 3
Dn Slope=0.02
DSS Import GetInterval= 0
DSS Import GetPeak= 0
DSS Import FillOption= 0

--- Conroe Lake 089.f02 (steady flow) ---

Flow Title=Orig_BLE_Flow
Program Version=4.10
Number of Profiles= 7
Profile Names=10-year,25-year,50-year,1pct_min,100-year,1pct_plu,500-year
River Rch & RM=Conroe Lake 089,Reach-1         ,1101
     456     596     707     276     833    2516    1154
Boundary for River Rch & Prof#=Conroe Lake 089,Reach-1         , 1
Up Type= 0
Dn Type= 3
Dn Slope=0.009
Boundary for River Rch & Prof#=Conroe Lake 089,Reach-1         , 2
Up Type= 0
Dn Type= 3
Dn Slope=0.009
Boundary for River Rch & Prof#=Conroe Lake 089,Reach-1         , 3
Up Type= 0
Dn Type= 3
Dn Slope=0.009
Boundary for River Rch & Prof#=Conroe Lake 089,Reach-1         , 4
Up Type= 0
Dn Type= 3
Dn Slope=0.009
Boundary for River Rch & Prof#=Conroe Lake 089,Reach-1         , 5
Up Type= 0
Dn Type= 3
Dn Slope=0.009
Boundary for River Rch & Prof#=Conroe Lake 089,Reach-1         , 6
Up Type= 0
Dn Type= 3
Dn Slope=0.009
Boundary for River Rch & Prof#=Conroe Lake 089,Reach-1         , 7
Up Type= 0
Dn Type= 3
Dn Slope=0.009
DSS Import GetInterval= 0
DSS Import GetPeak= 0
DSS Import FillOption= 0

--- Conroe Lake 089.g01 (geometry) ---

Geom Title=Existing Conditions
Program Version=4.10

River Reach=Conroe Lake 089 ,Reach-1
Reach XY= 30
      3724913.23     10203491.84      3724948.23     10203536.84
      3724938.23     10203556.84      3724948.23     10203566.84
      3724968.23     10203576.84      3725018.23     10203576.84
      3725038.23     10203566.84      3725088.23     10203616.84
      3725108.23     10203616.84      3725146.89     10203598.21
      3725143.97     10203542.55      3725158.23     10203506.84
      3725158.23     10203476.84      3725188.23     10203446.84
      3725178.23     10203436.84      3725208.23     10203416.84
      3725278.23     10203416.84      3725318.23     10203456.84
      3725328.23     10203446.84      3725478.23     10203446.84
      3725508.23     10203426.84      3725518.23     10203436.84
      3725538.23     10203426.84      3725625.41     10203489.81
      3725587.32     10203539.62      3725598.07     10203569.89
      3725600.02      10203669.5      3725616.62     10203699.77
      3725702.56     10203741.77       3725756.3      10203728.9

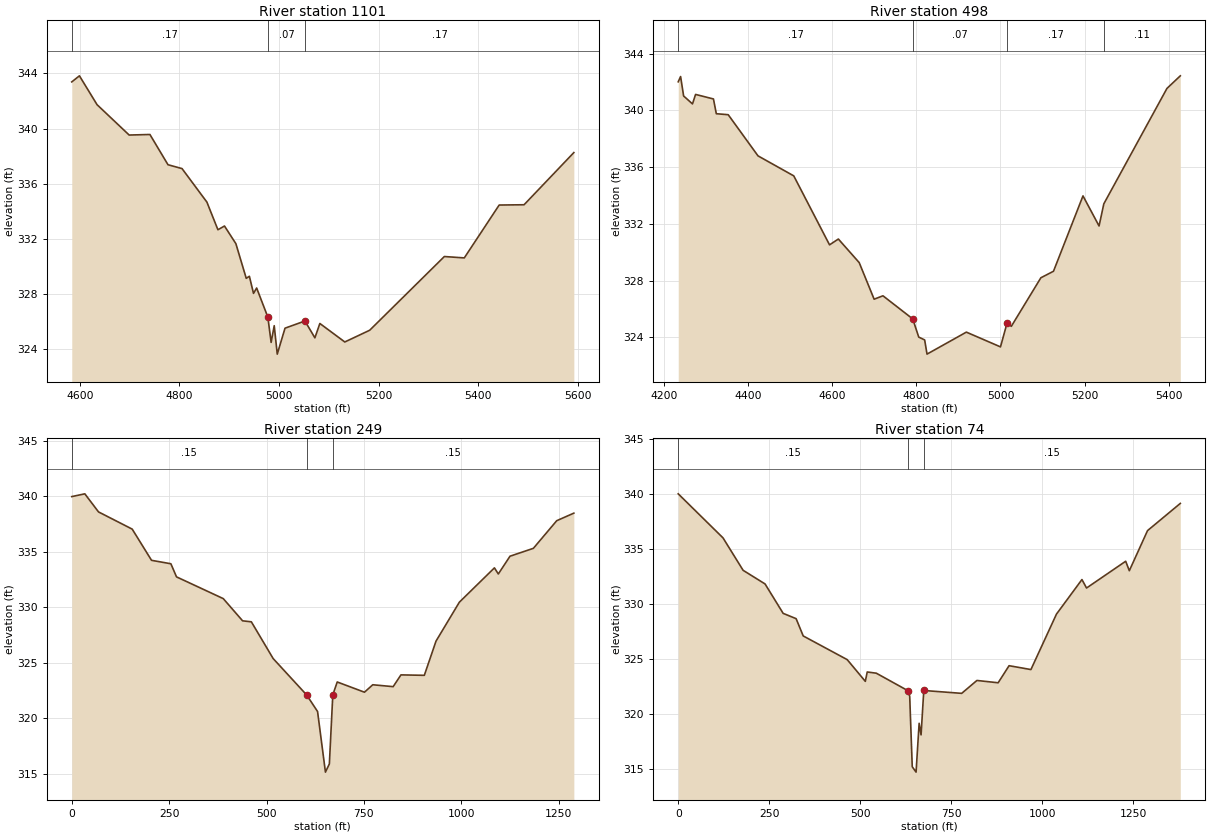
Type RM Length L Ch R = 1 ,1101    ,603,603,603
BEGIN DESCRIPTION:
Conroe Lake 089 2.0
END DESCRIPTION:
XS GIS Cut Line= 3
      3724881.22     10203935.32      3725132.25     10203603.09
      3725117.85     10203011.07
#Sta/Elev= 30
  4583.6  343.38    4599  343.82  4634.4  341.73  4698.9  339.53  4740.6  339.57
  4776.9  337.38  4805.1   337.1  4855.1  334.67  4877.2  332.67  4890.4  332.94
  4913.3  331.66  4934.1  329.15  4940.4   329.3  4948.7  328.06    4955  328.45
  4977.5  326.34  4984.1  324.51  4990.3  325.72  4996.4  323.66    5012  325.54
    5052  326.06    5072  324.84    5082  325.88  5132.1  324.54  5182.1  325.39
  5332.1  330.73  5372.1  330.63  5442.2  334.46  5492.2  334.48  5592.2  338.26
#Mann= 3 , 0 , 0
  4583.6     .17       0  4977.5     .07       0    5052     .17       0
#XS Ineff= 2 , 0
       0    4955  328.45               0
Permanent Ineff=
       F       F
Bank Sta=4977.5,5052
XS Rating Curve= 0 ,0
Exp/Cntr=0.3,0.1

Type RM Length L Ch R = 1 ,498     ,249,249,249
BEGIN DESCRIPTION:
Conroe Lake 089 1.0
END DESCRIPTION:
XS GIS Cut Line= 3
      3725012.65     10203983.95      3725538.23     10203426.84
      3725564.56     10203000.26
#Sta/Elev= 30
  4234.1  342.01  4239.7  342.38  4246.9  341.01    4268  340.45  4275.3  341.12
  4317.8   340.8  4324.6  339.76  4352.9  339.69  4423.7  336.79  4508.7  335.38
  4593.7  330.52  4614.7  330.93  4664.2  329.27  4699.7  326.69  4720.7  326.93
  4791.5   325.3  4805.7  324.02  4819.8  323.82  4825.4  322.82  4918.9  324.37
    5000  323.33  5015.8  325.03  5025.8  324.78    5096   328.2    5126  328.66
  5196.1  333.97  5234.3  331.85  5245.6  333.41  5395.6  341.54  5427.4  342.43
#Mann= 4 ,-1 , 0
  4234.1     .17       0  4791.5     .07       0  5015.8     .17       0
  5245.6     .11       0
#XS Ineff= 2 , 0
       0  4720.7  326.93               0
Permanent Ineff=
       F       F
Bank Sta=4791.5,5015.8
XS Rating Curve= 0 ,0
Exp/Cntr=0.3,0.1

Type RM Length L Ch R = 1 ,249     ,175,175,175
XS GIS Cut Line= 5
      3725076.53     10203986.86      3725540.07     10203617.07
      3725666.81     10203599.71      3725698.06     10203516.37
      3725698.06     10203037.21
#Sta/Elev= 30
       0  339.98    33.5  340.23    68.7   338.6   155.2  337.05   204.8  334.24
   254.5  333.93   268.9  332.75     389  330.79   438.6  328.79   461.1   328.7
   517.1  325.39   603.1  322.11   631.1  320.62   651.3  315.16   661.4   315.9
   670.2  322.12   681.6  323.28   751.5  322.36   772.8  323.03   825.2  322.86
   845.2  323.92   905.2  323.88   935.2  326.96   995.2  330.47  1085.2  333.56
  1095.2  333.01  1125.2  334.61  1185.2  335.32  1245.2  337.81  1289.1  338.49
#Mann= 3 , 0 , 0
       0     .15       0   603.1     .07       0   670.2     .15       0
Bank Sta=603.1,670.2
XS Rating Curve= 0 ,0
Exp/Cntr=0.3,0.1

Type RM Length L Ch R = 1 ,74      ,0,0,0
XS GIS Cut Line= 4
      3725116.46     10203999.01      3725668.55     10203790.68
      3725720.63     10203639.64      3725741.46     10203011.17
#Sta/Elev= 30
       0  339.99     123  335.99   178.1  333.05   238.4  331.81   288.1  329.14
   323.7  328.66   343.2  327.09     464  324.94   513.7  322.97     519  323.82
   543.9  323.71   630.3  322.13   635.6  321.62   642.6  315.22   653.1  314.73
   661.5  319.16   666.8  318.11   674.3  322.14   778.4  321.88   820.2  323.05
   878.5  322.84   908.5  324.39   968.5  324.04  1038.6  329.07  1108.6  332.21
  1121.2  331.44  1228.7  333.87  1238.7  333.01  1288.7  336.65  1378.7  339.12
#Mann= 3 , 0 , 0
       0     .15       0   630.3     .07       0   674.3     .15       0
Bank Sta=630.3,674.3
XS Rating Curve= 0 ,0
Exp/Cntr=0.3,0.1

Chan Stop Cuts=-1
Use User Specified Reach Order=0
Composite Channel Slope=5