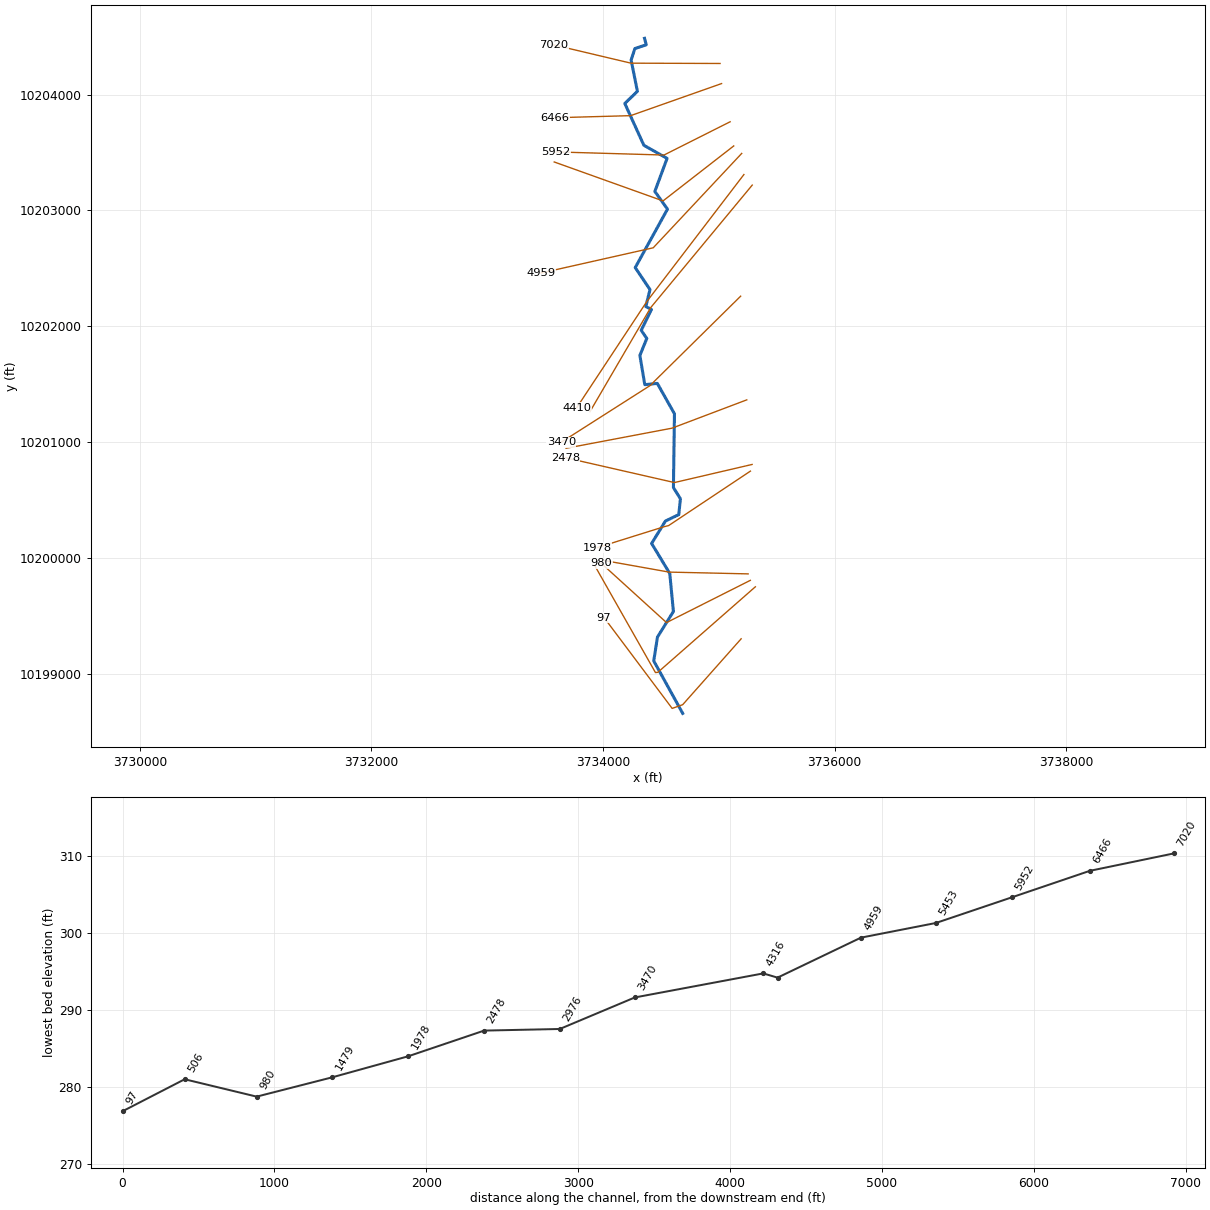
--- Conroe Lake 091.prj (project) ---

Proj Title=Conroe Lake 091 Base Level Engineering
Current Plan=p01
Default Exp/Contr=0.3,0.1
English Units
Geom File=g01
Flow File=f01
Flow File=f02
Plan File=p01
Y Axis Title=Elevation
X Axis Title(PF)=Main Channel Distance
X Axis Title(XS)=Station
BEGIN DESCRIPTION:
Conroe Lake 091
END DESCRIPTION:
DSS Export Rating Curves= 0
DSS Export Rating Curve Sorted= 0
DSS Export Volume Flow Curves= 0
DXF OffsetX= 0
DXF OffsetY= 0
DXF ScaleX= 1
DXF ScaleY= 10

--- Conroe Lake 091.p01 (plan) ---

Plan Title=Multiple Run
Short Identifier=Multiple
Geom File=g01
Flow File=f01
Subcritical Flow
K Sum by GR= 0
Std Step Tol= 0.01
Critical Tol= 0.01
Num of Std Step Trials= 20
Max Error Tol= 0.3
Flow Tol Ratio= 0.001
Split Flow NTrial= 30
Split Flow Tol= 0.02
Split Flow Ratio= 0.02
Log Output Level= 0
Friction Slope Method= 1
Unsteady Friction Slope Method= 2
Unsteady Bridges Friction Slope Method= 1
Parabolic Critical Depth
Global Vel Dist=  1 , 1 , 1
Global Log Level= 0
CheckData=True
Encroach Param= -1, 0, 0, 0
BEGIN DESCRIPTION:
Multiple Run
END DESCRIPTION:

--- Conroe Lake 091.f01 (steady flow) ---

Flow Title=Multiple
Program Version=4.10
Number of Profiles= 7
Profile Names=10-year,25-year,50-year,1pct_min,100-year,1pct_plu,500-year
River Rch & RM=Conroe Lake 091,Reach-1         ,7020
     556     756    1025     458    1383    4177    2602
River Rch & RM=Conroe Lake 091,Reach-1         ,6466
     705     964    1311     587    1772    5351    3345
River Rch & RM=Conroe Lake 091,Reach-1         ,2976
     917    1274    1750     791    2388    7212    4599
Boundary for River Rch & Prof#=Conroe Lake 091,Reach-1         , 1
Up Type= 0
Dn Type= 3
Dn Slope=0.005
Boundary for River Rch & Prof#=Conroe Lake 091,Reach-1         , 2
Up Type= 0
Dn Type= 3
Dn Slope=0.005
Boundary for River Rch & Prof#=Conroe Lake 091,Reach-1         , 3
Up Type= 0
Dn Type= 3
Dn Slope=0.005
Boundary for River Rch & Prof#=Conroe Lake 091,Reach-1         , 4
Up Type= 0
Dn Type= 3
Dn Slope=0.005
Boundary for River Rch & Prof#=Conroe Lake 091,Reach-1         , 5
Up Type= 0
Dn Type= 3
Dn Slope=0.005
Boundary for River Rch & Prof#=Conroe Lake 091,Reach-1         , 6
Up Type= 0
Dn Type= 3
Dn Slope=0.005
Boundary for River Rch & Prof#=Conroe Lake 091,Reach-1         , 7
Up Type= 0
Dn Type= 3
Dn Slope=0.005
DSS Import GetInterval= 0
DSS Import GetPeak= 0
DSS Import FillOption= 0

--- Conroe Lake 091.f02 (steady flow) ---

Flow Title=Orig_BLE_Flow
Program Version=4.10
Number of Profiles= 7
Profile Names=10-year,25-year,50-year,1pct_min,100-year,1pct_plu,500-year
River Rch & RM=Conroe Lake 091,Reach-1         ,7020
     556     741     891     352    1064    3214    1513
River Rch & RM=Conroe Lake 091,Reach-1         ,6466
     705     945    1140     451    1363    4116    1945
River Rch & RM=Conroe Lake 091,Reach-1         ,2976
     917    1249    1522     608    1837    5548    2674
Boundary for River Rch & Prof#=Conroe Lake 091,Reach-1         , 1
Up Type= 0
Dn Type= 3
Dn Slope=0.006
Boundary for River Rch & Prof#=Conroe Lake 091,Reach-1         , 2
Up Type= 0
Dn Type= 3
Dn Slope=0.006
Boundary for River Rch & Prof#=Conroe Lake 091,Reach-1         , 3
Up Type= 0
Dn Type= 3
Dn Slope=0.006
Boundary for River Rch & Prof#=Conroe Lake 091,Reach-1         , 4
Up Type= 0
Dn Type= 3
Dn Slope=0.006
Boundary for River Rch & Prof#=Conroe Lake 091,Reach-1         , 5
Up Type= 0
Dn Type= 3
Dn Slope=0.006
Boundary for River Rch & Prof#=Conroe Lake 091,Reach-1         , 6
Up Type= 0
Dn Type= 3
Dn Slope=0.006
Boundary for River Rch & Prof#=Conroe Lake 091,Reach-1         , 7
Up Type= 0
Dn Type= 3
Dn Slope=0.006
DSS Import GetInterval= 0
DSS Import GetPeak= 0
DSS Import FillOption= 0

--- Conroe Lake 091.g01 (geometry) ---

Geom Title=Existing Conditions
Program Version=4.10

River Reach=Conroe Lake 091 ,Reach-1
Reach XY= 30
      3734358.23     10204486.84      3734373.59      10204430.8
      3734275.14     10204398.49      3734242.83     10204300.04
      3734297.04     10204029.24      3734188.31     10203924.01
      3734352.93     10203562.98      3734553.38     10203449.97
      3734447.65     10203164.69       3734556.9     10203011.81
      3734278.23     10202506.84      3734405.94     10202316.82
       3734369.7     10202170.59      3734418.49     10202145.24
      3734329.92     10201965.19      3734378.15     10201894.57
      3734318.26     10201748.17      3734360.89     10201495.71
      3734468.99     10201506.77      3734616.99     10201244.35
      3734608.16     10200607.06      3734668.53     10200509.98
      3734654.23     10200373.59      3734539.25     10200318.24
      3734419.73     10200124.38      3734576.49     10199865.18
      3734608.05     10199536.65      3734470.27       10199316.
      3734438.19     10199109.72      3734688.23     10198656.84

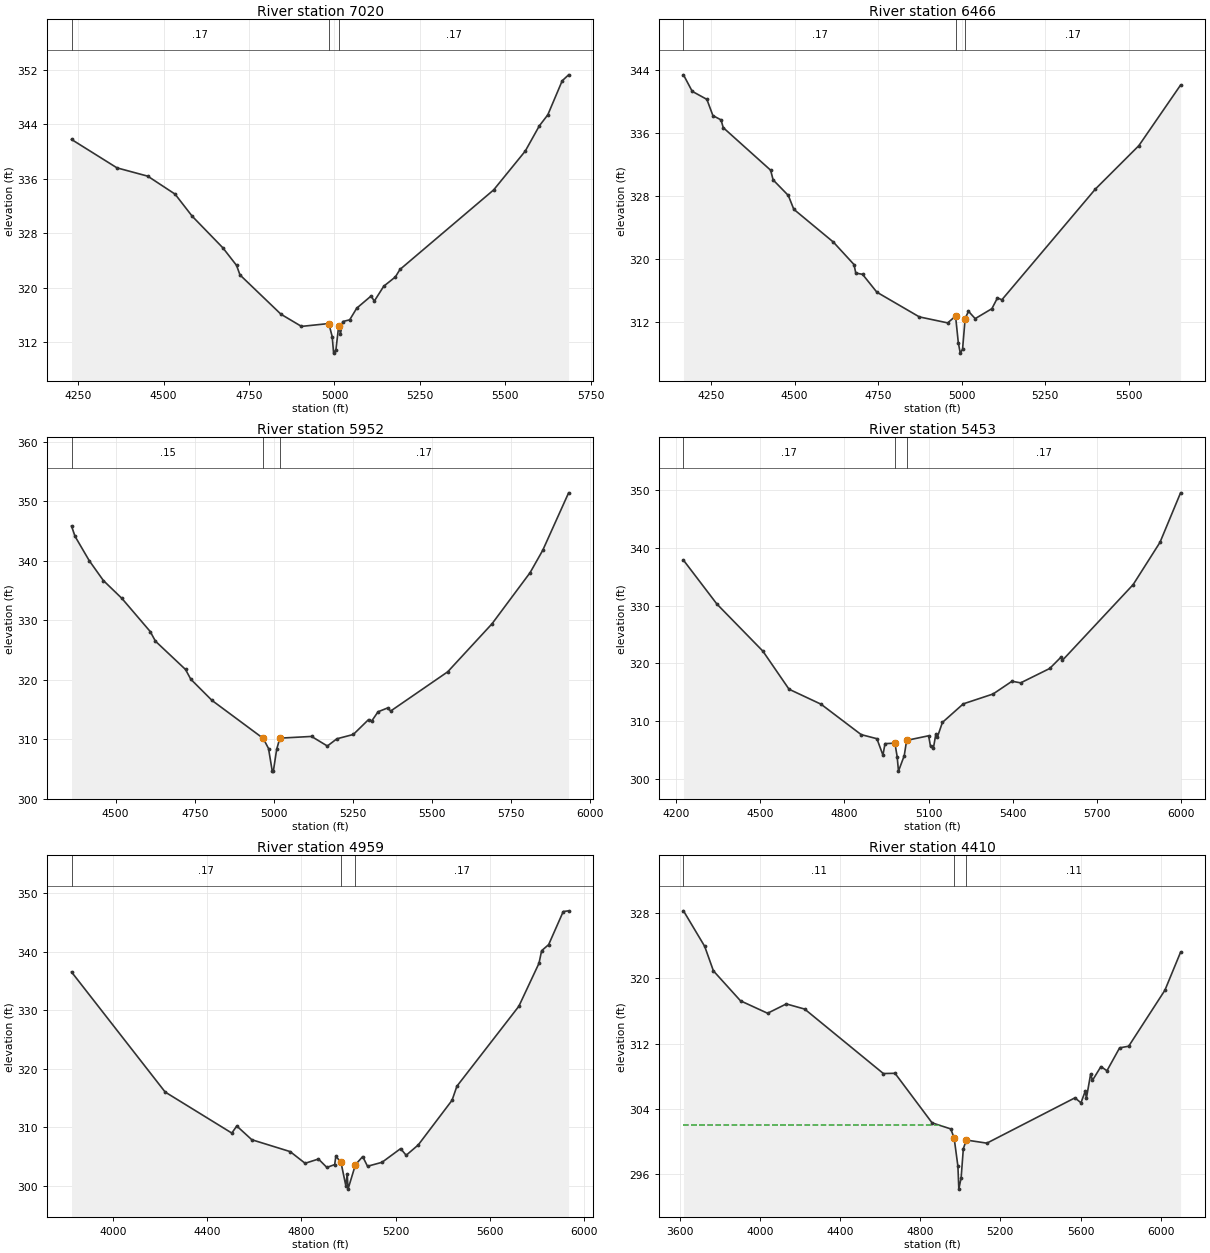
Type RM Length L Ch R = 1 ,7020    ,554,554,554
BEGIN DESCRIPTION:
Conroe Lake 091 14.0
END DESCRIPTION:
XS GIS Cut Line= 3
      3735010.99      10204269.7      3734241.29     10204272.34
      3733574.34      10204430.3
#Sta/Elev= 30
  4230.3  341.78  4363.4   337.6  4453.4  336.38  4533.4  333.74  4583.4   330.5
  4673.4  325.84  4713.4  323.26  4723.4  321.86  4843.4  316.08  4903.4  314.29
  4983.4  314.71  4993.4  312.79  4997.5  310.36  5004.3  310.86  5012.4  314.37
  5017.6  313.21  5024.1     315  5044.6  315.26  5065.2  316.97  5107.2  318.76
  5116.6  318.01  5144.3   320.2  5178.2  321.56  5191.7  322.66    5466  334.36
  5558.5  340.07  5599.6  343.77  5624.5   345.4  5666.7  350.41  5685.4  351.28
#Mann= 3 , 0 , 0
  4230.3     .17       0  4983.4     .09       0  5012.4     .17       0
#XS Ineff= 2 , 0
       0                  5107.2       0  318.76
Permanent Ineff=
       F       F
Bank Sta=4983.4,5012.4
XS Rating Curve= 0 ,0
Exp/Cntr=0.3,0.1

Type RM Length L Ch R = 1 ,6466    ,514,514,514
BEGIN DESCRIPTION:
Conroe Lake 091 13.0
END DESCRIPTION:
XS GIS Cut Line= 3
      3735023.99     10204096.07      3734238.39     10203819.08
      3733583.04     10203800.95
#Sta/Elev= 30
    4167  343.34  4193.2  341.25  4237.1  340.23  4255.1  338.18  4279.5  337.63
  4286.1  336.65    4428  331.26  4435.5  330.03    4481  328.06  4497.4  326.31
  4615.8  322.16  4677.7  319.31    4683  318.23  4703.3  318.07  4746.1  315.81
  4873.3  312.68  4958.2  311.92  4981.8  312.78    4990  309.43  4995.9  308.09
  5002.8  308.59  5010.5  312.47  5020.5  313.39  5040.6  312.46  5090.6  313.72
  5107.2  315.08  5120.6  314.85  5400.7  328.88  5530.7  334.37  5655.6  342.04
#Mann= 3 , 0 , 0
    4167     .17       0  4981.8     .09       0  5010.5     .17       0
Bank Sta=4981.8,5010.5
XS Rating Curve= 0 ,0
Exp/Cntr=0.3,0.1

Type RM Length L Ch R = 1 ,5952    ,499,499,499
BEGIN DESCRIPTION:
Conroe Lake 091 12.0
END DESCRIPTION:
XS GIS Cut Line= 3
       3735097.8     10203766.22      3734526.59     10203478.92
      3733596.07     10203505.81
#Sta/Elev= 30
  4360.6  345.82  4371.7  344.09  4416.5  340.01  4461.3  336.66  4519.8  333.66
  4609.1   328.1  4625.8  326.47  4720.7  321.72  4737.4  320.08  4804.4  316.52
  4966.2  310.14  4982.9  308.44  4994.7  304.64  4998.2  304.64  5008.7  308.31
  5018.7  310.18  5118.8  310.47  5168.8  308.86  5198.8  310.07  5250.8   310.8
  5298.9   313.3  5308.9  313.06  5328.9  314.61  5358.9  315.25  5368.9  314.74
    5549  321.33    5689   329.4  5809.1  337.98  5849.1  341.74  5930.9   351.4
#Mann= 3 , 0 , 0
  4360.6     .15       0  4966.2     .09       0  5018.7     .17       0
Bank Sta=4966.2,5018.7
XS Rating Curve= 0 ,0
Exp/Cntr=0.3,0.1

Type RM Length L Ch R = 1 ,5453    ,494,494,494
BEGIN DESCRIPTION:
Conroe Lake 091 11.0
END DESCRIPTION:
XS GIS Cut Line= 3
      3735129.11      10203557.6      3734518.27     10203082.75
      3733578.72       10203419.
#Sta/Elev= 30
  4226.3  337.88  4345.5  330.27  4509.3  322.11  4602.5  315.51  4716.6  312.91
  4859.6  307.64  4915.7  306.93  4937.2  304.08  4944.6  306.08  4979.9  306.15
  4987.9  303.82  4992.6  301.31  5013.1  303.99  5021.7  306.64  5100.1  307.44
  5106.7   305.6  5117.3  305.36  5125.6   307.7  5130.9  307.16  5149.1  309.75
  5223.5  312.97  5329.7  314.68  5397.2  316.89    5428  316.61  5531.5   319.1
  5571.2  321.04  5576.5   320.5  5828.9  333.64  5924.5  340.96  5997.9  349.55
#Mann= 3 ,-1 , 0
  4226.3     .17       0  4979.9     .09       0  5021.7     .17       0
Bank Sta=4979.9,5021.7
XS Rating Curve= 0 ,0
Exp/Cntr=0.3,0.1

Type RM Length L Ch R = 1 ,4959    ,549,549,549
BEGIN DESCRIPTION:
Mapping XS 6020c487
END DESCRIPTION:
XS GIS Cut Line= 3
      3735197.67     10203492.81      3734433.81     10202677.95
      3733465.23     10202460.04
#Sta/Elev= 30
  3824.1  336.55  4221.5  316.01  4504.4  308.99  4525.5   310.2  4589.3  307.85
    4752  305.82  4815.5  303.82  4872.2  304.55  4907.8  303.11    4941   303.6
  4945.8  305.02  4967.6  304.01  4988.1  300.01  4994.2  302.02  4997.6   299.4
  5029.1  303.58  5059.9  304.97  5080.4  303.31  5141.9  303.99  5220.8  306.33
  5244.4  305.19  5295.6  306.96  5439.1   314.6  5459.6     317  5722.5  330.68
  5808.1  338.04  5819.3  340.19  5849.1  341.23    5911  346.89  5933.8  347.01
#Mann= 3 , 0 , 0
  3824.1     .17       0  4967.6     .09       0  5029.1     .17       0
#XS Ineff= 2 , 0
       0  4945.8  305.02  5059.9       0  304.97
Permanent Ineff=
       F       F
Bank Sta=4967.6,5029.1
XS Rating Curve= 0 ,0
Exp/Cntr=0.3,0.1

Type RM Length L Ch R = 1 ,4410    ,94,94,94
BEGIN DESCRIPTION:
Conroe Lake 091 9.0
END DESCRIPTION:
XS GIS Cut Line= 3
      3735216.84     10203310.53      3734378.27     10202213.66
      3733772.58     10201296.51
#Sta/Elev= 30
  3619.3  328.22  3725.1  323.88  3768.7  320.88  3903.8  317.22  4038.9   315.7
  4132.3  316.84  4223.9  316.21  4616.5  308.33  4674.6  308.36  4859.6   302.3
  4952.9  301.56  4969.7  300.43  4988.4  296.99    4993   294.2  5004.5  295.59
  5015.4  299.14  5030.5   300.2  5132.9  299.82  5572.3  305.36  5602.3  304.75
  5623.5  306.17  5629.5  305.33  5650.6  308.28  5659.7   307.5  5701.8  309.18
  5731.9  308.67  5795.1  311.47  5840.3  311.67  6020.9  318.51  6099.1  323.16
#Mann= 3 ,-1 , 0
  3619.3     .11       0  4969.7     .06       0  5030.5     .11       0
#XS Ineff= 2 , 0
       0  4909.5  302.09               0
Permanent Ineff=
       F       F
Bank Sta=4969.7,5030.5
XS Rating Curve= 0 ,0
Exp/Cntr=0.3,0.1

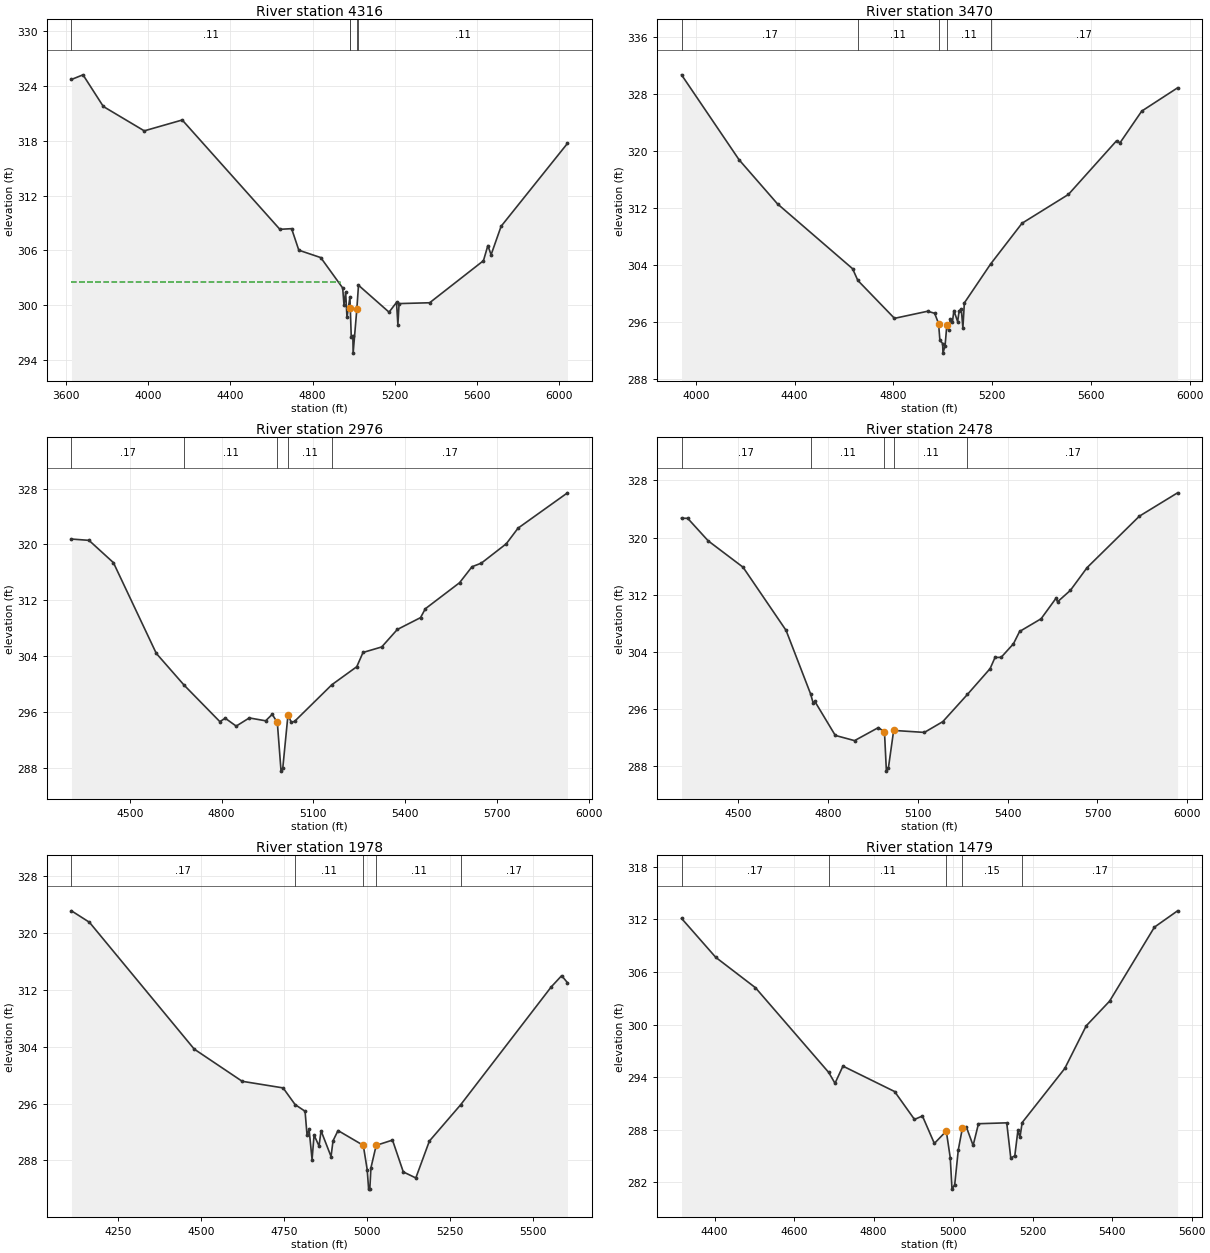
Type RM Length L Ch R = 1 ,4316    ,846,846,846
BEGIN DESCRIPTION:
Conroe Lake 091 8.0
END DESCRIPTION:
XS GIS Cut Line= 3
      3735288.78     10203219.33      3734411.88     10202161.29
      3733886.89      10201261.9
#Sta/Elev= 30
  3625.8  324.74    3682  325.25    3781  321.78  3980.3  319.11  4165.2   320.3
  4640.6  308.32  4697.9  308.39    4733  306.03  4839.8  305.22  4946.6  301.89
  4953.1  300.01    4961  301.43  4967.5  298.67  4981.8  300.89 4983.64  299.67
  4988.3  296.55  4996.1  296.68  4997.5  294.75  5015.4  299.54  5023.6  302.19
  5172.4  299.24  5208.7  300.31  5215.4  297.87  5221.2  300.18    5370  300.27
  5632.1  304.88  5653.6  306.54  5669.3  305.53  5718.1  308.65  6041.4  317.74
#Mann= 5 ,-1 , 0
  3625.8     .11       0  4981.8     .08       0 4983.64     .06       0
  5015.4     .08       0  5023.6     .11       0
#XS Ineff= 2 , 0
       0  4932.3   302.5  5023.6       0  302.19
Permanent Ineff=
       F       T
Bank Sta=4983.64,5015.4
XS Rating Curve= 0 ,0
Exp/Cntr=0.3,0.1

Type RM Length L Ch R = 1 ,3470    ,494,494,494
BEGIN DESCRIPTION:
Conroe Lake 091 7.0
END DESCRIPTION:
XS GIS Cut Line= 4
      3735188.69     10202260.02      3734435.75     10201517.32
      3734412.76     10201491.97      3733639.32     10200998.84
#Sta/Elev= 30
  3942.4  330.75  4175.6   318.8  4331.2   312.6  4635.2  303.49  4656.5  301.84
  4804.9  296.51  4939.3  297.51  4967.6  297.22  4983.5  295.78  4988.8  293.44
    5000  292.96  5001.3  291.62  5009.8  292.66  5017.2  295.64  5023.9  294.94
  5031.4  296.36  5039.7  296.03  5045.6   297.6  5060.8  296.05  5066.7  297.55
  5075.6   297.8    5082  295.16  5087.9  298.68  5194.3  304.15  5321.5  309.88
  5509.4  313.93  5704.2  321.47  5718.4  321.19  5806.4  325.65  5951.5  328.92
#Mann= 5 ,-1 , 0
  3942.4     .17       0  4656.5     .11       0  4983.5     .09       0
  5017.2     .11       0  5194.3     .17       0
Bank Sta=4983.5,5017.2
XS Rating Curve= 0 ,0
Exp/Cntr=0.3,0.1

Type RM Length L Ch R = 1 ,2976    ,498,498,498
BEGIN DESCRIPTION:
Conroe Lake 091 6.0
END DESCRIPTION:
XS GIS Cut Line= 3
      3735241.41     10201364.51      3734595.36     10201119.92
      3733681.27     10200946.48
#Sta/Elev= 30
  4309.2  320.77  4366.5  320.58  4446.3  317.39  4586.4  304.39  4676.9  299.86
  4794.2  294.61  4811.7   295.1  4847.6  293.97  4890.4  295.14  4943.9  294.73
  4965.3  295.66    4982  294.49  4994.2  287.52    5000  288.02  5016.7  295.51
    5028  294.52  5038.2  294.64  5160.3   299.9  5241.7  302.48  5262.1  304.52
  5323.2  305.31  5374.1  307.81  5450.1  309.51  5465.7  310.78  5577.6  314.51
  5618.3   316.8  5648.9  317.32  5730.3  320.09  5768.8  322.33  5930.4  327.39
#Mann= 5 ,-1 , 0
  4309.2     .17       0  4676.9     .11       0    4982     .09       0
  5016.7     .11       0  5160.3     .17       0
#XS Ineff= 2 , 0
       0  4731.9  297.28               0
Permanent Ineff=
       F       F
Bank Sta=4982,5016.7
XS Rating Curve= 0 ,0
Exp/Cntr=0.3,0.1

Type RM Length L Ch R = 1 ,2478    ,500,500,500
BEGIN DESCRIPTION:
Conroe Lake 091 5.0
END DESCRIPTION:
XS GIS Cut Line= 3
      3735287.91     10200806.73       3734616.8      10200650.3
      3733673.46     10200865.59
#Sta/Elev= 30
  4310.9  322.72  4331.5   322.7  4400.1  319.54  4516.3  315.86  4660.1  307.01
  4742.2  298.09  4750.8   296.8    4756  297.08  4824.4  292.31  4888.8  291.58
  4968.1   293.4  4988.7  292.81  4995.1  287.31    5002  287.81  5019.4  293.01
    5122  292.73  5183.6  294.24  5265.6  298.04  5341.5  301.66  5357.9  303.22
  5378.4  303.24  5419.5  305.14    5440  306.86  5511.8  308.64  5561.6  311.51
  5566.7  311.01  5609.7  312.62  5665.6  315.81    5840     323  5967.6  326.27
#Mann= 5 ,-1 , 0
  4310.9     .17       0  4742.2     .11       0  4988.7     .09       0
  5019.4     .11       0  5265.6     .17       0
Bank Sta=4988.7,5019.4
XS Rating Curve= 0 ,0
Exp/Cntr=0.3,0.1

Type RM Length L Ch R = 1 ,1978    ,499,499,499
BEGIN DESCRIPTION:
Conroe Lake 091 4.0
END DESCRIPTION:
XS GIS Cut Line= 4
      3735273.18     10200749.16      3734566.84     10200278.86
      3734526.43     10200268.53      3733951.07     10200088.39
#Sta/Elev= 30
  4109.7  323.07  4163.8  321.46  4479.3  303.64  4623.6  299.12  4746.8  298.19
  4782.9  295.85  4812.9  294.91  4818.9  291.53    4825  292.36    4834  288.13
    4840  291.56    4855  290.02    4861  292.17  4891.1  288.55  4897.1  290.76
  4912.1   292.2  4988.2  290.12    5000  286.69  5004.2  283.97  5007.8  283.97
  5011.2  286.96 5027.02  290.12  5076.1  290.86  5108.6  286.39  5146.3  285.54
  5187.1  290.72  5281.4  295.83  5553.9  312.38  5585.3  313.96  5602.9  312.97
#Mann= 5 ,-1 , 0
  4109.7     .17       0  4782.9     .11       0  4988.2     .09       0
 5027.02     .11       0  5281.4     .17       0
Bank Sta=4988.2,5027.02
XS Rating Curve= 0 ,0
Exp/Cntr=0.3,0.1

Type RM Length L Ch R = 1 ,1479    ,499,499,499
BEGIN DESCRIPTION:
Conroe Lake 091 3.0
END DESCRIPTION:
XS GIS Cut Line= 3
      3735253.81     10199861.59      3734570.58     10199876.94
      3734014.77     10199976.16
#Sta/Elev= 30
  4316.6  312.12  4402.6  307.68  4502.6  304.21  4686.9  294.55  4702.7  293.31
  4722.7  295.27  4852.7  292.37  4902.7  289.19  4922.7  289.58  4952.7  286.45
  4982.7  287.86  4992.7  284.82  4997.1  281.24  5003.9  281.74  5012.9  285.71
  5023.1  288.17  5033.2  288.33  5050.2  286.22  5063.7   288.7  5134.8   288.8
    5145  284.78  5155.1  285.05    5163  287.96  5168.1  287.14  5173.6  288.83
  5280.8     295  5334.7  299.86  5393.6  302.68  5506.4  311.12  5564.6  312.98
#Mann= 5 ,-1 , 0
  4316.6     .17       0  4686.9     .11       0  4982.7     .09       0
  5023.1     .15       0  5173.6     .17       0
#XS Ineff= 2 , 0
       0  4722.7  295.27               0
Permanent Ineff=
       F       F
Bank Sta=4982.7,5023.1
XS Rating Curve= 0 ,0
Exp/Cntr=0.3,0.1

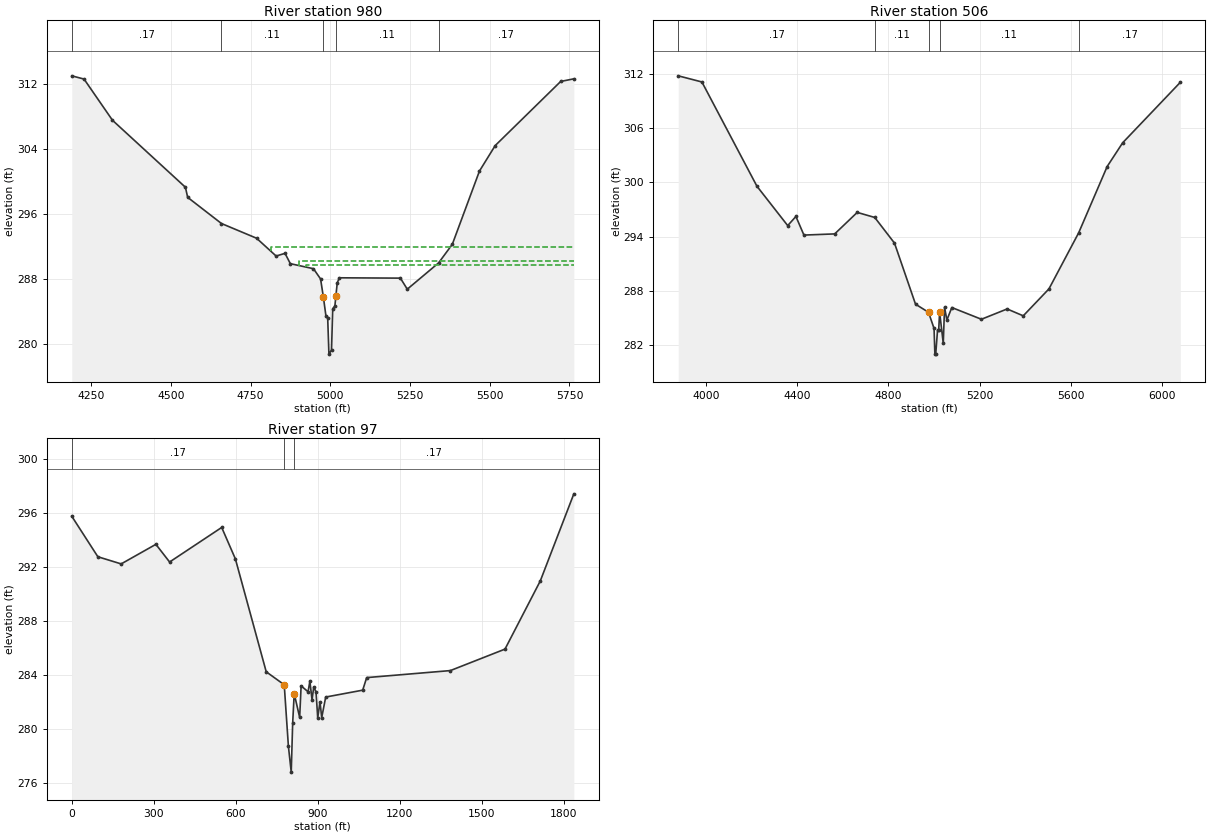
Type RM Length L Ch R = 1 ,980     ,474,474,474
BEGIN DESCRIPTION:
Conroe Lake 091 2.0
END DESCRIPTION:
XS GIS Cut Line= 3
      3735272.39     10199805.82      3734548.45     10199440.93
      3733983.28     10199954.57
#Sta/Elev= 30
  4189.3  312.96  4227.8  312.56    4317  307.49  4545.7  299.25  4552.7  298.01
  4658.7  294.79  4768.8  292.98  4830.1  290.79    4858  291.12  4874.7  289.85
  4947.2  289.23  4969.5  287.97  4978.3  285.74  4986.2  283.45  4991.8  283.19
  4995.7  278.72  5003.8  279.22  5007.6  284.31  5014.4  284.64 5017.41  285.84
  5021.8   287.5  5028.5  288.11  5219.8  288.07  5241.4  286.71  5339.5  289.94
  5382.6  292.23  5467.8  301.25  5517.1  304.38  5722.5  312.27  5763.7  312.59
#Mann= 5 ,-1 , 0
  4189.3     .17       0  4658.7     .11       0  4978.3     .09       0
 5017.41     .11       0  5339.5     .17       0
#XS Ineff= 3 ,-1
  4813.4  4776.7   291.9  4902.6  4880.3  290.14  4924.9  4911.1  289.71
Permanent Ineff=
       F       F       F
Bank Sta=4978.3,5017.41
XS Rating Curve= 0 ,0
Exp/Cntr=0.3,0.1

Type RM Length L Ch R = 1 ,506     ,409,409,409
BEGIN DESCRIPTION:
Conroe Lake 091 1.0
END DESCRIPTION:
XS GIS Cut Line= 4
      3735315.79     10199750.06      3734473.26     10199011.22
      3734452.91     10199009.33      3733930.63     10199929.74
#Sta/Elev= 30
  3879.4  311.79  3983.1  311.11  4224.1  299.57  4358.9  295.21  4394.9  296.22
    4430  294.16  4564.8  294.29  4663.5  296.67  4740.2  296.11  4826.7  293.27
  4918.8  286.51  4975.7  285.61    5000  283.82  5003.6  280.98  5007.3  280.98
  5015.4  283.68  5020.4  283.68  5024.4  285.64  5040.3  282.17    5046  286.17
  5056.1  284.75  5077.8  286.14  5207.5  284.84  5320.1  285.98  5390.7  285.22
  5503.2   288.2  5633.5  294.41  5758.3  301.75  5826.3  304.38  6078.7  311.07
#Mann= 5 ,-1 , 0
  3879.4     .17       0  4740.2     .11       0  4975.7     .09       0
  5024.4     .11       0  5633.5     .17       0
#XS Ineff= 2 , 0
       0  4663.5  296.67               0
Permanent Ineff=
       F       F
Bank Sta=4975.7,5024.4
XS Rating Curve= 0 ,0
Exp/Cntr=0.3,0.1

Type RM Length L Ch R = 1 ,97      ,0,0,0
XS GIS Cut Line= 4
      3735193.07     10199301.04      3734688.29     10198732.03
      3734597.15     10198699.69      3734009.04      10199484.2
#Sta/Elev= 30
       0  295.77    95.5  292.77   180.8  292.24   307.9  293.69   358.1  292.38
   548.8  294.94   598.9  292.61   711.8  284.25   777.7  283.29   792.9  278.75
   803.3  276.82   808.6  280.45   814.2  282.64   834.2  280.87   839.5  283.21
   864.9  282.77   871.6  283.55   879.5  282.17   885.7  283.13   894.1  282.76
   900.3  280.84   908.7  282.02   914.9  280.86   929.5  282.38  1064.9  282.89
  1079.5  283.82  1385.8  284.34  1585.8  285.93    1715  290.98  1837.8  297.43
#Mann= 3 , 0 , 0
       0     .17       0   777.7     .09       0   814.2     .17       0
Bank Sta=777.7,814.2
XS Rating Curve= 0 ,0
Exp/Cntr=0.3,0.1

Chan Stop Cuts=-1
Use User Specified Reach Order=0
Composite Channel Slope=5