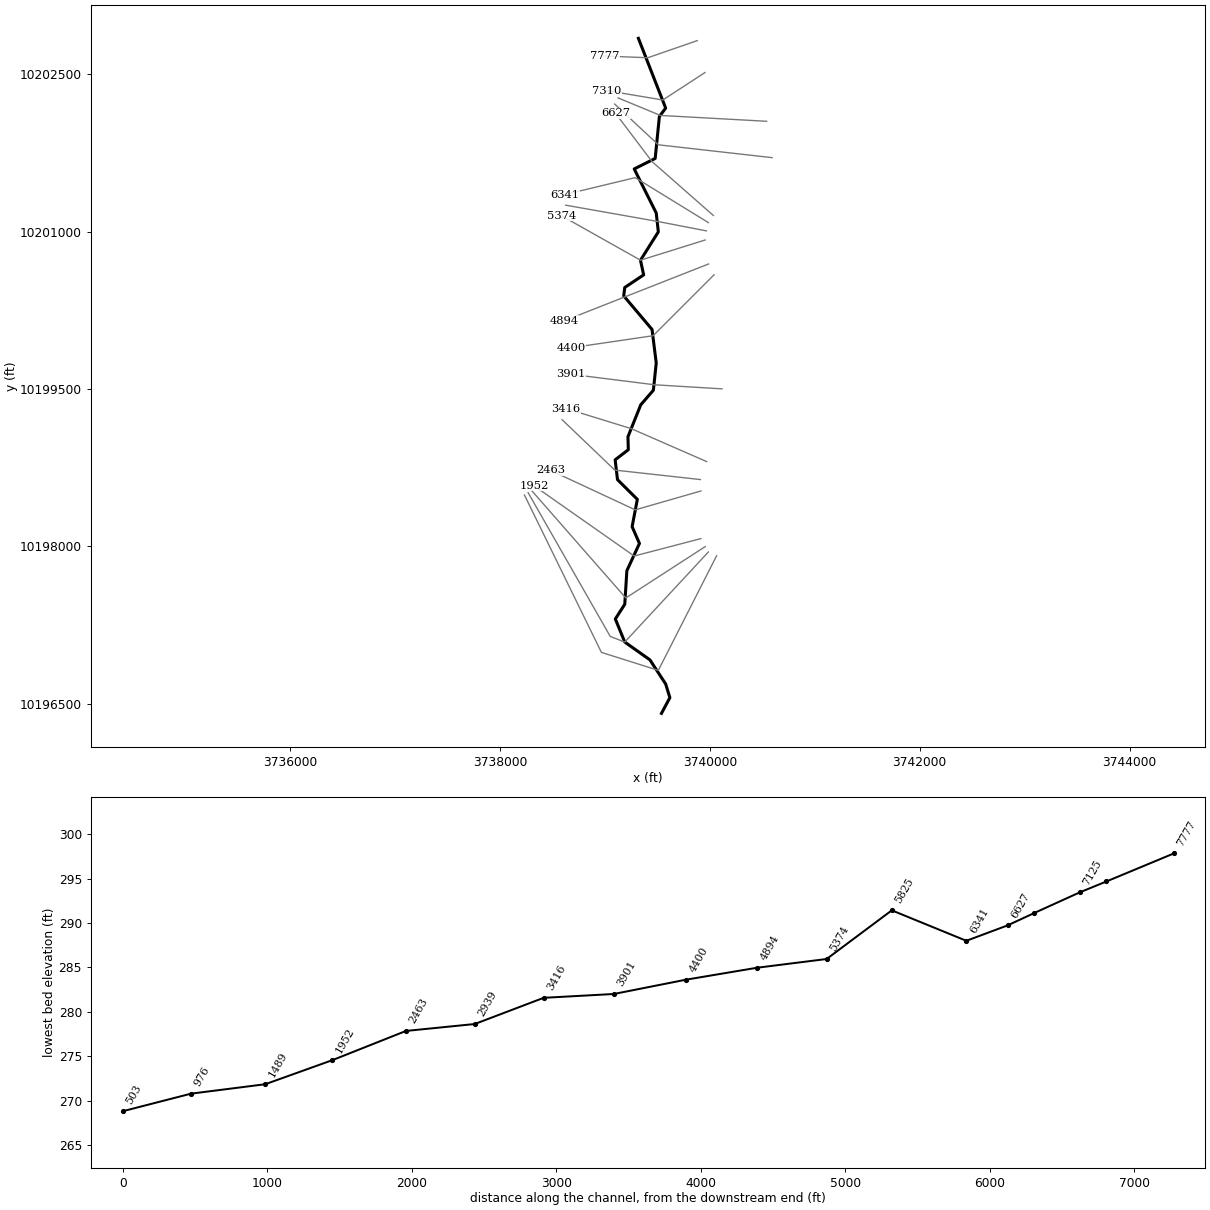
--- Conroe Lake 092.prj (project) ---

Proj Title=Conroe Lake 092 Base Level Engineering
Current Plan=p01
Default Exp/Contr=0.3,0.1
English Units
Geom File=g01
Flow File=f01
Flow File=f02
Plan File=p01
Y Axis Title=Elevation
X Axis Title(PF)=Main Channel Distance
X Axis Title(XS)=Station
BEGIN DESCRIPTION:
Conroe Lake 092
END DESCRIPTION:
DSS Export Rating Curves= 0
DSS Export Rating Curve Sorted= 0
DSS Export Volume Flow Curves= 0
DXF OffsetX= 0
DXF OffsetY= 0
DXF ScaleX= 1
DXF ScaleY= 10

--- Conroe Lake 092.p01 (plan) ---

Plan Title=Multiple Run
Short Identifier=Multiple
Geom File=g01
Flow File=f01
Subcritical Flow
K Sum by GR= 0
Std Step Tol= 0.01
Critical Tol= 0.01
Num of Std Step Trials= 20
Max Error Tol= 0.3
Flow Tol Ratio= 0.001
Split Flow NTrial= 30
Split Flow Tol= 0.02
Split Flow Ratio= 0.02
Log Output Level= 0
Friction Slope Method= 1
Unsteady Friction Slope Method= 2
Unsteady Bridges Friction Slope Method= 1
Parabolic Critical Depth
Global Vel Dist=  1 , 1 , 1
Global Log Level= 0
CheckData=True
Encroach Param= -1, 0, 0, 0
BEGIN DESCRIPTION:
Multiple Run
END DESCRIPTION:

--- Conroe Lake 092.f01 (steady flow) ---

Flow Title=Multiple
Program Version=4.10
Number of Profiles= 7
Profile Names=10-year,25-year,50-year,1pct_min,100-year,1pct_plu,500-year
River Rch & RM=Conroe Lake 092,Reach-1         ,7777
     544     741    1004     449    1356    4095    2554
River Rch & RM=Conroe Lake 092,Reach-1         ,7125
     768    1061    1452     654    1975    5964    3779
River Rch & RM=Conroe Lake 092,Reach-1         ,3416
     744    1017    1382     618    1866    5635    3516
Boundary for River Rch & Prof#=Conroe Lake 092,Reach-1         , 1
Up Type= 0
Dn Type= 3
Dn Slope=0.005
Boundary for River Rch & Prof#=Conroe Lake 092,Reach-1         , 2
Up Type= 0
Dn Type= 3
Dn Slope=0.005
Boundary for River Rch & Prof#=Conroe Lake 092,Reach-1         , 3
Up Type= 0
Dn Type= 3
Dn Slope=0.005
Boundary for River Rch & Prof#=Conroe Lake 092,Reach-1         , 4
Up Type= 0
Dn Type= 3
Dn Slope=0.005
Boundary for River Rch & Prof#=Conroe Lake 092,Reach-1         , 5
Up Type= 0
Dn Type= 3
Dn Slope=0.005
Boundary for River Rch & Prof#=Conroe Lake 092,Reach-1         , 6
Up Type= 0
Dn Type= 3
Dn Slope=0.005
Boundary for River Rch & Prof#=Conroe Lake 092,Reach-1         , 7
Up Type= 0
Dn Type= 3
Dn Slope=0.005
DSS Import GetInterval= 0
DSS Import GetPeak= 0
DSS Import FillOption= 0

--- Conroe Lake 092.f02 (steady flow) ---

Flow Title=Orig_BLE_Flow
Program Version=4.10
Number of Profiles= 7
Profile Names=10-year,25-year,50-year,1pct_min,100-year,1pct_plu,500-year
River Rch & RM=Conroe Lake 092,Reach-1         ,7777
     544     726     873     345    1043    3150    1485
River Rch & RM=Conroe Lake 092,Reach-1         ,7125
     768    1040    1263     503    1519    4588    2197
River Rch & RM=Conroe Lake 092,Reach-1         ,3416
     744     997    1202     475    1435    4334    2044
Boundary for River Rch & Prof#=Conroe Lake 092,Reach-1         , 1
Up Type= 0
Dn Type= 3
Dn Slope=0.005
Boundary for River Rch & Prof#=Conroe Lake 092,Reach-1         , 2
Up Type= 0
Dn Type= 3
Dn Slope=0.005
Boundary for River Rch & Prof#=Conroe Lake 092,Reach-1         , 3
Up Type= 0
Dn Type= 3
Dn Slope=0.005
Boundary for River Rch & Prof#=Conroe Lake 092,Reach-1         , 4
Up Type= 0
Dn Type= 3
Dn Slope=0.005
Boundary for River Rch & Prof#=Conroe Lake 092,Reach-1         , 5
Up Type= 0
Dn Type= 3
Dn Slope=0.005
Boundary for River Rch & Prof#=Conroe Lake 092,Reach-1         , 6
Up Type= 0
Dn Type= 3
Dn Slope=0.005
Boundary for River Rch & Prof#=Conroe Lake 092,Reach-1         , 7
Up Type= 0
Dn Type= 3
Dn Slope=0.005
DSS Import GetInterval= 0
DSS Import GetPeak= 0
DSS Import FillOption= 0

--- Conroe Lake 092.g01 (geometry) ---

Geom Title=Existing Conditions
Program Version=4.10

River Reach=Conroe Lake 092 ,Reach-1
Reach XY= 30
      3739318.23     10202841.84      3739578.23     10202176.84
      3739518.23     10202096.84      3739478.23     10201696.84
      3739278.23     10201596.84      3739488.23     10201176.84
      3739508.23     10200996.84      3739338.23     10200726.84
      3739368.23     10200586.84      3739188.23     10200466.84
      3739178.23     10200386.84      3739448.23     10200066.84
      3739488.23     10199746.84      3739460.99     10199487.47
      3739340.67     10199348.25      3739218.64     10199044.02
      3739222.07     10198920.26       3739096.6     10198824.01
      3739118.95     10198634.94      3739308.23     10198446.84
      3739258.23     10198186.84      3739328.23     10198026.84
      3739208.23     10197766.84      3739188.23     10197446.84
      3739098.23     10197306.84      3739188.23     10197086.84
      3739428.23     10196916.84      3739578.23     10196686.84
      3739618.23     10196556.84      3739538.23     10196406.84

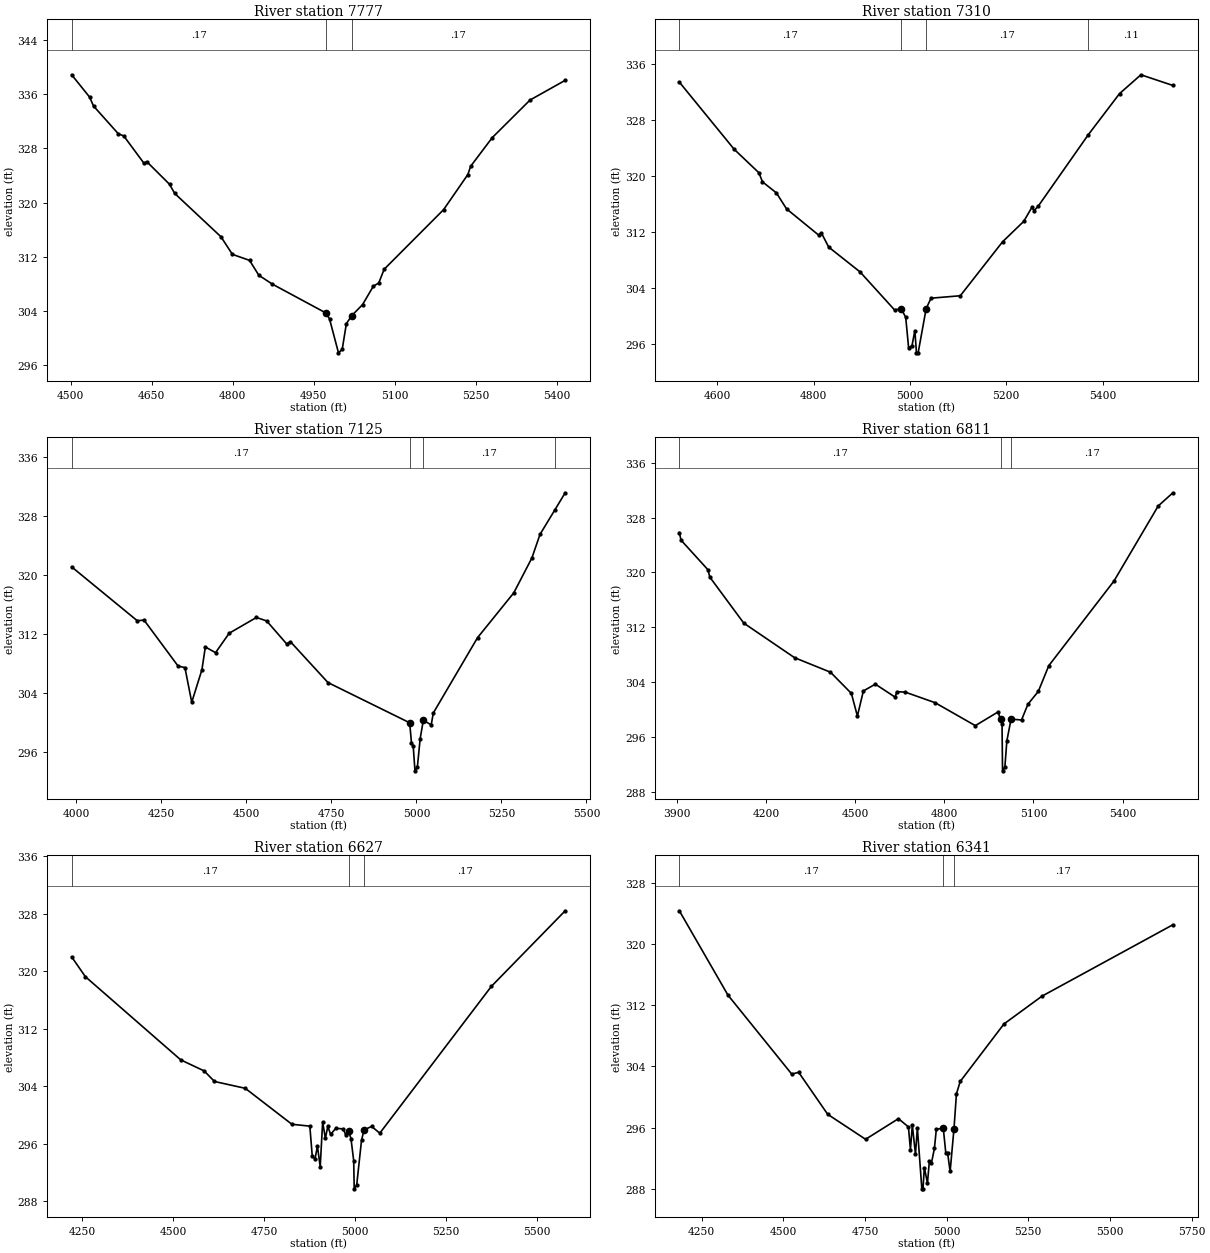
Type RM Length L Ch R = 1 ,7777    ,467,467,467
BEGIN DESCRIPTION:
Conroe Lake 092 16.0
END DESCRIPTION:
XS GIS Cut Line= 3
      3739879.18     10202819.97      3739408.23     10202656.84
      3738992.85     10202673.15
#Sta/Elev= 30
  4501.6  338.88  4534.8  335.59  4542.1  334.27  4587.7   330.2  4598.3  329.83
  4635.5  325.82  4640.8  326.05  4682.9  322.71  4692.5  321.36  4778.2  314.96
  4799.3  312.37  4831.1  311.48  4848.3  309.28  4873.4  307.97  4972.9   303.7
  4979.2  302.84  4995.8  297.83  5002.7  298.33  5010.4  302.14  5020.4  303.32
  5040.4  304.95  5060.4  307.67  5070.4  308.14  5080.4  310.17  5190.5  318.97
  5235.4  324.15  5240.6  325.37  5280.6   329.6  5350.6  335.15  5415.7  338.06
#Mann= 3 , 0 , 0
  4501.6     .17       0  4972.9     .09       0  5020.4     .17       0
Bank Sta=4972.9,5020.4
XS Rating Curve= 0 ,0
Exp/Cntr=0.3,0.1

Type RM Length L Ch R = 1 ,7310    ,185,185,185
BEGIN DESCRIPTION:
Conroe Lake 092 15.0
END DESCRIPTION:
XS GIS Cut Line= 3
      3739952.61     10202515.49      3739550.97     10202254.11
      3739012.33     10202344.11
#Sta/Elev= 30
  4520.8  333.46  4634.8  323.83  4686.1  320.47  4693.5  319.17  4722.4  317.59
  4743.5   315.3    4810  311.55  4815.9  311.85  4831.1  309.82  4896.3  306.26
  4967.9  300.82  4981.9  300.99  4991.1  299.75  4997.1   295.4  5004.1  295.68
  5010.1  297.87  5013.4  294.67  5016.9  294.67  5033.6  301.02  5043.7   302.5
  5104.5  302.85  5192.3  310.58  5236.3  313.51  5253.1   315.5  5258.2  315.06
  5266.8  315.73  5370.6  325.94  5435.3  331.81  5479.7  334.51  5546.1  332.98
#Mann= 4 ,-1 , 0
  4520.8     .17       0  4981.9     .09       0  5033.6     .17       0
  5370.6     .11       0
Bank Sta=4981.9,5033.6
XS Rating Curve= 0 ,0
Exp/Cntr=0.3,0.1

Type RM Length L Ch R = 1 ,7125    ,314,314,314
BEGIN DESCRIPTION:
Mapping XS e14d4bc7
END DESCRIPTION:
XS GIS Cut Line= 3
       3740540.4     10202051.17      3739528.23     10202106.84
      3739123.87     10202274.13
#Sta/Elev= 30
  3986.3  321.07  4179.1  313.78  4199.2  313.86  4299.3  307.63  4319.4  307.43
  4339.4  302.73  4369.4  307.14  4379.4  310.22  4409.5  309.45  4449.5  312.08
  4529.7  314.22  4559.7  313.75  4618.3  310.65  4629.8  310.93    4740   305.4
  4980.3  299.95  4985.6  297.23  4990.6  296.82  4995.9  293.44  5002.9  293.94
  5011.2  297.82  5020.4  300.28  5043.7  299.67  5049.7  301.27    5180  311.49
  5286.5  317.56  5339.7  322.28  5363.6  325.48  5407.9  328.84  5437.6  331.11
#Mann= 4 ,-1 , 0
  3986.3     .17       0  4980.3     .09       0  5020.4     .17       0
  5407.9     .11       0
#XS Ineff= 2 , 0
       0  4529.7  314.22               0
Permanent Ineff=
       F       F
Bank Sta=4980.3,5020.4
XS Rating Curve= 0 ,0
Exp/Cntr=0.3,0.1

Type RM Length L Ch R = 1 ,6811    ,184,184,184
BEGIN DESCRIPTION:
Conroe Lake 092 14.0
END DESCRIPTION:
XS GIS Cut Line= 3
      3740593.45     10201704.42      3739508.23     10201826.84
      3739092.07     10202215.32
#Sta/Elev= 30
  3907.9  325.81  3913.5  324.71  4004.1   320.4  4010.5  319.32  4124.9  312.62
  4295.9  307.59  4416.7  305.48  4487.1  302.39  4507.3  299.09  4527.4  302.75
  4567.7  303.74  4634.7  301.84  4639.7  302.64  4668.3  302.58  4768.9  301.04
  4904.3   297.7  4980.3  299.68  4989.2  298.68  4994.2  297.92  4995.9  291.12
  5003.7  291.62  5010.4  295.48  5024.6  298.65  5059.8  298.52  5081.3  300.81
  5116.5   302.7  5151.6  306.43    5371  318.75    5520  329.68  5569.3   331.6
#Mann= 3 , 0 , 0
  3907.9     .17       0  4989.2     .09       0  5024.6     .17       0
#XS Ineff= 2 , 0
       0  4567.7  303.74               0
Permanent Ineff=
       F       F
Bank Sta=4989.2,5024.6
XS Rating Curve= 0 ,0
Exp/Cntr=0.3,0.1

Type RM Length L Ch R = 1 ,6627    ,286,286,286
BEGIN DESCRIPTION:
Mapping XS 5a6462e0
END DESCRIPTION:
XS GIS Cut Line= 3
      3740033.03     10201152.96      3739448.23     10201666.84
       3739100.2     10202127.45
#Sta/Elev= 30
  4221.5  321.99  4259.1  319.24  4521.3  307.66  4585.5  306.13  4613.9  304.66
  4698.4  303.71  4826.5  298.71  4875.8  298.45  4882.5  294.25  4890.1  293.92
  4896.7  295.65  4904.3  292.79    4911  299.02  4918.5  296.76  4925.2  298.43
  4932.8   297.3    4947  298.14  4967.9  298.07  4974.5   297.2  4982.1  297.83
  4988.8  296.72  4996.3  293.65  4997.7  289.73  5004.5  290.23  5017.8  296.49
  5024.8  297.93  5045.6  298.41    5068  297.47  5374.4  317.88  5577.3   328.4
#Mann= 3 , 0 , 0
  4221.5     .17       0  4982.1     .09       0  5024.8     .17       0
#XS Ineff= 2 , 0
       0    4911  299.02               0
Permanent Ineff=
       F       F
Bank Sta=4982.1,5024.8
XS Rating Curve= 0 ,0
Exp/Cntr=0.3,0.1

Type RM Length L Ch R = 1 ,6341    ,516,516,516
BEGIN DESCRIPTION:
Conroe Lake 092 13.0
END DESCRIPTION:
XS GIS Cut Line= 3
      3739985.19     10201085.41      3739288.23     10201514.01
      3738614.98     10201351.85
#Sta/Elev= 30
  4181.8  324.36  4330.6  313.33  4525.8     303  4547.1  303.23  4635.9  297.74
  4751.9  294.47  4852.5  297.17    4883  296.09  4889.2  293.13    4895  296.29
  4904.6  292.52  4910.4  295.99  4924.1  287.99  4927.6  287.99  4931.7  290.77
  4941.3  288.74  4947.1   291.6  4953.5  291.37  4962.6  293.27  4968.4  295.78
  4989.7  295.93  4997.3  292.73  5002.8  292.73  5010.7  290.26 5022.51  295.87
    5030  300.41  5041.5  302.03  5175.3  309.55  5291.8  313.19  5692.5  322.53
#Mann= 3 , 0 , 0
  4181.8     .17       0  4989.7     .09       0 5022.51     .17       0
Bank Sta=4989.7,5022.51
XS Rating Curve= 0 ,0
Exp/Cntr=0.3,0.1

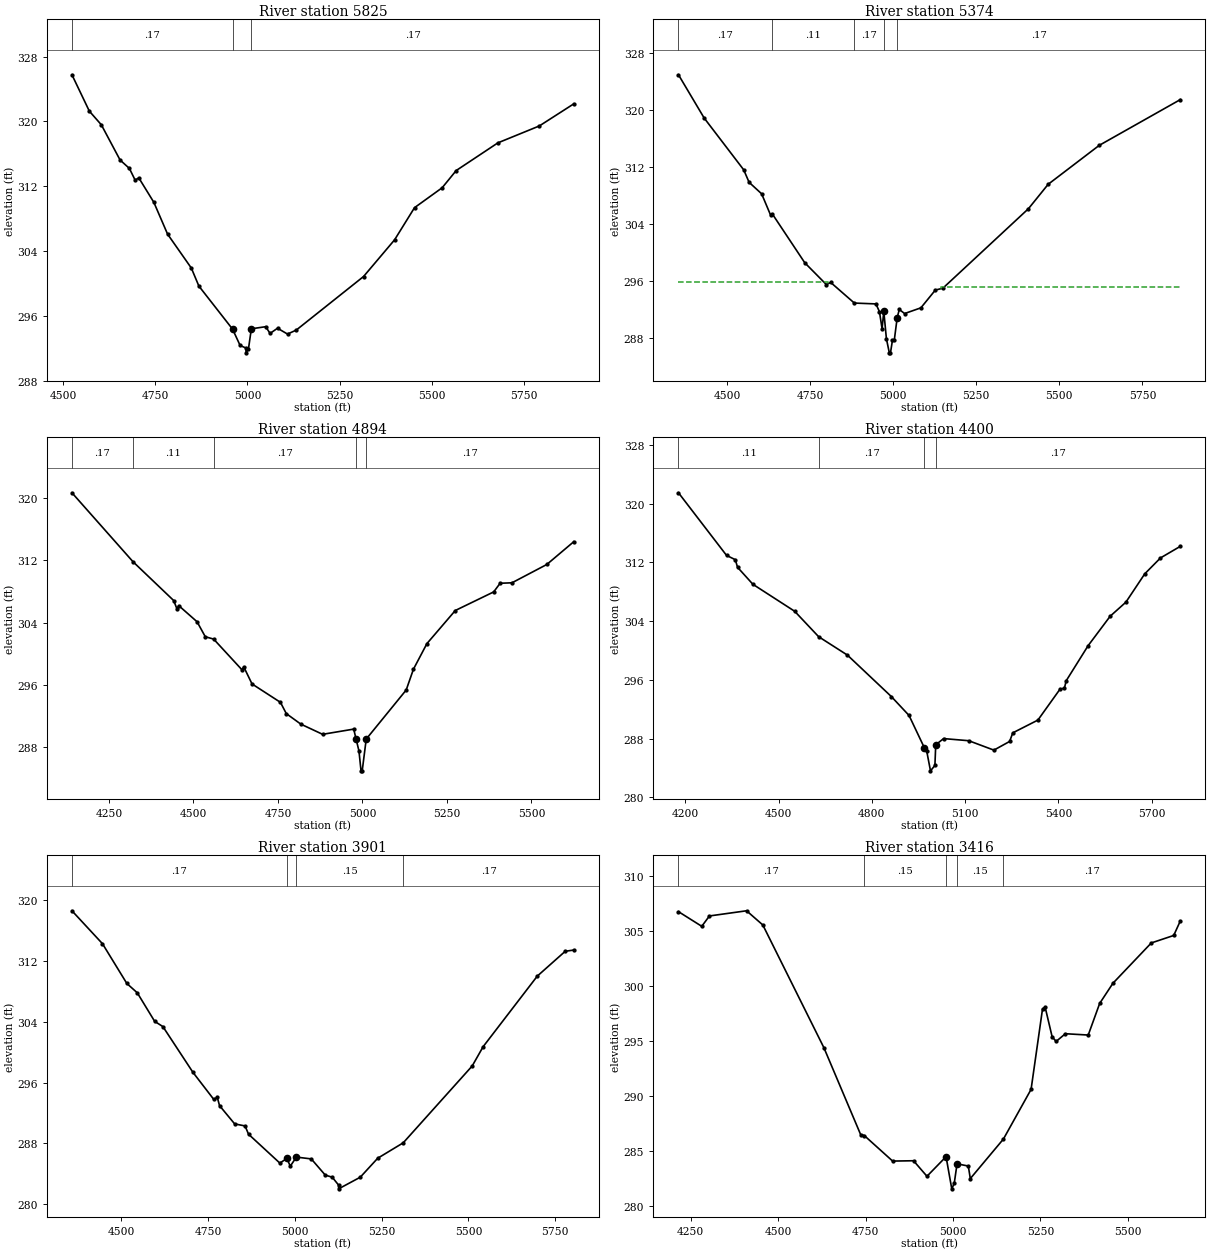
Type RM Length L Ch R = 1 ,5825    ,451,451,451
BEGIN DESCRIPTION:
Conroe Lake 092 12.0
END DESCRIPTION:
XS GIS Cut Line= 3
       3739966.2     10201006.55      3739498.23     10201096.84
      3738625.79     10201251.25
#Sta/Elev= 30
  4523.4  325.77  4570.6  321.28  4603.2  319.59  4654.1  315.24  4679.4   314.2
  4694.9  312.76    4705  313.03  4745.8  310.01  4783.1  306.08  4847.6  301.89
    4868  299.67  4959.6  294.34    4980  292.33  4995.6  292.02  4996.2  291.42
  5002.7  291.92  5010.5  294.39  5049.5  294.65  5061.3  293.82  5081.6  294.46
  5108.7  293.74  5132.4  294.23  5315.2  300.85  5399.4  305.38  5453.5  309.35
  5528.5  311.81  5566.7  313.94  5679.9  317.36  5792.5  319.45    5886  322.18
#Mann= 3 , 0 , 0
  4523.4     .17       0  4959.6     .09       0  5010.5     .17       0
Bank Sta=4959.6,5010.5
XS Rating Curve= 0 ,0
Exp/Cntr=0.3,0.1

Type RM Length L Ch R = 1 ,5374    ,480,480,480
BEGIN DESCRIPTION:
Conroe Lake 092 11.0
END DESCRIPTION:
XS GIS Cut Line= 3
      3739955.34     10200919.57      3739338.23     10200726.84
      3738585.07     10201150.63
#Sta/Elev= 30
  4353.5  324.93  4430.9  318.86  4549.9   311.6  4566.1  309.85  4603.8  308.24
    4631  305.23  4636.1  305.41  4733.7  298.57  4798.7  295.51  4811.8  295.81
  4882.9  292.92    4948   292.8  4958.5   291.7  4966.4  289.32  4971.6  291.75
  4979.4  287.93  4988.2  285.94  4991.7  285.94  4997.6  287.69  5003.1  287.69
  5011.9  290.87  5018.2  292.02  5034.2  291.45  5083.2  292.25  5126.7  294.74
  5149.6  295.01    5407  306.15  5466.3  309.57    5620  315.03  5864.2  321.45
#Mann= 5 ,-1 , 0
  4353.5     .17       0  4636.1     .11       0  4882.9     .17       0
  4971.6     .09       0  5011.9     .17       0
#XS Ineff= 2 , 0
       0    4804  295.85  5142.5       0  295.22
Permanent Ineff=
       F       F
Bank Sta=4971.6,5011.9
XS Rating Curve= 0 ,0
Exp/Cntr=0.3,0.1

Type RM Length L Ch R = 1 ,4894    ,494,494,494
BEGIN DESCRIPTION:
Conroe Lake 092 10.0
END DESCRIPTION:
XS GIS Cut Line= 3
      3739987.87     10200691.16      3739188.23     10200376.84
      3738606.76     10200147.41
#Sta/Elev= 30
  4140.8  320.67  4321.3  311.82  4441.7  306.83  4451.2  305.78  4456.6  306.18
  4510.8  304.11  4535.2  302.18  4559.9  301.88  4643.6  297.94    4649  298.31
  4673.4  296.12  4757.4  293.76  4774.8  292.31  4817.7  290.96  4882.2  289.65
  4974.2  290.32 4980.84   289.1  4989.7  287.51  4995.8  284.96  4999.3  284.96
  5011.2  289.04  5129.4  295.34  5150.9  298.02  5190.7   301.3  5274.6  305.55
  5388.2  307.94  5407.2  309.05  5442.3  309.11  5545.2  311.46  5625.1  314.39
#Mann= 5 ,-1 , 0
  4140.8     .17       0  4321.3     .11       0  4559.9     .17       0
 4980.84     .09       0  5011.2     .17       0
Bank Sta=4980.84,5011.2
XS Rating Curve= 0 ,0
Exp/Cntr=0.3,0.1

Type RM Length L Ch R = 1 ,4400    ,499,499,499
BEGIN DESCRIPTION:
Conroe Lake 092 9.0
END DESCRIPTION:
XS GIS Cut Line= 3
      3740039.56     10200587.85      3739458.23     10200006.84
      3738674.72     10199891.86
#Sta/Elev= 30
  4178.1  321.46  4332.6  312.94  4360.9  312.35    4368  311.32  4417.5     309
  4551.8  305.33  4628.8  301.87  4721.5  299.36  4862.9  293.71  4919.5  291.15
    4969  286.73  4976.1  286.36  4988.5  283.61  5002.7  284.34  5005.4  287.16
  5030.7     288  5111.6  287.71  5192.4  286.43    5243  287.61  5253.1  288.78
  5333.9  290.52  5404.7  294.71  5419.2  294.87  5424.9  295.87  5495.6  300.66
  5566.4  304.66  5616.9  306.57  5677.6  310.43  5728.1  312.59  5791.9  314.17
#Mann= 4 ,-1 , 0
  4178.1     .11       0  4628.8     .17       0    4969     .09       0
  5005.4     .17       0
Bank Sta=4969,5005.4
XS Rating Curve= 0 ,0
Exp/Cntr=0.3,0.1

Type RM Length L Ch R = 1 ,3901    ,485,485,485
BEGIN DESCRIPTION:
Conroe Lake 092 8.0
END DESCRIPTION:
XS GIS Cut Line= 3
      3740115.68     10199500.37      3739474.74     10199539.04
      3738677.49     10199639.02
#Sta/Elev= 30
  4357.9  318.61  4445.9  314.27    4516  309.04  4546.1  307.81  4596.2  304.05
  4619.9  303.36  4706.4  297.34  4766.5  293.77  4776.5  294.05  4783.1  292.95
  4826.6  290.55  4856.6  290.28  4866.6  289.19  4956.8  285.39  4976.8     286
  4986.9  284.99 5004.48  286.18  5047.3  285.94  5087.6  283.81  5107.7  283.53
  5125.9   282.5  5126.1     282  5188.4  283.53  5238.7  286.03  5312.2  288.06
  5510.9  298.18  5542.4  300.72  5698.4  310.01  5778.9  313.28  5803.5  313.44
#Mann= 4 ,-1 , 0
  4357.9     .17       0  4976.8     .09       0 5004.48     .15       0
  5312.2     .17       0
Bank Sta=4976.8,5004.48
XS Rating Curve= 0 ,0
Exp/Cntr=0.3,0.1

Type RM Length L Ch R = 1 ,3416    ,477,477,477
BEGIN DESCRIPTION:
Conroe Lake 092 7.0
END DESCRIPTION:
XS GIS Cut Line= 3
      3739968.91     10198807.07      3739249.58     10199121.37
       3738628.5     10199312.78
#Sta/Elev= 30
    4215  306.73  4281.6   305.4  4303.5  306.34  4409.7  306.81  4456.2  305.52
  4630.8  294.38  4735.8   286.5  4746.2  286.41  4827.3  284.09  4887.1  284.12
  4925.5  282.71  4980.1  284.49  4996.4  281.57  5003.5  282.07  5011.5  283.84
  5043.7  283.64  5049.4   282.5  5144.1  286.09  5223.2   290.6  5255.9   297.9
  5263.4  298.06  5283.4  295.37  5294.8  294.95  5321.3  295.65  5386.6  295.53
  5419.3   298.4  5457.2  300.23  5566.9  303.89    5631  304.57  5649.9  305.89
#Mann= 5 ,-1 , 0
    4215     .17       0  4746.2     .15       0  4980.1     .09       0
  5011.5     .15       0  5144.1     .17       0
Bank Sta=4980.1,5011.5
XS Rating Curve= 0 ,0
Exp/Cntr=0.3,0.1

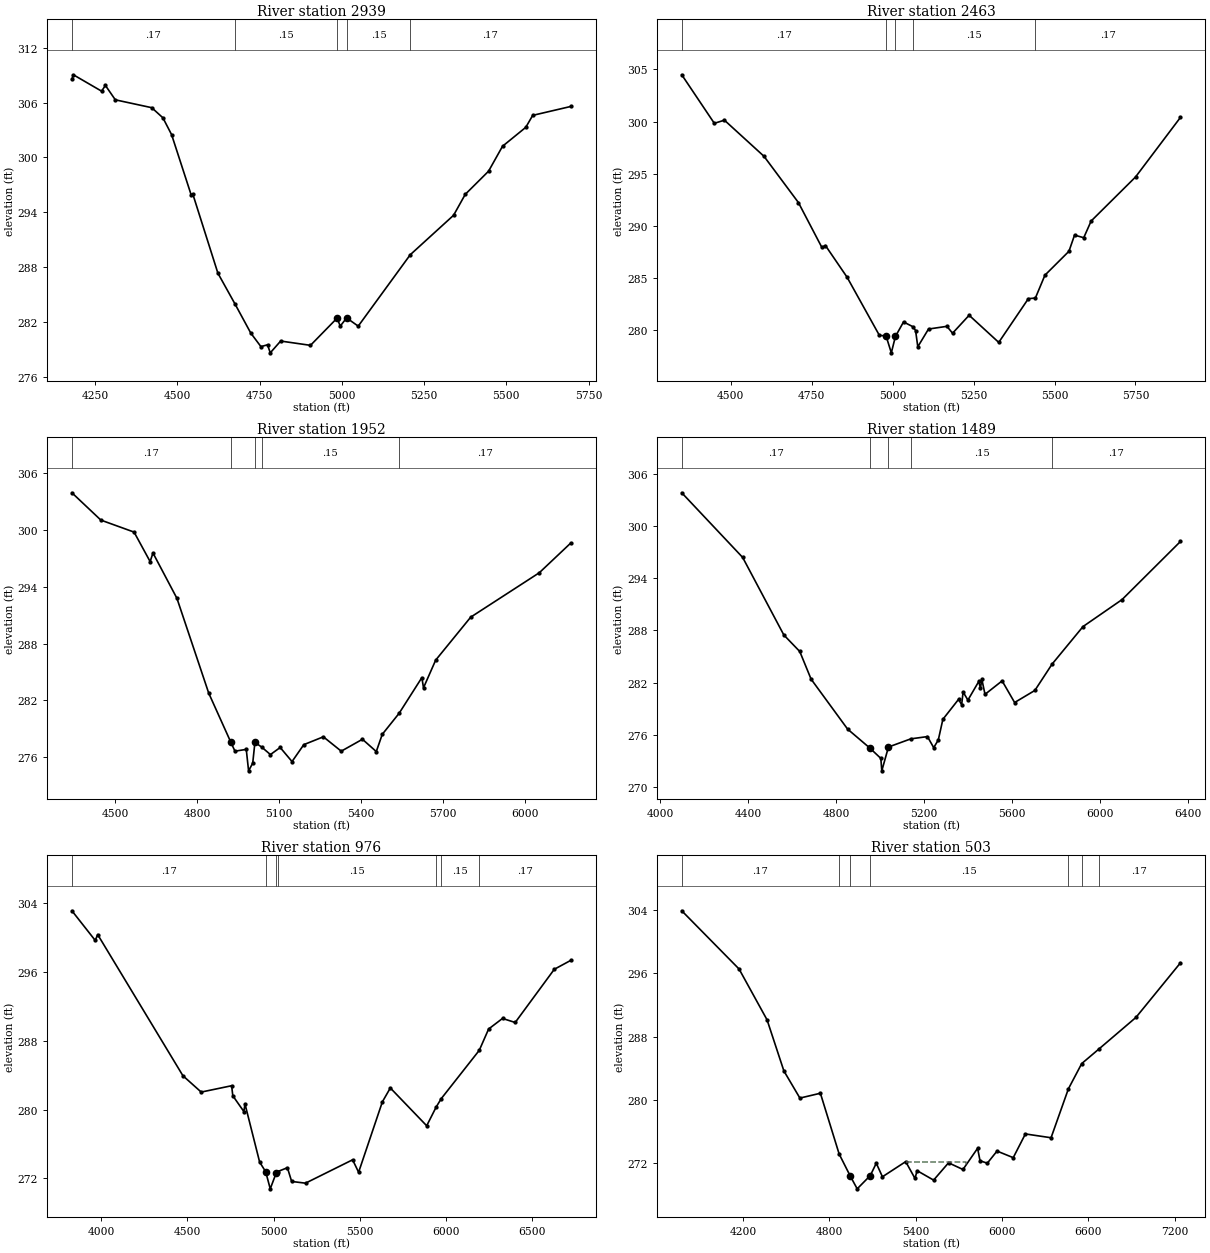
Type RM Length L Ch R = 1 ,2939    ,476,476,476
BEGIN DESCRIPTION:
Conroe Lake 092 6.0
END DESCRIPTION:
XS GIS Cut Line= 3
      3739909.09      10198635.8      3739093.16     10198726.04
       3738590.5     10199206.72
#Sta/Elev= 30
  4179.1  308.54  4183.5  309.04  4269.2  307.25    4281  307.87  4311.1   306.3
  4421.8  305.44  4455.8  304.33  4482.2  302.49  4541.5  295.92  4546.5  296.01
    4623  287.33  4674.6  283.99    4723  280.78  4753.8   279.3  4773.9   279.5
  4782.2  278.62  4813.8  279.91  4904.5  279.44  4985.2  282.41  4995.1  281.55
  5014.4  282.44  5049.6  281.54  5207.8  289.35  5339.6  293.67  5375.1  295.96
  5445.9  298.49  5488.4  301.22  5559.1  303.29  5580.2   304.6  5695.5  305.57
#Mann= 5 ,-1 , 0
  4179.1     .17       0  4674.6     .15       0  4985.2     .09       0
  5014.4     .15       0  5207.8     .17       0
Bank Sta=4985.2,5014.4
XS Rating Curve= 0 ,0
Exp/Cntr=0.3,0.1

Type RM Length L Ch R = 1 ,2463    ,511,511,511
BEGIN DESCRIPTION:
Conroe Lake 092 5.0
END DESCRIPTION:
XS GIS Cut Line= 3
      3739914.52     10198527.05      3739288.23     10198346.84
      3738482.29     10198722.54
#Sta/Elev= 30
  4348.3  304.48  4448.9  299.83  4480.1  300.13  4602.4  296.67  4708.7  292.24
  4781.2  287.94  4792.3  288.12    4859  285.09  4958.8  279.52  4979.6  279.45
  4995.8  277.84 5008.47  279.41  5033.5   280.8  5062.7  280.34  5070.7  279.98
  5077.6  278.42  5110.7  280.12  5167.6  280.38    5185  279.72  5236.2  281.44
  5327.7  278.84  5419.2  283.03  5440.9  283.09  5470.4  285.28  5544.6  287.57
  5561.9  289.12  5590.3  288.87  5613.2  290.47  5750.4  294.69  5889.2   300.4
#Mann= 5 ,-1 , 0
  4348.3     .17       0  4979.6     .09       0 5008.47     .17       0
  5062.7     .15       0  5440.9     .17       0
#XS Ineff= 2 , 0
       0                  5236.2       0  281.44
Permanent Ineff=
       F       T
Bank Sta=4979.6,5008.47
XS Rating Curve= 0 ,0
Exp/Cntr=0.3,0.1

Type RM Length L Ch R = 1 ,1952    ,463,463,463
BEGIN DESCRIPTION:
Conroe Lake 092 4.0
END DESCRIPTION:
XS GIS Cut Line= 3
      3739914.49     10198073.01      3739278.23     10197906.84
      3738324.07     10198575.97
#Sta/Elev= 30
  4342.4  303.96  4448.2  301.07  4569.6   299.8  4628.3  296.68  4638.7  297.59
  4726.3  292.79  4842.5  282.76  4923.4  277.56  4938.4  276.62  4979.7  276.81
  4988.2  274.54  5003.3  275.35  5011.3  277.55  5036.2  277.05    5068  276.26
  5103.7  277.01    5147  275.52    5190  277.31  5261.5  278.14  5326.9  276.62
  5404.4  277.88    5455  276.58  5476.8   278.4  5538.5  280.63  5621.5   284.4
  5627.6  283.33    5672  286.25  5800.1   290.8  6050.9   295.5  6165.4  298.63
#Mann= 5 ,-1 , 0
  4342.4     .17       0  4923.4     .09       0  5011.3     .17       0
  5036.2     .15       0  5538.5     .17       0
Bank Sta=4923.4,5011.3
XS Rating Curve= 0 ,0
Exp/Cntr=0.3,0.1

Type RM Length L Ch R = 1 ,1489    ,513,513,513
BEGIN DESCRIPTION:
Conroe Lake 092 3.0
END DESCRIPTION:
XS GIS Cut Line= 3
      3739955.27     10197996.88      3739198.23     10197506.84
      3738296.84     10198535.22
#Sta/Elev= 30
  4098.2  303.83  4375.4  296.39  4562.7  287.47  4635.2  285.57  4686.7  282.39
  4852.9  276.64  4952.8  274.49  5004.1  273.27  5008.4  271.84  5038.7  274.58
  5140.5  275.52  5216.1  275.78  5244.6  274.51  5265.5  275.39  5286.4  277.77
  5357.6  280.06  5371.8  279.45  5378.4  280.91  5400.3  279.98  5449.6  282.12
  5457.2  281.35  5463.8  282.35  5478.1  280.64  5555.9  282.19  5612.8   279.7
  5704.9  281.09  5783.3  284.12  5924.1  288.44  6101.6  291.54  6367.5  298.23
#Mann= 5 ,-1 , 0
  4098.2     .17       0  4952.8     .09       0  5038.7     .17       0
  5140.5     .15       0  5783.3     .17       0
Bank Sta=4952.8,5038.7
XS Rating Curve= 0 ,0
Exp/Cntr=0.3,0.1

Type RM Length L Ch R = 1 ,976     ,473,473,473
BEGIN DESCRIPTION:
Conroe Lake 092 2.0
END DESCRIPTION:
XS GIS Cut Line= 4
      3739985.19     10197945.22      3739188.23     10197086.84
      3739049.95     10197140.48      3738266.95     10198510.73
#Sta/Elev= 30
  3828.7  303.14  3964.2  299.69  3978.4  300.37  4473.8  283.94  4579.9  282.04
  4756.7  282.78  4763.6  281.61  4827.6  279.78  4834.4  280.65  4919.5  273.89
  4954.6  272.77  4981.1  270.78 5016.49  272.67  5023.3  272.78  5080.8  273.24
  5105.4  271.64    5186  271.44  5459.6  274.16  5494.5  272.71  5632.7  280.91
  5678.8  282.52  5890.1  278.12  5945.7  280.32  5974.8  281.28  6195.6   286.9
    6250  289.38  6330.6  290.61  6404.4  290.14  6631.5  296.33  6726.5  297.36
#Mann= 7 ,-1 , 0
  3828.7     .17       0  4954.6     .09       0 5016.49     .17       0
  5023.3     .15       0  5945.7     .17       0  5974.8     .15       0
  6195.6     .17       0
#XS Ineff= 2 , 0
       0                  5459.6       0  274.16
Permanent Ineff=
       F       F
Bank Sta=4954.6,5016.49
XS Rating Curve= 0 ,0
Exp/Cntr=0.3,0.1

Type RM Length L Ch R = 1 ,503     ,0,0,0
BEGIN DESCRIPTION:
Conroe Lake 092 1.0
END DESCRIPTION:
XS GIS Cut Line= 4
      3740064.02     10197909.85      3739508.23     10196816.84
      3738965.67     10196988.23      3738231.58     10198489.03
#Sta/Elev= 30
  3773.8  303.85  4172.1  296.51  4366.7   290.1  4483.6  283.66  4594.8  280.24
  4737.2  280.85  4867.8  273.18  4945.2   270.4    4993   268.8  5084.3  270.48
  5125.6  272.03  5168.4  270.32  5330.1  272.23  5394.7  270.11  5409.4  271.09
  5524.1   269.9  5627.8  272.08    5728  271.24  5829.8  273.91  5846.7  272.34
  5897.3  272.03  5964.8  273.56  6077.4  272.73  6161.9  275.72  6340.3  275.24
  6460.9  281.41  6553.4  284.59    6670  286.38  6930.3  290.41  7239.7  297.29
#Mann= 7 ,-1 , 0
  3773.8     .17       0  4867.8     .15       0  4945.2     .09       0
  5084.3     .15       0  6460.9     .17       0  6553.4     .15       0
    6670     .17       0
#XS Ineff= 3 ,-1
  5125.6  5330.1  272.03  5330.1 5750.54  272.23  5829.8  6116.8  273.91
Permanent Ineff=
       T       T       F
Bank Sta=4945.2,5084.3
XS Rating Curve= 0 ,0
Exp/Cntr=0.3,0.1

Chan Stop Cuts=-1
Use User Specified Reach Order=0
Composite Channel Slope=5