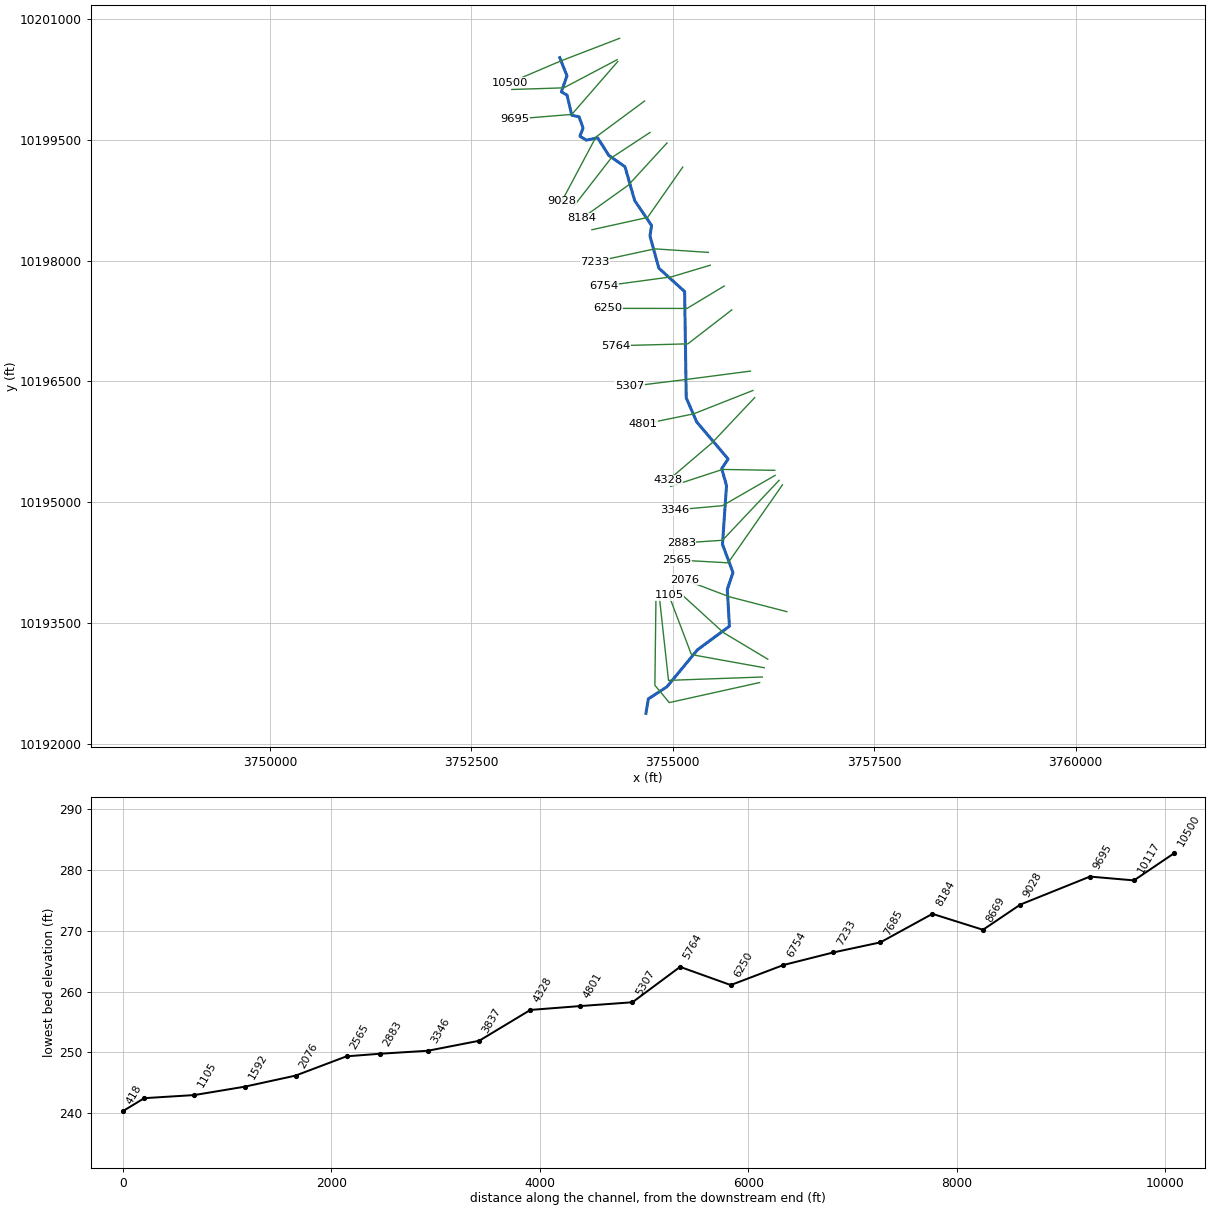
--- Conroe Lake 098.prj (project) ---

Proj Title=Conroe Lake 098 Base Level Engineering
Current Plan=p01
Default Exp/Contr=0.3,0.1
English Units
Geom File=g01
Flow File=f01
Flow File=f02
Plan File=p01
Y Axis Title=Elevation
X Axis Title(PF)=Main Channel Distance
X Axis Title(XS)=Station
BEGIN DESCRIPTION:
Conroe Lake 098
END DESCRIPTION:
DSS Export Rating Curves= 0
DSS Export Rating Curve Sorted= 0
DSS Export Volume Flow Curves= 0
DXF OffsetX= 0
DXF OffsetY= 0
DXF ScaleX= 1
DXF ScaleY= 10

--- Conroe Lake 098.p01 (plan) ---

Plan Title=Multiple Run
Short Identifier=Multiple
Geom File=g01
Flow File=f01
Subcritical Flow
K Sum by GR= 0
Std Step Tol= 0.01
Critical Tol= 0.01
Num of Std Step Trials= 20
Max Error Tol= 0.3
Flow Tol Ratio= 0.001
Split Flow NTrial= 30
Split Flow Tol= 0.02
Split Flow Ratio= 0.02
Log Output Level= 0
Friction Slope Method= 1
Unsteady Friction Slope Method= 2
Unsteady Bridges Friction Slope Method= 1
Parabolic Critical Depth
Global Vel Dist=  1 , 1 , 1
Global Log Level= 0
CheckData=True
Encroach Param= -1, 0, 0, 0
BEGIN DESCRIPTION:
Multiple Run
END DESCRIPTION:

--- Conroe Lake 098.f01 (steady flow) ---

Flow Title=Multiple
Program Version=4.10
Number of Profiles= 7
Profile Names=10-year,25-year,50-year,1pct_min,100-year,1pct_plu,500-year
River Rch & RM=Conroe Lake 098,Reach-1         ,10500
     586     793    1070     475    1435    4334    2671
River Rch & RM=Conroe Lake 098,Reach-1         ,8669
     782    1076    1472     662    1999    6037    3813
River Rch & RM=Conroe Lake 098,Reach-1         ,5764
    1089    1518    2091     945    2855    8622    5509
Boundary for River Rch & Prof#=Conroe Lake 098,Reach-1         , 1
Up Type= 0
Dn Type= 3
Dn Slope=0.01
Boundary for River Rch & Prof#=Conroe Lake 098,Reach-1         , 2
Up Type= 0
Dn Type= 3
Dn Slope=0.01
Boundary for River Rch & Prof#=Conroe Lake 098,Reach-1         , 3
Up Type= 0
Dn Type= 3
Dn Slope=0.01
Boundary for River Rch & Prof#=Conroe Lake 098,Reach-1         , 4
Up Type= 0
Dn Type= 3
Dn Slope=0.01
Boundary for River Rch & Prof#=Conroe Lake 098,Reach-1         , 5
Up Type= 0
Dn Type= 3
Dn Slope=0.01
Boundary for River Rch & Prof#=Conroe Lake 098,Reach-1         , 6
Up Type= 0
Dn Type= 3
Dn Slope=0.01
Boundary for River Rch & Prof#=Conroe Lake 098,Reach-1         , 7
Up Type= 0
Dn Type= 3
Dn Slope=0.01
DSS Import GetInterval= 0
DSS Import GetPeak= 0
DSS Import FillOption= 0

--- Conroe Lake 098.f02 (steady flow) ---

Flow Title=Orig_BLE_Flow
Program Version=4.10
Number of Profiles= 7
Profile Names=10-year,25-year,50-year,1pct_min,100-year,1pct_plu,500-year
River Rch & RM=Conroe Lake 098,Reach-1         ,10500
     586     777     930     366    1104    3334    1553
River Rch & RM=Conroe Lake 098,Reach-1         ,8669
     782    1055    1280     509    1538    4643    2217
River Rch & RM=Conroe Lake 098,Reach-1         ,5764
    1089    1488    1818     727    2196    6632    3203
Boundary for River Rch & Prof#=Conroe Lake 098,Reach-1         , 1
Up Type= 0
Dn Type= 3
Dn Slope=0.01
Boundary for River Rch & Prof#=Conroe Lake 098,Reach-1         , 2
Up Type= 0
Dn Type= 3
Dn Slope=0.01
Boundary for River Rch & Prof#=Conroe Lake 098,Reach-1         , 3
Up Type= 0
Dn Type= 3
Dn Slope=0.01
Boundary for River Rch & Prof#=Conroe Lake 098,Reach-1         , 4
Up Type= 0
Dn Type= 3
Dn Slope=0.01
Boundary for River Rch & Prof#=Conroe Lake 098,Reach-1         , 5
Up Type= 0
Dn Type= 3
Dn Slope=0.01
Boundary for River Rch & Prof#=Conroe Lake 098,Reach-1         , 6
Up Type= 0
Dn Type= 3
Dn Slope=0.01
Boundary for River Rch & Prof#=Conroe Lake 098,Reach-1         , 7
Up Type= 0
Dn Type= 3
Dn Slope=0.01
DSS Import GetInterval= 0
DSS Import GetPeak= 0
DSS Import FillOption= 0

--- Conroe Lake 098.g01 (geometry) ---

Geom Title=Existing Conditions
Program Version=4.10

River Reach=Conroe Lake 098 ,Reach-1
Reach XY= 30
      3753598.23     10200521.84      3753688.23     10200296.84
      3753618.23     10200096.84      3753688.23     10200056.84
      3753748.23     10199806.84      3753838.23     10199786.84
      3753888.23     10199646.84      3753848.23     10199546.84
      3753928.23     10199496.84      3754068.23     10199526.84
      3754208.23     10199306.84      3754408.23     10199166.84
      3754528.23     10198746.84      3754738.23     10198436.84
      3754718.23     10198306.84      3754828.23     10197906.84
      3755148.23     10197616.84      3755168.23     10196296.84
      3755298.23     10195996.84      3755688.23     10195536.84
      3755608.23     10195416.84      3755668.23     10195206.84
      3755618.23     10194476.84      3755748.23     10194126.84
      3755678.23     10193916.84      3755704.26     10193459.36
      3755308.23     10193166.84      3754928.23     10192706.84
      3754698.23     10192556.84      3754668.23     10192376.84

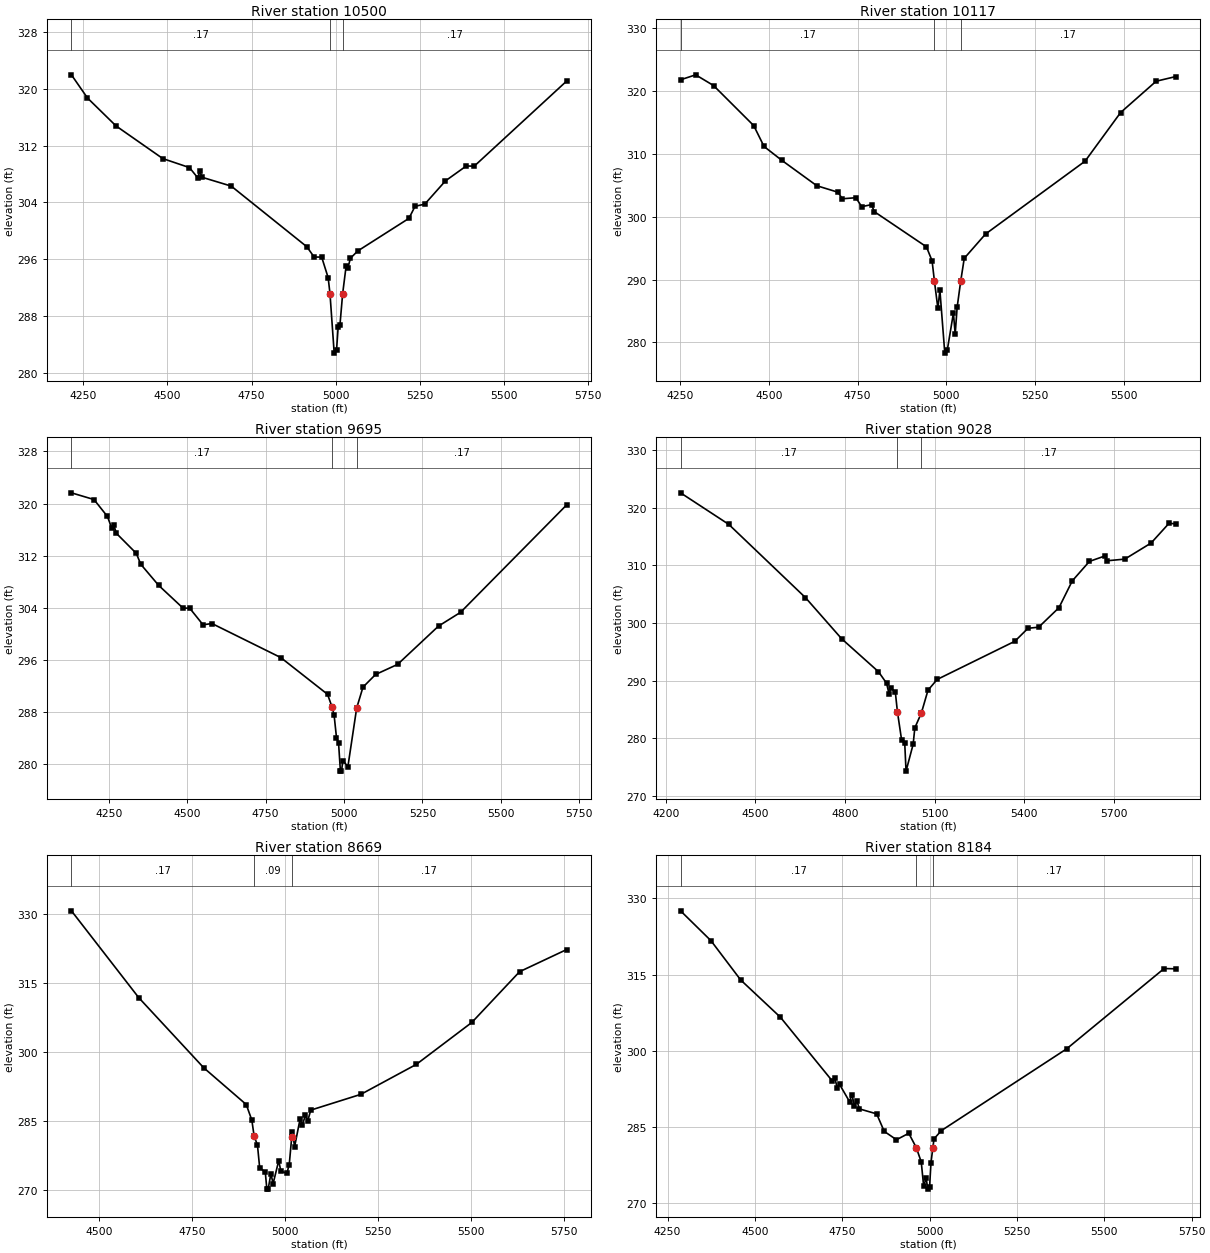
Type RM Length L Ch R = 1 ,10500   ,383,383,383
BEGIN DESCRIPTION:
Conroe Lake 098 21.5
END DESCRIPTION:
XS GIS Cut Line= 3
      3754341.33     10200761.76      3753608.23     10200479.68
      3752976.83     10200209.71
#Sta/Elev= 30
  4214.5  321.98  4262.3  318.71    4347  314.78  4486.2  310.17  4565.5   308.9
  4590.1  307.46  4595.5  308.35    4604  307.52  4689.7  306.29  4914.7  297.73
  4936.1  296.29  4958.6  296.28  4977.9  293.37  4983.3  291.12  4995.8  282.74
  5002.9  283.24  5007.5  286.36    5013  286.75 5020.88  291.09  5031.1  294.96
  5036.6  294.74  5043.9  296.11  5065.7  297.14    5218  301.74  5236.2  303.44
  5265.2  303.75  5326.7  307.03  5388.6  309.13  5412.2   309.1  5686.7  321.09
#Mann= 3 , 0 , 0
  4214.5     .17       0  4983.3     .09       0 5020.88     .17       0
Bank Sta=4983.3,5020.88
XS Rating Curve= 0 ,0
Exp/Cntr=0.3,0.1

Type RM Length L Ch R = 1 ,10117   ,422,422,422
BEGIN DESCRIPTION:
Conroe Lake 098 21.0
END DESCRIPTION:
XS GIS Cut Line= 3
      3754310.11     10200496.15      3753648.23     10200146.84
      3753002.86     10200126.36
#Sta/Elev= 30
  4251.6  321.83  4294.2  322.62  4344.6  320.91  4457.7  314.53  4486.7  311.21
  4536.8     309  4635.2  304.96  4695.1  303.92  4706.9  302.88  4745.3  303.05
  4761.7  301.62  4789.3  301.95  4796.9  300.84  4943.9  295.23  4959.8  293.01
  4966.5  289.73  4976.2  285.41  4981.8  288.35  4995.6   278.3  5002.7   278.8
  5019.9  284.68  5024.9  281.32  5030.4   285.6  5040.4  289.75  5050.4   293.4
  5110.4  297.27  5390.6  308.87  5490.6  316.61  5590.7   321.6  5645.7  322.34
#Mann= 3 , 0 , 0
  4251.6     .17       0  4966.5     .09       0  5040.4     .17       0
Bank Sta=4966.5,5040.4
XS Rating Curve= 0 ,0
Exp/Cntr=0.3,0.1

Type RM Length L Ch R = 1 ,9695    ,667,667,667
BEGIN DESCRIPTION:
Conroe Lake 098 20.0
END DESCRIPTION:
XS GIS Cut Line= 3
      3754317.97     10200472.75      3753748.23     10199816.84
      3753041.07     10199759.32
#Sta/Elev= 30
  4131.2  321.64  4203.1  320.61  4245.9  318.02  4260.1  316.17  4266.7  316.63
  4274.4  315.43    4338  312.35  4352.2  310.68  4409.2  307.44  4487.1  303.94
    4508  303.95  4550.7  301.39  4579.2  301.58  4798.5  296.36  4947.6  290.72
  4961.9  288.78  4968.5  287.54  4976.1  284.09  4982.7  283.27  4988.6  278.93
  4992.1  278.93  4996.5  280.56  5012.5  279.62  5040.5  288.62  5060.6  291.82
  5100.7  293.76  5170.9  295.31  5301.4  301.19  5371.6   303.3  5709.5  319.77
#Mann= 3 , 0 , 0
  4131.2     .17       0  4961.9     .09       0  5040.5     .17       0
Bank Sta=4961.9,5040.5
XS Rating Curve= 0 ,0
Exp/Cntr=0.3,0.1

Type RM Length L Ch R = 1 ,9028    ,359,359,359
BEGIN DESCRIPTION:
Conroe Lake 098 19.0
END DESCRIPTION:
XS GIS Cut Line= 3
      3754651.25     10199983.12      3754048.23     10199536.84
      3753622.83     10198736.13
#Sta/Elev= 30
  4249.8  322.57  4411.2   317.1  4667.9   304.4    4789  297.27  4912.2  291.56
  4939.3  289.56  4947.7  287.67  4953.9  288.71  4968.5  288.05  4975.6  284.59
  4989.4  279.78    5000  279.21  5004.4  274.33  5028.2  278.99  5033.8  281.83
  5055.8  284.42  5077.8  288.35  5108.5  290.22  5368.5  296.84  5412.5  299.09
  5448.2  299.28  5516.1  302.66  5560.7  307.31    5618  310.68  5670.6  311.64
  5676.2  310.79  5736.5  311.08  5824.5  313.87  5884.7   317.3  5906.7  317.18
#Mann= 3 , 0 , 0
  4249.8     .17       0  4975.6     .09       0  5055.8     .17       0
Bank Sta=4975.6,5055.8
XS Rating Curve= 0 ,0
Exp/Cntr=0.3,0.1

Type RM Length L Ch R = 1 ,8669    ,485,485,485
BEGIN DESCRIPTION:
Conroe Lake 098 18.0
END DESCRIPTION:
XS GIS Cut Line= 3
      3754718.96      10199592.5      3754238.23     10199276.84
      3753773.64     10198678.42
#Sta/Elev= 30
  4424.9  330.63  4606.1  311.77    4781  296.54  4895.4  288.56  4910.5  285.17
  4916.7  281.67  4925.6  279.77  4931.6  274.82  4946.7  273.87  4950.9  270.18
  4954.4  270.18  4961.8  273.52  4967.8  271.38  4982.8  276.35  4988.8  274.05
  5004.9  273.64  5011.2  275.52 5017.95  281.55  5019.4  282.67  5025.7  279.43
  5040.2  285.36  5046.5  284.13  5054.7  286.22    5061  285.04  5069.1  287.34
    5204  290.77  5353.3  297.28  5502.7  306.39  5631.2  317.41  5757.6  322.21
#Mann= 3 , 0 , 0
  4424.9     .17       0  4916.7     .09       0 5017.95     .17       0
#XS Ineff= 2 , 0
       0                  5054.7       0  286.22
Permanent Ineff=
       F       F
Bank Sta=4916.7,5017.95
XS Rating Curve= 0 ,0
Exp/Cntr=0.3,0.1

Type RM Length L Ch R = 1 ,8184    ,499,499,499
BEGIN DESCRIPTION:
Conroe Lake 098 17.0
END DESCRIPTION:
XS GIS Cut Line= 3
       3754929.9     10199462.28      3754448.23     10198936.84
      3753875.19     10198527.38
#Sta/Elev= 30
  4287.2  327.57  4374.3  321.69  4459.4  313.96  4572.9  306.64  4721.5  294.09
  4728.3  294.75  4735.7  292.75  4742.4   293.4  4770.8  290.03  4777.6  291.39
    4785  289.24  4791.8  290.19  4799.2  288.59  4848.5  287.61  4870.1  284.17
  4905.2  282.52  4940.4  283.79    4962  280.95  4976.1  278.15  4982.9  273.45
  4990.3  274.93  4994.8   272.8    5000   273.3    5004  278.04 5009.19  280.85
  5012.6  282.69  5033.5  284.31  5392.3  300.41  5671.2  316.21  5704.3  316.16
#Mann= 3 , 0 , 0
  4287.2     .17       0    4962     .09       0 5009.19     .17       0
Bank Sta=4962,5009.19
XS Rating Curve= 0 ,0
Exp/Cntr=0.3,0.1

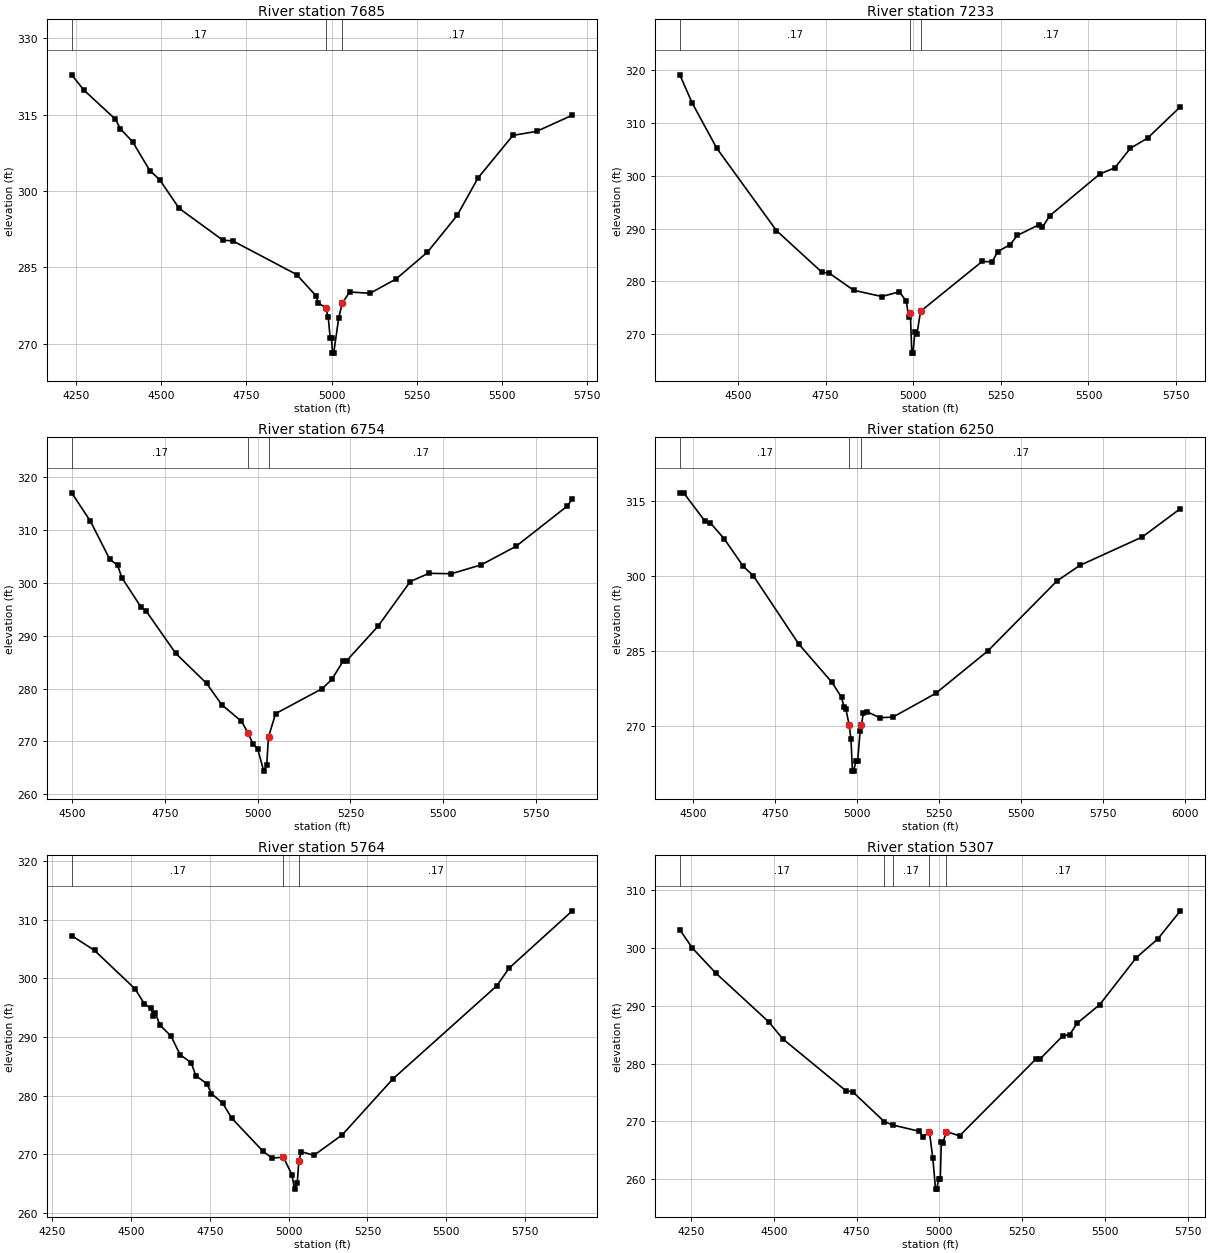
Type RM Length L Ch R = 1 ,7685    ,452,452,452
BEGIN DESCRIPTION:
Conroe Lake 098 16.0
END DESCRIPTION:
XS GIS Cut Line= 3
      3755125.22      10199162.8      3754688.23     10198536.84
       3753997.6     10198384.17
#Sta/Elev= 30
  4236.6  322.81  4272.4  319.81  4364.9  314.09  4379.7  312.19  4415.5  309.66
  4466.1  303.99  4494.8  302.22  4552.4  296.56  4680.7  290.31  4710.3  290.16
  4897.3  283.56  4954.6  279.36  4960.7  277.99  4982.6  277.05  4990.3  275.19
    4996  271.07    5000  271.07  5002.8  268.11  5006.3  268.11  5020.9  274.92
  5031.1  277.88  5053.3  280.13    5113  279.87  5189.4  282.67  5281.8  287.96
  5369.1  295.18  5430.5  302.55  5532.9  310.91  5602.7   311.7  5707.3  314.87
#Mann= 3 , 0 , 0
  4236.6     .17       0  4982.6     .09       0  5031.1     .17       0
Bank Sta=4982.6,5031.1
XS Rating Curve= 0 ,0
Exp/Cntr=0.3,0.1

Type RM Length L Ch R = 1 ,7233    ,479,479,479
BEGIN DESCRIPTION:
Conroe Lake 098 15.0
END DESCRIPTION:
XS GIS Cut Line= 3
      3755442.98     10198102.92      3754778.23     10198146.84
      3754032.98     10197986.06
#Sta/Elev= 30
  4333.8  319.05    4369  313.74  4439.2  305.19  4609.5  289.62  4739.8  281.71
  4759.9  281.59    4830  278.33  4910.2  277.15  4960.3  278.03  4980.3  276.25
  4986.8  273.26  4991.8  274.08  4995.9  266.45  4999.4  266.45  5004.6  270.42
  5010.6  270.03  5020.8  274.35  5196.6  283.77  5225.4  283.71  5240.8  285.63
  5276.6  286.96  5297.1   288.7  5358.4   290.7  5368.7  290.22  5389.1  292.39
  5532.4   300.3  5575.5  301.48  5619.7  305.17    5669   307.1  5762.4  313.02
#Mann= 3 , 0 , 0
  4333.8     .17       0  4991.8     .09       0  5020.8     .17       0
Bank Sta=4991.8,5020.8
XS Rating Curve= 0 ,0
Exp/Cntr=0.3,0.1

Type RM Length L Ch R = 1 ,6754    ,504,504,504
BEGIN DESCRIPTION:
Conroe Lake 098 14.0
END DESCRIPTION:
XS GIS Cut Line= 3
      3755466.37     10197943.63      3754985.62     10197799.45
      3754144.73     10197685.38
#Sta/Elev= 30
  4498.1  317.01  4548.8  311.62    4601  304.42  4621.8  303.34  4633.2  300.99
  4684.5  295.46  4699.3  294.62  4778.4  286.68    4862  280.98  4902.9  276.94
  4955.9  273.81  4974.3  271.58  4987.2  269.45    5000  268.58  5016.2  264.38
  5024.1  265.46  5029.1  270.87  5048.2  275.25  5174.1  279.99  5199.6  281.71
  5229.9  285.13    5240  285.27  5324.2  291.75  5411.5  300.23    5462  301.79
  5522.5  301.71  5603.2   303.4  5696.9   306.9  5835.4  314.52  5848.6  315.87
#Mann= 3 , 0 , 0
  4498.1     .17       0  4974.3     .09       0  5029.1     .17       0
Bank Sta=4974.3,5029.1
XS Rating Curve= 0 ,0
Exp/Cntr=0.3,0.1

Type RM Length L Ch R = 1 ,6250    ,486,486,486
BEGIN DESCRIPTION:
Conroe Lake 098 13.0
END DESCRIPTION:
XS GIS Cut Line= 3
      3755640.02     10197685.41      3755178.23     10197406.84
      3754191.63     10197407.61
#Sta/Elev= 30
  4460.7  316.56  4473.9  316.43    4538  310.86  4553.5  310.59  4596.2  307.38
  4654.5  301.88  4685.1  300.01  4823.3  286.42  4924.3  278.81  4953.7  275.81
  4961.2  273.87    4967  273.47  4976.7  270.35  4982.5  267.44    4987  261.09
  4990.5  261.09  4997.3  263.06  5002.7  263.06  5010.4  269.01 5014.18  270.34
  5020.4  272.67  5030.4  272.96  5070.4  271.74  5110.4  271.86  5240.4  276.57
  5400.4  285.09  5610.4     299  5680.4   302.1  5870.4  307.76  5986.6  313.41
#Mann= 3 , 0 , 0
  4460.7     .17       0  4976.7     .09       0 5014.18     .17       0
Bank Sta=4976.7,5014.18
XS Rating Curve= 0 ,0
Exp/Cntr=0.3,0.1

Type RM Length L Ch R = 1 ,5764    ,457,457,457
BEGIN DESCRIPTION:
Conroe Lake 098 12.0
END DESCRIPTION:
XS GIS Cut Line= 3
      3755733.32      10197388.1      3755188.23     10196966.84
      3754287.94      10196943.2
#Sta/Elev= 30
  4311.1  307.27  4383.7  304.75  4512.3   298.2  4541.3   295.7  4562.1  294.86
  4570.3  293.61  4576.6  294.11  4591.1  292.04  4626.4  290.16  4655.4  286.98
  4690.7  285.61  4705.2  283.41  4740.5  282.03    4755  280.35  4790.3  278.75
  4819.3  276.17  4918.9  270.51  4947.9  269.36  4983.2  269.53  5010.4  266.53
  5018.6  264.08  5027.4  265.18  5032.4  268.93  5040.4  270.46  5080.4  269.84
  5170.4  273.34  5330.5  282.83  5660.6  298.71  5700.6  301.77  5900.6   311.5
#Mann= 3 , 0 , 0
  4311.1     .17       0  4983.2     .09       0  5032.4     .17       0
Bank Sta=4983.2,5032.4
XS Rating Curve= 0 ,0
Exp/Cntr=0.3,0.1

Type RM Length L Ch R = 1 ,5307    ,506,506,506
BEGIN DESCRIPTION:
Conroe Lake 098 11.0
END DESCRIPTION:
XS GIS Cut Line= 3
      3755965.51     10196628.53      3755188.23     10196526.84
      3754465.93     10196437.56
#Sta/Elev= 30
  4216.1  303.16  4254.1  299.98  4324.7  295.66    4486  287.14  4526.4  284.29
    4718  275.27  4738.2  275.11  4833.2  269.96  4859.8  269.35  4939.9  268.26
    4950  267.32  4970.1  268.08  4980.2  263.62  4988.4  258.26  4992.1  258.26
  4997.7  260.02  5002.7  260.02  5005.9  266.43  5010.9  266.22  5020.5  268.23
  5060.8  267.48  5292.6  280.84  5302.7  280.72  5373.2  284.81  5393.3  284.98
  5416.2  286.98    5484  290.18  5594.9  298.34  5659.4  301.55  5727.8  306.43
#Mann= 5 ,-1 , 0
  4216.1     .17       0  4833.2     .15       0  4859.8     .17       0
  4970.1     .09       0  5020.5     .17       0
Bank Sta=4970.1,5020.5
XS Rating Curve= 0 ,0
Exp/Cntr=0.3,0.1

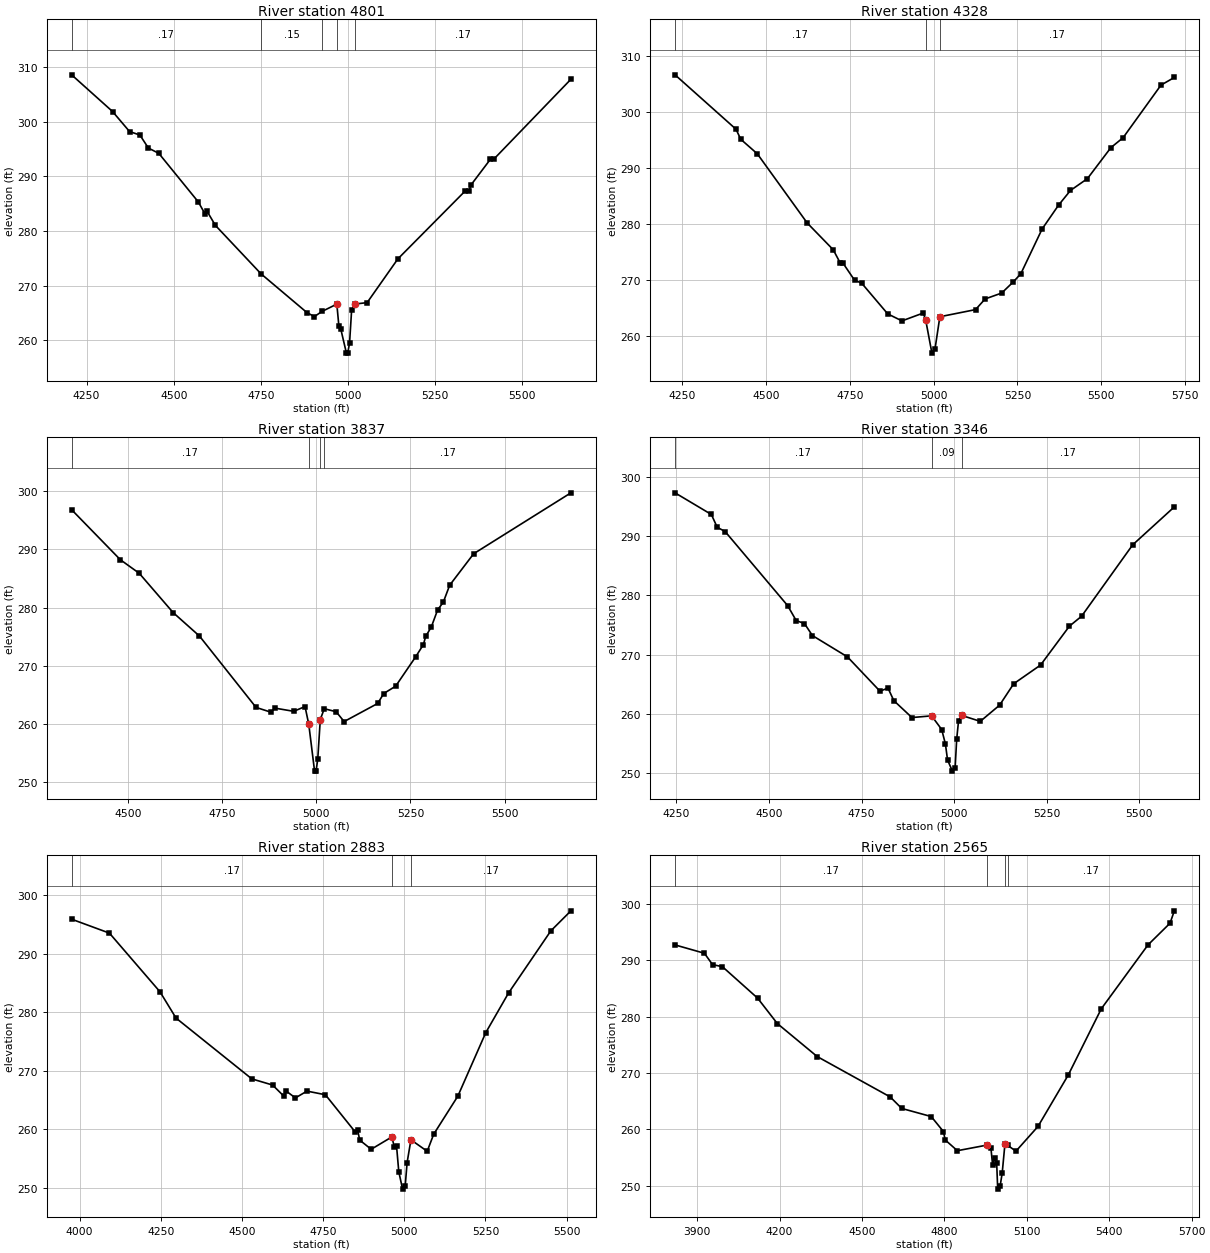
Type RM Length L Ch R = 1 ,4801    ,473,473,473
BEGIN DESCRIPTION:
Conroe Lake 098 10.0
END DESCRIPTION:
XS GIS Cut Line= 3
      3755995.88     10196387.64      3755258.23     10196096.84
      3754631.25     10195968.42
#Sta/Elev= 30
  4207.1  308.62  4324.5   301.9  4373.3  298.23    4403  297.59  4427.4   295.2
  4457.2  294.24  4570.8  285.32  4589.8  283.14  4595.2  283.68  4619.6  281.04
  4750.8  272.15  4882.2  265.07  4903.7  264.32  4925.4  265.26  4968.2  266.61
  4974.2  262.51  4979.6  262.03  4995.7  257.63  4999.4  257.63  5004.7  259.46
  5010.6  265.46  5020.8  266.63  5055.1  266.88  5143.3  274.89  5337.2  287.38
  5347.4  287.27  5352.6  288.39  5408.7  293.13  5418.9  293.18    5640  307.81
#Mann= 5 ,-1 , 0
  4207.1     .17       0  4750.8     .15       0  4925.4     .17       0
  4968.2     .09       0  5020.8     .17       0
Bank Sta=4968.2,5020.8
XS Rating Curve= 0 ,0
Exp/Cntr=0.3,0.1

Type RM Length L Ch R = 1 ,4328    ,491,491,491
BEGIN DESCRIPTION:
Conroe Lake 098 9.0
END DESCRIPTION:
XS GIS Cut Line= 3
      3756017.57     10196298.65      3755488.23     10195736.84
      3754941.99      10195270.7
#Sta/Elev= 30
  4228.1  306.56  4410.1  296.87  4424.3  295.08  4473.6   292.5  4622.5  280.18
  4700.2  275.41  4721.2  273.04  4728.5   273.1  4763.7     270  4785.2  269.45
  4862.8  263.99  4905.3  262.74  4968.8  264.14  4976.1  262.91  4994.7     257
  5004.1   257.8  5018.4  263.48  5124.9  264.75  5153.5  266.65  5202.9   267.7
    5238  269.71    5260  271.13  5323.6  279.11    5373  283.38  5408.2  285.97
  5458.7  288.07  5528.9   293.6  5565.2  295.36  5678.3  304.73  5718.1  306.09
#Mann= 3 , 0 , 0
  4228.1     .17       0  4976.1     .09       0  5018.4     .17       0
Bank Sta=4976.1,5018.4
XS Rating Curve= 0 ,0
Exp/Cntr=0.3,0.1

Type RM Length L Ch R = 1 ,3837    ,491,491,491
BEGIN DESCRIPTION:
Conroe Lake 098 8.0
END DESCRIPTION:
XS GIS Cut Line= 3
      3756267.14     10195395.89      3755618.23     10195406.84
      3754975.88     10195196.23
#Sta/Elev= 30
    4351  296.82  4480.3  288.23  4530.3  285.91  4620.3  279.16  4690.3  275.12
  4840.4  262.87  4880.4  262.04  4890.4  262.75  4940.4   262.2  4970.4  263.02
  4980.4  259.94  4995.7  251.93  4999.6  251.93  5004.1  253.95  5010.9  260.79
  5021.4  262.65    5053  262.13  5074.1  260.44  5163.2  263.55  5179.3  265.26
  5210.9  266.52    5264  271.56  5284.5  273.66  5290.6  275.06  5305.6   276.7
  5322.4  279.64  5337.2  280.92  5354.2  283.85  5417.9  289.26    5676  299.72
#Mann= 4 ,-1 , 0
    4351     .17       0  4980.4     .09       0  5010.9     .12       0
  5021.4     .17       0
Bank Sta=4980.4,5010.9
XS Rating Curve= 0 ,0
Exp/Cntr=0.3,0.1

Type RM Length L Ch R = 1 ,3346    ,463,463,463
BEGIN DESCRIPTION:
Conroe Lake 098 7.0
END DESCRIPTION:
XS GIS Cut Line= 3
      3756271.49     10195332.96      3755618.23     10194956.84
      3755025.85     10194903.27
#Sta/Elev= 30
  4246.2  297.36  4344.3   293.7  4360.1  291.54  4381.7   290.8  4550.4  278.28
  4573.5  275.75  4595.8  275.25  4617.3  273.22    4712  269.61  4799.8  263.81
  4821.4  264.34  4837.2  262.21  4886.1  259.35  4939.2  259.64  4966.5  257.33
  4976.5  254.88  4982.3  252.18  4995.4  250.29  5002.7  250.79    5007  255.72
    5012   258.8  5020.5  259.71  5070.7  258.71  5122.8  261.44    5161  265.07
  5233.5  268.23  5311.6  274.82  5344.2  276.48  5482.3  288.56  5594.8  294.98
#Mann= 3 , 0 , 0
  4246.2     .17       0  4939.2     .09       0  5020.5     .17       0
Bank Sta=4939.2,5020.5
XS Rating Curve= 0 ,0
Exp/Cntr=0.3,0.1

Type RM Length L Ch R = 1 ,2883    ,318,318,318
BEGIN DESCRIPTION:
Conroe Lake 098 6.0
END DESCRIPTION:
XS GIS Cut Line= 3
      3756321.41      10195272.2      3755618.23     10194526.84
      3755106.14     10194493.12
#Sta/Elev= 30
  3975.3  295.92  4091.7  293.54  4247.5  283.51  4296.9  279.02  4530.3  268.63
  4594.2  267.58  4629.4  265.66  4636.7  266.52  4664.6  265.38  4700.2  266.54
  4756.9  265.92  4848.7  259.57    4856  259.89  4862.8  258.16    4898   256.6
    4962  258.72  4968.8  257.04  4976.1  257.16    4983  252.76  4994.7  249.79
  5002.7  250.29  5008.6  254.32  5020.4  258.22  5070.5  256.26  5090.6  259.18
  5164.8  265.67  5250.9  276.53  5321.1  283.31  5451.4  293.93  5513.2  297.35
#Mann= 3 , 0 , 0
  3975.3     .17       0    4962     .09       0  5020.4     .17       0
Bank Sta=4962,5020.4
XS Rating Curve= 0 ,0
Exp/Cntr=0.3,0.1

Type RM Length L Ch R = 1 ,2565    ,489,489,489
BEGIN DESCRIPTION:
Conroe Lake 098 5.0
END DESCRIPTION:
XS GIS Cut Line= 3
      3756362.62     10195215.75      3755688.23     10194246.84
      3755052.33     10194282.59
#Sta/Elev= 30
  3819.5  292.71  3926.4  291.23  3956.1  289.21  3991.9  288.85  4120.2  283.26
  4191.8  278.76  4336.9   272.9  4602.8  265.73  4644.7  263.69  4752.1  262.25
  4796.6  259.58  4802.7  258.11  4847.2  256.19  4954.6  257.18  4969.4  256.62
  4975.5  253.66  4982.7  254.83  4990.3  254.04    4994  249.37  5002.7  249.87
  5010.4  252.23  5020.4   257.4  5030.4  257.13  5060.5  256.11  5140.6  260.49
  5250.8  269.62    5371  281.37  5541.2  292.72  5621.4  296.57  5636.9  298.76
#Mann= 4 ,-1 , 0
  3819.5     .17       0  4954.6     .09       0  5020.4     .12       0
  5030.4     .17       0
Bank Sta=4954.6,5020.4
XS Rating Curve= 0 ,0
Exp/Cntr=0.3,0.1

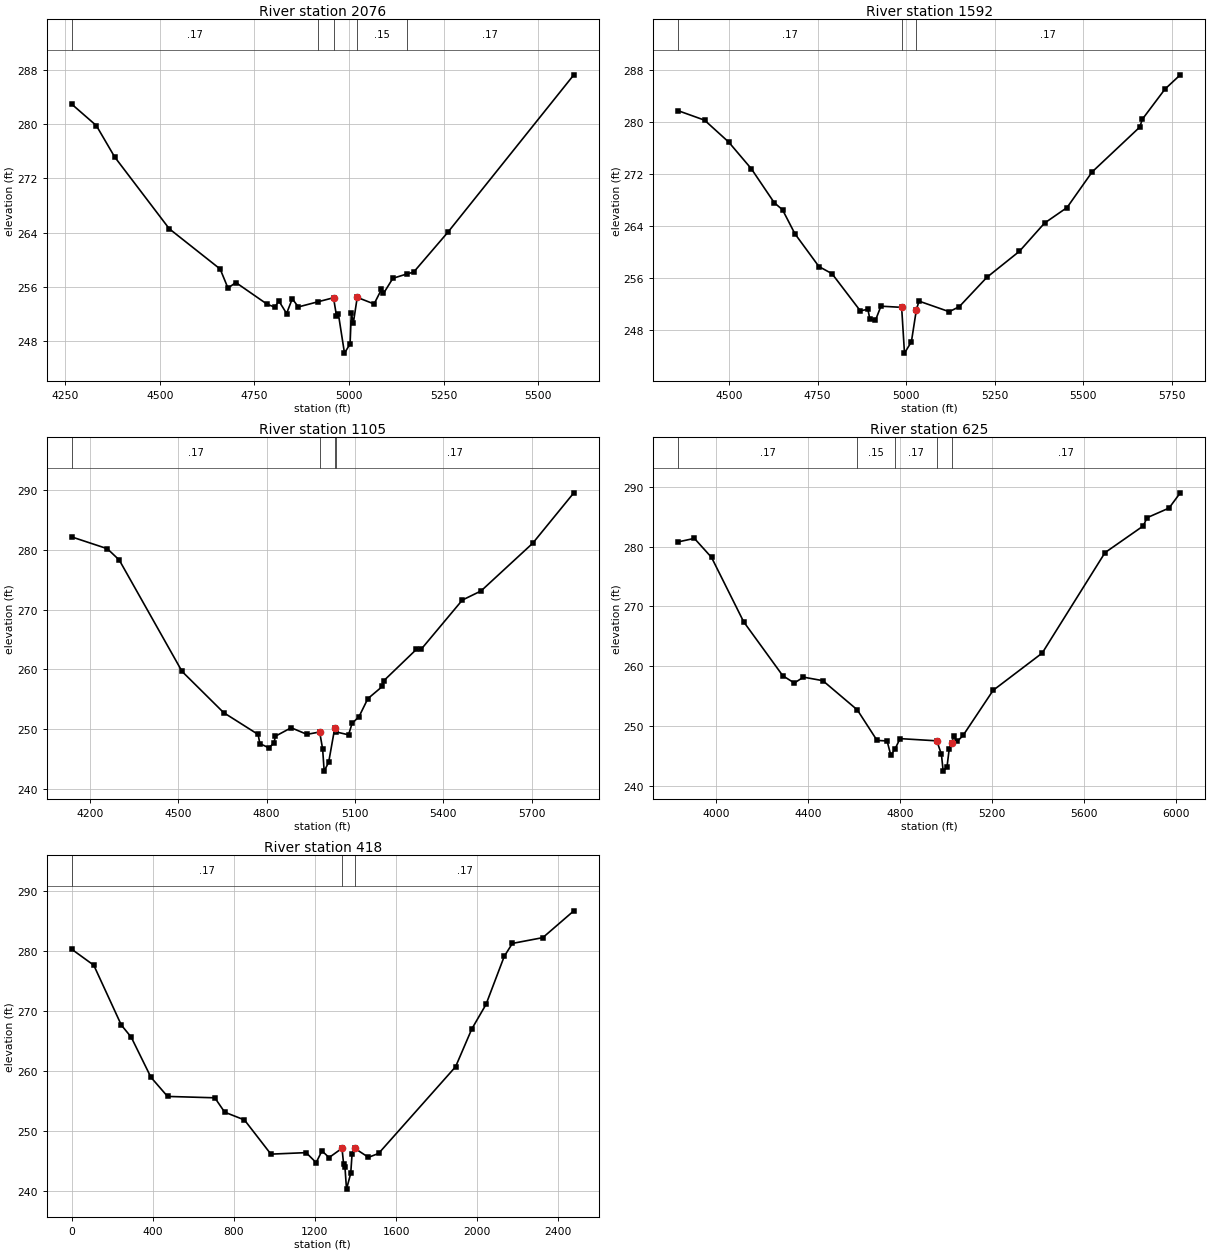
Type RM Length L Ch R = 1 ,2076    ,484,484,484
BEGIN DESCRIPTION:
Conroe Lake 098 4.0
END DESCRIPTION:
XS GIS Cut Line= 3
      3756417.89     10193640.21      3755708.23     10193823.71
      3755152.72     10194034.89
#Sta/Elev= 30
    4267  282.98  4332.3   279.8  4380.7  275.17  4525.1  264.56  4659.5  258.62
  4680.2   255.8  4700.9  256.63  4783.5  253.43  4804.1  252.98  4814.7   253.9
  4835.1  252.05  4850.1  254.23  4866.1  253.02  4919.2   253.8  4959.1  254.38
  4966.9  251.74    4972  251.98  4988.1   246.2  5002.9  247.56  5006.2  252.11
  5011.6  250.69  5021.8  254.43  5066.4  253.46  5085.9  255.62  5091.2  255.01
    5116  257.25    5153  257.89  5170.9  258.16  5261.2  264.04  5594.3   287.3
#Mann= 5 ,-1 , 0
    4267     .17       0  4919.2     .15       0  4959.1     .09       0
  5021.8     .15       0    5153     .17       0
#XS Ineff= 2 , 0
       0  4700.9  256.63               0
Permanent Ineff=
       F       F
Bank Sta=4959.1,5021.8
XS Rating Curve= 0 ,0
Exp/Cntr=0.3,0.1

Type RM Length L Ch R = 1 ,1592    ,487,487,487
BEGIN DESCRIPTION:
Conroe Lake 098 3.0
END DESCRIPTION:
XS GIS Cut Line= 3
      3756180.39     10193049.95      3755628.76     10193380.72
      3755058.36     10193902.86
#Sta/Elev= 30
  4356.8  281.78  4431.3  280.32  4499.3  276.95  4563.5  272.81  4627.9  267.59
  4651.3   266.5  4686.2   262.8    4754  257.74  4790.9  256.64  4870.6  250.92
    4892  251.14  4897.8  249.61  4913.4  249.45  4928.9  251.63  4987.3  251.45
  4995.3  244.39  5014.8  246.14  5028.9   251.1  5036.3  252.41  5121.4  250.78
  5149.8  251.55  5227.5  256.07  5319.4  260.09  5390.3  264.44  5453.8  266.84
  5524.7  272.34  5659.2  279.26  5665.9  280.44  5730.1  285.11  5773.3  287.31
#Mann= 3 , 0 , 0
  4356.8     .17       0  4987.3     .09       0  5028.9     .17       0
Bank Sta=4987.3,5028.9
XS Rating Curve= 0 ,0
Exp/Cntr=0.3,0.1

Type RM Length L Ch R = 1 ,1105    ,480,480,480
BEGIN DESCRIPTION:
Conroe Lake 098 2.0
END DESCRIPTION:
XS GIS Cut Line= 4
      3756136.91     10192943.64      3755288.23     10193096.84
      3755230.87     10193112.07      3754952.52     10193845.16
#Sta/Elev= 30
  4137.6  282.16  4258.6  280.19  4299.2   278.3  4512.6  259.67  4653.9  252.78
  4771.1  249.13  4776.8  247.61  4807.3   246.9  4824.7  247.68  4829.7  248.84
  4883.3  250.25  4936.8  249.15  4980.1  249.54  4990.2  246.69  4995.4     243
  5010.7  244.49  5031.1  250.14  5036.3  249.55  5078.1  249.07  5090.4     251
  5113.6  252.09  5143.8  255.12  5193.3  257.17  5198.7  258.15  5308.5  263.35
  5325.7  263.42  5464.7   271.6  5528.1  273.12  5703.6  281.09  5843.5  289.53
#Mann= 4 ,-1 , 0
  4137.6     .17       0  4980.1     .09       0  5031.1     .12       0
  5036.3     .17       0
Bank Sta=4980.1,5031.1
XS Rating Curve= 0 ,0
Exp/Cntr=0.3,0.1

Type RM Length L Ch R = 1 ,625     ,207,207,207
BEGIN DESCRIPTION:
Conroe Lake 098 1.0
END DESCRIPTION:
XS GIS Cut Line= 3
      3756113.08     10192828.62      3754948.23     10192786.84
      3754837.03     10193800.87
#Sta/Elev= 30
  3834.4  280.78  3905.1  281.37  3979.7   278.2  4119.8  267.43  4289.9  258.43
    4340  257.21    4380  258.19  4464.3   257.6  4614.3  252.72  4700.2  247.62
  4743.9  247.53  4760.2  245.13  4779.3  246.25  4800.3  247.92  4960.4  247.55
  4980.4  245.29    4988  242.49  5004.6  243.16  5014.3   246.2  5024.4  247.14
  5034.4  248.32  5049.4  247.45  5074.7  248.45  5205.5  255.99    5419  262.21
  5692.4  278.99  5859.3  283.46  5874.7  284.81  5970.9  286.43  6020.1  288.98
#Mann= 5 ,-1 , 0
  3834.4     .17       0  4614.3     .15       0  4779.3     .17       0
  4960.4     .09       0  5024.4     .17       0
Bank Sta=4960.4,5024.4
XS Rating Curve= 0 ,0
Exp/Cntr=0.3,0.1

Type RM Length L Ch R = 1 ,418     ,0,0,0
XS GIS Cut Line= 4
      3756079.63     10192759.71      3754958.11     10192510.69
      3754779.22     10192726.23      3754792.09     10193774.25
#Sta/Elev= 30
       0  280.25   109.2  277.58     245  267.63   293.7  265.62   391.1  258.94
     473  255.76   706.2  255.53   754.8  253.14   852.2  251.85   982.8  246.16
  1156.5  246.41  1205.9  244.75  1234.6   246.7  1269.7  245.59  1333.5  247.13
  1341.4  244.51  1347.9  244.07  1355.7  240.34  1376.5  242.96  1383.3  246.26
  1397.3  247.11  1463.8  245.63  1513.8  246.27  1893.8   260.7  1973.8  266.99
  2043.8  271.06  2133.8  279.06  2173.8  281.21  2323.9  282.17    2477  286.63
#Mann= 3 , 0 , 0
       0     .17       0  1333.5     .09       0  1397.3     .17       0
Bank Sta=1333.5,1397.3
XS Rating Curve= 0 ,0
Exp/Cntr=0.3,0.1

Chan Stop Cuts=-1
Use User Specified Reach Order=0
Composite Channel Slope=5