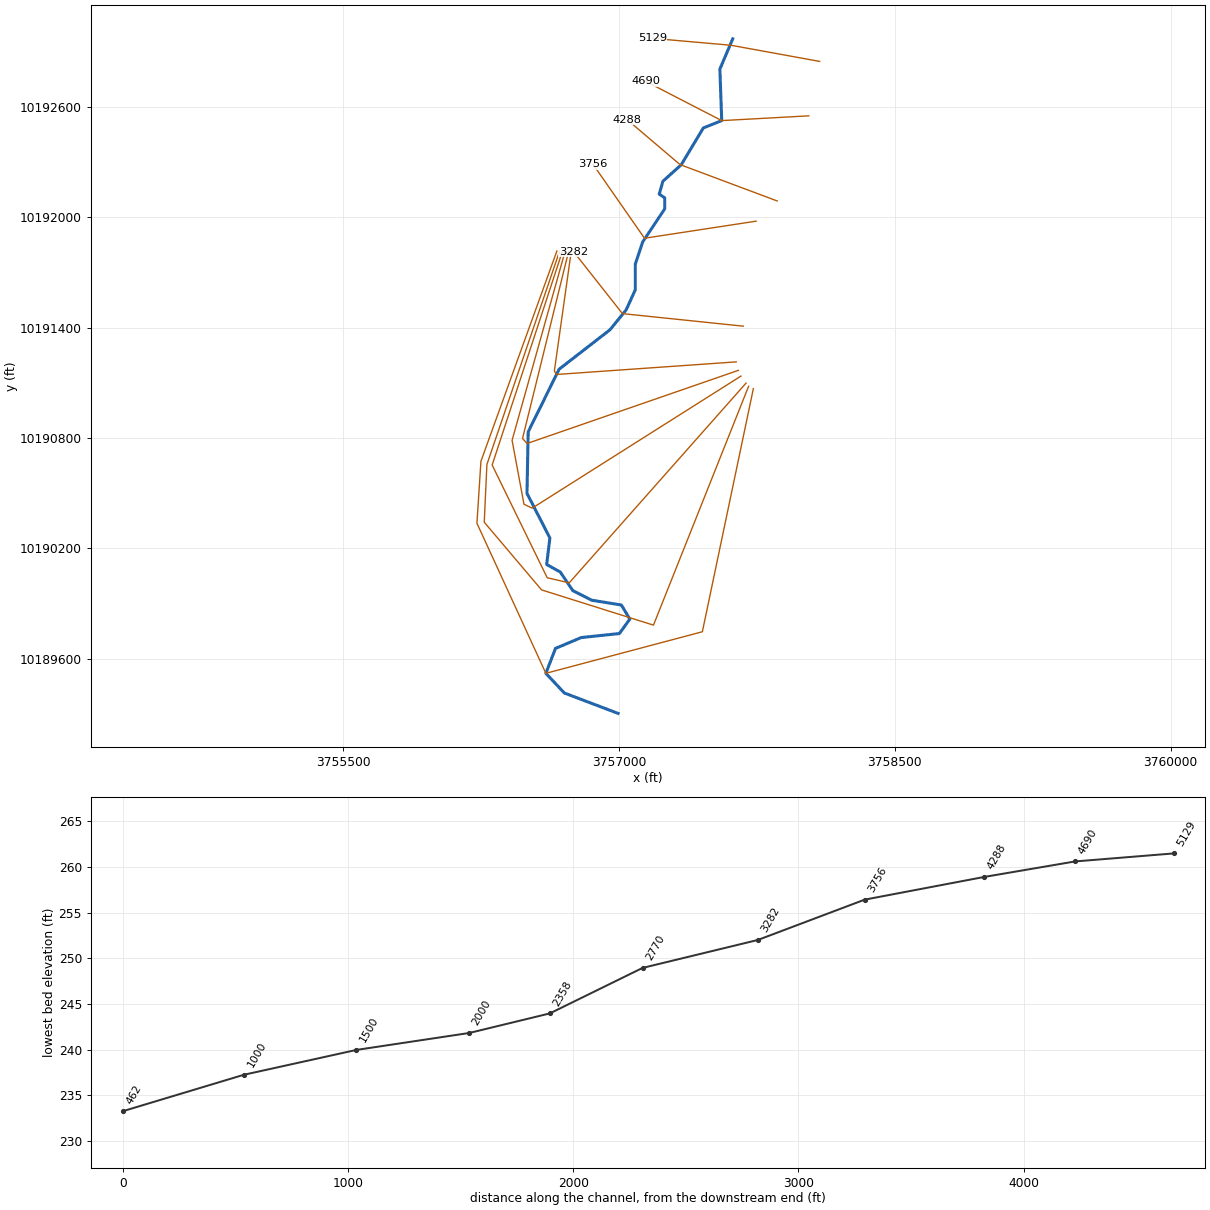
--- Conroe Lake 099.prj (project) ---

Proj Title=Conroe Lake 099 Base Level Engineering
Current Plan=p01
Default Exp/Contr=0.3,0.1
English Units
Geom File=g01
Flow File=f01
Flow File=f02
Plan File=p01
Y Axis Title=Elevation
X Axis Title(PF)=Main Channel Distance
X Axis Title(XS)=Station
BEGIN DESCRIPTION:
Conroe Lake 099
END DESCRIPTION:
DSS Export Rating Curves= 0
DSS Export Rating Curve Sorted= 0
DSS Export Volume Flow Curves= 0
DXF OffsetX= 0
DXF OffsetY= 0
DXF ScaleX= 1
DXF ScaleY= 10

--- Conroe Lake 099.p01 (plan) ---

Plan Title=Multiple Run
Short Identifier=Multiple
Geom File=g01
Flow File=f01
Subcritical Flow
K Sum by GR= 0
Std Step Tol= 0.01
Critical Tol= 0.01
Num of Std Step Trials= 20
Max Error Tol= 0.3
Flow Tol Ratio= 0.001
Split Flow NTrial= 30
Split Flow Tol= 0.02
Split Flow Ratio= 0.02
Log Output Level= 0
Friction Slope Method= 1
Unsteady Friction Slope Method= 2
Unsteady Bridges Friction Slope Method= 1
Parabolic Critical Depth
Global Vel Dist=  1 , 1 , 1
Global Log Level= 0
CheckData=True
Encroach Param= -1, 0, 0, 0
BEGIN DESCRIPTION:
Multiple Run
END DESCRIPTION:

--- Conroe Lake 099.f01 (steady flow) ---

Flow Title=Multiple
Program Version=4.10
Number of Profiles= 7
Profile Names=10-year,25-year,50-year,1pct_min,100-year,1pct_plu,500-year
River Rch & RM=Conroe Lake 099,Reach-1         ,5129
     420     555     736     323     974    2941    1756
River Rch & RM=Conroe Lake 099,Reach-1         ,4690
     558     749    1005     444    1340    4047    2465
Boundary for River Rch & Prof#=Conroe Lake 099,Reach-1         , 1
Up Type= 0
Dn Type= 3
Dn Slope=0.005
Boundary for River Rch & Prof#=Conroe Lake 099,Reach-1         , 2
Up Type= 0
Dn Type= 3
Dn Slope=0.005
Boundary for River Rch & Prof#=Conroe Lake 099,Reach-1         , 3
Up Type= 0
Dn Type= 3
Dn Slope=0.005
Boundary for River Rch & Prof#=Conroe Lake 099,Reach-1         , 4
Up Type= 0
Dn Type= 3
Dn Slope=0.005
Boundary for River Rch & Prof#=Conroe Lake 099,Reach-1         , 5
Up Type= 0
Dn Type= 3
Dn Slope=0.005
Boundary for River Rch & Prof#=Conroe Lake 099,Reach-1         , 6
Up Type= 0
Dn Type= 3
Dn Slope=0.005
Boundary for River Rch & Prof#=Conroe Lake 099,Reach-1         , 7
Up Type= 0
Dn Type= 3
Dn Slope=0.005
DSS Import GetInterval= 0
DSS Import GetPeak= 0
DSS Import FillOption= 0

--- Conroe Lake 099.f02 (steady flow) ---

Flow Title=Orig_BLE_Flow
Program Version=4.10
Number of Profiles= 7
Profile Names=10-year,25-year,50-year,1pct_min,100-year,1pct_plu,500-year
River Rch & RM=Conroe Lake 099,Reach-1         ,5129
     420     544     640     248     749    2262    1021
River Rch & RM=Conroe Lake 099,Reach-1         ,4690
     558     734     874     341    1031    3114    1433
Boundary for River Rch & Prof#=Conroe Lake 099,Reach-1         , 1
Up Type= 0
Dn Type= 3
Dn Slope=0.005
Boundary for River Rch & Prof#=Conroe Lake 099,Reach-1         , 2
Up Type= 0
Dn Type= 3
Dn Slope=0.005
Boundary for River Rch & Prof#=Conroe Lake 099,Reach-1         , 3
Up Type= 0
Dn Type= 3
Dn Slope=0.005
Boundary for River Rch & Prof#=Conroe Lake 099,Reach-1         , 4
Up Type= 0
Dn Type= 3
Dn Slope=0.005
Boundary for River Rch & Prof#=Conroe Lake 099,Reach-1         , 5
Up Type= 0
Dn Type= 3
Dn Slope=0.005
Boundary for River Rch & Prof#=Conroe Lake 099,Reach-1         , 6
Up Type= 0
Dn Type= 3
Dn Slope=0.005
Boundary for River Rch & Prof#=Conroe Lake 099,Reach-1         , 7
Up Type= 0
Dn Type= 3
Dn Slope=0.005
DSS Import GetInterval= 0
DSS Import GetPeak= 0
DSS Import FillOption= 0

--- Conroe Lake 099.g01 (geometry) ---

Geom Title=Existing Conditions
Program Version=4.10

River Reach=Conroe Lake 099 ,Reach-1
Reach XY= 30
      3757618.23     10192971.84      3757548.23     10192806.84
      3757558.23     10192526.84      3757458.23     10192486.84
      3757338.23     10192286.84      3757238.23     10192196.84
      3757218.23     10192126.84      3757248.23     10192106.84
      3757248.23     10192046.84      3757128.23     10191866.84
      3757088.23     10191746.84      3757088.23     10191606.84
      3757038.23     10191496.84      3756950.14     10191388.75
      3756673.67     10191174.42      3756505.39     10190833.48
      3756498.83      10190499.1      3756623.41     10190256.52
      3756605.92     10190112.27      3756680.23     10190070.75
      3756747.98     10189970.22       3756850.7     10189917.77
      3757012.42     10189891.54      3757058.32     10189815.05
       3757001.5     10189736.37      3756793.87     10189714.51
        3756654.     10189655.51      3756601.55     10189520.01
      3756702.08     10189412.92       3756994.3     10189302.09

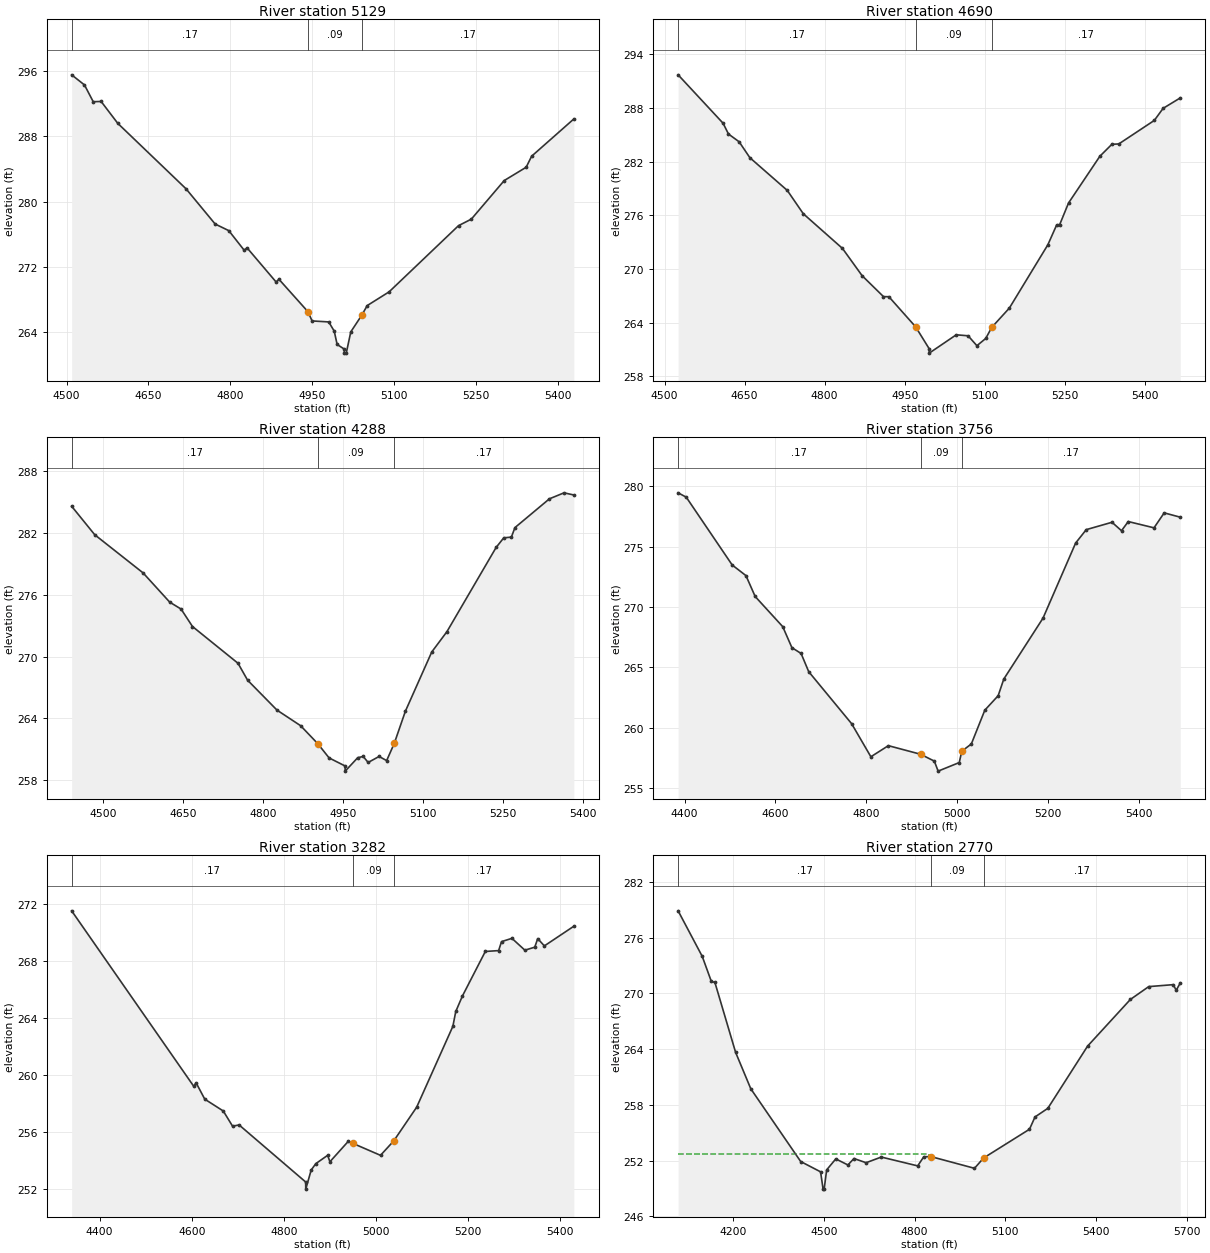
Type RM Length L Ch R = 1 ,5129    ,439,439,439
BEGIN DESCRIPTION:
Conroe Lake 099 10.0
END DESCRIPTION:
XS GIS Cut Line= 3
      3758090.98     10192848.87      3757608.23     10192936.84
      3757180.88     10192974.44
#Sta/Elev= 30
  4509.3  295.53  4532.8  294.29  4548.8  292.24  4563.3  292.27  4593.8  289.59
  4718.8  281.58  4772.1  277.27  4797.1  276.46  4825.4  274.05  4830.5  274.36
  4883.8  270.17  4888.9  270.51  4942.2  266.53  4949.6  265.41  4980.1  265.29
  4990.2  264.16  4995.5  262.53  5008.4  261.97  5008.7  261.47  5012.2  261.47
  5020.5  264.07  5040.5   266.1  5050.6  267.29  5090.7  268.97  5217.8  277.07
  5241.3  277.87  5301.5  282.59  5341.7  284.22  5351.7  285.57    5429  290.13
#Mann= 3 , 0 , 0
  4509.3     .17       0  4942.2     .09       0  5040.5     .17       0
Bank Sta=4942.2,5040.5
XS Rating Curve= 0 ,0
Exp/Cntr=0.3,0.1

Type RM Length L Ch R = 1 ,4690    ,402,402,402
BEGIN DESCRIPTION:
Conroe Lake 099 6.0
END DESCRIPTION:
XS GIS Cut Line= 3
      3758032.02     10192552.84      3757558.23     10192526.84
      3757143.95     10192740.65
#Sta/Elev= 30
  4525.5  291.72  4609.8   286.3  4619.8   285.1  4639.8  284.23  4659.9  282.45
    4730  278.79    4760  276.18  4833.4   272.3  4870.2  269.25  4910.2  266.91
  4920.3   266.9  4970.3  263.54  4995.7  261.09  4995.9  260.59  5046.5  262.64
  5068.7  262.53  5085.2  261.42  5101.7  262.23    5113  263.47    5146  265.63
  5218.1  272.71  5234.6  274.93  5240.3  274.97  5256.8  277.38  5315.5  282.61
    5338  283.95    5351  283.99  5417.5  286.62    5434  287.97  5466.2  289.14
#Mann= 3 , 0 , 0
  4525.5     .17       0  4970.3     .09       0    5113     .17       0
Bank Sta=4970.3,5113
XS Rating Curve= 0 ,0
Exp/Cntr=0.3,0.1

Type RM Length L Ch R = 1 ,4288    ,532,532,532
BEGIN DESCRIPTION:
Conroe Lake 099 9.0
END DESCRIPTION:
XS GIS Cut Line= 3
      3757860.17     10192089.69      3757331.21     10192287.67
      3757043.69     10192532.14
#Sta/Elev= 30
  4441.3  284.56  4484.6   281.8  4575.4   278.1  4625.3  275.27  4646.6   274.6
    4668  272.91  4753.4  269.35  4771.4  267.71  4826.6  264.81  4870.9   263.3
  4902.9  261.57  4924.3  260.18  4954.3   259.4  4954.5   258.9    4978   260.2
  4988.3  260.32  4997.6  259.74  5018.1  260.32  5032.3  259.92  5046.6  261.59
  5067.5  264.71  5116.9  270.44  5145.4  272.41  5237.7  280.57    5252   281.5
  5266.3  281.57    5273  282.49  5337.7  285.28  5365.1  285.86  5383.5  285.65
#Mann= 3 , 0 , 0
  4441.3     .17       0  4902.9     .09       0  5046.6     .17       0
Bank Sta=4902.9,5046.6
XS Rating Curve= 0 ,0
Exp/Cntr=0.3,0.1

Type RM Length L Ch R = 1 ,3756    ,474,474,474
BEGIN DESCRIPTION:
Conroe Lake 099 4.0
END DESCRIPTION:
XS GIS Cut Line= 3
      3757745.55     10191979.87      3757138.23     10191886.84
      3756857.45     10192290.25
#Sta/Elev= 30
  4385.6  279.47  4403.5  279.11  4504.7  273.49    4535  272.61  4555.3  270.88
    4616  268.38  4636.2  266.64  4656.4  266.16  4673.2  264.65  4767.7  260.34
  4810.1   257.6  4848.6  258.52  4919.4  257.81  4949.8  257.24  4958.2  256.41
  5004.7  257.12  5010.3  258.06  5031.3  258.66    5061  261.46  5090.4  262.66
  5102.8  264.04  5189.2  269.09    5261  275.31  5284.4  276.42  5341.1  277.03
    5362  276.33  5376.9  277.09  5433.6  276.57    5456  277.81  5491.5  277.45
#Mann= 3 , 0 , 0
  4385.6     .17       0  4919.4     .09       0  5010.3     .17       0
Bank Sta=4919.4,5010.3
XS Rating Curve= 0 ,0
Exp/Cntr=0.3,0.1

Type RM Length L Ch R = 1 ,3282    ,512,512,512
BEGIN DESCRIPTION:
Conroe Lake 099 3.0
END DESCRIPTION:
XS GIS Cut Line= 3
      3757675.49     10191408.51      3757018.23     10191476.84
      3756751.85     10191814.65
#Sta/Elev= 30
  4339.2  271.52  4604.5  259.21  4609.5  259.46  4628.4  258.31  4668.6  257.48
  4688.7  256.42  4703.1   256.5  4847.6   252.5  4847.8     252  4859.6  253.34
  4869.7  253.79  4895.3  254.37  4900.3  253.92  4940.1  255.35  4950.1  255.21
  5010.2  254.37  5039.1  255.39  5088.8  257.75  5167.4  263.42  5173.7  264.46
  5188.2  265.55  5237.9  268.67  5266.8  268.73  5273.1  269.36  5295.7  269.59
  5323.8  268.76  5345.3  268.97  5351.7  269.57  5366.2  269.06  5430.2  270.44
#Mann= 3 , 0 , 0
  4339.2     .17       0  4950.1     .09       0  5039.1     .17       0
Bank Sta=4950.1,5039.1
XS Rating Curve= 0 ,0
Exp/Cntr=0.3,0.1

Type RM Length L Ch R = 1 ,2770    ,412,412,412
BEGIN DESCRIPTION:
Conroe Lake 099 6.5
END DESCRIPTION:
XS GIS Cut Line= 4
      3757637.33     10191214.33      3756658.63     10191145.75
       3756647.9     10191165.17      3756739.45     10191814.36
#Sta/Elev= 30
  4018.9  278.87  4098.6  273.97  4128.6  271.28  4140.4  271.17  4208.8  263.65
    4259  259.73  4423.8  251.91  4489.5   250.8  4497.8  248.94  4501.3  248.94
  4509.6  251.01  4539.7  252.19  4579.8  251.54  4599.8  252.23  4639.9  251.78
    4690  252.39  4810.3  251.44  4830.4  252.42  4853.9  252.44  4997.9  251.18
  5028.1  252.29  5179.6  255.38  5197.8   256.7  5240.2  257.63  5371.5  264.32
  5512.9  269.34  5573.5  270.72  5654.3  270.93  5664.4  270.33  5677.8  271.12
#Mann= 3 , 0 , 0
  4018.9     .17       0  4853.9     .09       0  5028.1     .17       0
#XS Ineff= 2 , 0
       0  4848.9  252.74               0
Permanent Ineff=
       T       F
Bank Sta=4853.9,5028.1
XS Rating Curve= 0 ,0
Exp/Cntr=0.3,0.1

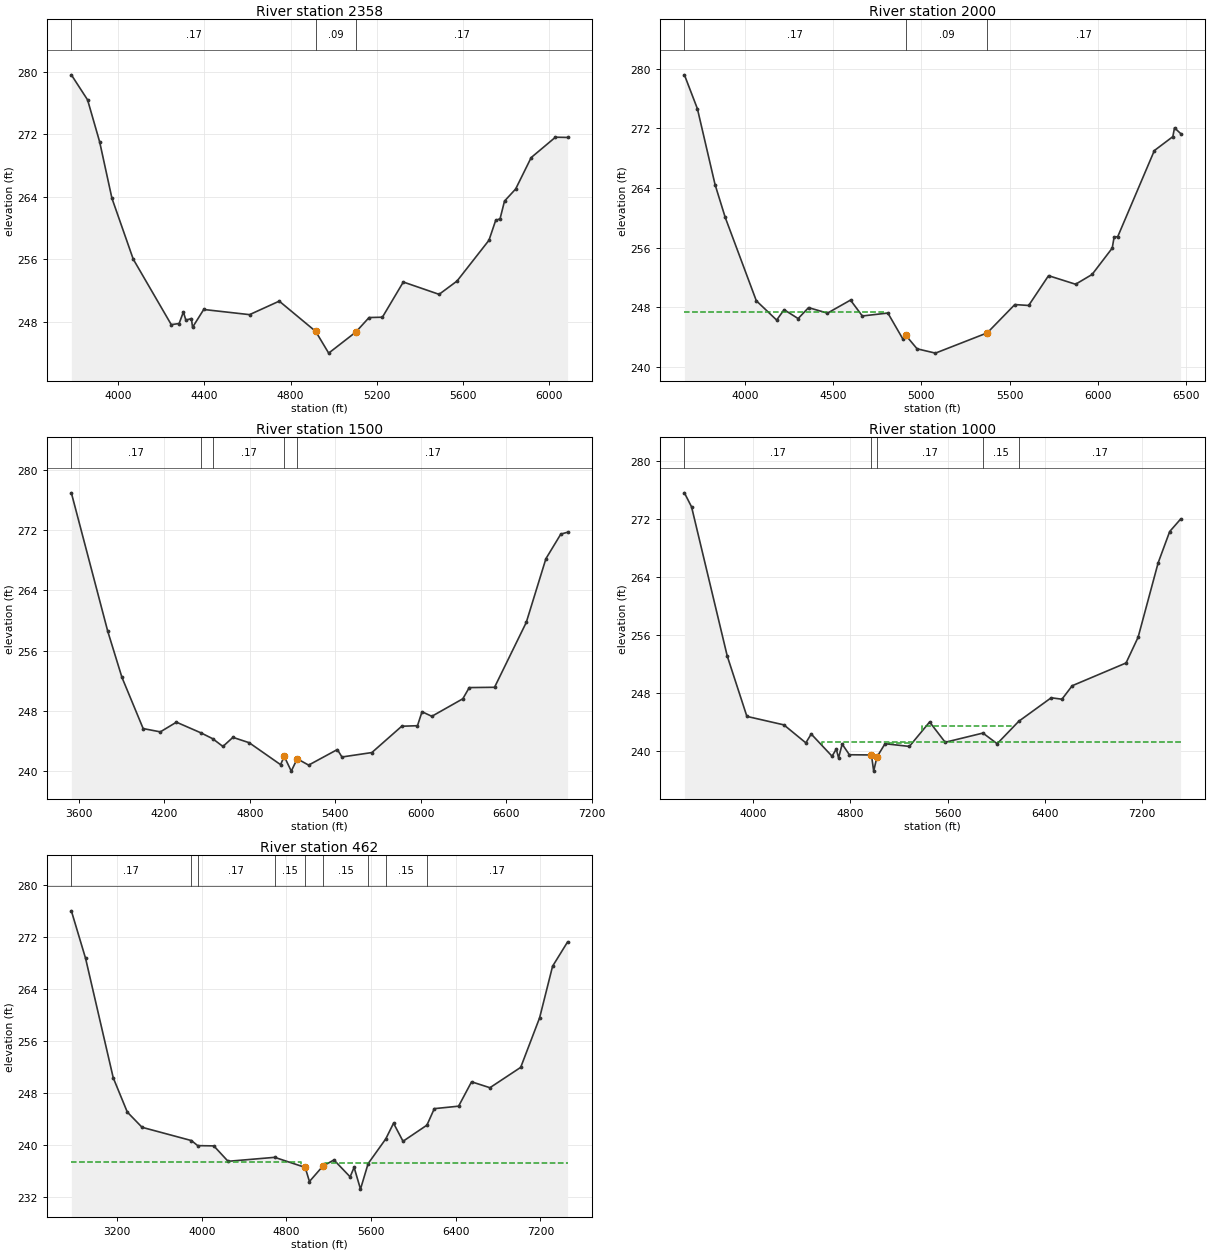
Type RM Length L Ch R = 1 ,2358    ,358,358,358
BEGIN DESCRIPTION:
Conroe Lake 099 2.0
END DESCRIPTION:
XS GIS Cut Line= 4
      3757648.97     10191168.25      3756498.83     10190770.11
      3756474.72     10190797.77      3756725.25     10191814.98
#Sta/Elev= 30
  3782.9  279.61  3858.2   276.4  3914.1  271.03  3971.1   263.8  4069.9     256
  4246.3  247.61  4282.7  247.75  4302.6  249.24  4313.9  248.19  4339.7  248.39
    4345  247.27  4396.8  249.55  4609.5  248.89  4747.1  250.62  4915.9  246.75
  4976.4  243.96  5101.9  246.65  5163.7  248.52  5225.5  248.56  5322.5  253.07
  5488.5  251.49  5571.5  253.19  5719.8  258.42  5750.7  260.95  5771.3  261.18
  5791.9  263.44  5843.4  264.98  5915.5  269.01  6028.1  271.62  6084.3  271.59
#Mann= 3 , 0 , 0
  3782.9     .17       0  4915.9     .09       0  5101.9     .17       0
#XS Ineff= 2 , 0
       0  4747.1  250.62               0
Permanent Ineff=
       T       F
Bank Sta=4915.9,5101.9
XS Rating Curve= 0 ,0
Exp/Cntr=0.3,0.1

Type RM Length L Ch R = 1 ,2000    ,500,500,500
BEGIN DESCRIPTION:
Conroe Lake 099 4.5
END DESCRIPTION:
XS GIS Cut Line= 5
      3757662.83     10191136.98      3756527.35     10190418.69
      3756482.54     10190439.69      3756417.77     10190787.59
      3756705.89     10191814.37
#Sta/Elev= 30
  3656.4  279.19  3730.1  274.64  3830.2  264.46  3887.8  260.05  4064.2  248.85
  4179.4  246.26  4221.8  247.65  4301.3  246.46  4360.4  247.93  4467.6  247.19
  4598.2  248.94  4665.2  246.81  4810.1   247.2  4895.7  243.69    4911  244.23
  4975.7   242.4  5079.7  241.82  5373.5  244.54  5529.8  248.34  5608.4  248.22
    5721  252.22  5874.4  251.07  5967.8  252.38  6082.1  255.92    6093  257.43
  6113.2  257.45    6321  269.02  6425.8  270.89  6435.2  272.07  6469.8  271.31
#Mann= 3 , 0 , 0
  3656.4     .17       0    4911     .09       0  5373.5     .17       0
#XS Ineff= 2 , 0
       0  4801.6   247.3               0
Permanent Ineff=
       F       F
Bank Sta=4911,5373.5
XS Rating Curve= 0 ,0
Exp/Cntr=0.3,0.1

Type RM Length L Ch R = 1 ,1500    ,500,500,500
BEGIN DESCRIPTION:
Conroe Lake 099 3.5
END DESCRIPTION:
XS GIS Cut Line= 5
      3757690.66     10191098.84      3756728.72     10190012.26
      3756608.84     10190039.95      3756309.36     10190653.24
      3756691.65     10191816.18
#Sta/Elev= 30
  3548.8  276.98  3804.1  258.57  3903.7  252.44  4052.5  245.63    4173  245.19
  4285.9  246.48  4458.9  245.05  4540.3  244.28  4612.1  243.25  4682.3  244.46
  4796.1  243.75  5016.6  240.83  5041.9  241.94  5091.5  239.97  5133.3  241.61
  5213.3  240.77  5414.7  242.84    5447  241.85  5656.9  242.44  5866.4  245.94
  5976.9  246.01  6008.7  247.87  6077.5  247.26  6294.9  249.59  6340.1  251.08
  6517.5  251.12  6740.1  259.75  6877.8  268.22  6982.2  271.49  7029.7  271.74
#Mann= 5 ,-1 , 0
  3548.8     .17       0  4458.9     .15       0  4540.3     .17       0
  5041.9     .09       0  5133.3     .17       0
#XS Ineff= 2 , 0
       0  4796.1  243.75               0
Permanent Ineff=
       F       F
Bank Sta=5041.9,5133.3
XS Rating Curve= 0 ,0
Exp/Cntr=0.3,0.1

Type RM Length L Ch R = 1 ,1000    ,538,538,538
BEGIN DESCRIPTION:
Conroe Lake 099 2.5
END DESCRIPTION:
XS GIS Cut Line= 6
      3757704.52     10191081.45      3757186.96     10189782.14
      3756578.18     10189973.84      3756266.39     10190342.04
      3756280.87     10190656.35      3756676.16     10191816.17
#Sta/Elev= 30
    3433  275.64  3492.1   273.7    3786  253.12  3947.8   244.8  4252.5  243.63
  4433.2  241.15  4477.5  242.37    4649  239.31    4684  240.29  4702.9  239.07
  4732.5  240.98  4791.9  239.51  4973.5  239.48  4992.1  237.25  5018.6  239.19
  5085.4  241.03  5285.8  240.66  5452.8  244.03    5581  241.23  5891.8   242.5
    6009  241.03  6187.2  244.13  6454.2  247.37  6542.5  247.17  6627.1  249.03
  7070.6  252.17  7169.9  255.72  7334.9  265.98    7430   270.3  7519.9  272.02
#Mann= 5 ,-1 , 0
    3433     .17       0  4973.5     .09       0  5018.6     .17       0
  5891.8     .15       0  6187.2     .17       0
#XS Ineff= 4 ,-1
  4477.5  4379.3  242.37  4563.6  4487.2  241.21  5116.6  5318.4  241.17
  5391.6  6139.1  243.47
Permanent Ineff=
       F       F       F       T
Bank Sta=4973.5,5018.6
XS Rating Curve= 0 ,0
Exp/Cntr=0.3,0.1

Type RM Length L Ch R = 1 ,462     ,0,0,0
BEGIN DESCRIPTION:
Conroe Lake 099 1.0
END DESCRIPTION:
XS GIS Cut Line= 6
      3757730.31     10191068.45      3757452.95     10189746.14
      3756601.55     10189520.01      3756226.62     10190336.25
      3756248.32     10190673.71      3756661.51      10191817.5
#Sta/Elev= 30
    2768  276.07  2902.5  268.75  3163.8  250.38  3296.6  245.11  3436.1  242.77
  3902.1  240.73  3961.9  239.95    4114  239.91  4248.5  237.54  4689.1  238.15
  4977.2   236.6  5017.3  234.43  5143.7  236.79    5249  237.75  5401.6  235.15
  5439.4  236.61  5499.7  233.26  5571.7  237.18  5738.2  240.98    5812   243.4
  5901.6  240.62  6127.2   243.1  6197.1  245.64  6426.5  246.02  6549.1  249.77
  6722.5  248.86  7013.2  251.99  7191.9  259.61  7314.5  267.55    7456  271.28
#Mann= 9 ,-1 , 0
    2768     .17       0  3902.1     .15       0  3961.9     .17       0
  4689.1     .15       0  4977.2     .09       0  5143.7     .15       0
  5571.7     .17       0  5738.2     .15       0  6127.2     .17       0
#XS Ineff= 2 , 0
       0    4937  237.38  5167.3       0  237.32
Permanent Ineff=
       T       T
Bank Sta=4977.2,5143.7
XS Rating Curve= 0 ,0
Exp/Cntr=0.3,0.1

Chan Stop Cuts=-1
Use User Specified Reach Order=0
Composite Channel Slope=5