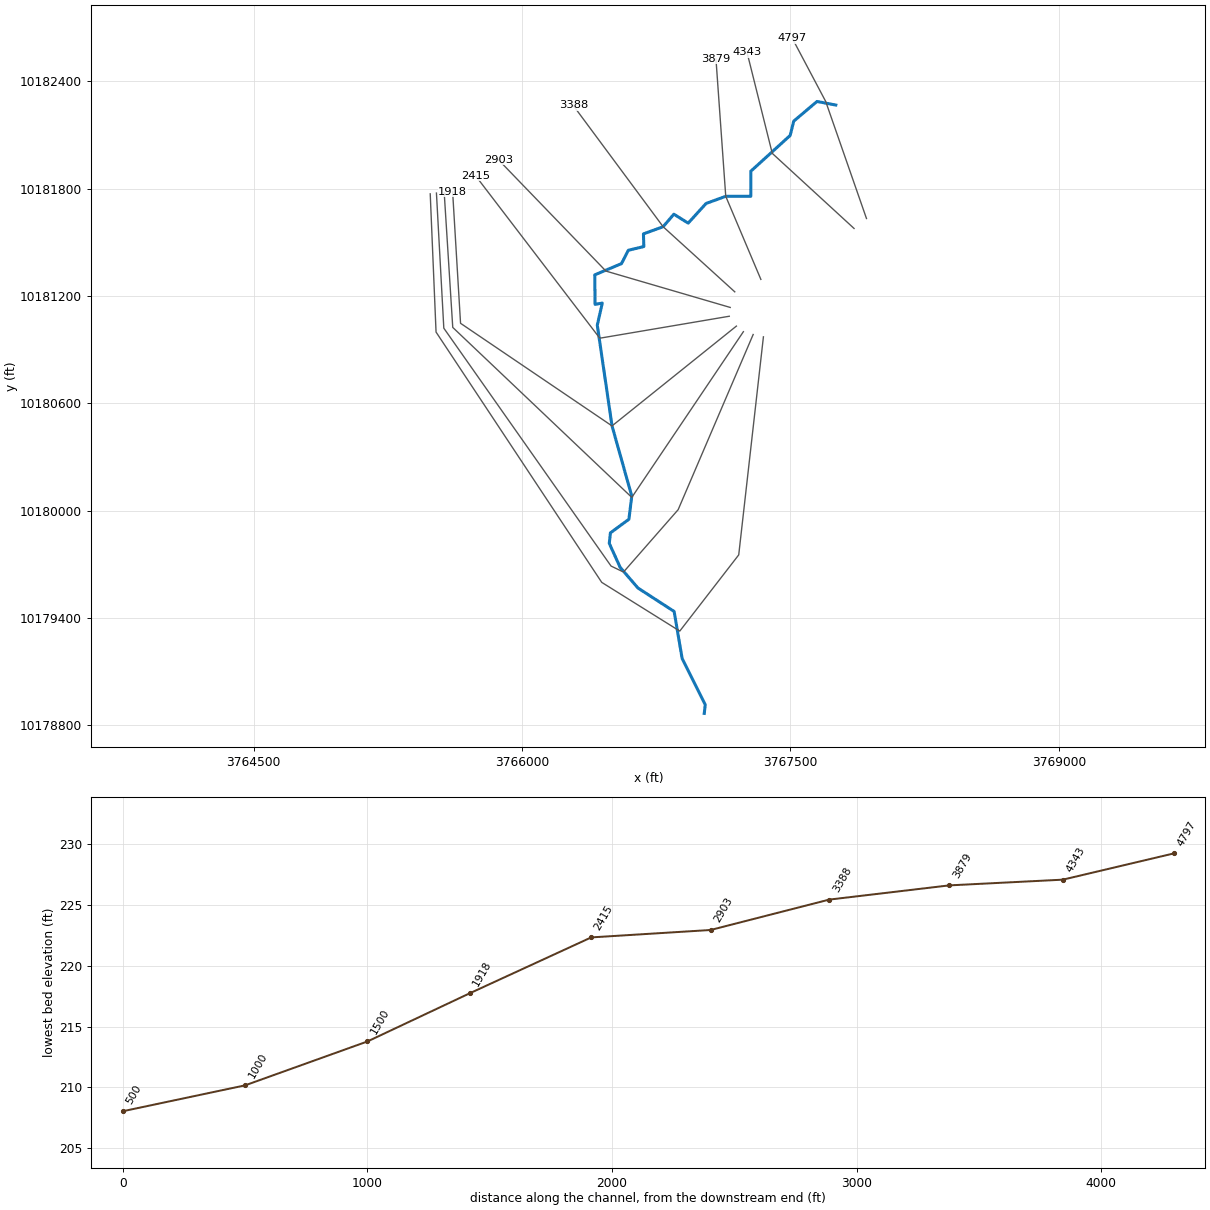
--- Conroe Lake 102.prj (project) ---

Proj Title=Conroe Lake 102 Base Level Engineering
Current Plan=p01
Default Exp/Contr=0.3,0.1
English Units
Geom File=g01
Flow File=f01
Flow File=f02
Plan File=p01
Y Axis Title=Elevation
X Axis Title(PF)=Main Channel Distance
X Axis Title(XS)=Station
BEGIN DESCRIPTION:
Conroe Lake 102
END DESCRIPTION:
DSS Export Rating Curves= 0
DSS Export Rating Curve Sorted= 0
DSS Export Volume Flow Curves= 0
DXF OffsetX= 0
DXF OffsetY= 0
DXF ScaleX= 1
DXF ScaleY= 10

--- Conroe Lake 102.p01 (plan) ---

Plan Title=Multiple Run
Short Identifier=Multiple
Geom File=g01
Flow File=f01
Subcritical Flow
K Sum by GR= 0
Std Step Tol= 0.01
Critical Tol= 0.01
Num of Std Step Trials= 20
Max Error Tol= 0.3
Flow Tol Ratio= 0.001
Split Flow NTrial= 30
Split Flow Tol= 0.02
Split Flow Ratio= 0.02
Log Output Level= 0
Friction Slope Method= 1
Unsteady Friction Slope Method= 2
Unsteady Bridges Friction Slope Method= 1
Parabolic Critical Depth
Global Vel Dist=  1 , 1 , 1
Global Log Level= 0
CheckData=True
Encroach Param= -1, 0, 0, 0
BEGIN DESCRIPTION:
Multiple Run
END DESCRIPTION:

--- Conroe Lake 102.f01 (steady flow) ---

Flow Title=Multiple
Program Version=4.10
Number of Profiles= 7
Profile Names=10-year,25-year,50-year,1pct_min,100-year,1pct_plu,500-year
River Rch & RM=Conroe Lake 102,Reach-1         ,4797
     530     711     955     422    1275    3850    2350
River Rch & RM=Conroe Lake 102,Reach-1         ,4343
     709     964    1305     581    1756    5303    3287
River Rch & RM=Conroe Lake 102,Reach-1         ,500
     746    1019    1385     619    1869    5644    3521
Boundary for River Rch & Prof#=Conroe Lake 102,Reach-1         , 1
Up Type= 0
Dn Type= 3
Dn Slope=0.005
Boundary for River Rch & Prof#=Conroe Lake 102,Reach-1         , 2
Up Type= 0
Dn Type= 3
Dn Slope=0.005
Boundary for River Rch & Prof#=Conroe Lake 102,Reach-1         , 3
Up Type= 0
Dn Type= 3
Dn Slope=0.005
Boundary for River Rch & Prof#=Conroe Lake 102,Reach-1         , 4
Up Type= 0
Dn Type= 3
Dn Slope=0.005
Boundary for River Rch & Prof#=Conroe Lake 102,Reach-1         , 5
Up Type= 0
Dn Type= 3
Dn Slope=0.005
Boundary for River Rch & Prof#=Conroe Lake 102,Reach-1         , 6
Up Type= 0
Dn Type= 3
Dn Slope=0.005
Boundary for River Rch & Prof#=Conroe Lake 102,Reach-1         , 7
Up Type= 0
Dn Type= 3
Dn Slope=0.005
DSS Import GetInterval= 0
DSS Import GetPeak= 0
DSS Import FillOption= 0

--- Conroe Lake 102.f02 (steady flow) ---

Flow Title=Orig_BLE_Flow
Program Version=4.10
Number of Profiles= 7
Profile Names=10-year,25-year,50-year,1pct_min,100-year,1pct_plu,500-year
River Rch & RM=Conroe Lake 102,Reach-1         ,4797
     530     697     830     325     981    2961    1366
River Rch & RM=Conroe Lake 102,Reach-1         ,4343
     709     945    1135     447    1351    4080    1911
River Rch & RM=Conroe Lake 102,Reach-1         ,500
     746     999    1204     476    1438    4342    2047
Boundary for River Rch & Prof#=Conroe Lake 102,Reach-1         , 1
Up Type= 0
Dn Type= 3
Dn Slope=0.005
Boundary for River Rch & Prof#=Conroe Lake 102,Reach-1         , 2
Up Type= 0
Dn Type= 3
Dn Slope=0.005
Boundary for River Rch & Prof#=Conroe Lake 102,Reach-1         , 3
Up Type= 0
Dn Type= 3
Dn Slope=0.005
Boundary for River Rch & Prof#=Conroe Lake 102,Reach-1         , 4
Up Type= 0
Dn Type= 3
Dn Slope=0.005
Boundary for River Rch & Prof#=Conroe Lake 102,Reach-1         , 5
Up Type= 0
Dn Type= 3
Dn Slope=0.005
Boundary for River Rch & Prof#=Conroe Lake 102,Reach-1         , 6
Up Type= 0
Dn Type= 3
Dn Slope=0.005
Boundary for River Rch & Prof#=Conroe Lake 102,Reach-1         , 7
Up Type= 0
Dn Type= 3
Dn Slope=0.005
DSS Import GetInterval= 0
DSS Import GetPeak= 0
DSS Import FillOption= 0

--- Conroe Lake 102.g01 (geometry) ---

Geom Title=Existing Conditions
Program Version=4.10

River Reach=Conroe Lake 102 ,Reach-1
Reach XY= 30
      3767753.23     10182266.84      3767648.23     10182286.84
      3767518.23     10182176.84      3767498.23     10182096.84
      3767278.23     10181896.84      3767278.23     10181756.84
      3767138.23     10181756.84      3767028.23     10181716.84
      3766928.23     10181606.84      3766848.23     10181656.84
      3766788.23     10181586.84      3766678.23     10181546.84
       3766680.5     10181475.97       3766593.7     10181455.13
       3766555.5     10181380.48       3766406.2     10181317.98
      3766407.93     10181153.05      3766448.23     10181159.99
      3766420.29     10181036.39      3766502.69     10180473.55
      3766613.03      10180081.1      3766596.97     10179951.91
      3766493.62     10179875.79      3766487.33     10179817.13
      3766548.09     10179683.06      3766647.25     10179567.84
      3766849.76     10179436.55      3766894.45     10179173.99
      3767023.64     10178915.61      3767018.12     10178866.98

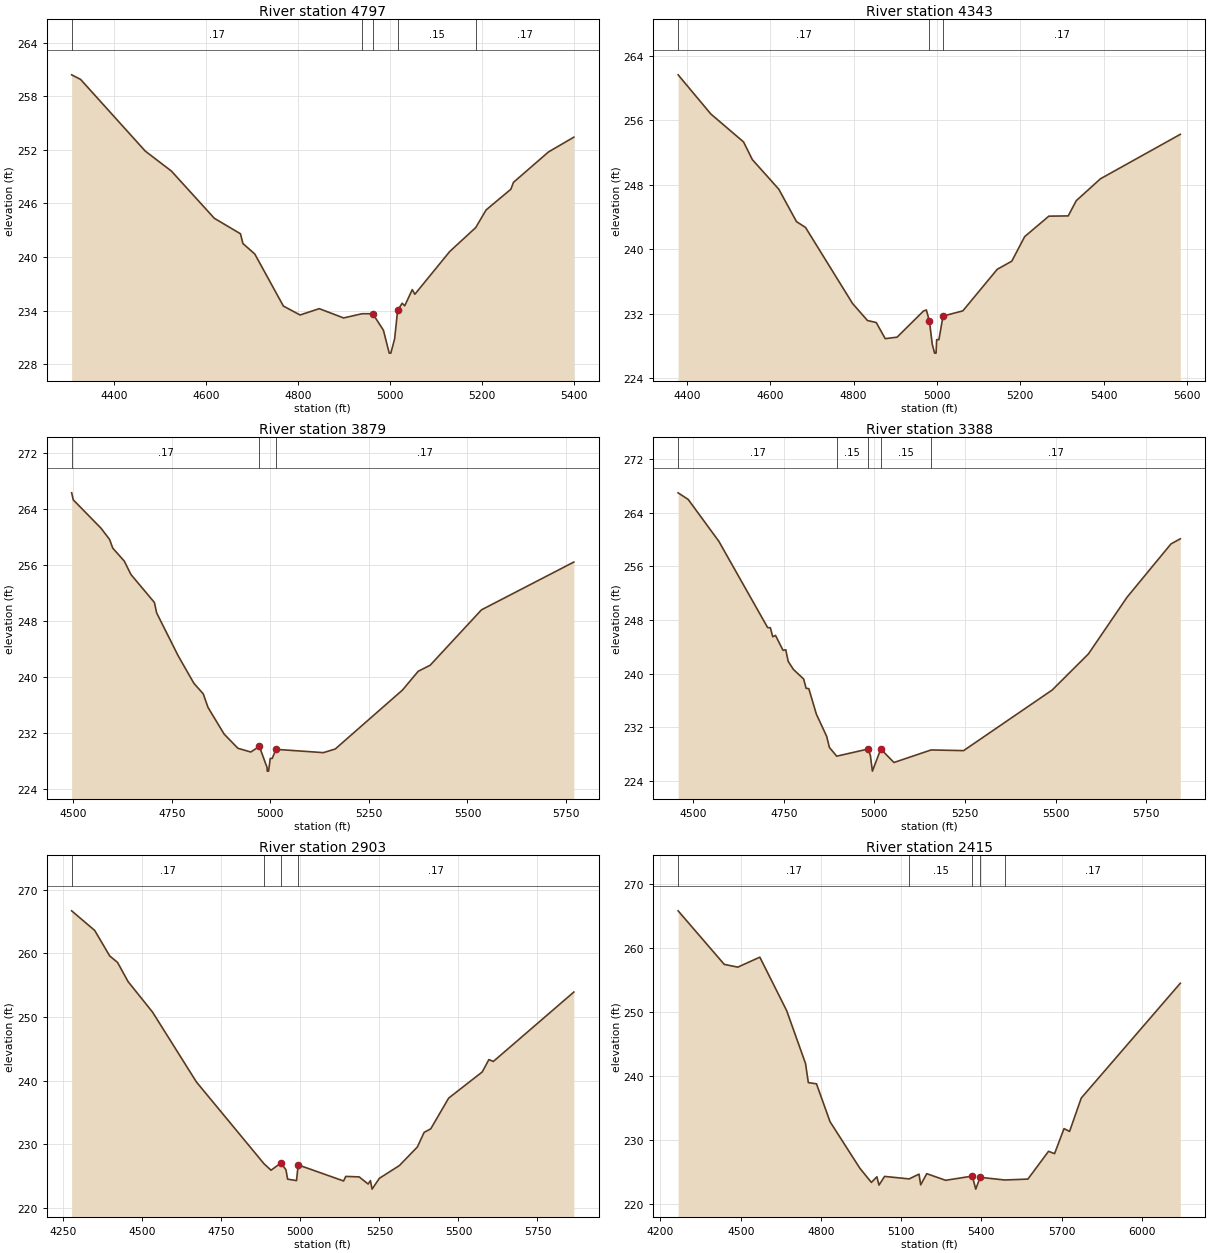
Type RM Length L Ch R = 1 ,4797    ,454,454,454
BEGIN DESCRIPTION:
Conroe Lake 102 8.0
END DESCRIPTION:
XS GIS Cut Line= 3
      3767924.79     10181632.71      3767696.89     10182286.84
      3767510.22     10182639.71
#Sta/Elev= 30
  4307.3   260.4  4326.7  259.89  4467.4  251.86  4524.3  249.62  4617.5  244.34
  4674.4   242.6  4679.7  241.51  4705.5  240.34  4767.7  234.51    4804  233.51
  4845.6  234.22  4898.6  233.18  4938.6  233.65  4962.1  233.65  4985.2   231.8
  4997.8  229.24  5001.3  229.24  5009.5  230.83  5016.1  234.04  5025.9  234.82
  5031.5  234.54  5047.9  236.35  5053.5  235.83  5129.2  240.61  5185.9   243.3
  5208.4  245.27  5262.3  247.59  5267.9  248.36  5344.2  251.77  5399.2  253.42
#Mann= 5 ,-1 , 0
  4307.3     .17       0  4938.6     .15       0  4962.1     .09       0
  5016.1     .15       0  5185.9     .17       0
Bank Sta=4962.1,5016.1
XS Rating Curve= 0 ,0
Exp/Cntr=0.3,0.1

Type RM Length L Ch R = 1 ,4343    ,464,464,464
BEGIN DESCRIPTION:
Conroe Lake 102 7.0
END DESCRIPTION:
XS GIS Cut Line= 3
      3767855.37     10181577.12      3767398.23     10181996.84
      3767256.74     10182563.14
#Sta/Elev= 30
  4379.4  261.64    4458  256.77  4536.3  253.31  4557.3  251.12  4620.8  247.44
  4663.3  243.41  4684.9  242.69  4797.8  233.24  4833.5  231.13  4854.5  230.88
  4876.1  228.88  4904.4  229.06  4967.9  232.31  4974.7  232.44  4982.1  231.04
  4988.9  228.18  4994.5  227.08    4998  227.08  4999.4  228.75  5004.8  228.75
  5014.7  231.68  5062.2  232.33  5144.7  237.49  5179.6   238.5  5210.5  241.55
  5268.5  244.09  5314.9  244.12  5334.2  246.01  5392.2  248.73  5583.7  254.25
#Mann= 3 , 0 , 0
  4379.4     .17       0  4982.1     .09       0  5014.7     .17       0
Bank Sta=4982.1,5014.7
XS Rating Curve= 0 ,0
Exp/Cntr=0.3,0.1

Type RM Length L Ch R = 1 ,3879    ,491,491,491
BEGIN DESCRIPTION:
Conroe Lake 102 6.0
END DESCRIPTION:
XS GIS Cut Line= 3
      3767334.52     10181292.42      3767138.23     10181756.84
      3767083.51      10182524.8
#Sta/Elev= 30
  4495.8  266.33  4499.9  265.33  4570.3  261.28    4592  259.68  4600.1  258.44
  4629.3  256.59  4646.3  254.67  4705.8  250.68  4711.5  249.19  4765.7  243.11
    4806  239.14  4829.7  237.64  4841.7  235.71  4882.6   231.9  4917.7  229.87
  4950.3  229.34    4972  230.14  4991.7  227.11    4992  226.61  4995.5  226.61
  4999.6  228.42  5004.6  228.42  5014.3  229.72  5134.6  229.25  5164.6  229.77
  5335.1  238.18  5375.2  240.87  5405.3  241.72  5535.6  249.63  5769.9  256.45
#Mann= 3 , 0 , 0
  4495.8     .17       0    4972     .09       0  5014.3     .17       0
Bank Sta=4972,5014.3
XS Rating Curve= 0 ,0
Exp/Cntr=0.3,0.1

Type RM Length L Ch R = 1 ,3388    ,485,485,485
BEGIN DESCRIPTION:
Conroe Lake 102 5.0
END DESCRIPTION:
XS GIS Cut Line= 3
       3767188.7     10181222.95      3766788.23     10181586.84
      3766285.93      10182264.6
#Sta/Elev= 30
  4458.9  266.96  4486.8  265.97  4571.3  259.72  4705.7  246.86  4713.2  246.83
  4719.9  245.49  4727.4  245.69  4748.3  243.46  4755.7  243.55  4762.5  241.81
  4776.7  240.62  4805.1  239.18  4811.8   237.8  4819.3  237.74  4840.2  233.93
  4868.6  230.62    4876  228.98  4896.2  227.67  4982.1  228.73  4988.9  227.83
  4994.6  225.44  5017.7  228.73  5054.1  226.73  5156.5   228.6  5246.1   228.5
  5490.3  237.54  5590.3  242.93  5696.8  251.39  5817.9  259.34  5843.6   260.1
#Mann= 5 ,-1 , 0
  4458.9     .17       0  4896.2     .15       0  4982.1     .09       0
  5017.7     .15       0  5156.5     .17       0
Bank Sta=4982.1,5017.7
XS Rating Curve= 0 ,0
Exp/Cntr=0.3,0.1

Type RM Length L Ch R = 1 ,2903    ,488,488,488
BEGIN DESCRIPTION:
Conroe Lake 102 4.0
END DESCRIPTION:
XS GIS Cut Line= 3
       3767163.3     10181135.68       3766468.7     10181338.82
      3765867.85     10181961.07
#Sta/Elev= 30
  4276.3  266.66  4349.3  263.58  4396.6  259.58  4421.4  258.56  4454.9  255.54
  4532.2  250.75  4671.1  239.77  4884.6  226.94  4907.1  225.91  4938.4  227.05
  4954.3  225.97  4959.5  224.51  4987.7  224.28  4992.9  226.75  5136.6  224.22
  5143.5  224.94    5186  224.86  5214.3  223.74  5221.5  224.28  5226.7  222.94
  5249.8  224.64  5313.3  226.65  5369.9  229.56  5391.3  231.85  5412.4  232.42
    5469  237.24    5575  241.34  5596.3  243.29  5610.4     243    5865   253.9
#Mann= 4 ,-1 , 0
  4276.3     .17       0  4884.6     .15       0  4938.4     .09       0
  4992.9     .17       0
Bank Sta=4938.4,4992.9
XS Rating Curve= 0 ,0
Exp/Cntr=0.3,0.1

Type RM Length L Ch R = 1 ,2415    ,497,497,497
BEGIN DESCRIPTION:
Conroe Lake 102 3.0
END DESCRIPTION:
XS GIS Cut Line= 3
      3767158.02     10181086.53      3766434.26     10180963.76
      3765739.43     10181872.57
#Sta/Elev= 30
  4265.9  265.88  4438.5   257.5  4489.2  257.07  4571.5  258.63  4671.8  250.27
  4742.4  241.99  4752.9     239  4783.4  238.81  4834.1  232.88  4945.6   225.6
  4988.7  223.38  5009.2  224.26  5017.1  222.96    5038  224.32    5130  223.93
  5166.8  224.68  5173.1     223  5195.8  224.75  5266.5  223.71  5366.2  224.37
    5379  222.33  5395.3  224.18  5487.1  223.76    5574   223.9  5651.2  228.25
  5673.7  227.88  5709.1   231.8  5729.9  231.36  5773.5  236.58    6144  254.55
#Mann= 5 ,-1 , 0
  4265.9     .17       0    5130     .15       0  5366.2     .09       0
  5395.3     .15       0  5487.1     .17       0
Bank Sta=5366.2,5395.3
XS Rating Curve= 0 ,0
Exp/Cntr=0.3,0.1

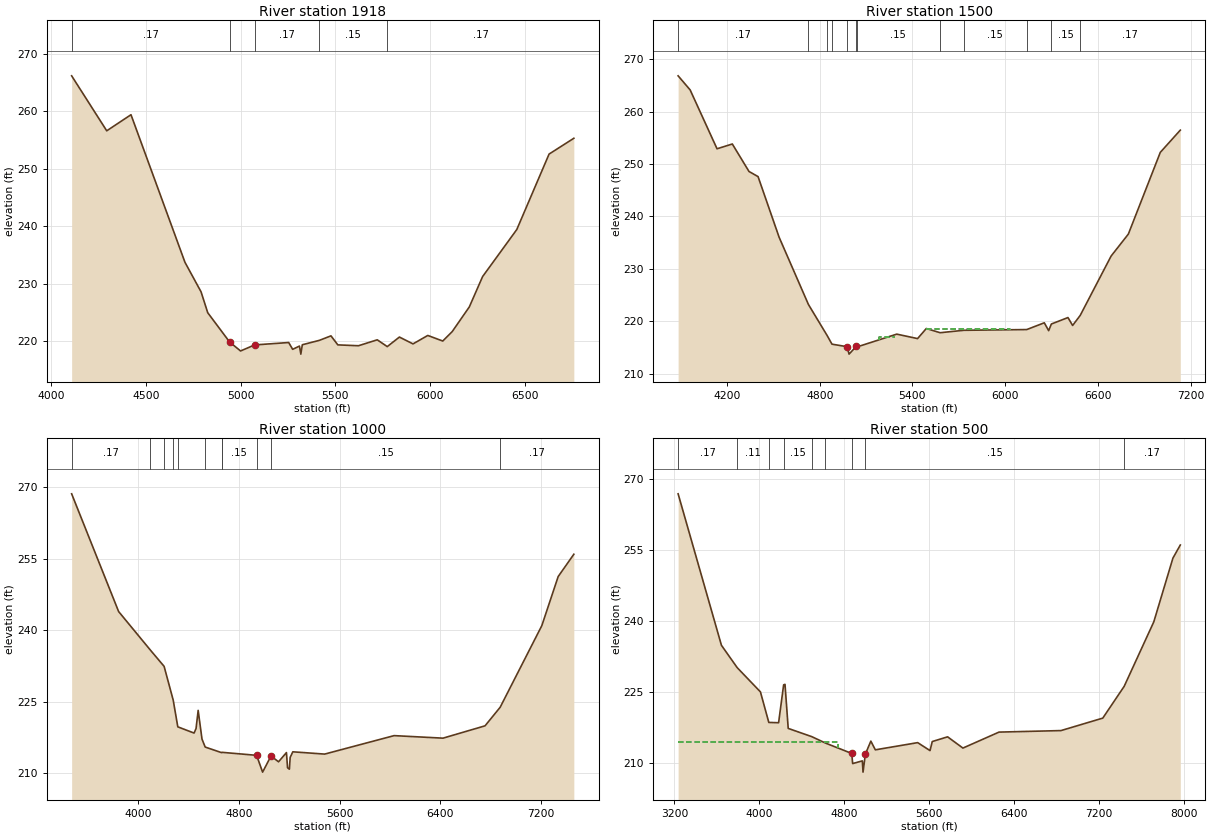
Type RM Length L Ch R = 1 ,1918    ,418,418,418
BEGIN DESCRIPTION:
Conroe Lake 102 2.0
END DESCRIPTION:
XS GIS Cut Line= 4
      3767197.78     10181031.46      3766502.69     10180473.55
      3765656.09     10181047.06      3765611.82     10181781.45
#Sta/Elev= 30
  4108.7  266.17  4293.8   256.6  4421.8   259.4  4706.6  233.71  4791.5  228.57
  4826.7  224.94  4941.9  219.85  4999.9  218.28  5074.1  219.33  5253.8  219.75
  5274.8  218.57  5310.7  219.13  5317.9  217.73  5325.7  219.36  5415.9  220.13
  5476.9  220.91  5513.1  219.34  5621.9  219.19  5721.1  220.22  5773.9  219.04
  5837.9   220.7  5909.8  219.51  5987.7  220.98  6066.7  220.01  6116.8  221.66
  6206.9  225.95    6277  231.23  6457.4  239.42  6627.7  252.55  6758.3   255.3
#Mann= 5 ,-1 , 0
  4108.7     .17       0  4941.9     .09       0  5074.1     .17       0
  5415.9     .15       0  5773.9     .17       0
#XS Ineff= 2 , 0
       0                  5476.9       0  220.91
Permanent Ineff=
       F       T
Bank Sta=4941.9,5074.1
XS Rating Curve= 0 ,0
Exp/Cntr=0.3,0.1

Type RM Length L Ch R = 1 ,1500    ,500,500,500
BEGIN DESCRIPTION:
Conroe Lake 102 3.5
END DESCRIPTION:
XS GIS Cut Line= 4
      3767236.83     10181000.21      3766613.13     10180074.04
      3765612.47     10181024.13      3765564.76     10181776.67
#Sta/Elev= 30
  3883.4   266.8  3961.4  264.11  4135.3   252.9  4234.3  253.81  4342.3  248.57
  4400.8   247.6  4537.2  236.04  4726.9  223.23  4848.5  217.29  4879.2  215.67
    4978  215.18  4989.8  213.77  5036.9  215.25  5039.1  215.12  5298.6  217.58
  5433.3  216.73  5489.9  218.65    5579  217.85  5733.1  218.31    6140  218.45
  6253.6  219.74  6281.9  218.24  6299.3  219.51  6406.8  220.74  6436.9  219.23
  6485.9  221.14  6686.1  232.46  6797.6  236.64  7004.5  252.22  7133.9  256.45
#Mann= 12 ,-1 , 0
  3883.4     .17       0  4726.9     .11       0  4848.5     .15       0
  4879.2     .11       0    4978     .06       0  5036.9     .11       0
  5039.1     .15       0    5579     .17       0  5733.1     .15       0
    6140     .17       0  6299.3     .15       0  6485.9     .17       0
#XS Ineff= 3 ,-1
  5185.7 5288.73  216.96  5298.6  5489.9  217.58  5489.9  6034.3  218.65
Permanent Ineff=
       F       F       F
Bank Sta=4978,5036.9
XS Rating Curve= 0 ,0
Exp/Cntr=0.3,0.1

Type RM Length L Ch R = 1 ,1000    ,500,500,500
BEGIN DESCRIPTION:
Conroe Lake 102 2.5
END DESCRIPTION:
XS GIS Cut Line= 6
      3767291.49     10180984.51      3766872.23     10180005.39
      3766566.91     10179656.94      3766497.23     10179690.29
      3765562.55     10181019.79      3765521.32     10181775.04
#Sta/Elev= 30
  3471.6  268.65  3844.5  243.91    4097   235.8  4205.7  232.39    4278  225.29
  4314.4  219.68  4443.5  218.37  4459.4  219.33  4476.1  223.14  4506.5  217.11
  4531.8  215.43  4662.3  214.25  4665.8  214.32  4940.1  213.69  4987.7  210.16
  5054.4  213.55  5114.2  212.33    5177  214.27  5185.7  211.08  5200.4  210.78
  5206.6  213.25  5227.5  214.43  5480.1  213.95  6031.7  217.83  6420.2   217.3
  6753.8  219.89  6873.8  223.79  7204.5  240.94  7334.6  251.27  7458.8  255.95
#Mann= 11 ,-1 , 0
  3471.6     .17       0    4097     .11       0  4205.7     .17       0
    4278     .11       0  4314.4     .17       0  4531.8     .15       0
  4662.3     .11       0  4665.8     .15       0  4940.1     .09       0
  5054.4     .15       0  6873.8     .17       0
Bank Sta=4940.1,5054.4
XS Rating Curve= 0 ,0
Exp/Cntr=0.3,0.1

Type RM Length L Ch R = 1 ,500     ,0,0,0
BEGIN DESCRIPTION:
Conroe Lake 102 1.0
END DESCRIPTION:
XS GIS Cut Line= 6
      3767348.79      10180971.5      3767210.78     10179752.79
      3766881.28     10179326.86      3766445.15     10179599.14
      3765519.15     10180998.09       3765486.6     10181770.61
#Sta/Elev= 30
    3235  266.92  3643.1  234.87  3791.1  230.15  4010.3  225.01  4089.2  218.55
  4181.5  218.48  4228.9   226.5  4241.8  226.61    4272  217.28  4493.8  215.54
  4621.9  214.19  4870.6  211.98  4878.8  209.84  4970.2  210.41  4976.6  208.03
  4998.7  211.83  5050.2  214.59  5092.7  212.75  5491.4  214.27  5607.6  212.59
  5628.7   214.5  5773.1   215.5  5917.5  213.12  6257.5   216.5  6841.2  216.82
  7234.8  219.46  7436.3  226.18  7715.2  239.82  7895.4  253.31    7965  256.09
#Mann= 9 ,-1 , 0
    3235     .17       0  3791.1     .11       0  4089.2     .17       0
  4228.9     .15       0  4493.8     .11       0  4621.9     .15       0
  4870.6     .09       0  4998.7     .15       0  7436.3     .17       0
#XS Ineff= 2 , 0
       0    4742   214.4  5050.2       0  214.59
Permanent Ineff=
       T       T
Bank Sta=4870.6,4998.7
XS Rating Curve= 0 ,0
Exp/Cntr=0.3,0.1

Chan Stop Cuts=-1
Use User Specified Reach Order=0
Composite Channel Slope=5