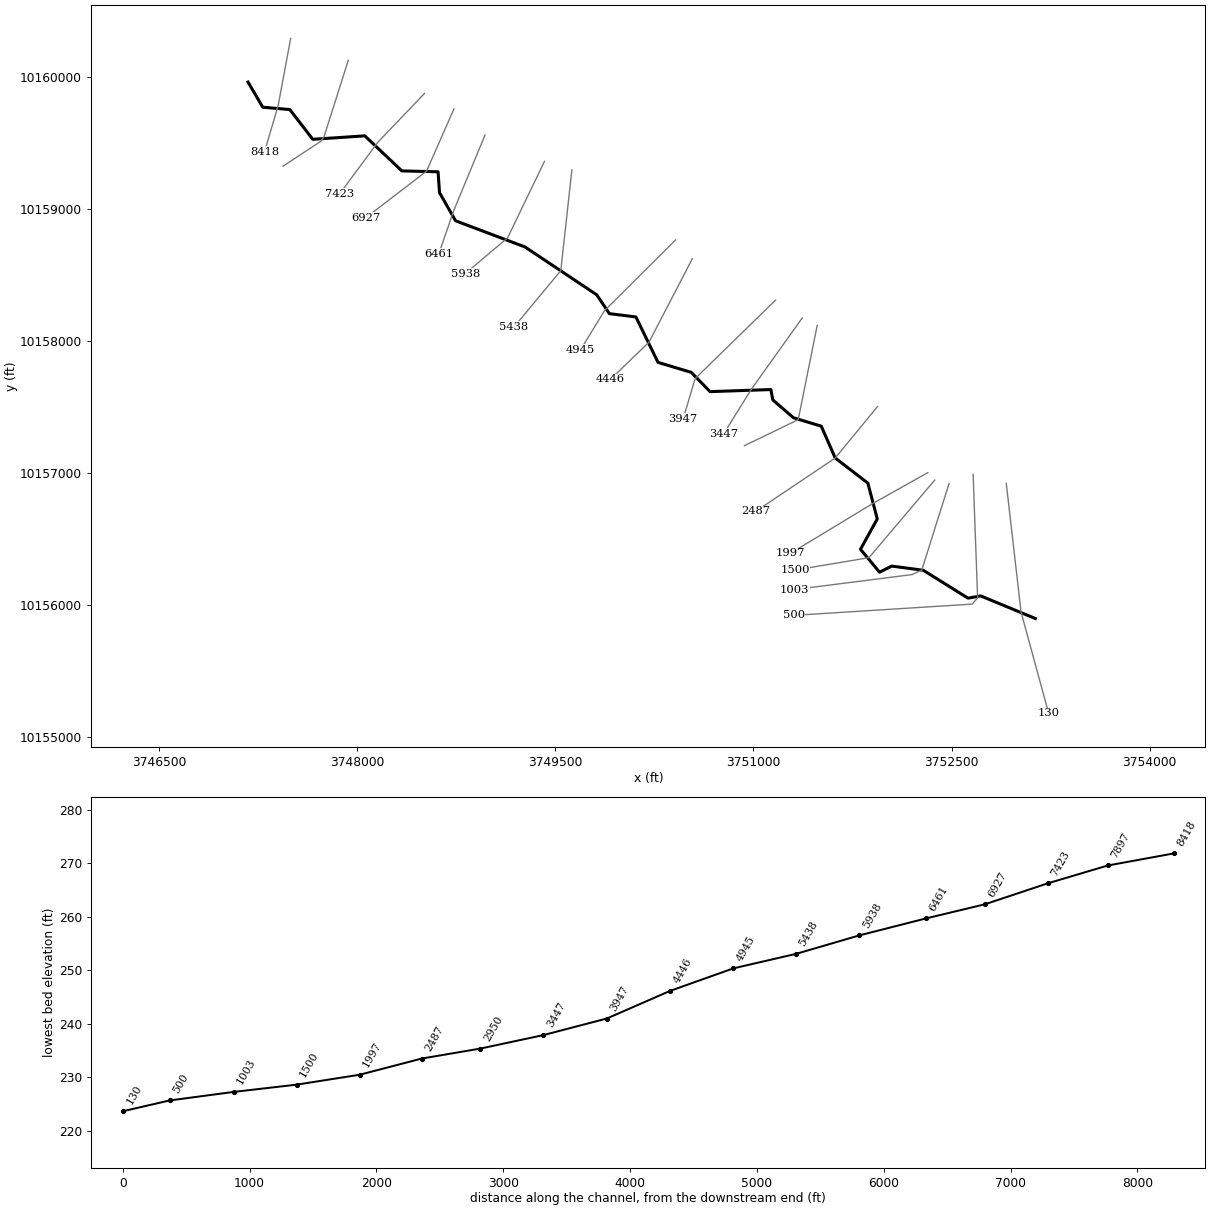
--- Conroe Lake 104.prj (project) ---

Proj Title=Conroe Lake 104 Base Level Engineering
Current Plan=p01
Default Exp/Contr=0.3,0.1
English Units
Geom File=g01
Flow File=f01
Flow File=f02
Plan File=p01
Y Axis Title=Elevation
X Axis Title(PF)=Main Channel Distance
X Axis Title(XS)=Station
BEGIN DESCRIPTION:
Conroe Lake 104
END DESCRIPTION:
DSS File=dss
DSS Export Rating Curves= 0
DSS Export Rating Curve Sorted= 0
DSS Export Volume Flow Curves= 0
DXF OffsetX= 0
DXF OffsetY= 0
DXF ScaleX= 1
DXF ScaleY= 10

--- Conroe Lake 104.p01 (plan) ---

Plan Title=Multiple Run
Program Version=4.10
Geom File=g01
Flow File=f01
Subcritical Flow
K Sum by GR= 0
Std Step Tol= 0.01
Critical Tol= 0.01
Num of Std Step Trials= 20
Max Error Tol= 0.3
Flow Tol Ratio= 0.001
Split Flow NTrial= 30
Split Flow Tol= 0.02
Split Flow Ratio= 0.02
Log Output Level= 0
Friction Slope Method= 1
Unsteady Friction Slope Method= 2
Unsteady Bridges Friction Slope Method= 1
Parabolic Critical Depth
Global Vel Dist= 1 , 1 , 1
Global Log Level= 0
CheckData=True
Encroach Param=-1 ,0,0, 0
BEGIN DESCRIPTION:
Multiple Run
END DESCRIPTION:
Computation Interval=1HOUR
Output Interval=1HOUR
Run HTab= 0
Run UNet= 0
Run PostProcess= 0
Run WQNet= 0
UNET Theta= 1
UNET Theta Warmup= 1
UNET ZTol= 0.02
UNET ZSATol= 0.05
UNET MxIter= 20
UNET MaxInSteps= 0
UNET DtIC= 0
UNET DtMin= 0
UNET MaxCRTS= 20
UNET WFStab= 2
UNET SFStab= 1
UNET WFX= 1
UNET SFX= 1
UNET DSS MLevel= 4
UNET DZMax Abort= 100
UNET Convert EG Bridges= 0
UNET Use Existing IB Tables=-1
UNET Froude Reduction=False
UNET Froude Limit= 1
UNET Froude Power= 10
UNET Time Slicing=0,0, 5
UNET Junction Losses=0
Instantaneous Interval=1HOUR
DSS File=dss
Write IC File= 0
Write IC File at Sim End=0
Echo Input=False
Echo Parameters=False
Echo Output=False
Write Detailed= 0
WQ AD Non Conservative
WQ ULTIMATE=-1
WQ Max Comp Step=1HOUR
WQ Output Interval=15MIN
WQ Output Selected Increments= 0
WQ Output face flow=0
WQ Output face velocity=0
WQ Output face area=0
WQ Output face dispersion=0
WQ Output cell volume=0
WQ Output cell surface area=0
WQ Output cell continuity=0
WQ Output cumulative cell continuity=0
WQ Output face conc=0
WQ Output face dconc_dx=0
WQ Output face courant=0
WQ Output face peclet=0
WQ Output face adv mass=0
WQ Output face disp mass=0
WQ Output cell mass=0
WQ Output cell source sink temp=0
WQ Output cell source sink nsm=0
WQ Output MaxMinRange=-1
WQ Daily Max Min Mean=-1
WQ Daily Range=0
WQ Daily Time=0
WQ Create Restart=0
WQ Fixed Restart=0
WQ System Summary=0
WQ Use Fixed Temperature=0
Sorting and Armoring Iterations= 10
XS Update Threshold= 0.02
Hydraulics Update Threshold= 0.02
Energy Slope Method= 1
Volume Change Method= 0
XS Weighting Method= 0
Number of US Weighted Cross Sections= 1
Number of DS Weighted Cross Sections= 1
Upstream XS Weight=0.25
Main XS Weight=0.5
Downstream XS Weight=0.25
Number of DS XS's Weighted with US Boundary= 1
Upstream Boundary Weight= 1
Weight of XSs Associated with US Boundary= 0
Number of US XS's Weighted with DS Boundary= 1
Downstream Boundary Weight= 0.5
Weight of XSs Associated with DS Boundary= 0.5
Sediment Output Level= 4
Mass or Volume Output= 0
Output Increment Type= 1
Profile and TS Output Increment= 10
XS Output Flag= 0
XS Output Increment= 10
Disregard all LS=0
Disregard all Conn=0
Disregard all Breaches=0
Disregard all Pumps=0

--- Conroe Lake 104.f01 (steady flow) ---

Flow Title=Multiple
Program Version=4.10
Number of Profiles= 7
Profile Names=10-year,25-year,50-year,1pct_min,100-year,1pct_plu,500-year
River Rch & RM=Conroe Lake 104,Reach-1         ,8418
     280     364     480     208     629    1900    1121
River Rch & RM=Conroe Lake 104,Reach-1         ,7423
     562     756    1015     449    1357    4098    2506
River Rch & RM=Conroe Lake 104,Reach-1         ,130
    1881    2679    3741    1712    5170   15613   10224
Boundary for River Rch & Prof#=Conroe Lake 104,Reach-1         , 1
Up Type= 0
Dn Type= 3
Dn Slope=0.01
Boundary for River Rch & Prof#=Conroe Lake 104,Reach-1         , 2
Up Type= 0
Dn Type= 3
Dn Slope=0.01
Boundary for River Rch & Prof#=Conroe Lake 104,Reach-1         , 3
Up Type= 0
Dn Type= 3
Dn Slope=0.01
Boundary for River Rch & Prof#=Conroe Lake 104,Reach-1         , 4
Up Type= 0
Dn Type= 3
Dn Slope=0.01
Boundary for River Rch & Prof#=Conroe Lake 104,Reach-1         , 5
Up Type= 0
Dn Type= 3
Dn Slope=0.01
Boundary for River Rch & Prof#=Conroe Lake 104,Reach-1         , 6
Up Type= 0
Dn Type= 3
Dn Slope=0.01
Boundary for River Rch & Prof#=Conroe Lake 104,Reach-1         , 7
Up Type= 0
Dn Type= 3
Dn Slope=0.01
DSS Import GetInterval= 0
DSS Import GetPeak= 0
DSS Import FillOption= 0

--- Conroe Lake 104.f02 (steady flow) ---

Flow Title=Orig_BLE_Flow
Program Version=4.10
Number of Profiles= 7
Profile Names=10-year,25-year,50-year,1pct_min,100-year,1pct_plu,500-year
River Rch & RM=Conroe Lake 104,Reach-1         ,8418
     280     357     417     160     484    1463     652
River Rch & RM=Conroe Lake 104,Reach-1         ,7423
     562     741     883     346    1044    3153    1457
Boundary for River Rch & Prof#=Conroe Lake 104,Reach-1         , 1
Up Type= 0
Dn Type= 3
Dn Slope=0.015
Boundary for River Rch & Prof#=Conroe Lake 104,Reach-1         , 2
Up Type= 0
Dn Type= 3
Dn Slope=0.015
Boundary for River Rch & Prof#=Conroe Lake 104,Reach-1         , 3
Up Type= 0
Dn Type= 3
Dn Slope=0.015
Boundary for River Rch & Prof#=Conroe Lake 104,Reach-1         , 4
Up Type= 0
Dn Type= 3
Dn Slope=0.015
Boundary for River Rch & Prof#=Conroe Lake 104,Reach-1         , 5
Up Type= 0
Dn Type= 3
Dn Slope=0.015
Boundary for River Rch & Prof#=Conroe Lake 104,Reach-1         , 6
Up Type= 0
Dn Type= 3
Dn Slope=0.015
Boundary for River Rch & Prof#=Conroe Lake 104,Reach-1         , 7
Up Type= 0
Dn Type= 3
Dn Slope=0.015
DSS Import GetInterval= 0
DSS Import GetPeak= 0
DSS Import FillOption= 0

--- Conroe Lake 104.g01 (geometry) ---

Geom Title=Existing Conditions
Program Version=4.10

River Reach=Conroe Lake 104 ,Reach-1
Reach XY= 30
      3747173.23     10159961.84      3747284.79     10159771.45
      3747489.63     10159753.71       3747663.5     10159528.53
      3748057.42     10159554.58      3748338.28     10159289.15
      3748612.24     10159282.56      3748623.13      10159124.3
      3748744.67     10158911.48      3749270.54     10158713.18
      3749813.61     10158351.05      3749909.04     10158208.46
      3750110.26     10158183.37      3750277.42      10157839.5
      3750529.82     10157763.67      3750671.65     10157617.88
      3751132.38     10157633.58      3751146.71     10157555.45
      3751302.96     10157420.04      3751513.89     10157356.24
      3751619.36     10157115.32      3751866.56     10156925.21
      3751937.93     10156653.87      3751810.65     10156424.06
      3751955.09     10156250.79      3752047.24     10156296.78
      3752286.59     10156265.18      3752624.57     10156054.15
      3752721.14     10156070.96      3753135.13     10155899.75

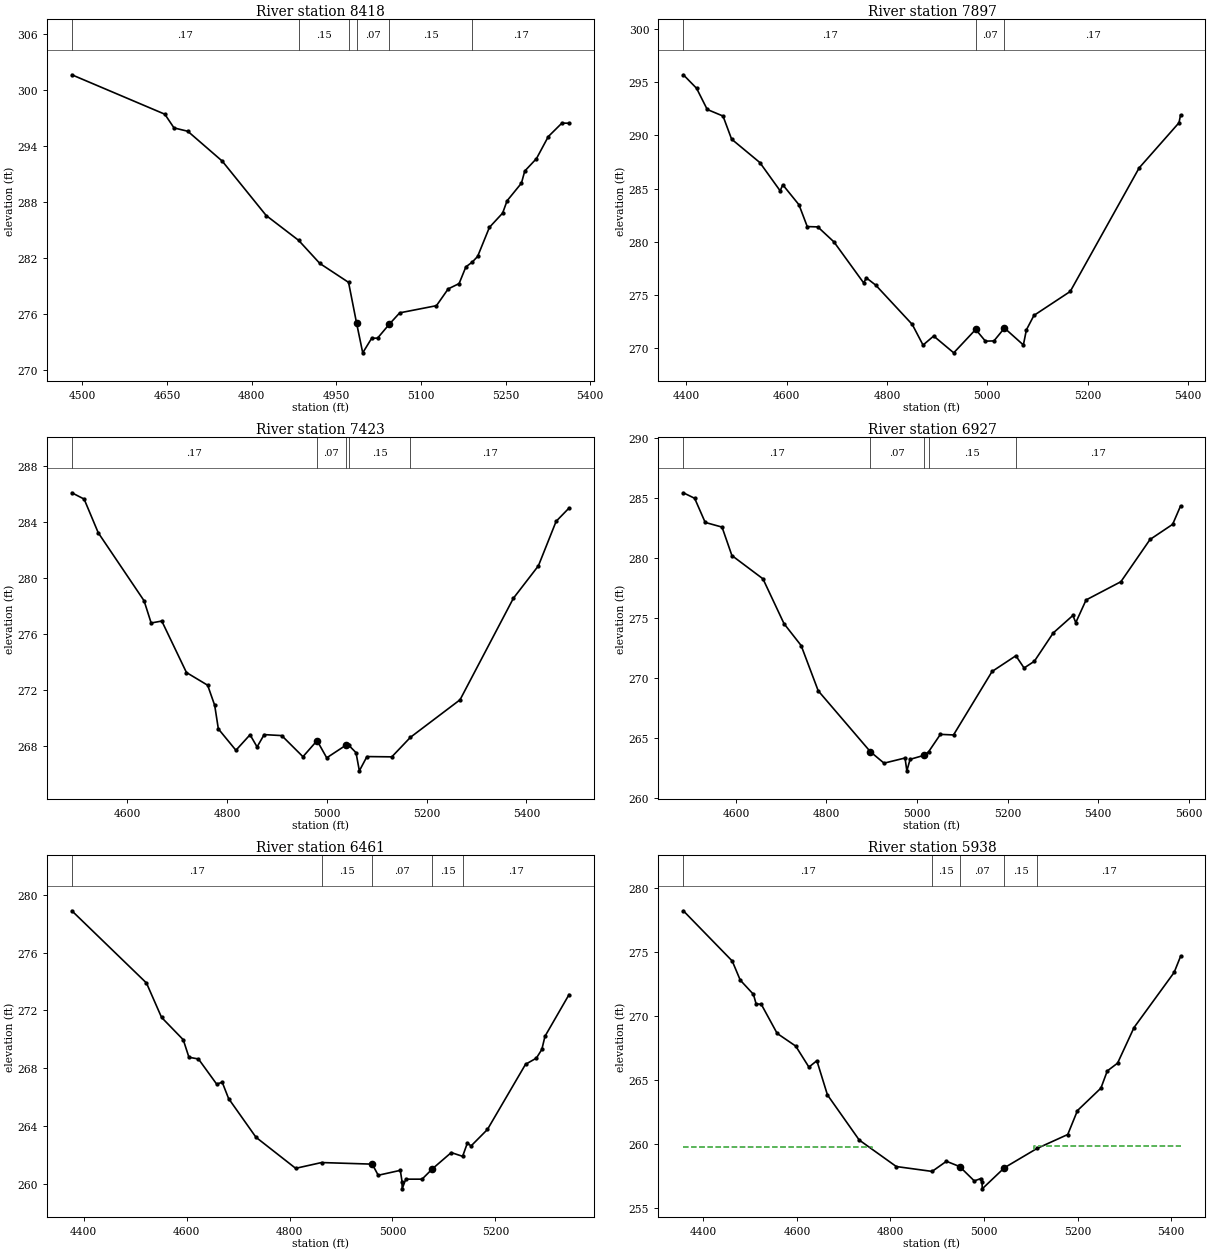
Type RM Length L Ch R = 1 ,8418    ,521,521,521
BEGIN DESCRIPTION:
Conroe Lake 104 16.0
END DESCRIPTION:
XS GIS Cut Line= 3
      3747496.15     10160292.98      3747401.28     10159783.34
      3747298.78     10159435.73
#Sta/Elev= 30
  4481.6  301.65  4646.3  297.42  4662.6  295.95    4687  295.59    4748  292.39
  4825.9  286.55  4883.5  283.88  4920.9  281.41  4971.8  279.38 4985.87  275.05
  4996.9  271.82  5012.8  273.39  5023.2   273.4  5044.1   274.9  5062.4  276.11
  5127.5  276.88  5148.3  278.68  5167.6  279.25  5179.6  281.04    5191  281.56
  5200.4  282.16  5221.3  285.28  5244.7  286.81  5252.6  288.13    5278  290.02
  5283.9  291.32  5304.7  292.66  5325.6  295.02  5349.8  296.47  5362.4  296.45
#Mann= 6 ,-1 , 0
  4481.6     .17       0  4883.5     .15       0  4971.8     .11       0
 4985.87     .07       0  5044.1     .15       0    5191     .17       0
Bank Sta=4985.87,5044.1
XS Rating Curve= 0 ,0
Exp/Cntr=0.3,0.1

Type RM Length L Ch R = 1 ,7897    ,474,474,474
BEGIN DESCRIPTION:
Conroe Lake 104 15.0
END DESCRIPTION:
XS GIS Cut Line= 4
      3747932.39     10160126.45        3747749.     10159549.07
      3747724.97     10159513.81      3747438.91     10159325.23
#Sta/Elev= 30
  4394.2   295.7  4420.6  294.43  4441.8  292.44  4473.3  291.82  4490.4  289.65
  4546.7  287.45  4587.2  284.79  4592.4  285.36  4624.7  283.48  4641.2  281.43
  4662.2   281.4  4694.4  279.99  4753.7  276.13  4758.9  276.61  4777.6  275.93
  4850.5  272.23    4872  270.29  4893.2  271.14  4933.2  269.56  4976.9  271.76
  4996.3  270.66  5013.3  270.68  5034.3  271.89    5072   270.3    5078  271.72
  5093.1  273.08  5165.4  275.33  5302.7  286.94  5382.2  291.19  5385.3  291.92
#Mann= 3 , 0 , 0
  4394.2     .17       0  4976.9     .07       0  5034.3     .17       0
Bank Sta=4976.9,5034.3
XS Rating Curve= 0 ,0
Exp/Cntr=0.3,0.1

Type RM Length L Ch R = 1 ,7423    ,496,496,496
BEGIN DESCRIPTION:
Conroe Lake 104 14.0
END DESCRIPTION:
XS GIS Cut Line= 3
      3748508.96     10159874.74      3748155.72     10159505.76
      3747867.36     10159115.42
#Sta/Elev= 30
  4489.2   286.1  4513.8  285.65  4542.1  283.24  4633.9  278.38  4648.1  276.79
  4669.4  276.93  4718.8  273.25  4761.3  272.34  4775.4   270.9  4782.7  269.22
  4817.9  267.69  4846.2   268.8  4860.3  267.93  4874.5  268.81  4909.7  268.74
  4952.2  267.23  4980.5  268.38  4999.8  267.15  5037.7  268.04  5043.9  268.05
  5058.5  267.52  5065.2  266.22  5080.4  267.24  5130.2  267.22  5167.6  268.62
  5266.9   271.3  5373.8  278.56  5423.9  280.88  5459.4  284.06  5485.3  285.01
#Mann= 5 ,-1 , 0
  4489.2     .17       0  4980.5     .07       0  5037.7     .11       0
  5043.9     .15       0  5167.6     .17       0
Bank Sta=4980.5,5037.7
XS Rating Curve= 0 ,0
Exp/Cntr=0.3,0.1

Type RM Length L Ch R = 1 ,6927    ,466,466,466
BEGIN DESCRIPTION:
Conroe Lake 104 13.0
END DESCRIPTION:
XS GIS Cut Line= 3
      3748732.75      10159759.3      3748524.66     10159286.91
      3748062.49     10158932.69
#Sta/Elev= 30
  4483.8  285.47  4508.8  285.01  4532.1     283  4569.3  282.61  4591.1  280.24
  4659.7   278.3  4706.3  274.56  4744.1  272.74  4781.8  268.97  4897.1  263.89
  4927.2  262.94  4973.6  263.37  4977.6   262.3  4984.8  263.26  5016.3   263.6
  5025.7  263.89  5051.7  265.34  5080.7  265.29  5165.9  270.58  5218.5  271.89
  5236.6  270.87  5259.3  271.43    5301  273.79  5344.5  275.25  5350.8  274.65
  5373.6  276.54  5450.5  278.06  5514.9  281.58  5564.8  282.84  5582.3  284.37
#Mann= 5 ,-1 , 0
  4483.8     .17       0  4897.1     .07       0  5016.3     .17       0
  5025.7     .15       0  5218.5     .17       0
Bank Sta=4897.1,5016.3
XS Rating Curve= 0 ,0
Exp/Cntr=0.3,0.1

Type RM Length L Ch R = 1 ,6461    ,523,523,523
BEGIN DESCRIPTION:
Conroe Lake 104 12.0
END DESCRIPTION:
XS GIS Cut Line= 3
      3748967.86      10159561.1      3748729.58     10158985.47
      3748617.85     10158661.07
#Sta/Elev= 30
    4377   278.9    4522   273.9  4551.3  271.52  4593.5  269.97  4604.5  268.76
    4623  268.64  4658.4   266.9  4669.2  267.03  4681.6   265.9  4734.8  263.22
  4811.9  261.07  4862.2  261.47  4960.7  261.36  4972.3  260.59  5015.2  260.93
  5018.6  260.15  5018.8  259.65  5025.9  260.32  5057.5  260.32  5077.7  261.04
  5114.2  262.16  5136.3   261.9  5145.5  262.82  5152.7  262.62  5184.5  263.76
  5258.5  268.27  5279.6   268.7  5290.2   269.3  5296.3  270.21  5343.1   273.1
#Mann= 5 ,-1 , 0
    4377     .17       0  4862.2     .15       0  4960.7     .07       0
  5077.7     .15       0  5136.3     .17       0
Bank Sta=4960.7,5077.7
XS Rating Curve= 0 ,0
Exp/Cntr=0.3,0.1

Type RM Length L Ch R = 1 ,5938    ,500,500,500
BEGIN DESCRIPTION:
Conroe Lake 104 11.0
END DESCRIPTION:
XS GIS Cut Line= 3
      3749417.86     10159361.09      3749138.63     10158782.21
      3748817.87     10158511.09
#Sta/Elev= 30
  4357.3  278.19  4461.8  274.27  4478.9  272.78  4507.1  271.67  4512.8  270.93
  4523.9  270.89  4557.8  268.62  4597.5  267.63  4625.7  265.99  4642.7  266.49
  4665.3  263.82  4733.2   260.3  4812.5  258.23    4889  257.85  4919.6  258.64
  4947.8  258.23  4979.1  257.11    4993  257.29  4995.9  256.99  4996.1  256.49
  5043.7  258.14  5113.1  259.64  5178.9  260.73  5199.7   262.6  5249.8  264.35
  5263.4  265.69  5285.4   266.3  5320.6  269.08  5406.3  273.38    5420  274.63
#Mann= 5 ,-1 , 0
  4357.3     .17       0    4889     .15       0  4947.8     .07       0
  5043.7     .15       0  5113.1     .17       0
#XS Ineff= 2 , 0
       0  4761.3  259.74  5107.4       0  259.85
Permanent Ineff=
       F       F
Bank Sta=4947.8,5043.7
XS Rating Curve= 0 ,0
Exp/Cntr=0.3,0.1

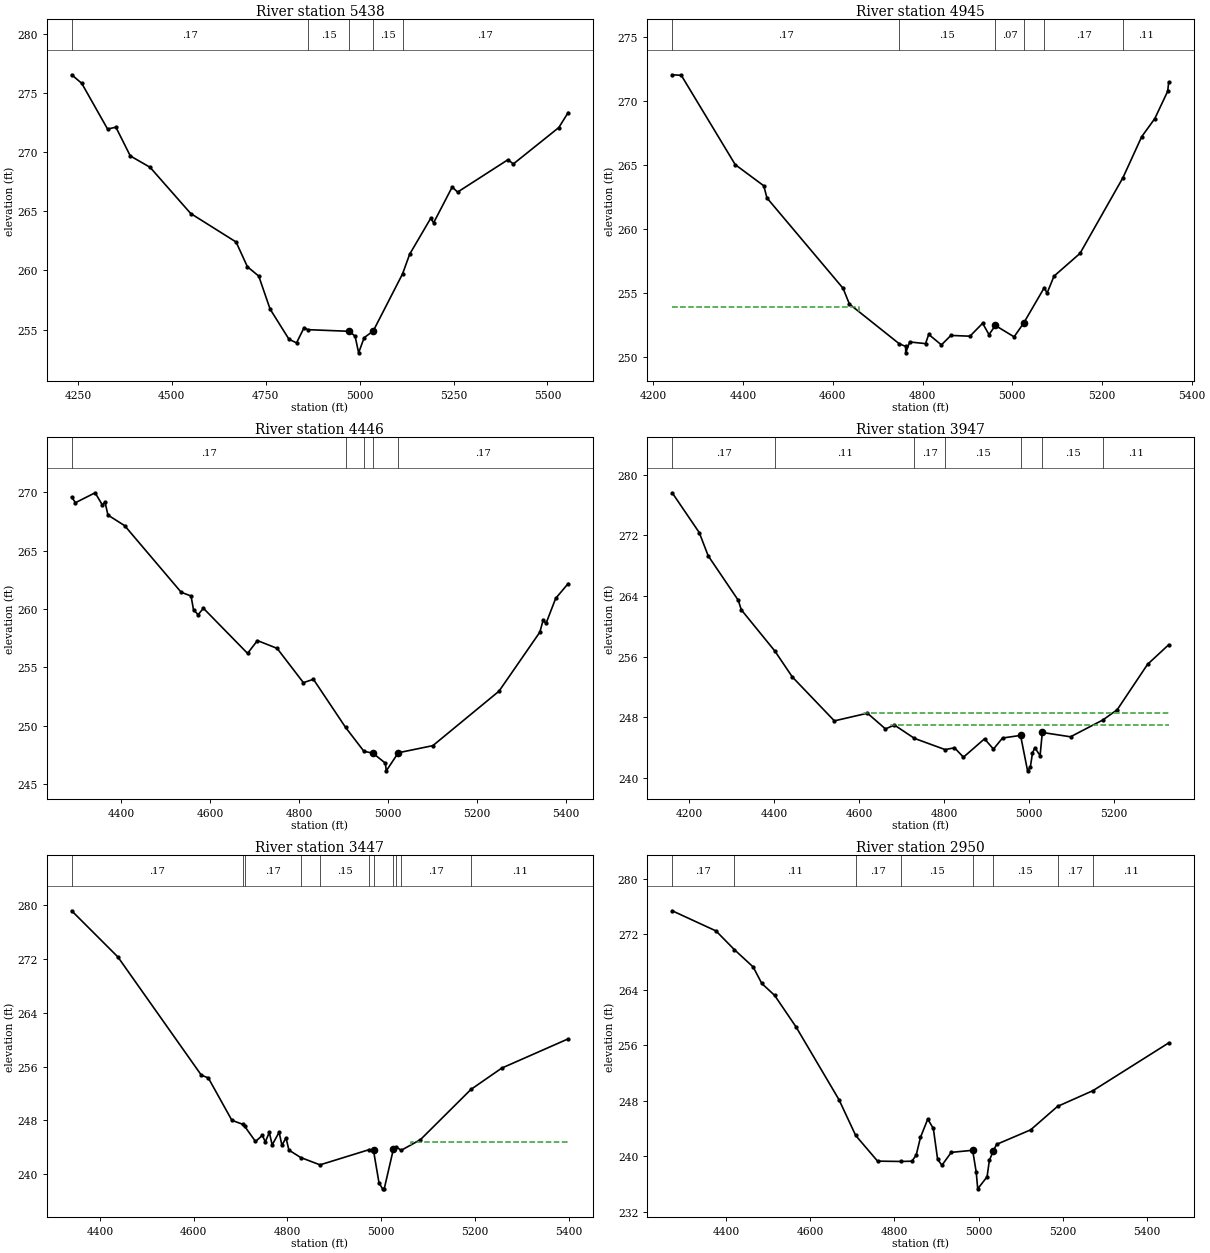
Type RM Length L Ch R = 1 ,5438    ,493,493,493
BEGIN DESCRIPTION:
Conroe Lake 104 10.0
END DESCRIPTION:
XS GIS Cut Line= 3
      3749625.38     10159296.11      3749541.52     10158534.01
        3749187.     10158106.87
#Sta/Elev= 30
  4233.3  276.54    4260  275.82  4328.9  271.95    4351  272.11  4389.3  269.68
  4441.9  268.72  4550.2  264.81    4671   262.4  4701.1  260.31  4731.3  259.52
  4761.5  256.73  4811.8  254.18  4831.9  253.87    4852  255.16  4861.7  254.99
  4972.8  254.85  4987.9  254.43  4997.2  253.03  5011.9  254.31 5036.15  254.88
  5114.2  259.71  5133.1  261.37    5189   264.4  5196.9  264.03  5246.3  267.05
  5260.7  266.62  5394.8  269.36  5409.1     269  5530.2  272.08  5555.1  273.35
#Mann= 5 ,-1 , 0
  4233.3     .17       0  4861.7     .15       0  4972.8     .07       0
 5036.15     .15       0  5114.2     .17       0
Bank Sta=4972.8,5036.15
XS Rating Curve= 0 ,0
Exp/Cntr=0.3,0.1

Type RM Length L Ch R = 1 ,4945    ,499,499,499
BEGIN DESCRIPTION:
Conroe Lake 104 9.0
END DESCRIPTION:
XS GIS Cut Line= 3
      3750410.97      10158766.6      3749873.38     10158232.08
      3749691.34     10157934.67
#Sta/Elev= 30
  4241.9  272.05  4262.1  272.01  4382.4  265.03    4446  263.38  4453.1  262.43
  4622.8  255.37  4636.9  254.14  4747.6  251.05  4762.2  250.83  4762.5  250.33
  4771.3  251.18  4806.6  251.05  4813.7  251.77    4842  250.95  4863.2  251.69
  4905.6  251.63  4933.9  252.64  4948.1  251.75  4962.2  252.47    5004  251.58
  5025.3  252.65  5071.3  255.42  5077.5  254.99    5093  256.32    5151   258.1
  5246.8  264.02  5288.4  267.21  5317.7  268.63  5346.4  270.76  5348.7  271.49
#Mann= 6 ,-1 , 0
  4241.9     .17       0  4747.6     .15       0  4962.2     .07       0
  5025.3     .15       0  5071.3     .17       0  5246.8     .11       0
#XS Ineff= 2 , 0
       0  4658.1  253.89               0
Permanent Ineff=
       F       F
Bank Sta=4962.2,5025.3
XS Rating Curve= 0 ,0
Exp/Cntr=0.3,0.1

Type RM Length L Ch R = 1 ,4446    ,499,499,499
BEGIN DESCRIPTION:
Conroe Lake 104 8.0
END DESCRIPTION:
XS GIS Cut Line= 3
      3750536.85      10158623.4      3750209.26     10157992.14
      3749917.83     10157711.05
#Sta/Elev= 30
  4288.8  269.59  4297.3  269.11  4341.5  269.96    4358   268.9  4363.6  269.19
  4370.3  268.05  4407.9  267.14    4535  261.43  4557.1  261.11  4562.7  259.92
  4573.1  259.51  4584.9  260.06  4684.2  256.19  4706.3  257.29  4750.6  256.62
  4809.7  253.68  4832.2  253.97  4904.4  249.85  4945.6   247.8  4966.1  247.63
  4993.9  246.78    4996  246.12    5023  247.67  5100.7  248.28  5249.4  252.95
  5341.2  258.01  5348.4  259.01  5355.3  258.78  5376.7   260.9  5404.9  262.18
#Mann= 5 ,-1 , 0
  4288.8     .17       0  4904.4     .15       0  4945.6     .17       0
  4966.1     .07       0    5023     .17       0
Bank Sta=4966.1,5023
XS Rating Curve= 0 ,0
Exp/Cntr=0.3,0.1

Type RM Length L Ch R = 1 ,3947    ,500,500,500
BEGIN DESCRIPTION:
Conroe Lake 104 7.0
END DESCRIPTION:
XS GIS Cut Line= 4
      3751167.88      10158311.1      3750566.88     10157724.38
      3750556.62     10157709.54      3750467.86      10157411.1
#Sta/Elev= 30
  4160.1  277.62  4223.8  272.37  4244.9   269.3  4315.6  263.45  4322.8  262.19
    4402  256.74    4443  253.33    4542  247.54  4619.9  248.55  4662.3  246.48
  4683.4  246.99  4730.6  245.23  4802.9  243.75  4824.9  243.99    4846  242.75
  4895.6  245.17  4916.7  243.82    4938  245.28  4980.5  245.62    4997  240.95
  5003.5  241.45  5008.6  243.29  5014.1     244  5026.5  242.96  5031.7  246.01
  5098.1  245.44  5174.4  247.66  5208.1  249.01  5279.6     255  5329.4  257.58
#Mann= 7 ,-1 , 0
  4160.1     .17       0    4402     .11       0  4730.6     .17       0
  4802.9     .15       0  4980.5     .07       0  5031.7     .15       0
  5174.4     .11       0
#XS Ineff= 3 ,-1
  4612.7  4527.8  248.58  4676.4  4619.9  247.04  5131.2  5141.7  246.28
Permanent Ineff=
       F       F       F
Bank Sta=4980.5,5031.7
XS Rating Curve= 0 ,0
Exp/Cntr=0.3,0.1

Type RM Length L Ch R = 1 ,3447    ,497,497,497
BEGIN DESCRIPTION:
Conroe Lake 104 6.0
END DESCRIPTION:
XS GIS Cut Line= 3
      3751370.18     10158176.33      3750986.37     10157638.67
      3750775.54     10157299.56
#Sta/Elev= 30
  4339.4  279.12    4438  272.27  4616.2  254.72    4631  254.32  4681.4  248.02
  4704.1  247.44  4708.4  247.16  4731.8  244.88  4746.5  245.79  4752.7  244.82
  4761.3  246.22  4767.4  244.37  4782.2  246.25  4788.3   244.3  4796.9  245.43
  4803.1   243.6  4828.3   242.5  4869.5  241.41  4975.1  243.68  4983.7  243.55
  4995.5  238.72  5003.1  237.85  5006.6  237.85  5026.1  243.72  5032.5  244.08
  5042.6  243.56  5083.9  245.15  5191.8  252.61  5257.5  255.77  5399.3  260.11
#Mann= 11 ,-1 , 0
  4339.4     .17       0  4704.1     .11       0  4708.4     .17       0
  4828.3     .11       0  4869.5     .15       0  4975.1     .12       0
  4983.7     .09       0  5026.1     .12       0  5032.5     .15       0
  5042.6     .17       0  5191.8     .11       0
#XS Ineff= 2 , 0
       0  4796.9  245.43  5062.7       0  244.82
Permanent Ineff=
       F       F
Bank Sta=4983.7,5026.1
XS Rating Curve= 0 ,0
Exp/Cntr=0.3,0.1

Type RM Length L Ch R = 1 ,2950    ,463,463,463
BEGIN DESCRIPTION:
Conroe Lake 104 5.0
END DESCRIPTION:
XS GIS Cut Line= 3
      3751483.03     10158119.92      3751339.41     10157405.72
      3750932.29     10157208.68
#Sta/Elev= 30
  4271.5  275.36  4375.6  272.46  4419.1  269.78  4464.1  267.27  4484.5   264.9
  4515.1  263.18  4566.1  258.63  4668.1  248.17  4707.9  243.01  4759.9  239.32
  4814.9  239.27  4841.5  239.31  4851.7  240.18  4861.9  242.73  4879.2  245.37
  4892.5  244.02  4902.7  239.59  4912.9  238.72  4935.1  240.58    4986  240.88
  4994.5  237.73  4998.1  235.33  5020.3  237.06  5025.8  239.43  5035.1  240.78
  5042.9  241.73  5123.9  243.82  5187.9   247.2    5272  249.46  5452.3  256.34
#Mann= 8 ,-1 , 0
  4271.5     .17       0  4419.1     .11       0  4707.9     .17       0
  4814.9     .15       0    4986     .07       0  5035.1     .15       0
  5187.9     .17       0    5272     .11       0
#XS Ineff= 2 , 0
       0  4879.2  245.37               0
Permanent Ineff=
       F       F
Bank Sta=4986,5035.1
XS Rating Curve= 0 ,0
Exp/Cntr=0.3,0.1

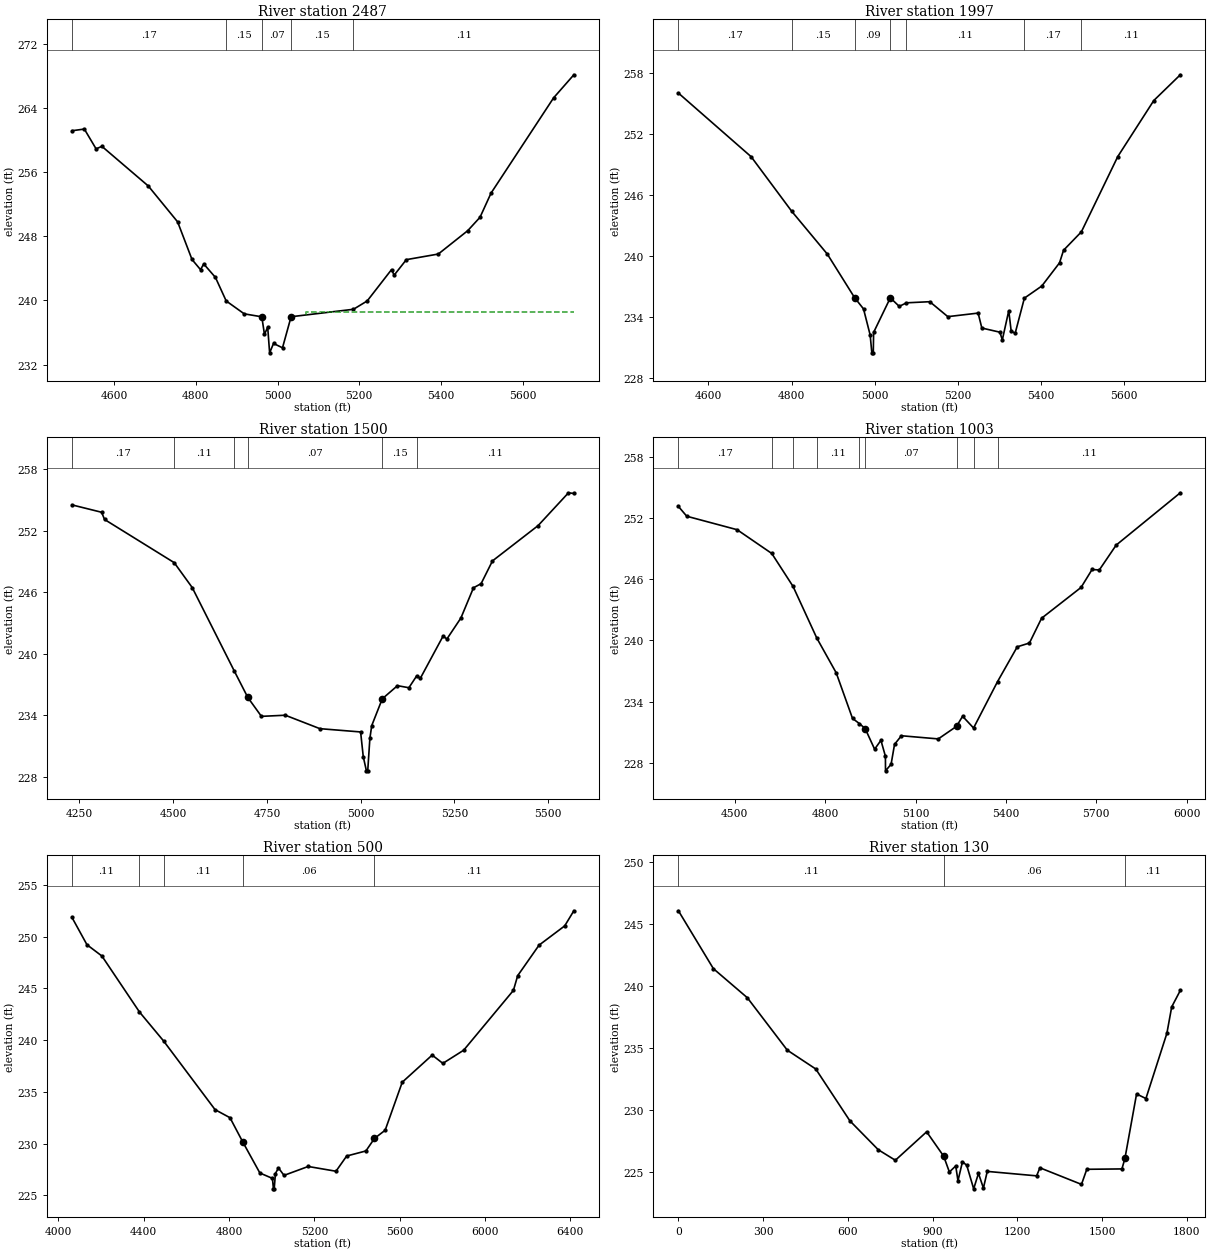
Type RM Length L Ch R = 1 ,2487    ,490,490,490
BEGIN DESCRIPTION:
Conroe Lake 104 4.0
END DESCRIPTION:
XS GIS Cut Line= 3
      3751938.72     10157503.55      3751619.36     10157115.32
      3751017.88     10156711.09
#Sta/Elev= 30
  4497.3   261.2  4527.6  261.41  4556.3  258.94  4570.6  259.25    4684   254.3
  4755.7  249.82  4790.9  245.12  4811.7  243.85  4819.6  244.56  4848.2  242.88
  4874.5  239.94  4918.6  238.33  4961.6  237.96  4968.1  235.76    4976  236.67
  4980.7  233.46  4990.3  234.63  5012.2  234.09  5033.2  237.97  5185.7   238.9
  5219.3  239.94  5278.9  243.86  5285.2  243.16  5315.1   245.1  5393.2   245.8
  5465.2  248.72  5495.2  250.39  5522.2  253.41  5675.2  265.31  5724.7  268.19
#Mann= 5 ,-1 , 0
  4497.3     .17       0  4874.5     .15       0  4961.6     .07       0
  5033.2     .15       0  5185.7     .11       0
#XS Ineff= 2 , 0
       0                  5069.2       0  238.62
Permanent Ineff=
       F       F
Bank Sta=4961.6,5033.2
XS Rating Curve= 0 ,0
Exp/Cntr=0.3,0.1

Type RM Length L Ch R = 1 ,1997    ,497,497,497
BEGIN DESCRIPTION:
Conroe Lake 104 3.0
END DESCRIPTION:
XS GIS Cut Line= 3
      3752320.65     10157004.43      3751908.61     10156773.59
      3751279.07      10156392.5
#Sta/Elev= 30
  4527.7  255.98  4702.8  249.72  4800.5  244.35  4886.2  240.14  4951.6  235.87
  4973.3  234.75  4989.3  232.18  4993.3  230.43  4996.8  230.43  4997.6  232.44
  5037.8  235.84  5059.3     235  5076.7  235.35  5132.8  235.46  5176.2  233.99
  5249.2  234.34  5258.1  232.87  5301.6  232.46  5307.4   231.7  5322.9  234.57
  5328.8  232.55  5338.4  232.36  5360.5  235.81  5402.4     237  5445.1  239.28
  5454.8  240.52  5497.7  242.33  5585.4  249.74  5672.1  255.25  5735.9  257.78
#Mann= 7 ,-1 , 0
  4527.7     .17       0  4800.5     .15       0  4951.6     .09       0
  5037.8     .15       0  5076.7     .11       0  5360.5     .17       0
  5497.7     .11       0
Bank Sta=4951.6,5037.8
XS Rating Curve= 0 ,0
Exp/Cntr=0.3,0.1

Type RM Length L Ch R = 1 ,1500    ,497,497,497
BEGIN DESCRIPTION:
Conroe Lake 104 2.0
END DESCRIPTION:
XS GIS Cut Line= 3
      3752372.77     10156948.02      3751874.86     10156360.54
      3751313.77     10156266.61
#Sta/Elev= 30
  4229.9   254.5  4309.1  253.78  4316.8  253.08  4502.7  248.87  4550.8  246.44
  4663.4  238.28  4699.1  235.73  4735.4  233.89  4799.1     234  4891.4  232.69
    5000  232.37  5007.1  229.95  5015.5  228.58    5019  228.58  5024.7  231.74
  5029.7  232.99  5057.8   235.6  5098.4  236.88  5128.8  236.68  5149.9  237.85
  5159.2  237.59    5220  241.71  5230.2  241.43  5267.5  243.47  5301.1  246.42
  5321.4  246.82  5351.8  249.04  5473.5  252.48  5554.6  255.68  5568.9  255.61
#Mann= 6 ,-1 , 0
  4229.9     .17       0  4502.7     .11       0  4663.4     .15       0
  4699.1     .07       0  5057.8     .15       0  5149.9     .11       0
Bank Sta=4699.1,5057.8
XS Rating Curve= 0 ,0
Exp/Cntr=0.3,0.1

Type RM Length L Ch R = 1 ,1003    ,503,503,503
BEGIN DESCRIPTION:
Conroe Lake 104 1.0
END DESCRIPTION:
XS GIS Cut Line= 4
       3752481.3     10156922.03      3752274.86     10156266.88
      3752203.08     10156232.85      3751311.13     10156119.25
#Sta/Elev= 30
  4313.1  253.14  4340.8  252.18  4507.8  250.86  4622.9  248.53  4693.5   245.3
  4772.4  240.23  4836.7  236.83  4890.8  232.36  4913.3  231.86  4932.7  231.37
  4964.2  229.34  4985.1  230.21    5000  228.65  5000.3  227.22  5018.8  227.86
  5030.3  229.82  5053.1  230.66  5175.4  230.35  5235.9  231.58  5256.1  232.57
  5292.5  231.42  5372.1  235.97  5437.5  239.38  5477.9  239.75  5518.2  242.18
  5649.2   245.2  5685.8  246.96  5709.7  246.91  5765.7  249.35  5978.6  254.48
#Mann= 9 ,-1 , 0
  4313.1     .17       0  4622.9     .11       0  4693.5     .17       0
  4772.4     .11       0  4913.3     .15       0  4932.7     .07       0
  5235.9     .11       0  5292.5     .15       0  5372.1     .11       0
#XS Ineff= 2 , 0
       0                  5256.1       0  232.57
Permanent Ineff=
       F       F
Bank Sta=4932.7,5235.9
XS Rating Curve= 0 ,0
Exp/Cntr=0.3,0.1

Type RM Length L Ch R = 1 ,500     ,370,370,370
BEGIN DESCRIPTION:
Conroe Lake 104 1.5
END DESCRIPTION:
XS GIS Cut Line= 4
      3752663.58      10156991.4      3752697.64     10156055.92
       3752656.2     10156008.89      3751305.07     10155923.72
#Sta/Elev= 30
  4063.9  251.85  4134.3  249.21  4204.3  248.12  4380.5  242.71  4493.6  239.91
  4734.7  233.28  4804.7   232.5    4864  230.18  4944.8  227.16  5003.6  226.64
  5008.4  225.63  5011.9  225.63  5017.7  227.11    5032  227.65  5057.9  226.93
  5171.2  227.79  5301.5  227.33  5351.6   228.8  5441.8  229.29  5481.9   230.5
    5532  231.29  5612.1  235.93  5752.4  238.55  5802.5  237.75    5900  239.02
  6133.2   244.8  6153.2  246.22  6253.4  249.17  6373.6  251.03  6416.5  252.49
#Mann= 5 ,-1 , 0
  4063.9     .11       0  4380.5     .11       0  4493.6     .11       0
    4864     .06       0  5481.9     .11       0
Bank Sta=4864,5481.9
XS Rating Curve= 0 ,0
Exp/Cntr=0.3,0.1

Type RM Length L Ch R = 1 ,130     ,0,0,0
XS GIS Cut Line= 3
       3752914.5     10156924.08      3753026.51     10155948.72
      3753235.76     10155181.63
#Sta/Elev= 30
       0  246.09   123.8  241.41     244  239.06   385.5  234.82   486.2   233.3
     607  229.11   707.6  226.77     768  225.92   878.8  228.22   939.1  226.25
   959.3  224.97   981.8  225.46   989.7  224.26  1005.6   225.8  1020.8  225.51
  1045.3  223.61  1062.3  224.86  1079.8  223.67  1093.4  225.02  1268.1  224.66
  1279.9  225.31    1427  223.97  1445.8  225.19  1570.2  225.22  1580.8  226.07
    1622  231.28  1655.1  230.91  1729.3  236.18  1746.4  238.32  1776.9  239.65
#Mann= 3 , 0 , 0
       0     .11       0   939.1     .06       0  1580.8     .11       0
Bank Sta=939.1,1580.8
XS Rating Curve= 0 ,0
Exp/Cntr=0.3,0.1

Chan Stop Cuts=-1
Use User Specified Reach Order=0
Composite Channel Slope=5