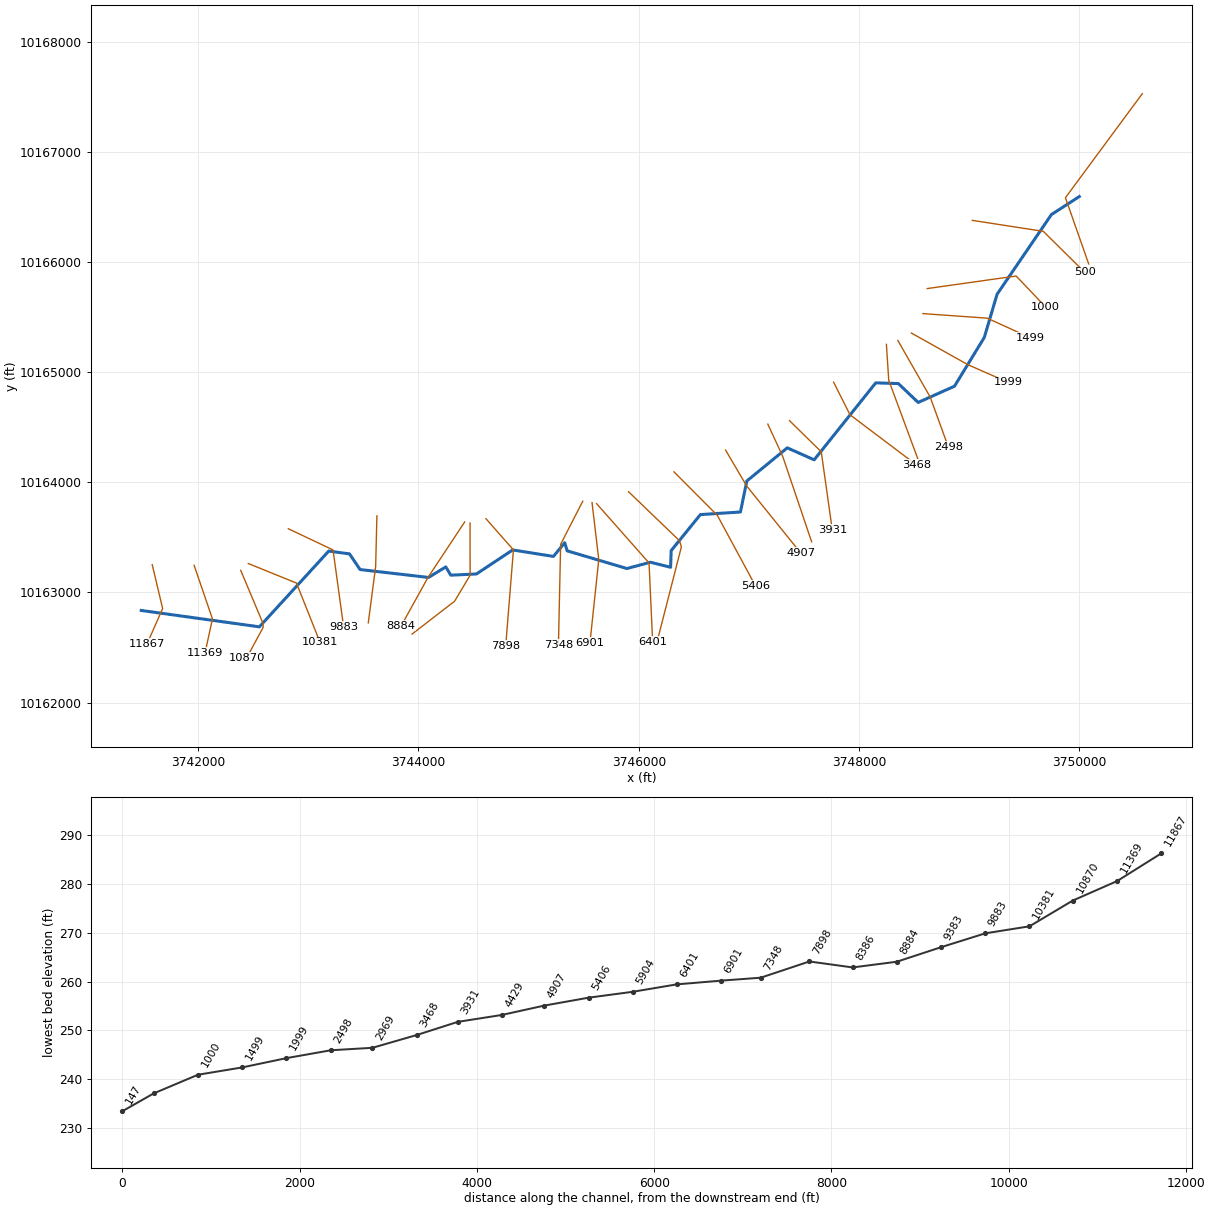
--- Conroe Lake 107.prj (project) ---

Proj Title=Conroe Lake 107 Base Level Engineering
Current Plan=p01
Default Exp/Contr=0.3,0.1
English Units
Geom File=g01
Flow File=f01
Flow File=f02
Plan File=p01
Y Axis Title=Elevation
X Axis Title(PF)=Main Channel Distance
X Axis Title(XS)=Station
BEGIN DESCRIPTION:
Conroe Lake 107
END DESCRIPTION:
DSS Export Rating Curves= 0
DSS Export Rating Curve Sorted= 0
DSS Export Volume Flow Curves= 0
DXF OffsetX= 0
DXF OffsetY= 0
DXF ScaleX= 1
DXF ScaleY= 10

--- Conroe Lake 107.p01 (plan) ---

Plan Title=Multiple Run
Short Identifier=Multiple
Geom File=g01
Flow File=f01
Subcritical Flow
K Sum by GR= 0
Std Step Tol= 0.01
Critical Tol= 0.01
Num of Std Step Trials= 20
Max Error Tol= 0.3
Flow Tol Ratio= 0.001
Split Flow NTrial= 30
Split Flow Tol= 0.02
Split Flow Ratio= 0.02
Log Output Level= 0
Friction Slope Method= 1
Unsteady Friction Slope Method= 2
Unsteady Bridges Friction Slope Method= 1
Parabolic Critical Depth
Global Vel Dist=  1 , 1 , 1
Global Log Level= 0
CheckData=True
Encroach Param= -1, 0, 0, 0
BEGIN DESCRIPTION:
Multiple Run
END DESCRIPTION:

--- Conroe Lake 107.f01 (steady flow) ---

Flow Title=Multiple
Program Version=4.10
Number of Profiles= 7
Profile Names=10-year,25-year,50-year,1pct_min,100-year,1pct_plu,500-year
River Rch & RM=Conroe Lake 107,Reach-1         ,11867
     324     425     565     248     750    2265    1359
River Rch & RM=Conroe Lake 107,Reach-1         ,10870
     682     925    1252     558    1684    5086    3144
River Rch & RM=Conroe Lake 107,Reach-1         ,3931
     694     938    1266     562    1697    5125    3149
River Rch & RM=Conroe Lake 107,Reach-1         ,147
    2340    3339    4671    2138    6456   19497   12766
Boundary for River Rch & Prof#=Conroe Lake 107,Reach-1         , 1
Up Type= 0
Dn Type= 3
Dn Slope=0.007
Boundary for River Rch & Prof#=Conroe Lake 107,Reach-1         , 2
Up Type= 0
Dn Type= 3
Dn Slope=0.007
Boundary for River Rch & Prof#=Conroe Lake 107,Reach-1         , 3
Up Type= 0
Dn Type= 3
Dn Slope=0.007
Boundary for River Rch & Prof#=Conroe Lake 107,Reach-1         , 4
Up Type= 0
Dn Type= 3
Dn Slope=0.007
Boundary for River Rch & Prof#=Conroe Lake 107,Reach-1         , 5
Up Type= 0
Dn Type= 3
Dn Slope=0.007
Boundary for River Rch & Prof#=Conroe Lake 107,Reach-1         , 6
Up Type= 0
Dn Type= 3
Dn Slope=0.007
Boundary for River Rch & Prof#=Conroe Lake 107,Reach-1         , 7
Up Type= 0
Dn Type= 3
Dn Slope=0.007
DSS Import GetInterval= 0
DSS Import GetPeak= 0
DSS Import FillOption= 0

--- Conroe Lake 107.f02 (steady flow) ---

Flow Title=Orig_BLE_Flow
Program Version=4.10
Number of Profiles= 7
Profile Names=10-year,25-year,50-year,1pct_min,100-year,1pct_plu,500-year
River Rch & RM=Conroe Lake 107,Reach-1         ,11867
     324     417     491     191     577    1742     790
River Rch & RM=Conroe Lake 107,Reach-1         ,10870
     682     907    1089     429    1295    3911    1828
River Rch & RM=Conroe Lake 107,Reach-1         ,3931
     694     920    1101     432    1305    3942    1831
Boundary for River Rch & Prof#=Conroe Lake 107,Reach-1         , 1
Up Type= 0
Dn Type= 3
Dn Slope=0.007
Boundary for River Rch & Prof#=Conroe Lake 107,Reach-1         , 2
Up Type= 0
Dn Type= 3
Dn Slope=0.007
Boundary for River Rch & Prof#=Conroe Lake 107,Reach-1         , 3
Up Type= 0
Dn Type= 3
Dn Slope=0.007
Boundary for River Rch & Prof#=Conroe Lake 107,Reach-1         , 4
Up Type= 0
Dn Type= 3
Dn Slope=0.007
Boundary for River Rch & Prof#=Conroe Lake 107,Reach-1         , 5
Up Type= 0
Dn Type= 3
Dn Slope=0.007
Boundary for River Rch & Prof#=Conroe Lake 107,Reach-1         , 6
Up Type= 0
Dn Type= 3
Dn Slope=0.007
Boundary for River Rch & Prof#=Conroe Lake 107,Reach-1         , 7
Up Type= 0
Dn Type= 3
Dn Slope=0.007
DSS Import GetInterval= 0
DSS Import GetPeak= 0
DSS Import FillOption= 0

--- Conroe Lake 107.g01 (geometry) ---

Geom Title=Existing Conditions
Program Version=4.10

River Reach=Conroe Lake 107 ,Reach-1
Reach XY= 30
      3741483.23     10162836.84      3742555.72     10162688.01
      3743185.37      10163376.5      3743373.63     10163350.85
      3743469.76     10163208.53      3744090.97     10163136.65
       3744247.8     10163232.61      3744293.16     10163157.23
      3744525.71     10163168.33      3744855.31      10163386.6
      3745224.95     10163327.82      3745327.37     10163452.65
      3745349.57     10163378.37      3745892.44     10163217.69
      3746104.53     10163274.88      3746288.42     10163229.14
      3746293.47     10163380.74      3746559.01     10163707.93
       3746922.3     10163731.32      3746980.43     10164013.01
      3747347.42     10164314.14      3747591.66     10164205.32
      3748150.47     10164904.47      3748355.53     10164898.26
      3748535.48      10164726.5      3748865.33     10164874.12
      3749135.81      10165316.9      3749251.74     10165709.28
      3749745.52     10166433.84      3749998.23     10166596.84

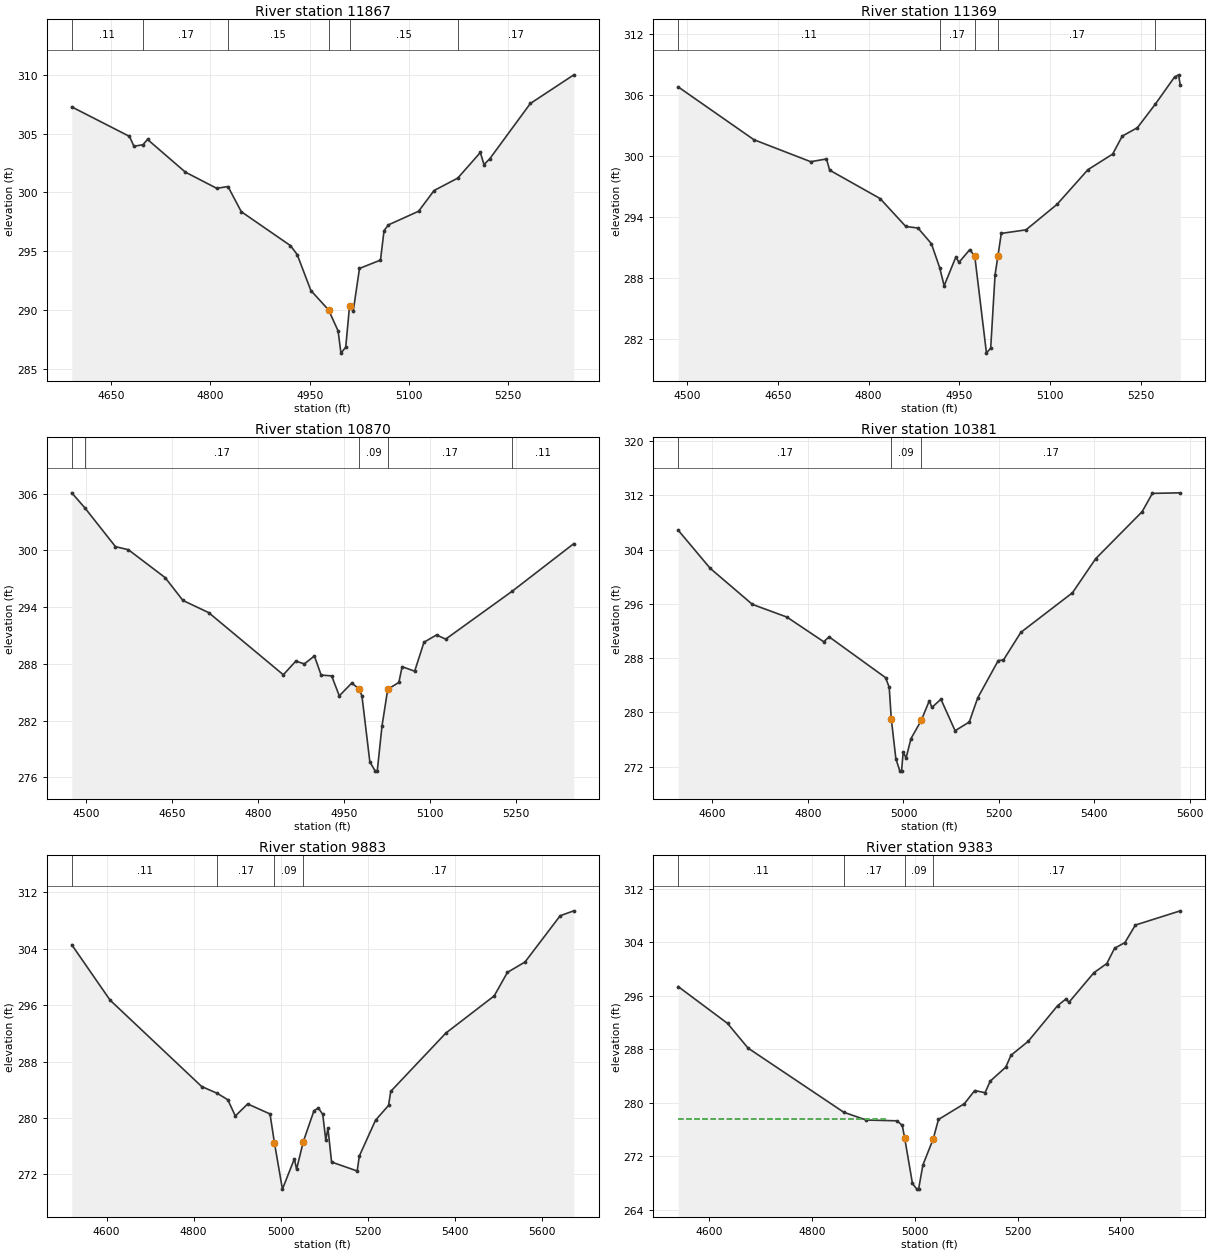
Type RM Length L Ch R = 1 ,11867   ,498,498,498
BEGIN DESCRIPTION:
Conroe Lake 107 24.0
END DESCRIPTION:
XS GIS Cut Line= 3
      3741583.14     10163252.41      3741677.58     10162854.26
      3741536.79     10162534.92
#Sta/Elev= 30
  4590.8  307.28  4677.9  304.77  4684.7  303.93  4698.3  304.06  4705.2  304.51
  4762.3  301.73  4809.7  300.35  4826.7   300.5  4846.8  298.36  4921.1  295.47
  4931.2  294.71  4951.9  291.65  4978.6     290    4993  288.21  4997.3  286.32
  5004.5  286.82  5010.3  290.34  5015.8  289.89  5025.3  293.53    5057  294.24
  5062.4  296.75  5069.1  297.24  5114.6   298.4  5137.9  300.16  5173.7  301.22
  5207.8   303.4  5213.3  302.37  5222.1  302.87  5283.3  307.57    5349  310.01
#Mann= 6 ,-1 , 0
  4590.8     .11       0  4698.3     .17       0  4826.7     .15       0
  4978.6     .09       0  5010.3     .15       0  5173.7     .17       0
Bank Sta=4978.6,5010.3
XS Rating Curve= 0 ,0
Exp/Cntr=0.3,0.1

Type RM Length L Ch R = 1 ,11369   ,499,499,499
BEGIN DESCRIPTION:
Conroe Lake 107 23.0
END DESCRIPTION:
XS GIS Cut Line= 3
      3741963.33     10163247.26      3742129.69     10162760.19
      3742062.58      10162451.7
#Sta/Elev= 30
  4485.3  306.81  4610.5  301.62  4704.4  299.46  4730.5  299.73  4735.7  298.63
  4819.1  295.84  4861.7  293.09  4881.8  292.94    4904   291.4  4917.7  289.04
  4925.1  287.26  4944.4  290.08  4949.7  289.57  4967.4  290.81  4975.7  290.19
  4995.1  280.64  5002.1  281.14  5009.3  288.33 5014.07   290.2  5019.6  292.41
  5060.5  292.76  5111.7  295.26  5162.8  298.67  5203.8  300.21  5219.7  301.98
  5244.7   302.8  5274.5  305.13  5306.1  307.78  5312.8     308  5315.7  306.97
#Mann= 5 ,-1 , 0
  4485.3     .11       0  4917.7     .17       0  4975.7     .09       0
 5014.07     .17       0  5274.5     .11       0
#XS Ineff= 2 , 0
       0  4967.4  290.81               0
Permanent Ineff=
       F       F
Bank Sta=4975.7,5014.07
XS Rating Curve= 0 ,0
Exp/Cntr=0.3,0.1

Type RM Length L Ch R = 1 ,10870   ,489,489,489
BEGIN DESCRIPTION:
Conroe Lake 107 22.0
END DESCRIPTION:
XS GIS Cut Line= 4
      3742386.31      10163201.3      3742589.24     10162717.75
      3742589.75     10162682.68      3742439.62     10162404.37
#Sta/Elev= 30
  4475.6  306.08  4498.7  304.47  4551.8  300.39  4574.4  300.06  4638.5  297.11
  4669.5   294.7  4714.4  293.41  4844.6  286.84  4866.3  288.28  4881.3  287.99
  4898.8  288.83  4910.5  286.81  4928.9  286.72  4942.2  284.61  4963.9  285.96
 4977.36  285.32  4981.8  284.56  4995.5  277.63  5004.9  276.65  5008.4  276.65
  5016.7  281.42  5026.7  285.31  5046.1  286.03  5051.8  287.69  5073.7  287.22
  5089.9  290.28  5111.8  291.05  5127.8  290.61  5244.3   295.7  5351.3  300.71
#Mann= 5 ,-1 , 0
  4475.6     .11       0  4498.7     .17       0 4977.36     .09       0
  5026.7     .17       0  5244.3     .11       0
#XS Ineff= 2 , 0
       0  4963.9  285.96               0
Permanent Ineff=
       F       F
Bank Sta=4977.36,5026.7
XS Rating Curve= 0 ,0
Exp/Cntr=0.3,0.1

Type RM Length L Ch R = 1 ,10381   ,498,498,498
BEGIN DESCRIPTION:
Conroe Lake 107 21.0
END DESCRIPTION:
XS GIS Cut Line= 3
      3742455.48     10163263.03      3742892.59     10163085.72
      3743106.41     10162546.68
#Sta/Elev= 30
  4528.3  306.84  4595.1  301.24  4683.6  295.92  4755.9  294.05    4833  290.42
  4844.3  291.14  4962.5  285.13  4970.2  283.72 4974.49   279.1  4984.1  273.19
  4992.5  271.36    4996  271.36  4999.5  274.18  5005.5  273.29  5015.8  276.15
  5037.3  278.83  5054.2  281.73  5059.6  280.74  5078.5  281.95  5108.2  277.31
  5137.9   278.6  5155.6  282.16  5198.6  287.65  5209.4  287.72  5245.9   291.8
    5354  297.63  5402.6  302.65  5499.9  309.57  5521.4  312.27  5579.9  312.35
#Mann= 3 , 0 , 0
  4528.3     .17       0 4974.49     .09       0  5037.3     .17       0
#XS Ineff= 2 , 0
       0                  5054.2       0  281.73
Permanent Ineff=
       F       F
Bank Sta=4974.49,5037.3
XS Rating Curve= 0 ,0
Exp/Cntr=0.3,0.1

Type RM Length L Ch R = 1 ,9883    ,500,500,500
BEGIN DESCRIPTION:
Mapping XS 67911ad9
END DESCRIPTION:
XS GIS Cut Line= 3
      3742818.38     10163579.11      3743224.39     10163386.85
      3743320.08     10162690.01
#Sta/Elev= 30
  4520.2  304.54  4608.1   296.7  4818.4  284.46  4854.2  283.49  4878.5  282.58
  4895.7  280.28    4924  281.99  4975.3  280.57  4985.4   276.5  5003.8  269.92
  5031.2  274.21  5036.3  272.74 5051.63  276.63  5076.2  281.03  5086.3  281.42
  5096.4   280.5  5103.3  276.88  5108.3  278.56  5116.6  273.76  5175.4  272.49
  5180.4  274.62  5217.5  279.68  5247.4  281.78  5252.5  283.77    5379  292.03
    5490   297.3  5520.3  300.63  5560.7   302.1  5641.5  308.66  5672.8  309.35
#Mann= 4 ,-1 , 0
  4520.2     .11       0  4854.2     .17       0  4985.4     .09       0
 5051.63     .17       0
#XS Ineff= 2 , 0
       0    4924  281.99  5086.3       0  281.42
Permanent Ineff=
       F       F
Bank Sta=4985.4,5051.63
XS Rating Curve= 0 ,0
Exp/Cntr=0.3,0.1

Type RM Length L Ch R = 1 ,9383    ,499,499,499
BEGIN DESCRIPTION:
Conroe Lake 107 19.0
END DESCRIPTION:
XS GIS Cut Line= 3
      3743622.64      10163696.9      3743611.15     10163236.45
      3743544.32     10162724.29
#Sta/Elev= 30
  4539.4  297.37  4635.3  291.87  4675.3  288.17  4861.6  278.57  4905.3  277.41
  4965.4  277.29  4975.4   276.6  4980.2  274.67  4995.2  267.92  5003.7  267.07
  5007.2  267.07  5015.5  270.67  5035.7   274.6  5045.8  277.49  5096.2  279.85
  5116.4  281.82  5136.5   281.5  5146.6  283.23  5176.9  285.33  5186.9  287.09
  5220.5  289.19  5277.7  294.52  5294.4  295.55  5299.5     295  5348.3  299.45
  5373.4  300.82  5388.6  303.11  5408.8  303.97    5429  306.58  5516.5  308.71
#Mann= 4 ,-1 , 0
  4539.4     .11       0  4861.6     .17       0  4980.2     .09       0
  5035.7     .17       0
#XS Ineff= 2 , 0
       0  4945.4  277.62               0
Permanent Ineff=
       F       F
Bank Sta=4980.2,5035.7
XS Rating Curve= 0 ,0
Exp/Cntr=0.3,0.1

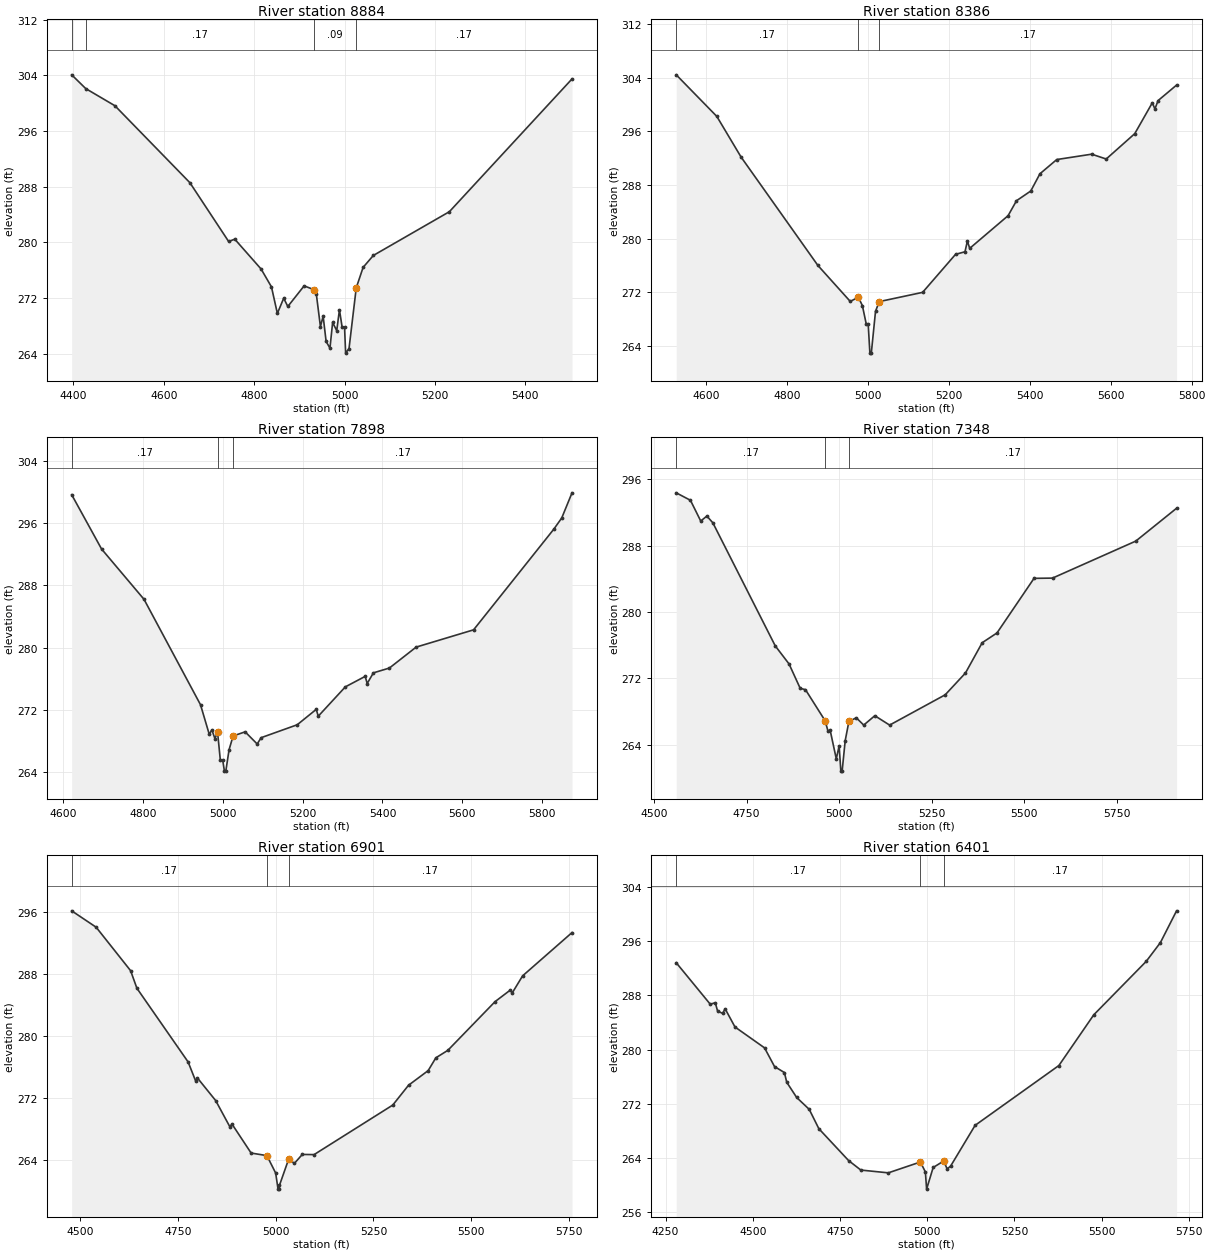
Type RM Length L Ch R = 1 ,8884    ,498,498,498
BEGIN DESCRIPTION:
Conroe Lake 107 18.0
END DESCRIPTION:
XS GIS Cut Line= 3
      3744419.45     10163640.87      3744086.39       10163137.
      3743842.61     10162696.45
#Sta/Elev= 30
    4396  304.07  4427.2  302.09  4491.7  299.63  4657.7  288.57  4743.4  280.13
    4757  280.46  4815.3  276.17  4838.2  273.61  4851.3  269.79  4865.3  271.98
  4874.4  270.79  4910.5  273.75  4931.5  273.23  4937.5  272.59  4946.6   267.9
  4952.6   269.4  4959.2  265.77  4967.7   264.8  4973.6   268.5  4982.7  267.32
  4988.7  270.32  4994.6  267.84    5000  267.84  5002.4  264.09  5009.9  264.75
  5025.9  273.47  5041.1  276.41  5063.7  278.12  5232.1  284.41  5503.5  303.48
#Mann= 4 ,-1 , 0
    4396     .11       0  4427.2     .17       0  4931.5     .09       0
  5025.9     .17       0
Bank Sta=4931.5,5025.9
XS Rating Curve= 0 ,0
Exp/Cntr=0.3,0.1

Type RM Length L Ch R = 1 ,8386    ,488,488,488
BEGIN DESCRIPTION:
Conroe Lake 107 17.0
END DESCRIPTION:
XS GIS Cut Line= 4
      3744468.06     10163631.44      3744468.59     10163156.64
      3744327.78     10162920.73       3743941.7     10162622.31
#Sta/Elev= 30
  4525.2  304.41  4625.6  298.21  4685.6  292.15  4875.6  275.99  4955.6  270.63
  4975.6  271.25  4985.6  270.01  4995.3  267.22    5000  267.22  5004.2  262.92
  5007.7  262.92  5018.1  269.15  5027.3   270.6  5134.6  271.98  5216.1  277.65
  5239.4  278.03  5245.3  279.63  5251.1  278.54    5346  283.41  5366.8  285.64
  5402.1  287.09  5424.8  289.66  5466.4  291.78  5552.7  292.58  5588.7  291.86
  5659.3  295.64  5702.8  300.25  5709.1  299.32    5717  300.57  5762.7  302.88
#Mann= 3 , 0 , 0
  4525.2     .17       0  4975.6     .09       0  5027.3     .17       0
Bank Sta=4975.6,5027.3
XS Rating Curve= 0 ,0
Exp/Cntr=0.3,0.1

Type RM Length L Ch R = 1 ,7898    ,550,550,550
BEGIN DESCRIPTION:
Conroe Lake 107 16.0
END DESCRIPTION:
XS GIS Cut Line= 3
      3744612.08     10163670.75      3744861.85     10163387.16
      3744791.68     10162515.48
#Sta/Elev= 30
  4622.1  299.67  4696.9  292.69  4803.2  286.22  4944.6  272.67  4966.4  268.88
    4973  269.44  4980.6  268.33  4987.3  269.13  4994.1   265.6    5000   265.6
  5004.4  264.14  5007.9  264.14  5016.1   266.9  5026.2  268.66  5056.3  269.19
  5086.4  267.63  5096.4  268.44  5186.7   270.1  5234.3  272.08  5239.3   271.2
  5307.1  274.97  5356.8  276.32  5361.8   275.4  5377.3  276.77  5417.4  277.39
  5484.3  280.08  5628.1   282.3  5828.8  295.23  5848.8  296.68  5874.5  299.91
#Mann= 3 , 0 , 0
  4622.1     .17       0  4987.3     .09       0  5026.2     .17       0
#XS Ineff= 2 , 0
       0                  5234.3       0  272.08
Permanent Ineff=
       F       F
Bank Sta=4987.3,5026.2
XS Rating Curve= 0 ,0
Exp/Cntr=0.3,0.1

Type RM Length L Ch R = 1 ,7348    ,447,447,447
BEGIN DESCRIPTION:
Conroe Lake 107 15.0
END DESCRIPTION:
XS GIS Cut Line= 3
      3745490.94     10163829.14      3745290.27     10163437.46
      3745270.45     10162526.07
#Sta/Elev= 30
  4559.9  294.36  4598.3  293.46  4626.1  290.96  4642.7  291.56  4658.9  290.74
  4827.4  275.91  4864.7  273.73  4894.8  270.79  4909.1  270.63  4962.2  266.88
  4970.1   265.6  4975.7  265.75  4992.3  262.29    5000  263.86  5004.6  260.81
  5008.1  260.81  5016.4  264.49  5026.4   266.8  5046.4  267.24  5066.4  266.36
  5096.4  267.49  5136.4  266.36  5286.5  270.01  5341.3  272.64  5386.5  276.29
  5426.5  277.47  5526.5  284.05  5576.5  284.08  5801.4  288.54  5911.6   292.5
#Mann= 3 , 0 , 0
  4559.9     .17       0  4962.2     .09       0  5026.4     .17       0
Bank Sta=4962.2,5026.4
XS Rating Curve= 0 ,0
Exp/Cntr=0.3,0.1

Type RM Length L Ch R = 1 ,6901    ,500,500,500
BEGIN DESCRIPTION:
Conroe Lake 107 14.0
END DESCRIPTION:
XS GIS Cut Line= 3
      3745575.33     10163816.65      3745636.39     10163298.74
      3745556.69     10162545.44
#Sta/Elev= 30
  4478.5  296.16  4541.1  294.04  4629.1  288.43  4645.2  286.16  4776.1  276.64
  4795.1  274.22  4800.1  274.56  4846.6  271.65  4883.1  268.24  4888.1  268.63
  4937.2  264.87  4977.5  264.54    5000  262.28    5006  260.21  5009.5  260.21
  5009.7  260.71  5033.3   264.1  5047.9  263.54    5068  264.69  5098.2  264.67
  5299.3  271.07  5339.6  273.63  5389.8  275.52  5409.4  277.17  5440.1  278.14
  5560.8  284.43  5599.9  285.93    5605  285.58  5631.2  287.76  5757.5  293.35
#Mann= 3 , 0 , 0
  4478.5     .17       0  4977.5     .09       0  5033.3     .17       0
Bank Sta=4977.5,5033.3
XS Rating Curve= 0 ,0
Exp/Cntr=0.3,0.1

Type RM Length L Ch R = 1 ,6401    ,497,497,497
BEGIN DESCRIPTION:
Conroe Lake 107 13.0
END DESCRIPTION:
XS GIS Cut Line= 3
      3745616.49     10163807.28      3746092.89      10163268.1
      3746125.14     10162554.12
#Sta/Elev= 30
  4280.5  292.81  4378.1  286.69  4392.4  286.92    4399  285.69  4413.2  285.35
  4420.8  286.01  4448.9  283.34  4533.7  280.26  4562.2  277.51  4590.6  276.62
  4597.3  275.19  4625.7  272.95  4661.7   271.2  4689.3  268.35  4774.6  263.65
  4809.7  262.25  4888.4  261.84  4980.4  263.44  4994.7  261.97  4998.2  259.44
    5017  262.63  5047.1  263.58  5057.1  262.42  5067.1  262.84  5137.2  268.84
  5377.4  277.66  5477.5  285.14  5627.7  293.01  5668.4  295.78  5714.7  300.46
#Mann= 3 , 0 , 0
  4280.5     .17       0  4980.4     .09       0  5047.1     .17       0
Bank Sta=4980.4,5047.1
XS Rating Curve= 0 ,0
Exp/Cntr=0.3,0.1

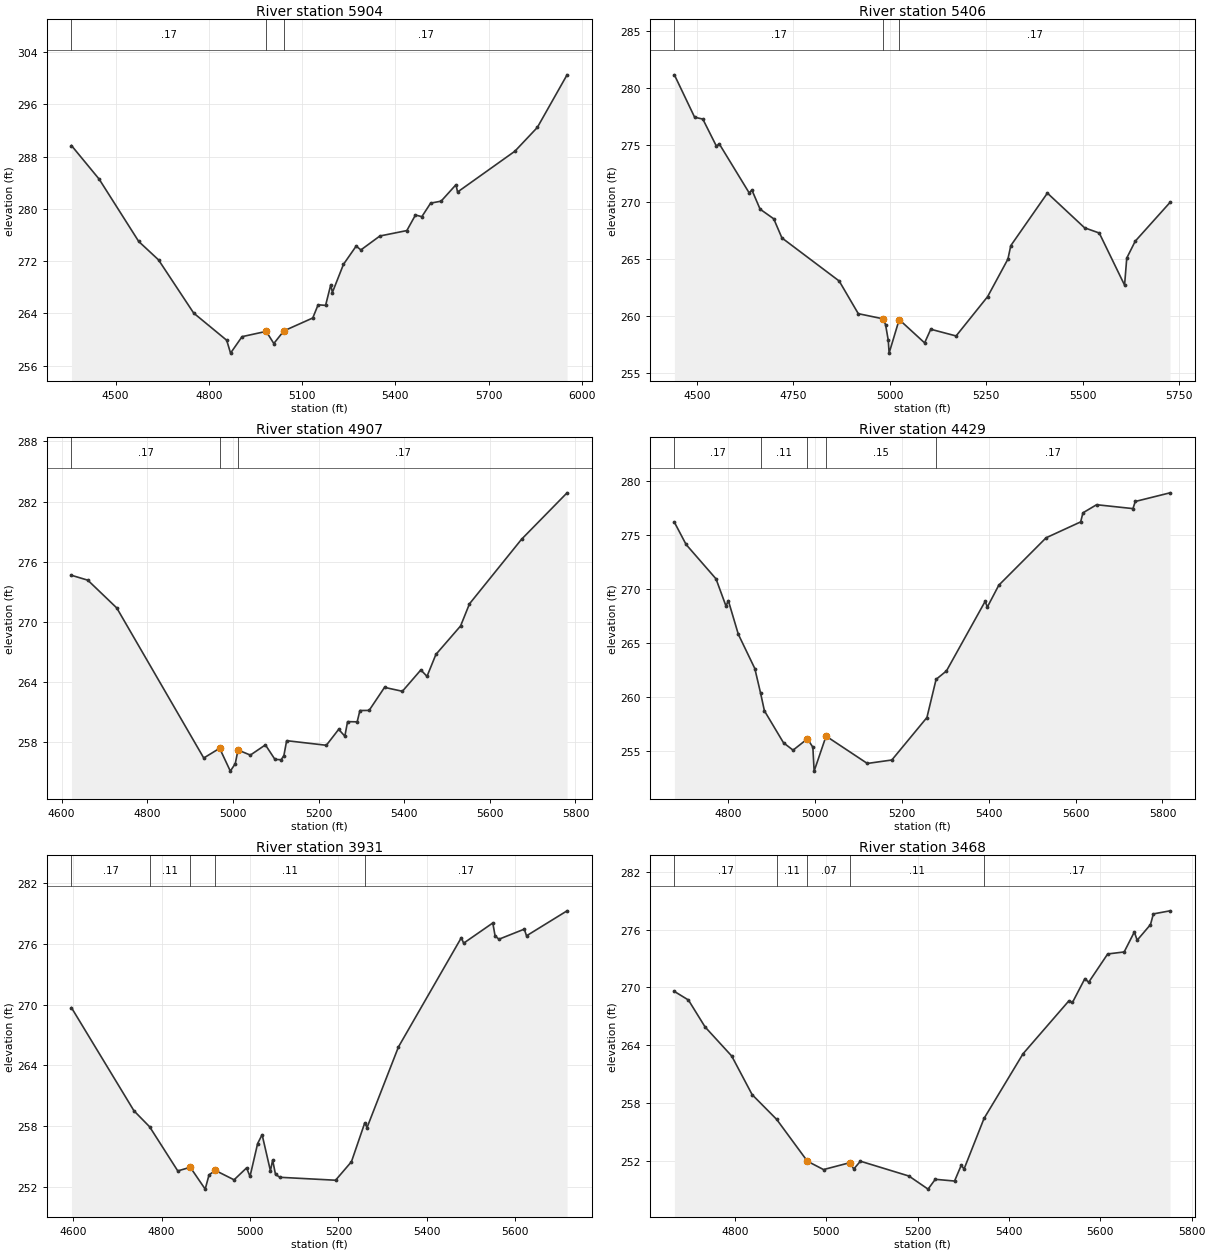
Type RM Length L Ch R = 1 ,5904    ,498,498,498
BEGIN DESCRIPTION:
Conroe Lake 107 12.0
END DESCRIPTION:
XS GIS Cut Line= 4
      3745906.39     10163915.78      3746368.89     10163470.66
      3746386.18      10163413.9      3746164.49     10162548.48
#Sta/Elev= 30
  4358.1   289.7  4447.3  284.55  4574.6  275.01  4638.2   272.2  4751.4  264.05
  4857.6  259.89    4870  257.92    4907  260.44  4984.7  261.25  5009.2  259.39
  5041.4  261.32  5134.5   263.3  5151.7  265.32  5175.8  265.23  5192.5   268.4
  5197.6   267.2  5233.3  271.51  5274.1   274.3  5289.4  273.72  5350.5  275.85
  5437.2  276.68  5464.9  279.06  5485.5  278.81  5513.7  280.88  5547.4  281.18
  5595.3   283.7  5600.4  282.58  5784.9  288.83  5857.1  292.47  5952.7  300.52
#Mann= 3 , 0 , 0
  4358.1     .17       0  4984.7     .09       0  5041.4     .17       0
Bank Sta=4984.7,5041.4
XS Rating Curve= 0 ,0
Exp/Cntr=0.3,0.1

Type RM Length L Ch R = 1 ,5406    ,499,499,499
BEGIN DESCRIPTION:
Conroe Lake 107 11.0
END DESCRIPTION:
XS GIS Cut Line= 3
      3746318.62      10164096.1      3746712.89     10163700.53
      3747058.22     10163061.35
#Sta/Elev= 30
  4441.5  281.18    4494  277.45  4515.2  277.29  4550.6   274.9  4557.7  275.12
  4635.4   270.8  4642.5  271.05  4663.7  269.37  4699.1  268.52  4720.3  266.84
  4868.8  263.05  4918.3  260.18  4981.9  259.73    4989  259.22  4996.1  257.83
  4998.2  256.71  5024.4  259.66  5090.3  257.61  5106.2  258.81  5171.9  258.22
  5253.7  261.68  5306.3  264.98  5313.7  266.16  5408.6  270.78    5505  267.73
  5543.1  267.27  5608.7  262.69  5614.4  265.07  5636.3  266.55  5726.5  269.96
#Mann= 3 , 0 , 0
  4441.5     .17       0  4981.9     .09       0  5024.4     .17       0
Bank Sta=4981.9,5024.4
XS Rating Curve= 0 ,0
Exp/Cntr=0.3,0.1

Type RM Length L Ch R = 1 ,4907    ,478,478,478
BEGIN DESCRIPTION:
Conroe Lake 107 10.0
END DESCRIPTION:
XS GIS Cut Line= 3
      3746787.37     10164294.02      3746978.15     10163968.74
      3747467.83     10163361.09
#Sta/Elev= 30
  4622.9  274.64  4661.1  274.15  4728.7  271.38  4931.9   256.4    4969  257.37
    4994  255.09  5005.5  255.84  5011.9   257.2  5040.7  256.69  5075.9  257.71
  5098.2  256.26  5112.6  256.23    5119  256.63  5125.5  258.13  5218.2  257.67
    5247  259.26  5261.4  258.58  5267.8  260.03  5290.2  260.01  5296.6  261.14
  5318.1  261.15  5354.1  263.45  5395.8  263.06  5438.9  265.19  5453.3  264.55
  5474.1  266.74  5531.7  269.58  5552.5  271.79    5674  278.23  5780.4  282.87
#Mann= 3 , 0 , 0
  4622.9     .17       0    4969     .09       0  5011.9     .17       0
Bank Sta=4969,5011.9
XS Rating Curve= 0 ,0
Exp/Cntr=0.3,0.1

Type RM Length L Ch R = 1 ,4429    ,498,498,498
BEGIN DESCRIPTION:
Conroe Lake 107 9.0
END DESCRIPTION:
XS GIS Cut Line= 3
      3747170.97     10164529.38      3747306.76     10164234.89
      3747568.62     10163460.67
#Sta/Elev= 30
  4675.7   276.2  4702.7  274.14  4771.6  270.96  4794.5  268.45    4800  268.94
    4823  265.83    4861  262.66  4874.4  260.36  4883.1  258.75  4927.1  255.79
  4949.1  255.11  4982.2  256.16  4994.7  255.38  4997.6  253.17  5025.1  256.41
  5120.1  253.88  5176.6   254.2  5257.4  258.13  5278.5  261.66  5302.4  262.44
  5391.4  268.87  5396.7  268.36  5422.9  270.37  5531.9  274.76  5611.5  276.23
  5616.8  277.07  5648.2  277.82    5732  277.46  5737.3  278.12  5817.3  278.92
#Mann= 5 ,-1 , 0
  4675.7     .17       0  4874.4     .11       0  4982.2     .07       0
  5025.1     .15       0  5278.5     .17       0
Bank Sta=4982.2,5025.1
XS Rating Curve= 0 ,0
Exp/Cntr=0.3,0.1

Type RM Length L Ch R = 1 ,3931    ,463,463,463
BEGIN DESCRIPTION:
Conroe Lake 107 8.0
END DESCRIPTION:
XS GIS Cut Line= 3
      3747367.84     10164561.08      3747655.89     10164278.23
      3747756.11     10163568.37
#Sta/Elev= 30
  4596.3  269.69  4737.7  259.49  4773.1  257.91  4836.7  253.55    4865  253.91
  4898.7  251.75  4907.4  253.16  4921.6   253.6    4964  252.67  4992.3  253.85
    5000     253  5017.3  256.26  5027.4  257.13  5046.2  253.56  5051.2  254.62
  5057.7   253.2  5067.8  252.92  5193.5  252.63  5229.4  254.46  5259.5   258.3
  5264.6  257.83  5335.7  265.81  5477.9  276.61    5483  276.06    5549  278.06
  5554.1   276.8  5562.7  276.45  5620.2  277.45  5625.2  276.79  5716.9  279.26
#Mann= 5 ,-1 , 0
  4596.3     .17       0  4773.1     .11       0    4865     .07       0
  4921.6     .11       0  5259.5     .17       0
#XS Ineff= 2 , 0
       0                  5027.4       0  257.13
Permanent Ineff=
       F       F
Bank Sta=4865,4921.6
XS Rating Curve= 0 ,0
Exp/Cntr=0.3,0.1

Type RM Length L Ch R = 1 ,3468    ,499,499,499
BEGIN DESCRIPTION:
Conroe Lake 107 7.0
END DESCRIPTION:
XS GIS Cut Line= 3
      3747767.85     10164911.07      3747917.18     10164614.44
      3748517.88     10164161.05
#Sta/Elev= 30
  4667.9  269.58  4698.6  268.69  4735.1  265.89  4793.4  262.87  4838.1  258.86
  4891.8  256.29    4959  251.95  4994.3  251.08  5052.2   251.8  5060.5  251.14
    5075  251.95  5181.2  250.41  5223.1  249.05  5238.9  250.07  5281.1  249.89
  5295.7  251.53  5301.9  251.14  5345.6  256.39    5431  263.11  5530.9  268.58
  5539.2  268.44  5566.3  270.91  5574.6  270.53  5616.2  273.47  5652.3  273.68
  5674.5  275.75  5680.8   274.9  5709.9  276.52  5716.2  277.63  5752.6  277.95
#Mann= 5 ,-1 , 0
  4667.9     .17       0  4891.8     .11       0    4959     .07       0
  5052.2     .11       0  5345.6     .17       0
Bank Sta=4959,5052.2
XS Rating Curve= 0 ,0
Exp/Cntr=0.3,0.1

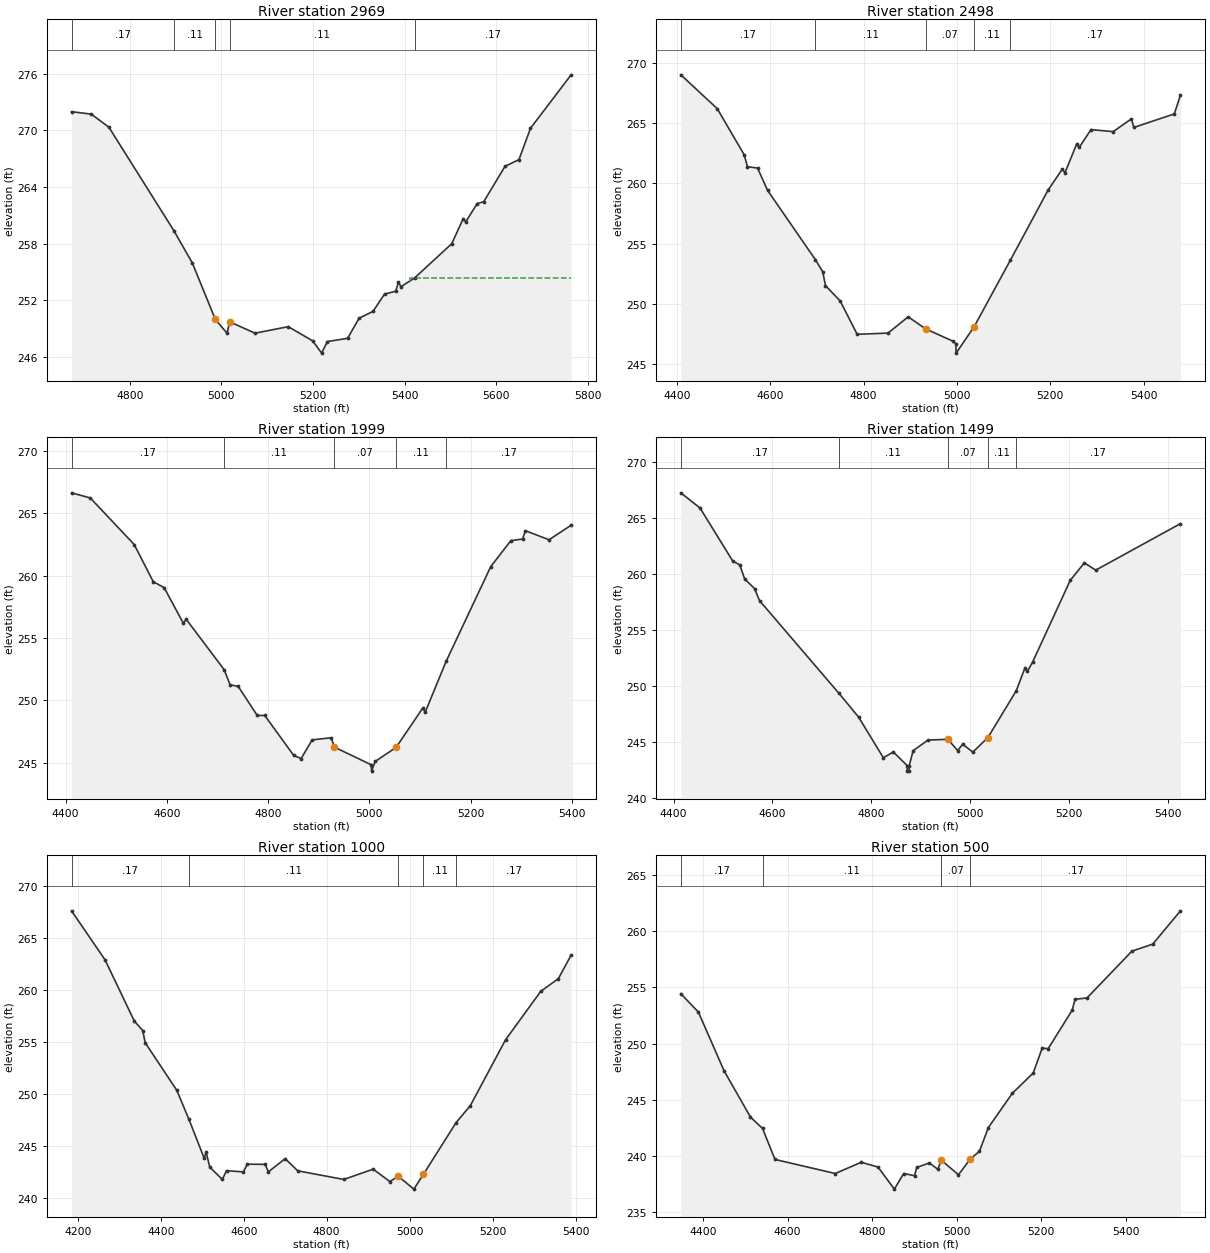
Type RM Length L Ch R = 1 ,2969    ,471,471,471
BEGIN DESCRIPTION:
Conroe Lake 107 6.0
END DESCRIPTION:
XS GIS Cut Line= 3
      3748247.36     10165254.19      3748268.54     10164927.77
      3748533.37      10164212.1
#Sta/Elev= 30
  4672.9  271.98  4716.1  271.72  4754.4  270.34  4896.5  259.37  4936.6  255.96
  4986.7     250  5012.5  248.52  5017.8  249.75  5073.3  248.54  5145.8  249.23
  5199.1  247.73  5218.7  246.43  5231.1  247.65  5275.4     248  5300.5  250.13
  5330.9  250.85  5355.9  252.68  5380.3  252.98  5386.3  253.96  5391.7  253.46
  5421.4  254.38  5502.6  258.01  5527.7  260.67    5533  260.31  5558.1  262.26
  5572.3  262.45  5618.9   266.2  5649.3  266.91  5674.4  270.22  5763.1  275.88
#Mann= 5 ,-1 , 0
  4672.9     .17       0  4896.5     .11       0  4986.7     .07       0
  5017.8     .11       0  5421.4     .17       0
#XS Ineff= 2 , 0
       0                  5411.4       0  254.34
Permanent Ineff=
       F       F
Bank Sta=4986.7,5017.8
XS Rating Curve= 0 ,0
Exp/Cntr=0.3,0.1

Type RM Length L Ch R = 1 ,2498    ,499,499,499
BEGIN DESCRIPTION:
Conroe Lake 107 5.0
END DESCRIPTION:
XS GIS Cut Line= 3
      3748351.52     10165288.93      3748644.75     10164775.58
      3748808.04      10164325.7
#Sta/Elev= 30
  4408.8  268.99  4486.7  266.19  4544.5  262.36  4551.5  261.37  4573.1  261.26
  4594.6  259.41  4696.9  253.67  4712.7  252.66  4718.5  251.52  4750.2  250.23
  4786.4  247.48  4852.4  247.58  4895.6  248.93    4933  247.93    4992   246.9
  4997.8  246.69  4998.2  245.92  5036.7   248.1  5114.1   253.6  5195.3  259.44
  5225.9  261.19  5231.2  260.86  5256.5  263.26  5261.8  262.97  5287.1  264.45
  5334.6  264.28  5373.6  265.34    5379  264.63  5465.5  265.75  5478.6   267.3
#Mann= 5 ,-1 , 0
  4408.8     .17       0  4696.9     .11       0    4933     .07       0
  5036.7     .11       0  5114.1     .17       0
Bank Sta=4933,5036.7
XS Rating Curve= 0 ,0
Exp/Cntr=0.3,0.1

Type RM Length L Ch R = 1 ,1999    ,500,500,500
BEGIN DESCRIPTION:
Conroe Lake 107 4.0
END DESCRIPTION:
XS GIS Cut Line= 3
      3748474.83     10165356.54      3748988.08     10165069.02
      3749353.13      10164908.7
#Sta/Elev= 30
  4411.7  266.66  4448.7  266.25  4535.5  262.51  4573.1  259.53  4594.8  259.04
  4632.5  256.19  4638.2  256.51  4713.2  252.46    4725  251.24  4740.9  251.12
  4778.6  248.78  4793.4  248.78  4850.7  245.57  4865.4  245.32  4887.1  246.82
  4924.7  246.99    4931  246.24  5004.2  244.81  5004.4  244.31  5011.7  245.09
    5053  246.22  5105.2  249.35  5110.6  249.06  5151.9  253.14    5240  260.74
  5279.6  262.82  5302.9  262.95  5308.4  263.62  5355.1  262.89  5398.7  264.06
#Mann= 5 ,-1 , 0
  4411.7     .17       0  4713.2     .11       0    4931     .07       0
    5053     .11       0  5151.9     .17       0
Bank Sta=4931,5053
XS Rating Curve= 0 ,0
Exp/Cntr=0.3,0.1

Type RM Length L Ch R = 1 ,1499    ,499,499,499
BEGIN DESCRIPTION:
Conroe Lake 107 3.0
END DESCRIPTION:
XS GIS Cut Line= 3
      3748579.03     10165533.61      3749162.96     10165492.16
      3749549.93     10165315.46
#Sta/Elev= 30
  4414.6  267.24  4453.5  265.88  4519.9  261.13  4533.7  260.82  4543.7  259.56
  4563.8  258.69  4573.8  257.62  4734.2  249.36  4774.3  247.22  4824.4  243.59
  4844.5  244.11  4872.4   242.9  4872.7   242.4  4876.4   242.4  4876.7   242.9
  4884.6  244.23  4914.7  245.17  4954.8  245.24  4974.8  244.24  4984.8   244.8
  5005.4   244.1  5035.8  245.39  5093.3  249.58  5110.4  251.57  5115.9  251.31
  5126.3  252.13  5202.5  259.43    5231  260.99  5254.1  260.34  5425.4  264.49
#Mann= 5 ,-1 , 0
  4414.6     .17       0  4734.2     .11       0  4954.8     .07       0
  5035.8     .11       0  5093.3     .17       0
Bank Sta=4954.8,5035.8
XS Rating Curve= 0 ,0
Exp/Cntr=0.3,0.1

Type RM Length L Ch R = 1 ,1000    ,500,500,500
BEGIN DESCRIPTION:
Conroe Lake 107 2.0
END DESCRIPTION:
XS GIS Cut Line= 3
      3748617.84     10165761.07      3749424.99     10165875.29
      3749693.24     10165593.02
#Sta/Elev= 30
  4184.8  267.66  4265.6  262.95  4336.3  257.05  4356.5  256.15  4362.4  254.98
  4438.5  250.41  4467.6  247.64  4504.5  243.89  4509.5  244.44  4518.1  243.02
  4548.4  241.83  4558.5  242.67  4598.9  242.56    4609   243.3  4651.6  243.28
  4659.5  242.56  4699.9  243.83  4730.2  242.66  4841.3  241.83    4912  242.82
  4952.4  241.63  4972.6  242.14  5010.2   240.9  5033.4  242.33  5112.1   247.3
  5146.4  248.93  5231.3  255.26  5316.2  259.92  5358.7  261.14  5389.4   263.4
#Mann= 5 ,-1 , 0
  4184.8     .17       0  4467.6     .11       0  4972.6     .07       0
  5033.4     .11       0  5112.1     .17       0
#XS Ineff= 2 , 0
       0  4699.9  243.83               0
Permanent Ineff=
       T       F
Bank Sta=4972.6,5033.4
XS Rating Curve= 0 ,0
Exp/Cntr=0.3,0.1

Type RM Length L Ch R = 1 ,500     ,353,353,353
BEGIN DESCRIPTION:
Conroe Lake 107 1.0
END DESCRIPTION:
XS GIS Cut Line= 3
      3749026.98     10166380.82      3749671.68     10166280.88
      3750047.79      10165908.6
#Sta/Elev= 30
  4347.6  254.44    4389  252.82  4449.7   247.6  4512.3  243.47  4540.8  242.46
  4570.3   239.7  4712.8  238.45  4774.4  239.45    4814  239.02  4852.6  237.06
  4874.7  238.45  4900.4  238.25  4905.5  238.99  4935.4  239.39  4955.6  238.82
  4963.4  239.64  5004.2  238.34  5032.5  239.75  5053.7  240.42    5075  242.54
  5131.5  245.58    5181  247.39  5202.2   249.6  5216.4  249.56    5273  252.97
    5280  253.95  5308.3  254.07  5414.4  258.23  5463.8  258.86  5529.2  261.82
#Mann= 4 ,-1 , 0
  4347.6     .17       0  4540.8     .11       0  4963.4     .07       0
  5032.5     .17       0
Bank Sta=4963.4,5032.5
XS Rating Curve= 0 ,0
Exp/Cntr=0.3,0.1

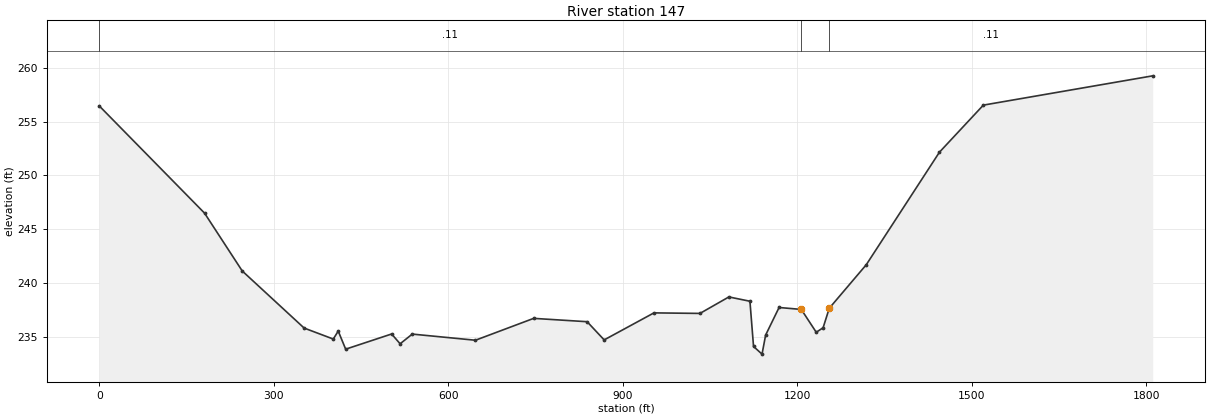
Type RM Length L Ch R = 1 ,147     ,0,0,0
BEGIN DESCRIPTION:
Conroe Lake 107 0.5
END DESCRIPTION:
XS GIS Cut Line= 3
      3750570.32     10167531.95       3749872.4     10166586.64
      3750083.34     10165985.08
#Sta/Elev= 30
       0  256.46   181.1   246.5   245.9  241.13   352.3  235.83   402.4  234.81
   410.9  235.55   423.7  233.87   502.7  235.28   517.3  234.37   538.2  235.27
   646.8   234.7   746.9  236.73   838.8  236.42   868.1  234.73   953.7  237.24
  1032.8  237.19  1082.5  238.72  1118.7  238.32  1124.9  234.12  1139.5  233.41
  1145.7  235.18  1168.8  237.74    1207  237.56  1232.7  235.44  1244.5  235.86
  1255.1  237.67  1318.7  241.71  1444.5  252.16    1520  256.53  1811.2  259.25
#Mann= 3 , 0 , 0
       0     .11       0    1207     .07       0  1255.1     .11       0
Bank Sta=1207,1255.1
XS Rating Curve= 0 ,0
Exp/Cntr=0.3,0.1

Chan Stop Cuts=-1
Use User Specified Reach Order=0
Composite Channel Slope=5