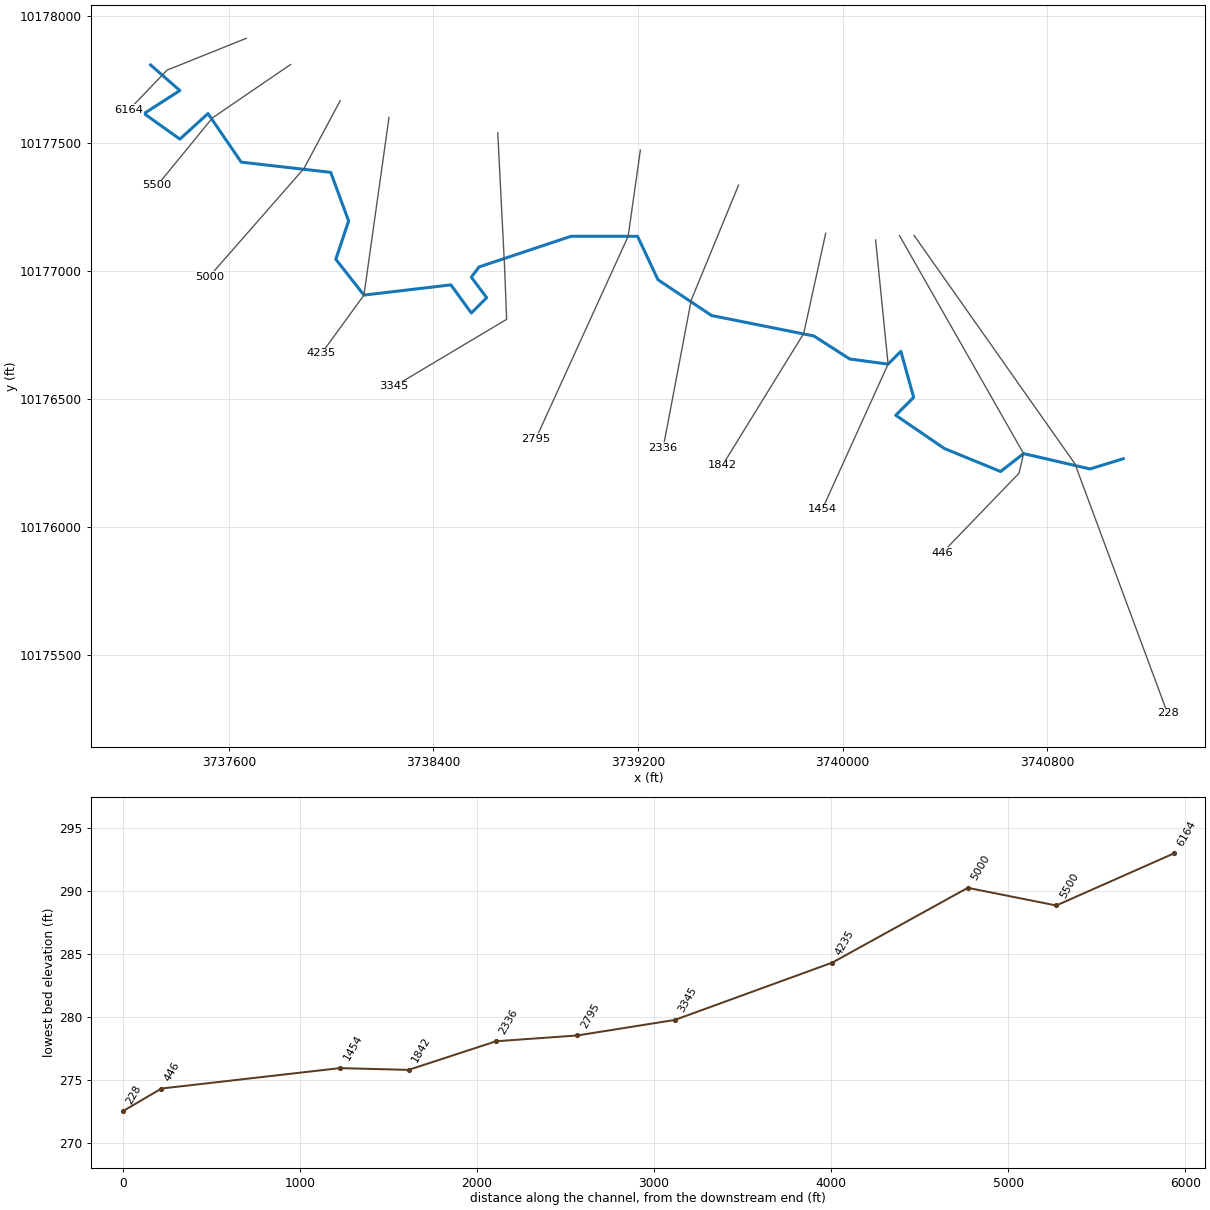
--- Conroe Lake 110.prj (project) ---

Proj Title=Conroe Lake 110 Base Level Engineering
Current Plan=p01
Default Exp/Contr=0.3,0.1
English Units
Geom File=g01
Flow File=f01
Flow File=f02
Plan File=p01
Y Axis Title=Elevation
X Axis Title(PF)=Main Channel Distance
X Axis Title(XS)=Station
BEGIN DESCRIPTION:
Conroe Lake 110
END DESCRIPTION:
DSS Export Rating Curves= 0
DSS Export Rating Curve Sorted= 0
DSS Export Volume Flow Curves= 0
DXF OffsetX= 0
DXF OffsetY= 0
DXF ScaleX= 1
DXF ScaleY= 10

--- Conroe Lake 110.p01 (plan) ---

Plan Title=Multiple Run
Short Identifier=Multiple
Geom File=g01
Flow File=f01
Subcritical Flow
K Sum by GR= 0
Std Step Tol= 0.01
Critical Tol= 0.01
Num of Std Step Trials= 20
Max Error Tol= 0.3
Flow Tol Ratio= 0.001
Split Flow NTrial= 30
Split Flow Tol= 0.02
Split Flow Ratio= 0.02
Log Output Level= 0
Friction Slope Method= 1
Unsteady Friction Slope Method= 2
Unsteady Bridges Friction Slope Method= 1
Parabolic Critical Depth
Global Vel Dist=  1 , 1 , 1
Global Log Level= 0
CheckData=True
Encroach Param= -1, 0, 0, 0
BEGIN DESCRIPTION:
Multiple Run
END DESCRIPTION:

--- Conroe Lake 110.f01 (steady flow) ---

Flow Title=Multiple
Program Version=4.10
Number of Profiles= 7
Profile Names=10-year,25-year,50-year,1pct_min,100-year,1pct_plu,500-year
River Rch & RM=Conroe Lake 110,Reach-1         ,6164
     549     740     996     441    1333    4026    2470
River Rch & RM=Conroe Lake 110,Reach-1         ,5000
     710     972    1323     592    1788    5400    3378
River Rch & RM=Conroe Lake 110,Reach-1         ,1842
     708     965    1310     584    1765    5330    3318
Boundary for River Rch & Prof#=Conroe Lake 110,Reach-1         , 1
Up Type= 0
Dn Type= 3
Dn Slope=0.01
Boundary for River Rch & Prof#=Conroe Lake 110,Reach-1         , 2
Up Type= 0
Dn Type= 3
Dn Slope=0.01
Boundary for River Rch & Prof#=Conroe Lake 110,Reach-1         , 3
Up Type= 0
Dn Type= 3
Dn Slope=0.01
Boundary for River Rch & Prof#=Conroe Lake 110,Reach-1         , 4
Up Type= 0
Dn Type= 3
Dn Slope=0.01
Boundary for River Rch & Prof#=Conroe Lake 110,Reach-1         , 5
Up Type= 0
Dn Type= 3
Dn Slope=0.01
Boundary for River Rch & Prof#=Conroe Lake 110,Reach-1         , 6
Up Type= 0
Dn Type= 3
Dn Slope=0.01
Boundary for River Rch & Prof#=Conroe Lake 110,Reach-1         , 7
Up Type= 0
Dn Type= 3
Dn Slope=0.01
DSS Import GetInterval= 0
DSS Import GetPeak= 0
DSS Import FillOption= 0

--- Conroe Lake 110.f02 (steady flow) ---

Flow Title=Orig_BLE_Flow
Program Version=4.10
Number of Profiles= 7
Profile Names=10-year,25-year,50-year,1pct_min,100-year,1pct_plu,500-year
River Rch & RM=Conroe Lake 110,Reach-1         ,6164
     549     725     866     340    1025    3097    1436
River Rch & RM=Conroe Lake 110,Reach-1         ,5000
     710     953    1150     455    1375    4153    1964
River Rch & RM=Conroe Lake 110,Reach-1         ,1842
     708     946    1139     450    1358    4102    1929
Boundary for River Rch & Prof#=Conroe Lake 110,Reach-1         , 1
Up Type= 0
Dn Type= 3
Dn Slope=0.01
Boundary for River Rch & Prof#=Conroe Lake 110,Reach-1         , 2
Up Type= 0
Dn Type= 3
Dn Slope=0.01
Boundary for River Rch & Prof#=Conroe Lake 110,Reach-1         , 3
Up Type= 0
Dn Type= 3
Dn Slope=0.01
Boundary for River Rch & Prof#=Conroe Lake 110,Reach-1         , 4
Up Type= 0
Dn Type= 3
Dn Slope=0.01
Boundary for River Rch & Prof#=Conroe Lake 110,Reach-1         , 5
Up Type= 0
Dn Type= 3
Dn Slope=0.01
Boundary for River Rch & Prof#=Conroe Lake 110,Reach-1         , 6
Up Type= 0
Dn Type= 3
Dn Slope=0.01
Boundary for River Rch & Prof#=Conroe Lake 110,Reach-1         , 7
Up Type= 0
Dn Type= 3
Dn Slope=0.01
DSS Import GetInterval= 0
DSS Import GetPeak= 0
DSS Import FillOption= 0

--- Conroe Lake 110.g01 (geometry) ---

Geom Title=Existing Conditions
Program Version=4.10

River Reach=Conroe Lake 110 ,Reach-1
Reach XY= 30
      3737293.85     10177806.84      3737408.23     10177706.84
      3737268.23     10177616.84      3737408.23     10177516.84
      3737518.23     10177616.84      3737648.23     10177426.84
      3737998.23     10177386.84      3738068.23     10177196.84
      3738018.23     10177046.84      3738128.23     10176906.84
      3738468.23     10176946.84      3738548.23     10176836.84
      3738608.23     10176896.84      3738548.23     10176976.84
      3738578.23     10177016.84      3738938.23     10177136.84
      3739198.23     10177136.84      3739278.23     10176966.84
      3739488.23     10176826.84      3739888.23     10176746.84
      3740028.23     10176656.84      3740178.23     10176636.84
      3740228.23     10176686.84      3740278.23     10176506.84
      3740208.23     10176436.84      3740398.23     10176306.84
      3740618.23     10176216.84      3740708.23     10176286.84
      3740968.23     10176226.84      3741098.23     10176266.84

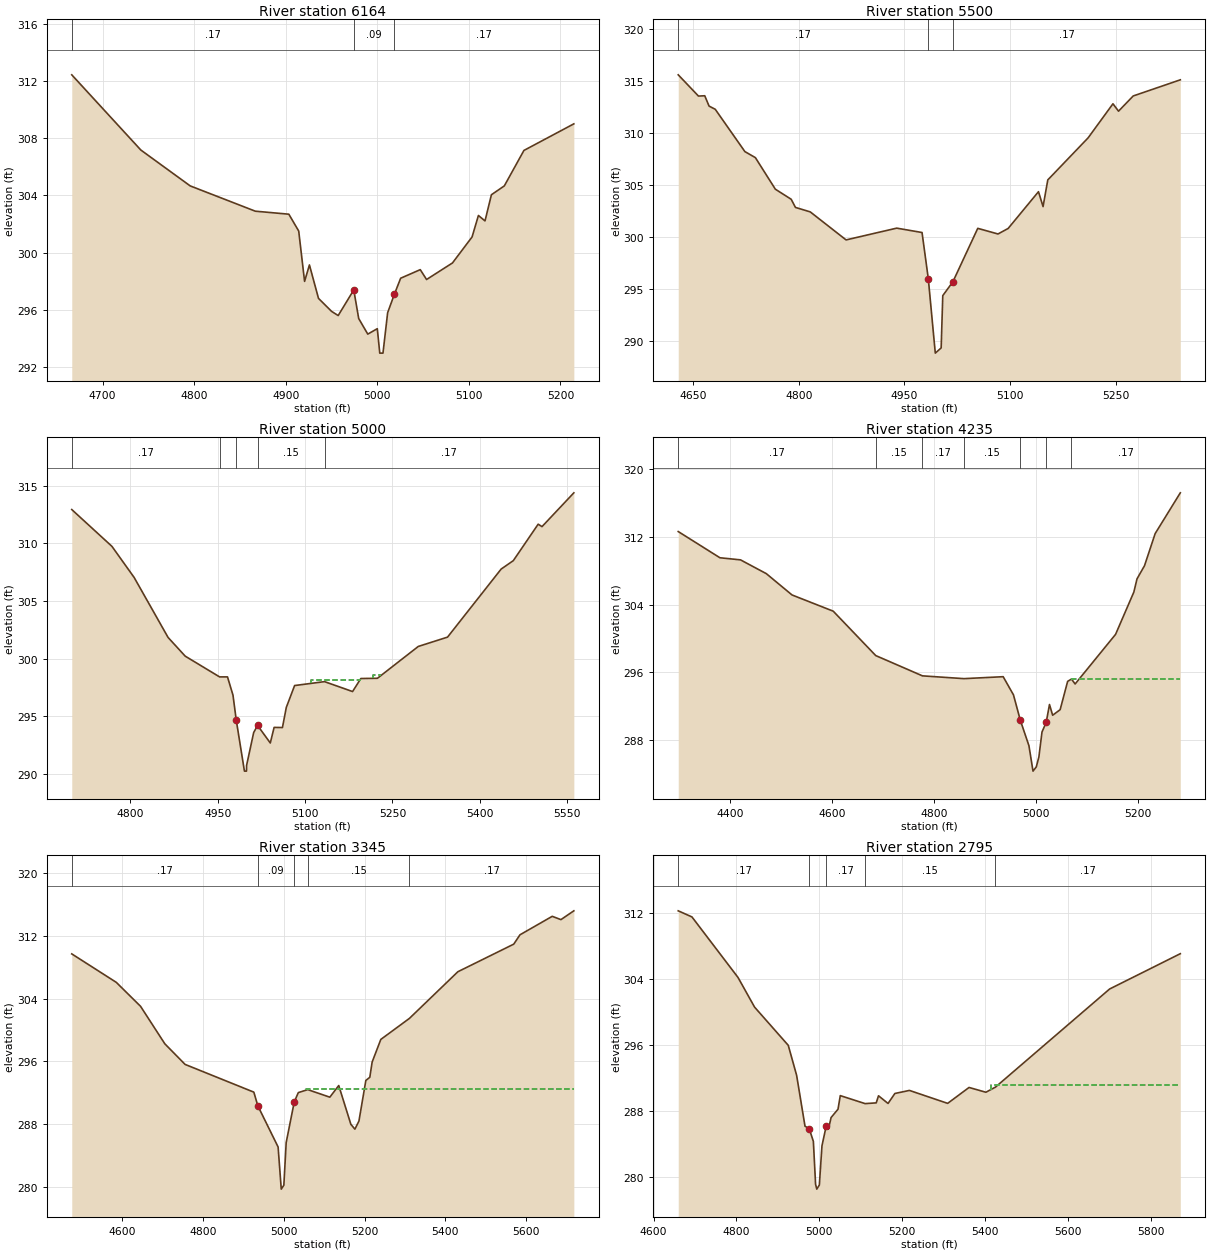
Type RM Length L Ch R = 1 ,6164    ,664,664,664
BEGIN DESCRIPTION:
Conroe Lake 110 10.0
END DESCRIPTION:
XS GIS Cut Line= 3
      3737667.84     10177911.07      3737358.23     10177786.84
      3737209.77     10177631.89
#Sta/Elev= 30
  4666.4  312.44  4741.8  307.18  4795.7  304.67  4866.8   302.9  4903.4  302.69
  4914.2  301.51  4920.6  297.99  4925.9  299.14  4935.8   296.8  4950.1  295.89
  4957.3   295.6  4974.3  297.39  4979.7  295.39  4989.6   294.3    5000  294.68
  5002.7  292.97  5006.2  292.97  5011.3   295.8  5018.6  297.08  5025.5  298.21
  5046.9  298.81  5053.8  298.12  5082.1  299.28  5103.5   301.1  5110.4   302.6
  5117.6  302.22  5124.6  304.05  5138.7  304.67  5160.1  307.15  5214.6  309.01
#Mann= 3 , 0 , 0
  4666.4     .17       0  4974.3     .09       0  5018.6     .17       0
#XS Ineff= 2 , 0
       0                  5110.4       0   302.6
Permanent Ineff=
       F       F
Bank Sta=4974.3,5018.6
XS Rating Curve= 0 ,0
Exp/Cntr=0.3,0.1

Type RM Length L Ch R = 1 ,5500    ,500,500,500
BEGIN DESCRIPTION:
Conroe Lake 110 11.0
END DESCRIPTION:
XS GIS Cut Line= 3
      3737841.53     10177808.91       3737535.4     10177599.67
      3737319.58     10177335.53
#Sta/Elev= 30
  4629.2  315.56  4657.9  313.52  4666.8  313.55  4672.9  312.56  4681.7  312.25
  4723.7  308.19  4738.6  307.61  4766.9  304.58  4789.4  303.61  4795.4  302.83
  4816.4   302.4  4867.2  299.71    4939  300.84  4974.9  300.42  4983.8  295.97
  4993.7  288.84    5002  289.34  5004.3  294.36  5018.7   295.7  5053.9  300.82
  5082.6  300.28    5097  300.81    5140  304.34  5146.5  302.91  5153.2  305.47
  5210.4  309.51  5245.6  312.78  5253.5  312.07  5274.3  313.53  5341.1  315.08
#Mann= 3 , 0 , 0
  4629.2     .17       0  4983.8     .09       0  5018.7     .17       0
#XS Ineff= 2 , 0
       0    4939  300.84    5140       0  304.34
Permanent Ineff=
       F       F
Bank Sta=4983.8,5018.7
XS Rating Curve= 0 ,0
Exp/Cntr=0.3,0.1

Type RM Length L Ch R = 1 ,5000    ,765,765,765
BEGIN DESCRIPTION:
Conroe Lake 110 10.5
END DESCRIPTION:
XS GIS Cut Line= 3
      3738035.29     10177667.02      3737893.39     10177401.68
      3737523.17     10176979.13
#Sta/Elev= 30
  4699.1  312.92  4768.1  309.73  4806.3  307.03  4864.6  301.83    4894  300.21
  4953.1  298.41  4966.7  298.41  4976.1  296.83  4981.8  294.64  4995.8  290.24
  4999.3  290.24  4999.5  290.74  5011.7  293.59  5018.4   294.2  5040.2  292.68
  5046.8  294.03  5061.1  294.02  5067.7  295.76    5082  297.66  5133.4     298
  5181.6  297.14  5195.8  298.27  5224.3  298.29  5294.5  301.05  5344.8  301.86
  5436.9  307.76  5457.8  308.49  5500.5  311.65  5507.1  311.44  5561.8  314.37
#Mann= 5 ,-1 , 0
  4699.1     .17       0  4953.1     .15       0  4981.8     .09       0
  5018.4     .15       0  5133.4     .17       0
#XS Ineff= 2 ,-1
  5110.4  5195.8  298.15  5216.7    5231  298.54
Permanent Ineff=
       F       F
Bank Sta=4981.8,5018.4
XS Rating Curve= 0 ,0
Exp/Cntr=0.3,0.1

Type RM Length L Ch R = 1 ,4235    ,890,890,890
BEGIN DESCRIPTION:
Conroe Lake 110 8.0
END DESCRIPTION:
XS GIS Cut Line= 3
      3738226.28     10177601.96      3738128.23     10176906.84
       3737962.2      10176678.4
#Sta/Elev= 30
    4298  312.65  4379.7  309.55  4420.1   309.3  4470.7  307.67  4521.1  305.15
  4601.9  303.23  4685.2  297.98  4776.8  295.58  4858.1  295.25  4935.1  295.48
  4955.3  293.33  4968.7  290.33  4985.6  287.32  4993.6  284.31    5000  284.81
  5005.1  285.98  5011.2  288.93  5019.5  290.09  5025.9  292.19  5032.1  290.92
  5046.8  291.58  5061.5  294.93    5069   295.2  5076.2  294.62  5155.5  300.49
  5191.3  305.49  5197.5  307.05  5212.2  308.61  5233.1  312.41  5282.4  317.23
#Mann= 7 ,-1 , 0
    4298     .17       0  4685.2     .15       0  4776.8     .17       0
  4858.1     .15       0  4968.7     .09       0  5019.5     .15       0
    5069     .17       0
#XS Ineff= 2 , 0
       0                  5068.9       0  295.21
Permanent Ineff=
       F       F
Bank Sta=4968.7,5019.5
XS Rating Curve= 0 ,0
Exp/Cntr=0.3,0.1

Type RM Length L Ch R = 1 ,3345    ,550,550,550
BEGIN DESCRIPTION:
Conroe Lake 110 6.0
END DESCRIPTION:
XS GIS Cut Line= 4
      3738651.62     10177541.17      3738678.23     10177016.84
      3738686.35     10176812.01      3738245.77      10176549.4
#Sta/Elev= 30
    4475  309.69  4585.2  306.07  4645.3  303.02  4705.4  298.25  4755.5  295.63
  4925.7   292.1  4935.7  290.35  4985.8  285.12  4993.6  279.76    5000  280.26
  5005.8  285.69  5025.8  290.86  5035.8  292.04  5059.2  292.42  5113.8  291.46
  5135.9  292.94  5165.9  288.01  5175.9  287.39  5185.9  288.42    5203  293.59
  5212.8  293.99  5218.6  295.93  5240.1  298.81  5310.8  301.48  5430.8  307.42
  5569.1  310.93  5584.6  312.12  5664.4  314.47  5685.9  314.05  5717.9  315.17
#Mann= 5 ,-1 , 0
    4475     .17       0  4935.7     .09       0  5025.8     .17       0
  5059.2     .15       0  5310.8     .17       0
#XS Ineff= 2 , 0
       0                  5055.8       0   292.5
Permanent Ineff=
       F       F
Bank Sta=4935.7,5025.8
XS Rating Curve= 0 ,0
Exp/Cntr=0.3,0.1

Type RM Length L Ch R = 1 ,2795    ,459,459,459
BEGIN DESCRIPTION:
Conroe Lake 110 5.0
END DESCRIPTION:
XS GIS Cut Line= 3
      3739209.35     10177473.88      3739161.61     10177136.84
      3738800.44     10176344.58
#Sta/Elev= 30
  4659.6  312.28  4692.7  311.54  4803.8   304.2  4843.8   300.6    4925  295.97
  4945.2  292.33  4965.4  286.16  4975.5  285.87  4985.6  284.31  4990.9  279.12
  4993.8  278.53    5000  279.03  5006.3  283.78  5016.5  286.17    5022  285.82
  5028.3  287.21    5045  288.22  5050.5  289.87  5110.4   288.9  5137.2  288.99
  5142.7  289.85  5165.7  288.92  5182.2  290.13  5217.3   290.5  5309.5  288.93
  5361.1  290.86  5401.7  290.28  5424.8   290.9  5700.2   302.8  5870.7  307.08
#Mann= 5 ,-1 , 0
  4659.6     .17       0  4975.5     .09       0  5016.5     .17       0
  5110.4     .15       0  5424.8     .17       0
#XS Ineff= 2 , 0
       0                    5413       0  291.19
Permanent Ineff=
       F       F
Bank Sta=4975.5,5016.5
XS Rating Curve= 0 ,0
Exp/Cntr=0.3,0.1

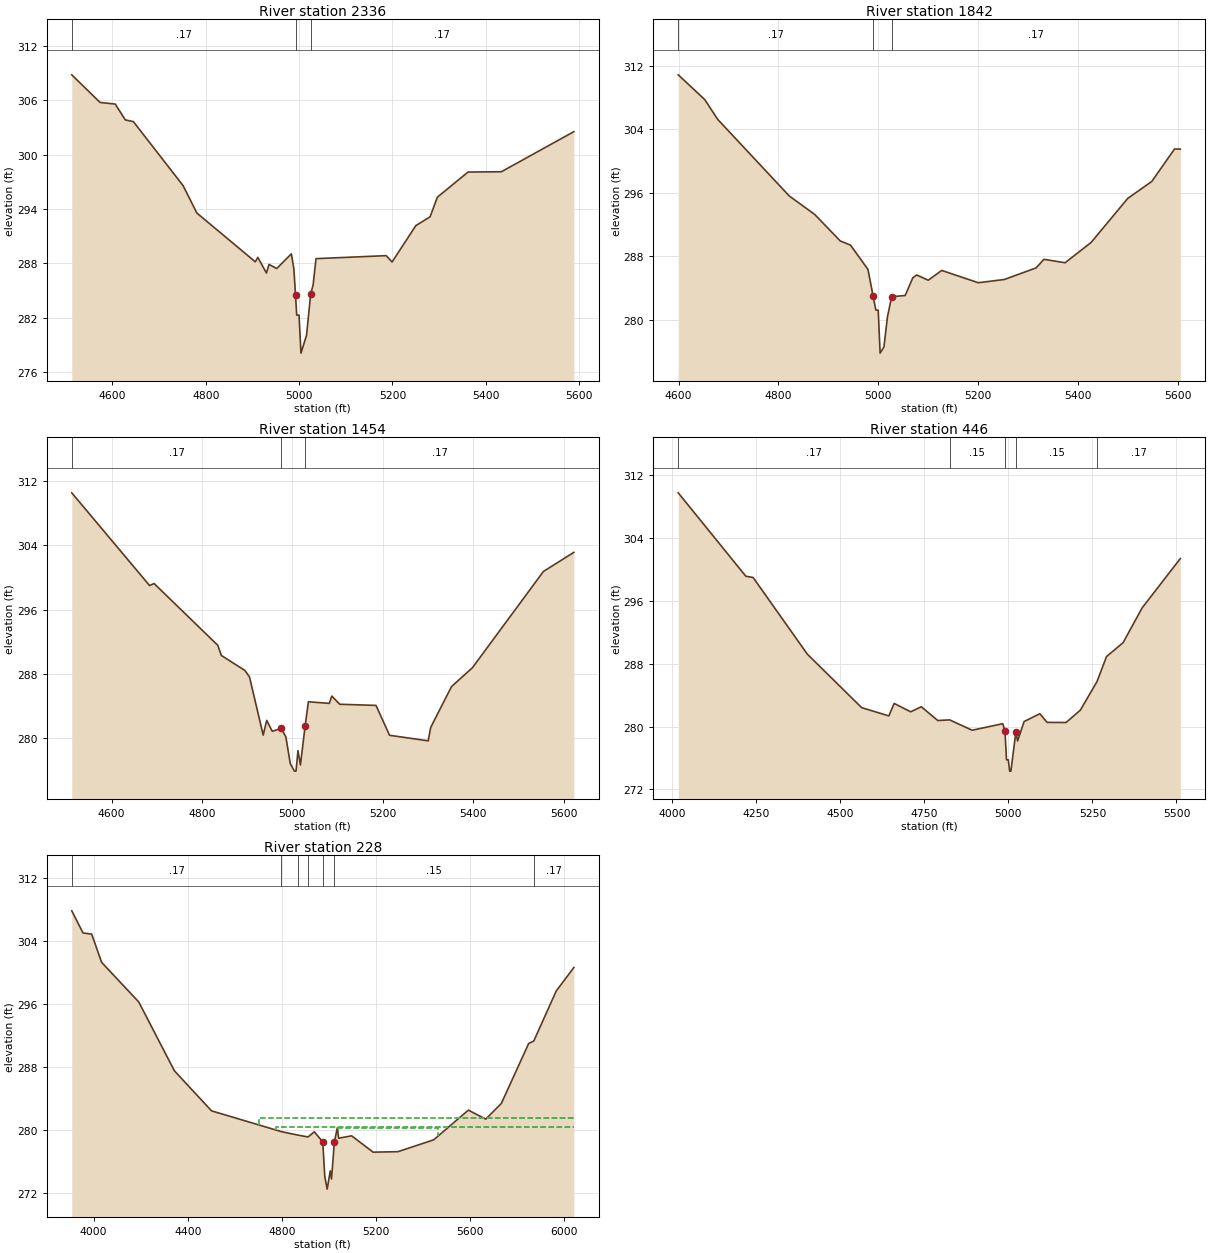
Type RM Length L Ch R = 1 ,2336    ,494,494,494
BEGIN DESCRIPTION:
Conroe Lake 110 4.0
END DESCRIPTION:
XS GIS Cut Line= 3
      3739593.45     10177337.14      3739408.23     10176886.84
      3739298.32      10176308.5
#Sta/Elev= 30
  4513.1  308.82  4573.7  305.77  4606.2  305.59  4627.8  303.84  4645.1  303.65
  4751.7  296.57  4781.1  293.55  4906.3  288.16  4911.7  288.65  4930.2  286.92
  4935.6  287.87  4952.2  287.42  4983.5  289.04  4988.9  287.39  4992.4  284.53
    4995  282.27    5000  282.27  5004.1  278.07  5016.1  280.05    5025  284.64
  5030.1  285.59  5036.4  288.51  5186.7  288.84  5199.3  288.14  5250.2  292.16
  5280.7  293.13  5296.3   295.3  5362.1  298.08  5433.4  298.11  5588.7  302.54
#Mann= 3 , 0 , 0
  4513.1     .17       0  4992.4     .09       0    5025     .17       0
#XS Ineff= 2 , 0
       0  4983.5  289.04  5036.4       0  288.51
Permanent Ineff=
       F       F
Bank Sta=4992.4,5025
XS Rating Curve= 0 ,0
Exp/Cntr=0.3,0.1

Type RM Length L Ch R = 1 ,1842    ,388,388,388
BEGIN DESCRIPTION:
Conroe Lake 110 3.0
END DESCRIPTION:
XS GIS Cut Line= 3
      3739934.18     10177148.42      3739848.23     10176756.84
      3739530.53     10176241.27
#Sta/Elev= 30
  4599.1  310.87  4652.3  307.75  4678.3  305.25  4821.6  295.61  4872.8  293.27
    4924  289.93  4944.5  289.41  4979.4  286.36 4989.73     283  4995.3  281.22
    5000  281.22  5003.8   275.8  5011.5  276.59  5018.5  280.36  5026.9  282.91
    5054  283.06  5069.4   285.3  5077.3  285.65  5100.2  284.99  5127.4  286.22
  5200.7  284.67  5252.8  285.08  5316.6  286.54  5332.1  287.62  5374.6  287.19
  5426.7  289.74  5500.1  295.29  5548.5  297.44  5594.1  301.53  5605.6  301.51
#Mann= 3 , 0 , 0
  4599.1     .17       0 4989.73     .09       0  5026.9     .17       0
#XS Ineff= 2 , 0
       0                  5127.4       0  286.22
Permanent Ineff=
       F       F
Bank Sta=4989.73,5026.9
XS Rating Curve= 0 ,0
Exp/Cntr=0.3,0.1

Type RM Length L Ch R = 1 ,1454    ,1008,1008,1008
BEGIN DESCRIPTION:
Conroe Lake 110 2.0
END DESCRIPTION:
XS GIS Cut Line= 3
      3740129.49      10177122.3      3740178.23     10176636.84
      3739921.14      10176069.8
#Sta/Elev= 30
  4512.1  310.49  4684.2  298.98  4694.2  299.23  4834.9  291.57    4843   290.3
  4895.2  288.43  4905.3  287.62  4935.5  280.41  4943.3  282.24  4955.6  280.88
  4975.7  281.26  4985.7  280.17  4995.4  276.88  5004.6  275.94  5008.1  275.94
  5012.4  278.49  5017.9  276.71  5028.3  281.58  5035.5  284.55  5081.7  284.35
  5087.2  285.26  5104.8  284.24    5185   284.1    5215  280.39  5300.5   279.7
    5306  281.37  5352.1  286.44  5398.3  288.78  5555.3  300.73  5622.6   303.1
#Mann= 3 , 0 , 0
  4512.1     .17       0  4975.7     .09       0  5028.3     .17       0
#XS Ineff= 2 , 0
       0                  5087.2       0  285.26
Permanent Ineff=
       F       T
Bank Sta=4975.7,5028.3
XS Rating Curve= 0 ,0
Exp/Cntr=0.3,0.1

Type RM Length L Ch R = 1 ,446     ,218,218,218
BEGIN DESCRIPTION:
Conroe Lake 110 1.0
END DESCRIPTION:
XS GIS Cut Line= 4
      3740222.82     10177139.68      3740708.23     10176286.84
      3740690.39      10176210.3      3740390.04     10175898.67
#Sta/Elev= 30
  4018.7  309.79  4219.7  299.16  4241.3     299  4402.7  289.22  4564.1  282.41
  4644.8  281.36  4660.7  282.95  4709.7  281.88  4741.4  282.52  4790.4  280.77
  4825.7  280.85  4892.7  279.53  4983.5  280.37  4990.1  279.44  4994.7  275.76
    5000  275.76  5004.1  274.32  5007.7  274.32  5022.5  279.32  5027.6  278.16
    5047  280.64  5093.9  281.64  5115.3  280.53  5171.9  280.52  5214.3   282.1
  5263.6  285.72    5292  288.92  5341.4   290.7    5398  295.13  5511.4  301.41
#Mann= 5 ,-1 , 0
  4018.7     .17       0  4825.7     .15       0  4990.1     .09       0
  5022.5     .15       0  5263.6     .17       0
#XS Ineff= 2 , 0
       0  4660.7  282.95  5093.9       0  281.64
Permanent Ineff=
       F       F
Bank Sta=4990.1,5022.5
XS Rating Curve= 0 ,0
Exp/Cntr=0.3,0.1

Type RM Length L Ch R = 1 ,228     ,0,0,0
BEGIN DESCRIPTION:
Conroe Lake 110 1.5
END DESCRIPTION:
XS GIS Cut Line= 3
      3740279.93     10177140.24      3740909.08     10176246.84
      3741271.42     10175270.83
#Sta/Elev= 30
  3907.3  307.82  3955.2  305.01  3991.9  304.87  4034.3  301.28    4192  296.26
  4343.5  287.53  4501.2  282.45  4798.5  279.81  4870.3  279.36  4911.5  279.14
  4938.4  279.79  4974.1   278.5  4982.6  274.11  4992.8  272.52  5005.8  274.84
  5011.2  273.81 5023.29  278.48  5036.2  280.33  5041.5  278.98  5096.9  279.28
    5188  277.21  5293.5  277.27  5445.3  278.77  5592.8  282.54  5666.9   281.4
    5733  283.39  5849.1  290.99  5870.9  291.31  5966.2  297.65  6041.1  300.63
#Mann= 7 ,-1 , 0
  3907.3     .17       0  4798.5     .15       0  4870.3     .17       0
  4911.5     .15       0  4974.1     .09       0 5023.29     .15       0
  5870.9     .17       0
#XS Ineff= 4 ,-1
  4701.3  4623.1  281.52  4774.7  4709.4  280.41  4938.4  4816.5  279.79
  5036.2  5464.8  280.33
Permanent Ineff=
       F       F       F       T
Bank Sta=4974.1,5023.29
XS Rating Curve= 0 ,0
Exp/Cntr=0.3,0.1

Chan Stop Cuts=-1
Use User Specified Reach Order=0
Composite Channel Slope=5