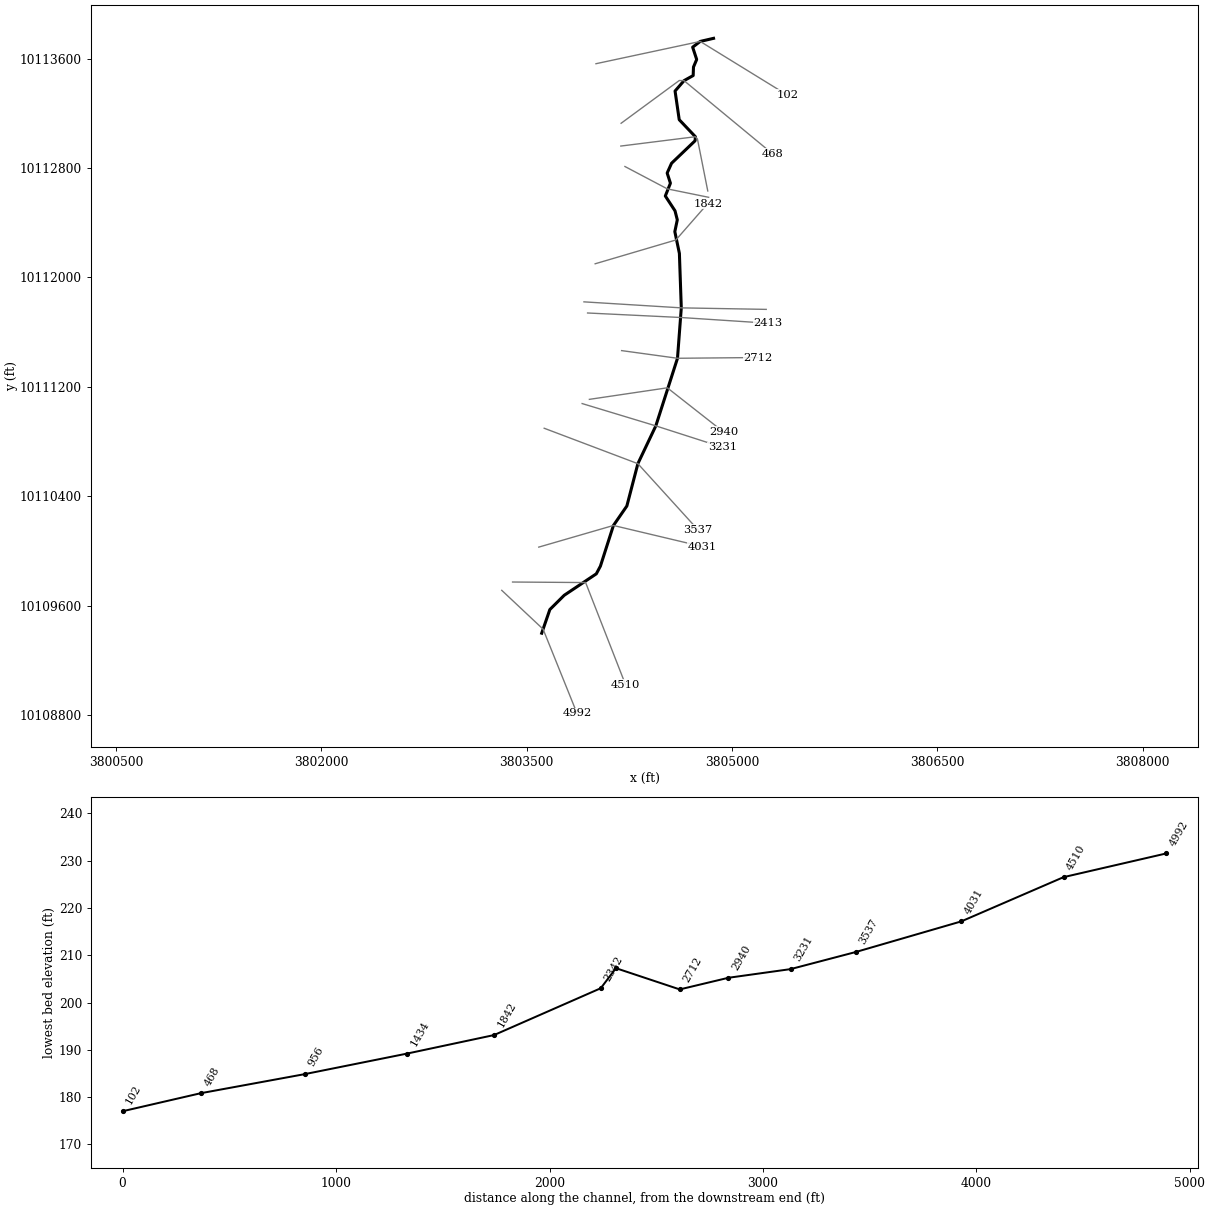
--- Conroe Lake 115.prj (project) ---

Proj Title=Conroe Lake 115 Base Level Engineering
Current Plan=p01
Default Exp/Contr=0.3,0.1
English Units
Geom File=g01
Flow File=f01
Flow File=f02
Plan File=p01
Y Axis Title=Elevation
X Axis Title(PF)=Main Channel Distance
X Axis Title(XS)=Station
BEGIN DESCRIPTION:
Conroe Lake 115
END DESCRIPTION:
DSS Export Rating Curves= 0
DSS Export Rating Curve Sorted= 0
DSS Export Volume Flow Curves= 0
DXF OffsetX= 0
DXF OffsetY= 0
DXF ScaleX= 1
DXF ScaleY= 10

--- Conroe Lake 115.p01 (plan) ---

Plan Title=Multiple Run
Short Identifier=Multiple
Geom File=g01
Flow File=f01
Subcritical Flow
K Sum by GR= 0
Std Step Tol= 0.01
Critical Tol= 0.01
Num of Std Step Trials= 20
Max Error Tol= 0.3
Flow Tol Ratio= 0.001
Split Flow NTrial= 30
Split Flow Tol= 0.02
Split Flow Ratio= 0.02
Log Output Level= 0
Friction Slope Method= 1
Unsteady Friction Slope Method= 2
Unsteady Bridges Friction Slope Method= 1
Parabolic Critical Depth
Global Vel Dist=  1 , 1 , 1
Global Log Level= 0
CheckData=True
Encroach Param= -1, 0, 0, 0
BEGIN DESCRIPTION:
Multiple Run
END DESCRIPTION:

--- Conroe Lake 115.f01 (steady flow) ---

Flow Title=Multiple
Program Version=4.10
Number of Profiles= 7
Profile Names=10-year,25-year,50-year,1pct_min,100-year,1pct_plu,500-year
River Rch & RM=Conroe Lake 115,Reach-1         ,4992
     221     278     359     153     463    1398     791
River Rch & RM=Conroe Lake 115,Reach-1         ,4031
     543     730     982     436    1317    3977    2439
Boundary for River Rch & Prof#=Conroe Lake 115,Reach-1         , 1
Up Type= 0
Dn Type= 3
Dn Slope=0.02
Boundary for River Rch & Prof#=Conroe Lake 115,Reach-1         , 2
Up Type= 0
Dn Type= 3
Dn Slope=0.02
Boundary for River Rch & Prof#=Conroe Lake 115,Reach-1         , 3
Up Type= 0
Dn Type= 3
Dn Slope=0.02
Boundary for River Rch & Prof#=Conroe Lake 115,Reach-1         , 4
Up Type= 0
Dn Type= 3
Dn Slope=0.02
Boundary for River Rch & Prof#=Conroe Lake 115,Reach-1         , 5
Up Type= 0
Dn Type= 3
Dn Slope=0.02
Boundary for River Rch & Prof#=Conroe Lake 115,Reach-1         , 6
Up Type= 0
Dn Type= 3
Dn Slope=0.02
Boundary for River Rch & Prof#=Conroe Lake 115,Reach-1         , 7
Up Type= 0
Dn Type= 3
Dn Slope=0.02
DSS Import GetInterval= 0
DSS Import GetPeak= 0
DSS Import FillOption= 0

--- Conroe Lake 115.f02 (steady flow) ---

Flow Title=Orig_BLE_Flow
Program Version=4.10
Number of Profiles= 7
Profile Names=10-year,25-year,50-year,1pct_min,100-year,1pct_plu,500-year
River Rch & RM=Conroe Lake 115,Reach-1         ,4992
     221     273     312     118     356    1075     460
River Rch & RM=Conroe Lake 115,Reach-1         ,4031
     543     716     854     335    1013    3058    1418
Boundary for River Rch & Prof#=Conroe Lake 115,Reach-1         , 1
Up Type= 0
Dn Type= 3
Dn Slope=0.01
Boundary for River Rch & Prof#=Conroe Lake 115,Reach-1         , 2
Up Type= 0
Dn Type= 3
Dn Slope=0.01
Boundary for River Rch & Prof#=Conroe Lake 115,Reach-1         , 3
Up Type= 0
Dn Type= 3
Dn Slope=0.01
Boundary for River Rch & Prof#=Conroe Lake 115,Reach-1         , 4
Up Type= 0
Dn Type= 3
Dn Slope=0.01
Boundary for River Rch & Prof#=Conroe Lake 115,Reach-1         , 5
Up Type= 0
Dn Type= 3
Dn Slope=0.01
Boundary for River Rch & Prof#=Conroe Lake 115,Reach-1         , 6
Up Type= 0
Dn Type= 3
Dn Slope=0.01
Boundary for River Rch & Prof#=Conroe Lake 115,Reach-1         , 7
Up Type= 0
Dn Type= 3
Dn Slope=0.01
DSS Import GetInterval= 0
DSS Import GetPeak= 0
DSS Import FillOption= 0

--- Conroe Lake 115.g01 (geometry) ---

Geom Title=Existing Conditions
Program Version=4.10

River Reach=Conroe Lake 115 ,Reach-1
Reach XY= 30
      3803609.77     10109397.59      3803669.26     10109570.47
      3803774.46     10109675.07      3804008.72     10109831.71
      3804038.68     10109888.06      3804133.84     10110185.48
      3804231.93     10110327.85       3804312.4     10110637.48
      3804443.54     10110913.96      3804601.88      10111408.4
      3804629.65     10111777.15      3804615.77     10112175.76
      3804582.43     10112334.79      3804600.49      10112420.9
      3804583.82     10112486.87      3804512.97     10112595.34
       3804550.3     10112689.09      3804526.43     10112763.31
      3804558.55     10112834.92      3804730.42     10112999.42
      3804732.59     10113028.93      3804614.54      10113153.5
      3804584.15     10113363.13      3804649.69     10113439.09
      3804716.53     10113476.41       3804718.7     10113538.48
      3804742.14     10113594.04      3804712.63     10113683.88
      3804767.75     10113725.98      3804865.43     10113748.58

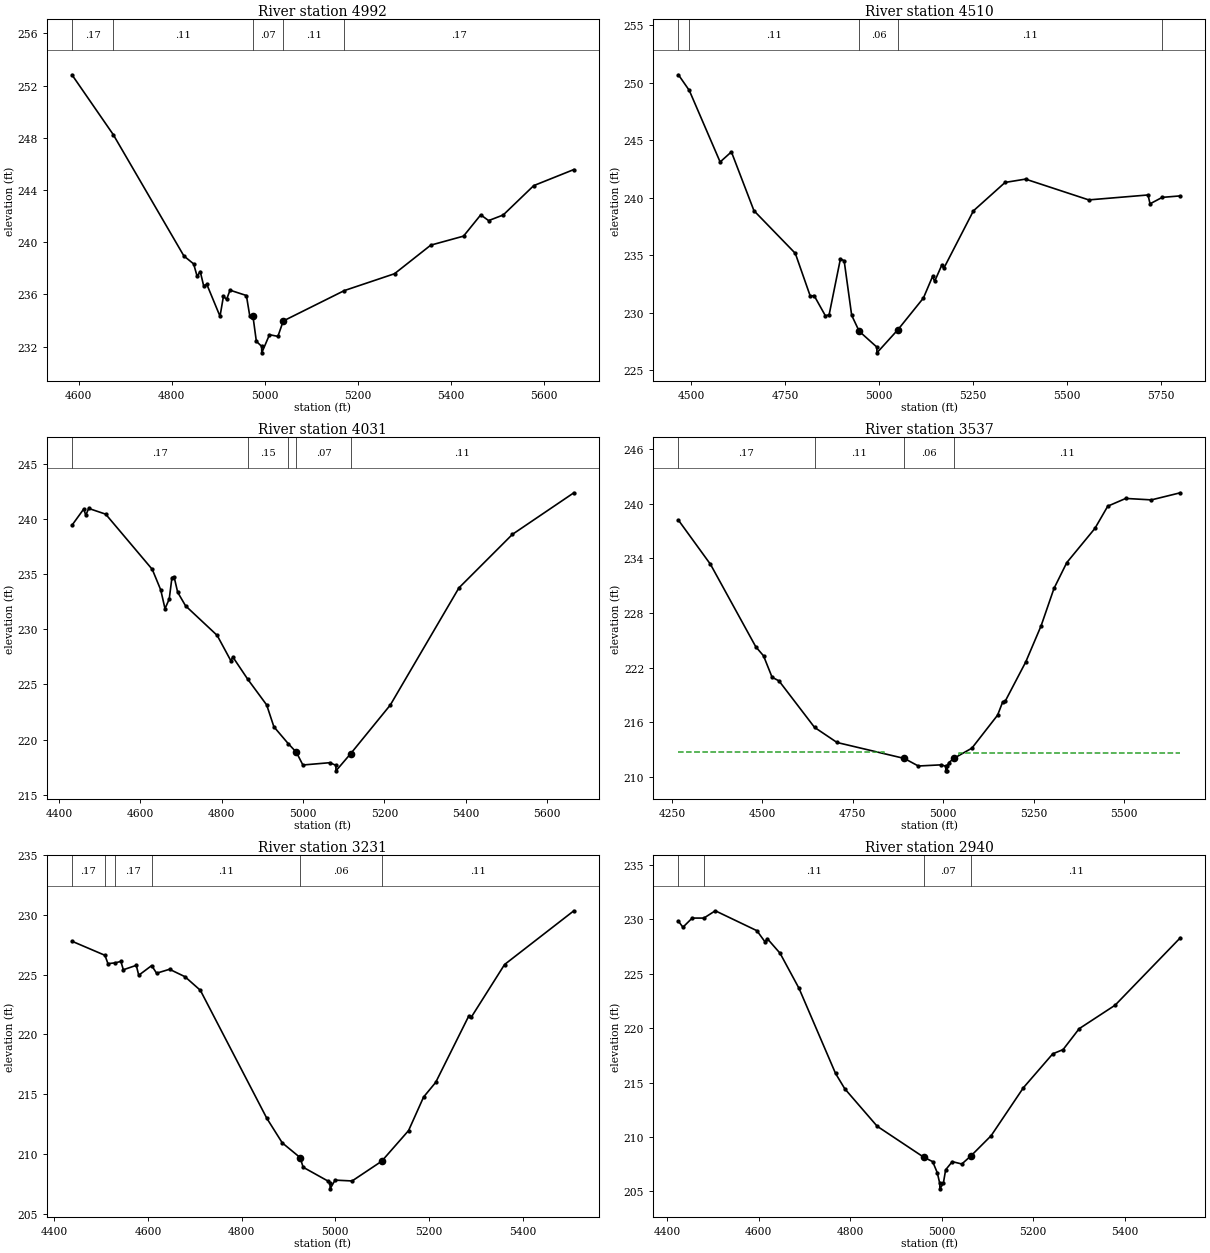
Type RM Length L Ch R = 1 ,4992    ,482,482,482
BEGIN DESCRIPTION:
Conroe Lake 115 12.0
END DESCRIPTION:
XS GIS Cut Line= 3
      3803317.85     10109711.08      3803619.78     10109427.24
      3803867.84      10108811.1
#Sta/Elev= 30
  4585.6  252.83  4674.3  248.25  4826.2  238.95  4847.2  238.34  4854.5   237.4
  4861.3  237.76  4868.6  236.67  4875.5  236.77  4903.8  234.33  4911.1  235.85
    4918  235.63  4925.3  236.33  4960.5  235.92  4967.8  234.34  4974.6  234.33
  4981.9  232.41  4993.2  232.03  4993.5  231.53  5010.1  232.92  5028.2  232.79
  5039.7  233.97    5171   236.3  5278.8  237.59  5356.7  239.78  5427.1  240.47
  5464.1   242.1    5481  241.66  5512.4  242.09    5578  244.34  5664.2  245.57
#Mann= 5 ,-1 , 0
  4585.6     .17       0  4674.3     .11       0  4974.6     .07       0
  5039.7     .11       0    5171     .17       0
#XS Ineff= 2 , 0
       0  4925.3  236.33               0
Permanent Ineff=
       F       F
Bank Sta=4974.6,5039.7
XS Rating Curve= 0 ,0
Exp/Cntr=0.3,0.1

Type RM Length L Ch R = 1 ,4510    ,479,479,479
BEGIN DESCRIPTION:
Conroe Lake 115 11.0
END DESCRIPTION:
XS GIS Cut Line= 3
      3803396.83     10109771.85      3803930.71     10109767.95
      3804222.22     10109021.23
#Sta/Elev= 30
  4466.1  250.71    4495  249.35  4577.1  243.12  4607.1     244  4667.1  238.88
  4777.1  235.17  4817.1  231.43  4827.1   231.5  4857.1  229.74  4867.1  229.82
  4897.1  234.68  4907.1  234.53  4927.1  229.78  4947.1  228.39  4994.1  227.01
  4994.3  226.51  5050.3  228.53    5118  231.28  5142.5  233.17  5147.8  232.73
    5167  234.15  5172.3  233.87  5251.1  238.87  5335.3  241.34  5389.7  241.63
    5558  239.82  5715.7  240.25    5721  239.48  5753.4  240.04  5801.6  240.17
#Mann= 5 ,-1 , 0
  4466.1     .17       0    4495     .11       0  4947.1     .06       0
  5050.3     .11       0  5753.4     .17       0
#XS Ineff= 2 , 0
       0  4897.1  234.68               0
Permanent Ineff=
       F       F
Bank Sta=4947.1,5050.3
XS Rating Curve= 0 ,0
Exp/Cntr=0.3,0.1

Type RM Length L Ch R = 1 ,4031    ,494,494,494
BEGIN DESCRIPTION:
Conroe Lake 115 10.0
END DESCRIPTION:
XS GIS Cut Line= 3
      3803588.24     10110027.17      3804133.84     10110185.48
       3804781.3     10110031.59
#Sta/Elev= 30
  4431.9  239.44  4460.7  240.91  4465.9  240.36  4473.1  240.97  4514.8  240.45
  4629.3  235.44  4650.2  233.57  4660.6  231.87    4671  232.75  4677.7   234.7
  4682.9  234.77  4691.8  233.36  4711.2  232.13  4788.8  229.45  4822.3  227.16
  4827.5  227.48    4864  225.47  4910.5  223.14  4928.2  221.16  4963.2  219.64
  4983.4  218.85  4999.5  217.69  5065.8   217.9  5080.6  217.66  5080.8  217.16
  5117.2  218.73  5214.3  223.13    5383  233.76  5514.6  238.62  5665.5  242.39
#Mann= 5 ,-1 , 0
  4431.9     .17       0    4864     .15       0  4963.2     .11       0
  4983.4     .07       0  5117.2     .11       0
Bank Sta=4983.4,5117.2
XS Rating Curve= 0 ,0
Exp/Cntr=0.3,0.1

Type RM Length L Ch R = 1 ,3537    ,306,306,306
BEGIN DESCRIPTION:
Conroe Lake 115 9.0
END DESCRIPTION:
XS GIS Cut Line= 3
      3803627.91     10110896.63       3804312.4     10110637.48
      3804752.68     10110152.66
#Sta/Elev= 30
  4268.1   238.2  4356.7  233.35  4481.9   224.3  4503.3  223.31  4526.9  220.96
    4546  220.56  4644.2  215.46  4706.4   213.8  4892.3  212.05    4931  211.22
  4994.9  211.35  5006.7  211.19  5006.9  210.69  5010.4  210.69  5010.7  211.19
  5015.5   211.6  5029.7  212.07    5079  213.18    5150   216.8  5164.1  218.25
  5170.9  218.32  5227.7  222.63  5270.2   226.6  5305.8   230.7  5341.2  233.54
  5418.9  237.29  5454.4  239.73  5504.1  240.58    5575  240.42  5654.9   241.2
#Mann= 4 ,-1 , 0
  4268.1     .17       0  4644.2     .11       0  4892.3     .06       0
  5029.7     .11       0
#XS Ineff= 2 , 0
       0  4837.3  212.74  5043.9       0  212.66
Permanent Ineff=
       F       F
Bank Sta=4892.3,5029.7
XS Rating Curve= 0 ,0
Exp/Cntr=0.3,0.1

Type RM Length L Ch R = 1 ,3231    ,291,291,291
BEGIN DESCRIPTION:
Conroe Lake 115 8.0
END DESCRIPTION:
XS GIS Cut Line= 3
      3803905.23     10111077.13      3804443.54     10110913.96
      3804928.78     10110757.96
#Sta/Elev= 30
  4437.5  227.81    4508  226.63  4514.4  225.93  4530.1     226    4542  226.12
  4547.3  225.42  4574.9  225.79  4580.2  224.96  4607.8  225.77  4618.3  225.13
    4646  225.46  4678.9  224.84  4711.8   223.7  4853.9  212.97  4886.8  210.92
  4924.9  209.69  4931.4  208.88  4983.6  207.74  4988.8  207.57    4989  207.07
  4999.6   207.8    5036  207.73  5099.1  209.38  5156.6  211.95  5188.7  214.76
  5214.6  215.99    5285  221.53  5290.3  221.43  5361.7  225.86  5509.7  230.36
#Mann= 6 ,-1 , 0
  4437.5     .17       0    4508     .11       0  4530.1     .17       0
  4607.8     .11       0  4924.9     .06       0  5099.1     .11       0
Bank Sta=4924.9,5099.1
XS Rating Curve= 0 ,0
Exp/Cntr=0.3,0.1

Type RM Length L Ch R = 1 ,2940    ,228,228,228
BEGIN DESCRIPTION:
Conroe Lake 115 7.0
END DESCRIPTION:
XS GIS Cut Line= 3
       3803958.1     10111107.95      3804527.57     10111192.43
      3804937.61      10110870.2
#Sta/Elev= 30
  4424.3  229.82  4434.2  229.27  4454.4  230.11    4480  230.11  4504.9  230.78
  4595.9  228.95  4613.5  227.93  4618.6  228.22  4646.5  226.88    4688  223.65
  4767.8  215.84    4788  214.43  4858.8  210.99  4960.8  208.14  4980.1  207.74
  4990.2  206.72  4995.6  205.74  4995.9  205.24  5003.4  205.74  5008.5  206.99
    5023  207.74  5043.8  207.52  5064.6   208.3  5107.9  210.12  5178.5  214.53
  5242.6  217.64  5265.2  218.03  5300.4  219.95    5379  222.11  5521.5   228.3
#Mann= 4 ,-1 , 0
  4424.3     .17       0    4480     .11       0  4960.8     .07       0
  5064.6     .11       0
Bank Sta=4960.8,5064.6
XS Rating Curve= 0 ,0
Exp/Cntr=0.3,0.1

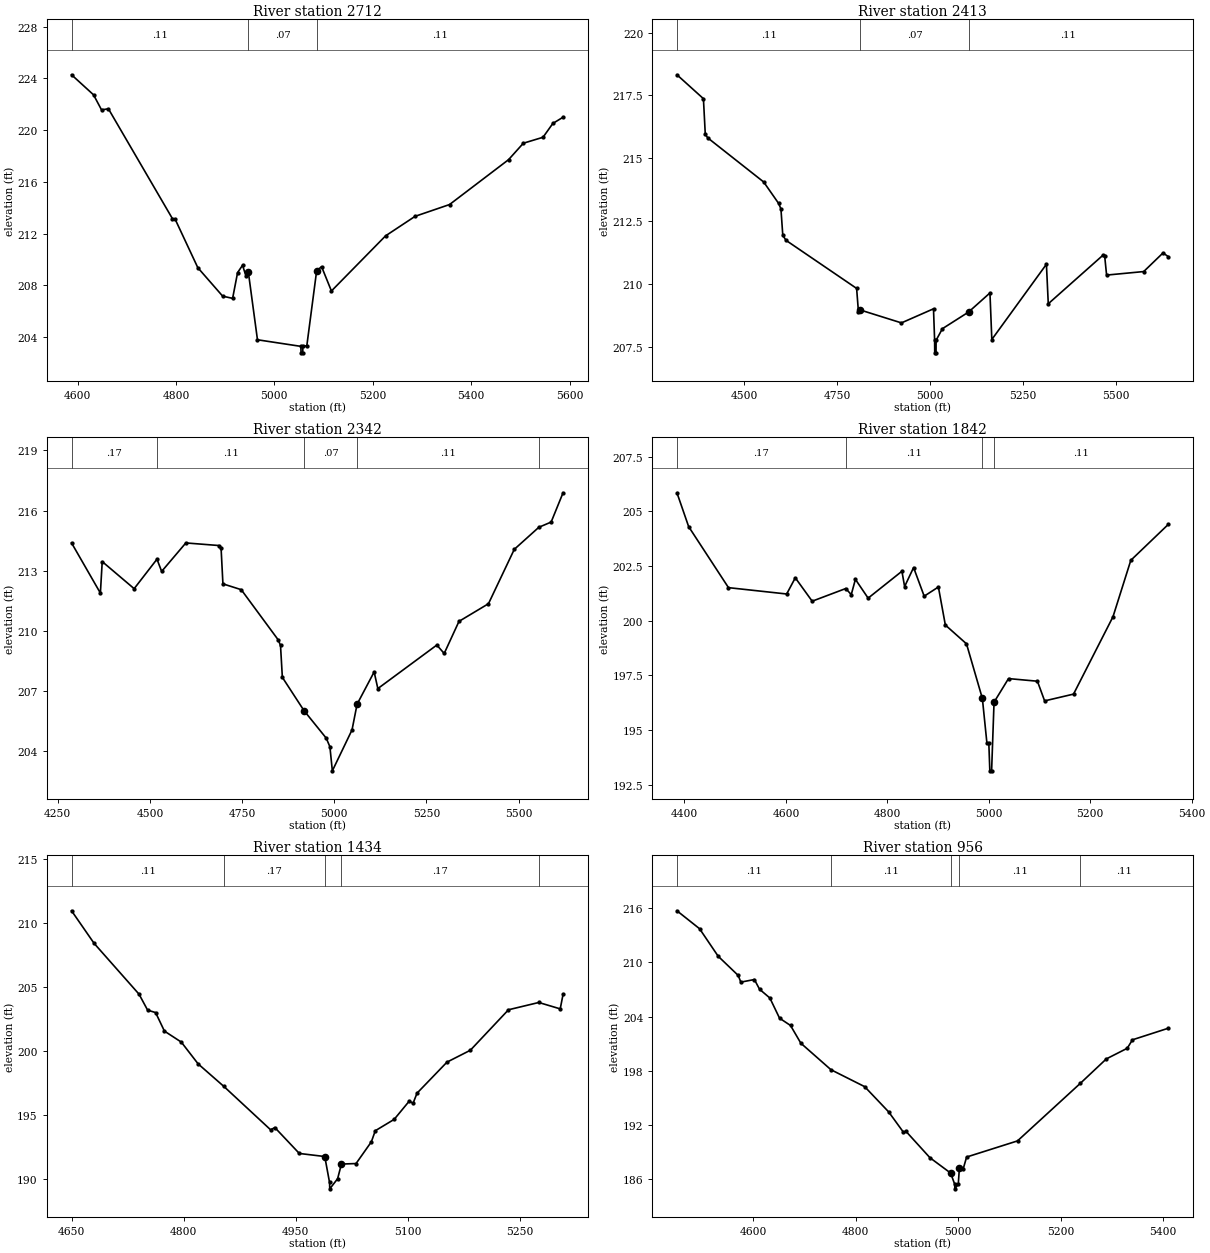
Type RM Length L Ch R = 1 ,2712    ,299,299,299
BEGIN DESCRIPTION:
Conroe Lake 115 6.0
END DESCRIPTION:
XS GIS Cut Line= 3
      3804193.62     10111464.52      3804601.88      10111408.4
      3805188.55      10111413.9
#Sta/Elev= 30
  4587.9  224.27  4632.6  222.72  4648.8  221.56  4662.8  221.64  4792.9  213.15
    4798  213.14  4844.5  209.36    4895  207.16  4915.2  206.99  4925.3  208.98
  4935.4  209.55    4942  208.75  4947.1  209.04  4965.7  203.79    5054  203.28
  5054.2  202.78  5057.7  202.78    5058  203.28    5066  203.33    5086  209.13
    5096  209.44    5116  207.56    5226  211.82    5286  213.33    5356  214.24
    5476  217.71    5506  218.98    5546  219.44    5566  220.51  5586.7  220.99
#Mann= 3 , 0 , 0
  4587.9     .11       0  4947.1     .07       0    5086     .11       0
#XS Ineff= 2 , 0
       0  4935.4  209.55    5096       0  209.44
Permanent Ineff=
       F       F
Bank Sta=4947.1,5086
XS Rating Curve= 0 ,0
Exp/Cntr=0.3,0.1

Type RM Length L Ch R = 1 ,2413    ,71,71,71
BEGIN DESCRIPTION:
Conroe Lake 115 5.5
END DESCRIPTION:
XS GIS Cut Line= 3
      3803944.91     10111739.67      3804625.02     10111706.72
      3805264.25     10111664.92
#Sta/Elev= 30
  4319.1  218.32  4390.3  217.37  4395.3  215.95  4402.1  215.81  4552.3  214.06
  4592.4  213.21  4598.7  212.99  4603.7  211.94  4612.4  211.74  4802.2  209.83
  4807.2  208.88  4812.6  208.97  4922.7  208.46  5008.9  209.02  5011.9  207.77
  5012.2  207.27  5015.7  207.27  5015.9  207.77  5032.9  208.23  5103.1  208.89
  5160.7  209.65  5165.7   207.8  5312.5  210.79  5317.5  209.22  5463.8  211.14
  5469.2  211.11  5474.3  210.36  5574.1   210.5    5626  211.24  5640.6  211.09
#Mann= 3 , 0 , 0
  4319.1     .11       0  4812.6     .07       0  5103.1     .11       0
#XS Ineff= 2 ,-1
  5160.7  5312.5  209.65  5312.5  5463.8  210.79
Permanent Ineff=
       F       F
Bank Sta=4812.6,5103.1
XS Rating Curve= 0 ,0
Exp/Cntr=0.3,0.1

Type RM Length L Ch R = 1 ,2342    ,500,500,500
BEGIN DESCRIPTION:
Conroe Lake 115 5.0
END DESCRIPTION:
XS GIS Cut Line= 3
      3803918.41     10111821.11      3804629.65     10111777.15
      3805250.16     10111766.08
#Sta/Elev= 30
  4287.4  214.39  4365.6  211.89  4370.6  213.46  4457.2  212.11  4519.1  213.58
  4531.8  212.97  4597.4  214.39  4687.6  214.26    4693  214.13    4698  212.35
  4747.7  212.06  4847.9  209.56  4854.2  209.28  4859.2  207.69    4918  206.03
  4978.2  204.66  4988.2  204.23  4994.8  203.03  5048.2  205.07  5061.9  206.35
  5108.2  207.96  5118.2  207.13  5278.2   209.3  5298.2  208.88  5338.3  210.48
  5418.3  211.36  5488.3  214.07  5554.9  215.17  5588.3  215.43  5620.6  216.89
#Mann= 5 ,-1 , 0
  4287.4     .17       0  4519.1     .11       0    4918     .07       0
  5061.9     .11       0  5554.9     .17       0
#XS Ineff= 2 , 0
       0                  5108.2       0  207.96
Permanent Ineff=
       F       F
Bank Sta=4918,5061.9
XS Rating Curve= 0 ,0
Exp/Cntr=0.3,0.1

Type RM Length L Ch R = 1 ,1842    ,408,408,408
BEGIN DESCRIPTION:
Conroe Lake 115 4.0
END DESCRIPTION:
XS GIS Cut Line= 3
      3804000.42     10112099.62      3804590.07     10112273.68
       3804823.1     10112540.29
#Sta/Elev= 30
  4385.2  205.85  4408.3   204.3  4486.8  201.51  4601.5  201.22  4618.5  201.96
  4651.8  200.89    4718  201.47  4728.8  201.19    4737  201.89  4762.1  201.03
  4828.7  202.26    4834  201.56  4851.7  202.43  4872.6  201.12  4900.6  201.54
  4914.3   199.8    4956  198.94  4987.3  196.44  4996.2  194.41    5000  194.41
    5002  193.13  5005.5  193.13  5010.3  196.27  5038.8  197.35  5095.8  197.23
    5110  196.33    5167  196.64  5244.8  200.18  5279.9  202.76  5354.1  204.41
#Mann= 4 ,-1 , 0
  4385.2     .17       0    4718     .11       0  4987.3     .09       0
  5010.3     .11       0
Bank Sta=4987.3,5010.3
XS Rating Curve= 0 ,0
Exp/Cntr=0.3,0.1

Type RM Length L Ch R = 1 ,1434    ,478,478,478
BEGIN DESCRIPTION:
Conroe Lake 115 3.0
END DESCRIPTION:
XS GIS Cut Line= 3
      3804217.88     10112811.05      3804527.73     10112647.42
      3804829.52     10112585.91
#Sta/Elev= 30
  4649.6  210.98  4679.8  208.43    4740  204.45  4751.5   203.2  4762.2  203.01
    4774  201.56  4796.6   200.7  4819.2  198.99  4853.6  197.23  4916.3  193.83
  4921.9  194.01  4954.7  191.98  4988.8  191.74  4995.2  189.71  4995.5  189.21
    5006     190  5011.1  191.15  5030.7  191.19  5051.2  192.89  5056.5  193.76
  5081.8  194.65    5102  196.08  5107.1  195.91  5112.4   196.7  5152.5  199.13
  5183.8  200.06  5234.9  203.23  5275.5   203.8  5304.2   203.3    5308  204.43
#Mann= 5 ,-1 , 0
  4649.6     .11       0  4853.6     .17       0  4988.8     .09       0
  5011.1     .17       0  5275.5     .11       0
Bank Sta=4988.8,5011.1
XS Rating Curve= 0 ,0
Exp/Cntr=0.3,0.1

Type RM Length L Ch R = 1 ,956     ,488,488,488
BEGIN DESCRIPTION:
Conroe Lake 115 2.0
END DESCRIPTION:
XS GIS Cut Line= 4
      3804187.94     10112960.74      3804732.59     10113028.93
      3804747.59       10113013.      3804823.11      10112632.2
#Sta/Elev= 30
  4451.1  215.74  4495.2  213.75  4531.6  210.69  4570.7  208.56  4575.7  207.82
  4602.2  208.11  4612.3  207.03  4632.4  206.06  4651.3  203.82  4672.7  203.01
  4692.9  201.04  4751.6   198.1  4817.4  196.22  4864.2  193.42  4892.9  191.17
    4898  191.26  4944.8  188.33  4985.1  186.63  4993.1  185.38  4993.3  184.88
    5000  185.38  5002.2  187.19  5009.4  187.05  5016.3  188.41  5115.6   190.2
  5238.2  196.59  5288.9   199.3  5329.7  200.48  5339.9  201.42  5410.1  202.71
#Mann= 5 ,-1 , 0
  4451.1     .11       0  4751.6     .11       0  4985.1     .09       0
  5002.2     .11       0  5238.2     .11       0
Bank Sta=4985.1,5002.2
XS Rating Curve= 0 ,0
Exp/Cntr=0.3,0.1

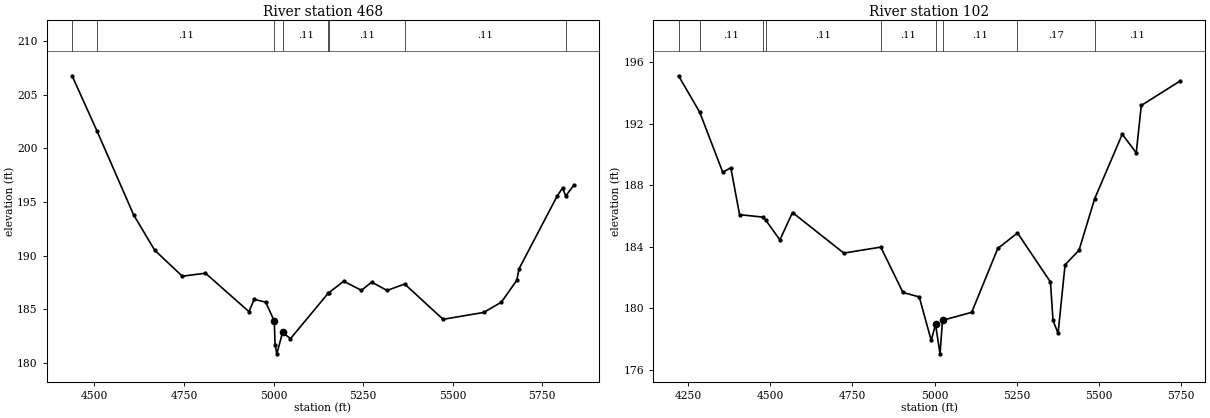
Type RM Length L Ch R = 1 ,468     ,366,366,366
BEGIN DESCRIPTION:
Conroe Lake 115 1.0
END DESCRIPTION:
XS GIS Cut Line= 4
        3804190.     10113127.37      3804614.78     10113440.08
      3804649.69     10113439.09      3805295.81     10112904.66
#Sta/Elev= 30
  4437.6  206.77  4506.8  201.65  4609.5   193.8  4668.1  190.51  4745.4  188.08
  4810.1  188.36  4931.6  184.77  4945.8  185.92  4978.2  185.66  5002.1   183.9
  5004.4  181.67  5009.2  180.84  5025.2  182.83  5047.4  182.26  5153.4  186.52
  5154.9  186.55  5195.9  187.61  5245.4  186.76    5274  187.53    5317  186.75
  5366.2  187.35  5473.4  184.06  5586.7   184.7  5636.2  185.66  5679.2   187.7
  5685.6  188.78  5792.5  195.59  5806.8   196.3    5816  195.56  5838.5  196.58
#Mann= 8 ,-1 , 0
  4437.6     .17       0  4506.8     .11       0  5002.1     .07       0
  5025.2     .11       0  5153.4     .11       0  5154.9     .11       0
  5366.2     .11       0    5816     .11       0
Bank Sta=5002.1,5025.2
XS Rating Curve= 0 ,0
Exp/Cntr=0.3,0.1

Type RM Length L Ch R = 1 ,102     ,0,0,0
BEGIN DESCRIPTION:
Conroe Lake 115 1.5
END DESCRIPTION:
XS GIS Cut Line= 3
      3804006.39     10113563.01      3804767.75     10113725.98
      3805404.08     10113333.95
#Sta/Elev= 30
  4221.4  195.11  4285.8  192.74  4355.8  188.84  4380.4  189.13    4407  186.08
  4478.1  185.92  4485.9  185.74  4529.7  184.44    4568  186.22    4724  183.58
  4836.5  183.97  4903.9  181.02  4953.4  180.73  4989.9   177.9    5003  178.95
  5016.6  177.03  5024.2  179.21    5113  179.73  5192.2  183.88  5252.2  184.89
  5352.5   181.7  5360.2   179.2  5375.6  178.37  5396.9  182.82  5439.4  183.77
  5486.8  187.11  5570.8  191.31  5613.3   190.1  5628.7  193.18  5747.4  194.78
#Mann= 9 ,-1 , 0
  4221.4     .17       0  4285.8     .11       0  4478.1     .17       0
  4485.9     .11       0  4836.5     .11       0    5003     .07       0
  5024.2     .11       0  5252.2     .17       0  5486.8     .11       0
Bank Sta=5003,5024.2
XS Rating Curve= 0 ,0
Exp/Cntr=0.3,0.1

Chan Stop Cuts=-1
Use User Specified Reach Order=0
Composite Channel Slope=5