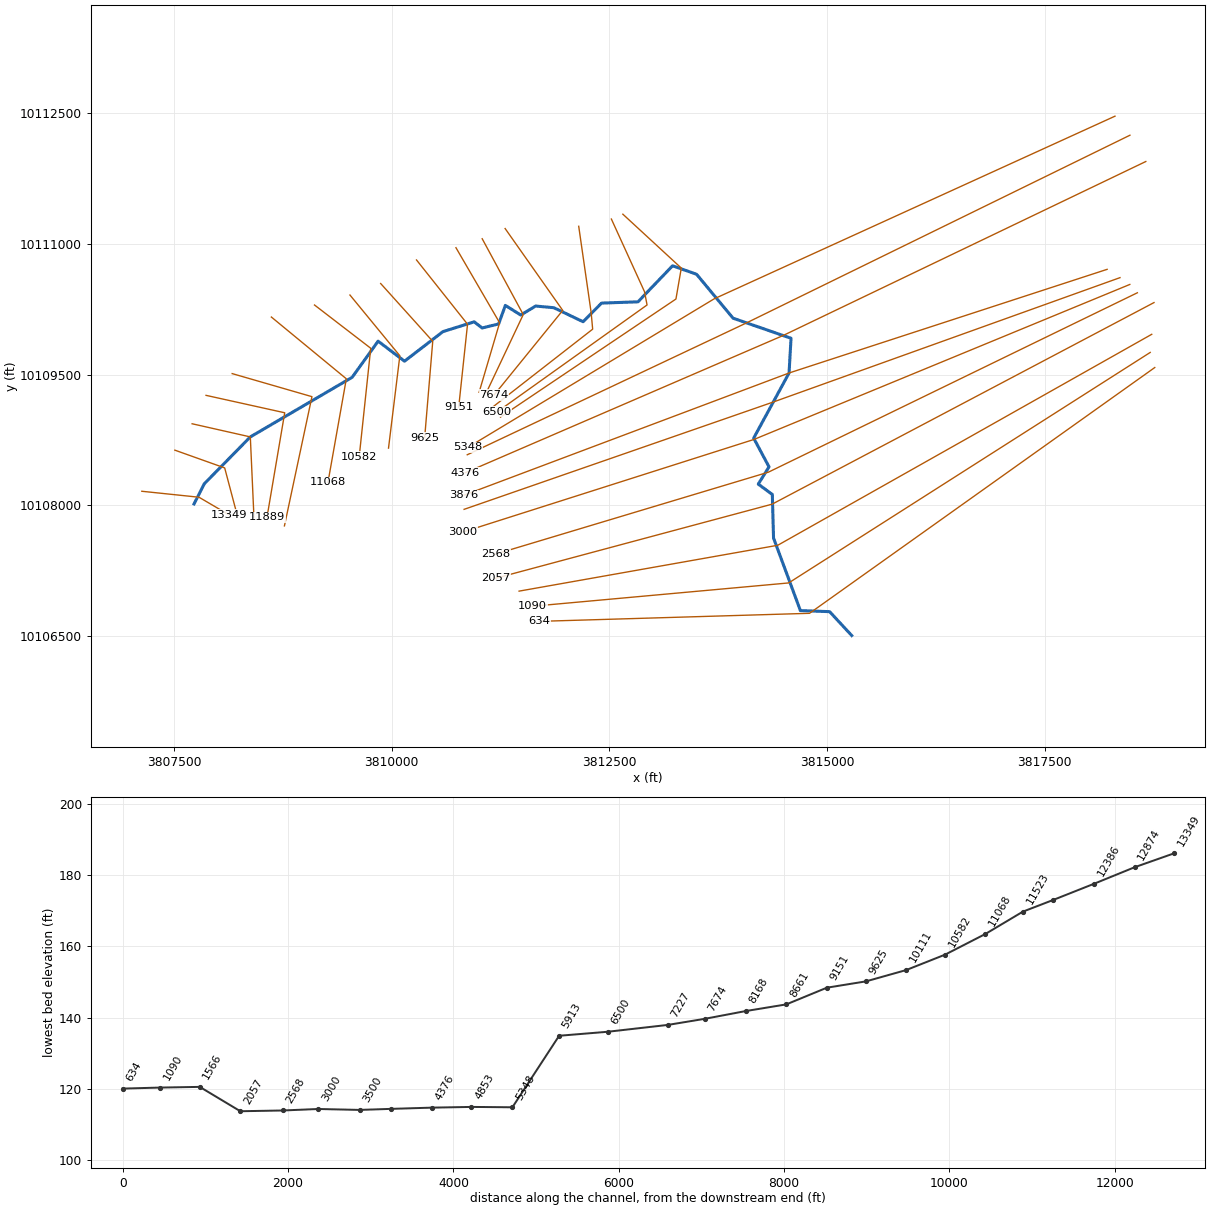
--- Conroe Lake 117.prj (project) ---

Proj Title=Conroe Lake 117 Base Level Engineering
Current Plan=p01
Default Exp/Contr=0.3,0.1
English Units
Geom File=g01
Flow File=f01
Flow File=f02
Plan File=p01
Y Axis Title=Elevation
X Axis Title(PF)=Main Channel Distance
X Axis Title(XS)=Station
BEGIN DESCRIPTION:
Conroe Lake 117
END DESCRIPTION:
DSS Export Rating Curves= 0
DSS Export Rating Curve Sorted= 0
DSS Export Volume Flow Curves= 0
DXF OffsetX= 0
DXF OffsetY= 0
DXF ScaleX= 1
DXF ScaleY= 10

--- Conroe Lake 117.p01 (plan) ---

Plan Title=Multiple Run
Short Identifier=Multiple
Geom File=g01
Flow File=f01
Subcritical Flow
K Sum by GR= 0
Std Step Tol= 0.01
Critical Tol= 0.01
Num of Std Step Trials= 20
Max Error Tol= 0.3
Flow Tol Ratio= 0.001
Split Flow NTrial= 30
Split Flow Tol= 0.02
Split Flow Ratio= 0.02
Log Output Level= 0
Friction Slope Method= 1
Unsteady Friction Slope Method= 2
Unsteady Bridges Friction Slope Method= 1
Parabolic Critical Depth
Global Vel Dist=  1 , 1 , 1
Global Log Level= 0
CheckData=True
Encroach Param= -1, 0, 0, 0
BEGIN DESCRIPTION:
Multiple Run
END DESCRIPTION:

--- Conroe Lake 117.f01 (steady flow) ---

Flow Title=Multiple
Program Version=4.10
Number of Profiles= 7
Profile Names=10-year,25-year,50-year,1pct_min,100-year,1pct_plu,500-year
River Rch & RM=Conroe Lake 117,Reach-1         ,13349
     780    1063    1443     644    1946    5877    3657
River Rch & RM=Conroe Lake 117,Reach-1         ,3876
    1182    1646    2267    1025    3095    9347    5970
Boundary for River Rch & Prof#=Conroe Lake 117,Reach-1         , 1
Up Type= 0
Dn Type= 3
Dn Slope=0.005
Boundary for River Rch & Prof#=Conroe Lake 117,Reach-1         , 2
Up Type= 0
Dn Type= 3
Dn Slope=0.005
Boundary for River Rch & Prof#=Conroe Lake 117,Reach-1         , 3
Up Type= 0
Dn Type= 3
Dn Slope=0.005
Boundary for River Rch & Prof#=Conroe Lake 117,Reach-1         , 4
Up Type= 0
Dn Type= 3
Dn Slope=0.005
Boundary for River Rch & Prof#=Conroe Lake 117,Reach-1         , 5
Up Type= 0
Dn Type= 3
Dn Slope=0.005
Boundary for River Rch & Prof#=Conroe Lake 117,Reach-1         , 6
Up Type= 0
Dn Type= 3
Dn Slope=0.005
Boundary for River Rch & Prof#=Conroe Lake 117,Reach-1         , 7
Up Type= 0
Dn Type= 3
Dn Slope=0.005
DSS Import GetInterval= 0
DSS Import GetPeak= 0
DSS Import FillOption= 0

--- Conroe Lake 117.f02 (steady flow) ---

Flow Title=Orig_BLE_Flow
Program Version=4.10
Number of Profiles= 7
Profile Names=10-year,25-year,50-year,1pct_min,100-year,1pct_plu,500-year
River Rch & RM=Conroe Lake 117,Reach-1         ,13349
     780    1042    1255     496    1497    4521    2126
River Rch & RM=Conroe Lake 117,Reach-1         ,3876
    1182    1614    1971     789    2381    7192    3471
Boundary for River Rch & Prof#=Conroe Lake 117,Reach-1         , 1
Up Type= 0
Dn Type= 3
Dn Slope=0.005
Boundary for River Rch & Prof#=Conroe Lake 117,Reach-1         , 2
Up Type= 0
Dn Type= 3
Dn Slope=0.005
Boundary for River Rch & Prof#=Conroe Lake 117,Reach-1         , 3
Up Type= 0
Dn Type= 3
Dn Slope=0.005
Boundary for River Rch & Prof#=Conroe Lake 117,Reach-1         , 4
Up Type= 0
Dn Type= 3
Dn Slope=0.005
Boundary for River Rch & Prof#=Conroe Lake 117,Reach-1         , 5
Up Type= 0
Dn Type= 3
Dn Slope=0.005
Boundary for River Rch & Prof#=Conroe Lake 117,Reach-1         , 6
Up Type= 0
Dn Type= 3
Dn Slope=0.005
Boundary for River Rch & Prof#=Conroe Lake 117,Reach-1         , 7
Up Type= 0
Dn Type= 3
Dn Slope=0.005
DSS Import GetInterval= 0
DSS Import GetPeak= 0
DSS Import FillOption= 0

--- Conroe Lake 117.g01 (geometry) ---

Geom Title=Existing Conditions
Program Version=4.10

River Reach=Conroe Lake 117 ,Reach-1
Reach XY= 30
      3807729.65     10108012.42      3807847.84     10108245.27
      3808376.23     10108783.64      3809545.41     10109468.36
       3809843.7      10109883.8      3810146.82     10109653.76
      3810588.49      10109993.4      3810947.08      10110105.9
      3811037.71     10110035.06      3811227.81     10110081.68
      3811304.89      10110294.7      3811481.46     10110184.02
      3811652.81     10110287.41       3811861.4     10110268.14
      3812197.34      10110107.2      3812409.32     10110321.26
      3812827.81     10110335.84      3813224.95     10110749.91
      3813500.73     10110652.51      3813919.48     10110147.82
      3814585.29     10109917.12      3814562.76     10109518.15
      3814156.33     10108769.53      3814332.54     10108439.67
      3814208.96     10108241.12      3814370.58      10108121.9
      3814384.47     10107621.75      3814692.79     10106787.76
      3815028.32     10106775.48      3815282.54     10106501.16

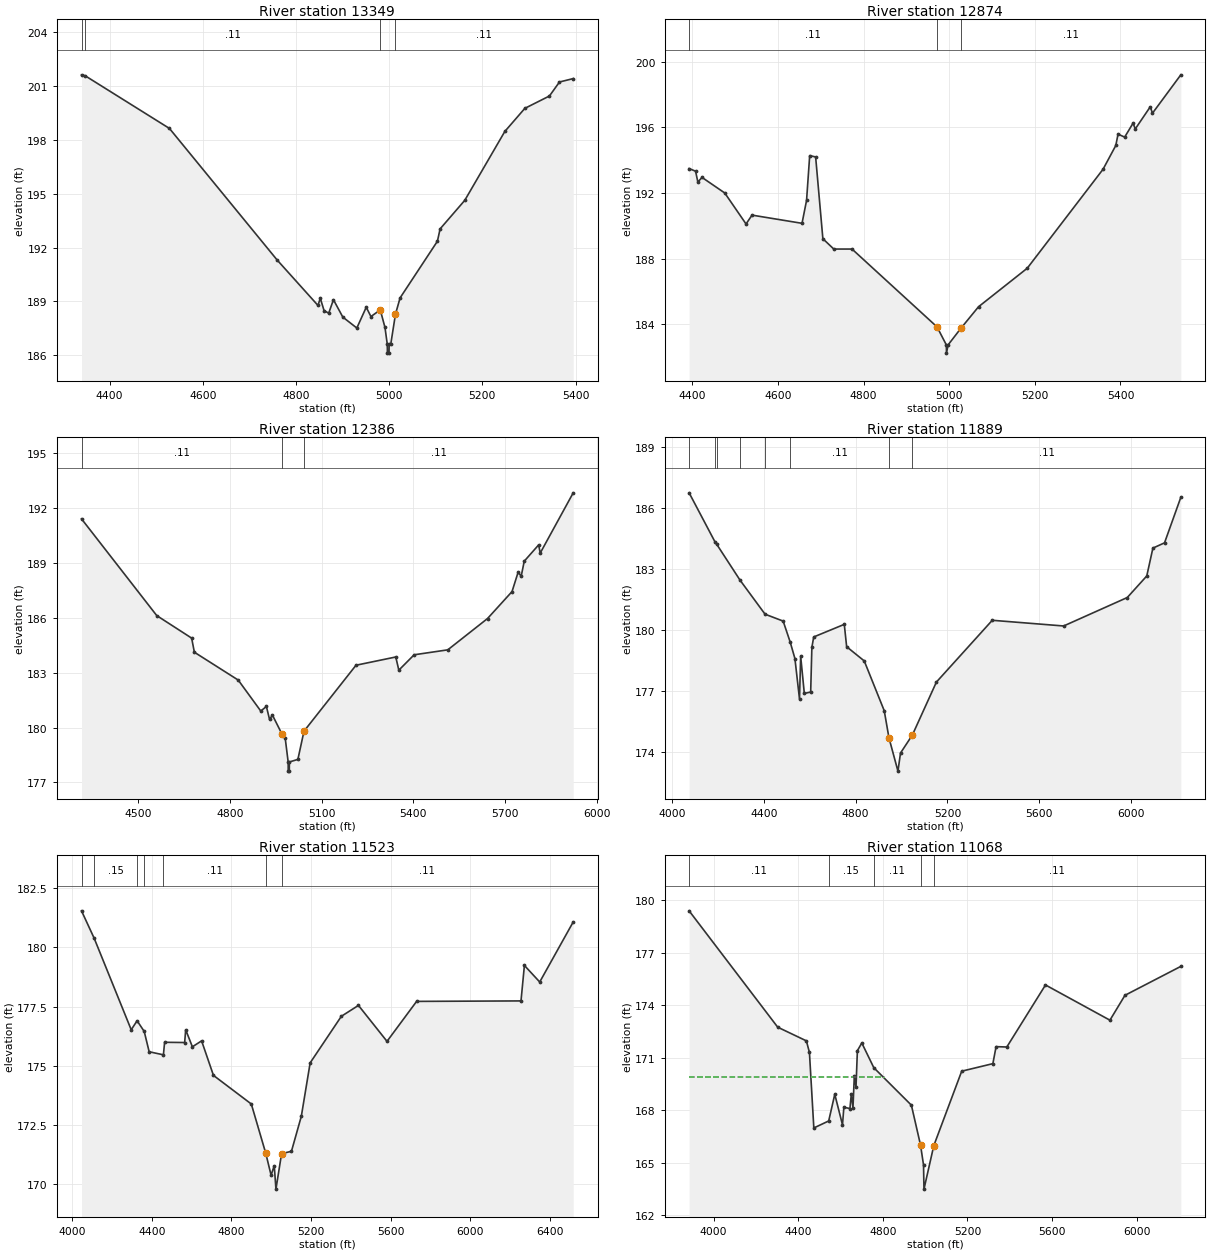
Type RM Length L Ch R = 1 ,13349   ,475,475,475
BEGIN DESCRIPTION:
Conroe Lake 117 22.0
END DESCRIPTION:
XS GIS Cut Line= 3
      3807130.21     10108158.98      3807786.73     10108090.41
      3808127.54     10107890.72
#Sta/Elev= 30
  4339.9  201.63  4347.6  201.58  4528.6  198.64  4759.8   191.3  4847.3  188.77
  4852.3  189.17  4860.4  188.48  4870.4  188.34  4880.5  189.09  4900.6  188.12
  4930.7  187.51  4950.9  188.67  4960.9  188.15    4981  188.52  4991.1  187.54
    4996  186.61  4996.3  186.11  4999.8  186.11    5000  186.61  5003.5  186.61
  5013.6  188.28  5023.5  189.19  5103.6  192.35  5109.4  193.04  5162.3  194.63
  5248.2  198.47  5291.2  199.76    5344  200.45  5365.5  201.23    5395  201.42
#Mann= 4 ,-1 , 0
  4339.9     .17       0  4347.6     .11       0    4981     .06       0
  5013.6     .11       0
Bank Sta=4981,5013.6
XS Rating Curve= 0 ,0
Exp/Cntr=0.3,0.1

Type RM Length L Ch R = 1 ,12874   ,488,488,488
BEGIN DESCRIPTION:
Conroe Lake 117 21.0
END DESCRIPTION:
XS GIS Cut Line= 3
      3807509.39     10108631.38      3808081.87     10108427.22
      3808220.39     10107904.25
#Sta/Elev= 30
  4392.2  193.49  4407.3  193.33  4412.6  192.67  4422.4  192.95  4475.5     192
  4525.2  190.11  4539.2  190.65    4656  190.15  4666.6  191.55  4673.9  194.28
  4687.8   194.2  4704.7  189.21  4730.2  188.58  4772.8  188.58  4971.4  183.83
  4993.2  182.73  4993.5  182.23  4997.2  182.73    5027  183.74  5068.4  185.06
  5182.2  187.41  5359.3  193.45  5389.1   194.9  5394.3  195.59  5409.8  195.41
  5429.4  196.26  5434.6  195.91  5469.6  197.26  5474.8  196.87    5541  199.21
#Mann= 3 , 0 , 0
  4392.2     .11       0  4971.4     .06       0    5027     .11       0
Bank Sta=4971.4,5027
XS Rating Curve= 0 ,0
Exp/Cntr=0.3,0.1

Type RM Length L Ch R = 1 ,12386   ,497,497,497
BEGIN DESCRIPTION:
Conroe Lake 117 20.0
END DESCRIPTION:
XS GIS Cut Line= 3
      3807707.68     10108934.67      3808376.23     10108783.64
      3808417.85     10107861.08
#Sta/Elev= 30
  4314.6  191.39  4560.8  186.11    4675  184.88  4683.9  184.11  4827.4  182.59
  4901.2   180.9  4919.6  181.15  4929.9  180.44  4939.3  180.68  4970.9  179.63
  4981.2  179.41  4990.8  178.12    4991  177.62  4994.5  177.62  4994.8  178.12
  5022.6  178.26  5042.6   179.8  5212.8   183.4  5342.9  183.85  5352.9  183.13
    5403  183.97  5513.1  184.24  5643.2  185.95  5723.3  187.42  5743.3  188.48
  5753.3  188.26  5763.3  189.08  5810.5  189.97  5815.5  189.52  5923.5  192.81
#Mann= 3 , 0 , 0
  4314.6     .11       0  4970.9     .06       0  5042.6     .11       0
Bank Sta=4970.9,5042.6
XS Rating Curve= 0 ,0
Exp/Cntr=0.3,0.1

Type RM Length L Ch R = 1 ,11889   ,366,366,366
BEGIN DESCRIPTION:
Conroe Lake 117 19.0
END DESCRIPTION:
XS GIS Cut Line= 3
      3807867.83     10109261.08      3808771.13     10109060.99
      3808567.85     10107861.09
#Sta/Elev= 30
  4074.8  186.74  4188.8   184.3  4194.4  184.22  4296.3  182.45  4405.6  180.77
  4484.5  180.43  4515.1   179.4  4535.7  178.59  4555.7   176.6  4560.8   178.7
  4576.7  176.87  4604.4  176.94  4609.6  179.14  4617.7  179.65  4750.8  180.27
  4761.1  179.17  4837.8  178.47  4924.9  176.02  4945.4  174.69  4984.6  173.05
  4995.8  173.94  5047.6  174.83  5152.1  177.43  5395.5  180.47  5706.5  180.19
  5983.7  181.59  6068.6  182.65  6095.3  184.02    6146  184.28    6217  186.52
#Mann= 8 ,-1 , 0
  4074.8     .15       0  4188.8     .17       0  4194.4     .15       0
  4296.3     .11       0  4405.6     .15       0  4515.1     .11       0
  4945.4     .06       0  5047.6     .11       0
#XS Ineff= 2 , 0
       0  4750.8  180.27               0
Permanent Ineff=
       F       F
Bank Sta=4945.4,5047.6
XS Rating Curve= 0 ,0
Exp/Cntr=0.3,0.1

Type RM Length L Ch R = 1 ,11523   ,455,455,455
BEGIN DESCRIPTION:
Conroe Lake 117 18.0
END DESCRIPTION:
XS GIS Cut Line= 3
      3808167.82     10109511.08      3809083.96     10109246.07
      3808767.84     10107761.04
#Sta/Elev= 30
  4046.3  181.55    4110  180.39  4296.2  176.52  4325.8   176.9  4361.6  176.45
  4386.4  175.59  4458.1  175.46  4464.1  175.99  4564.9  175.98  4570.1  176.52
  4603.7   175.8  4650.1  176.05  4709.7  174.59    4900  173.38  4972.8  171.29
  4999.4  170.37  5015.3  170.77  5023.8  169.78  5052.2  171.28  5101.8  171.38
  5151.4  172.86  5195.8  175.12  5352.7  177.09  5438.6  177.55  5582.2  176.03
    5731  177.72  6255.8  177.74  6272.9  179.24  6349.9  178.54  6518.3  181.08
#Mann= 7 ,-1 , 0
  4046.3     .11       0    4110     .15       0  4325.8     .11       0
  4361.6     .15       0  4458.1     .11       0  4972.8     .06       0
  5052.2     .11       0
Bank Sta=4972.8,5052.2
XS Rating Curve= 0 ,0
Exp/Cntr=0.3,0.1

Type RM Length L Ch R = 1 ,11068   ,486,486,486
BEGIN DESCRIPTION:
Conroe Lake 117 17.0
END DESCRIPTION:
XS GIS Cut Line= 3
      3808617.87     10110161.06      3809478.75     10109451.52
      3809267.85     10108261.06
#Sta/Elev= 30
  3884.4  179.38  4303.3  172.74  4438.8  171.96  4453.2   171.3    4474  166.99
  4544.3  167.39    4573  168.91  4609.5  167.17    4616  168.17  4644.7   168.1
  4651.2  168.93    4659  168.15  4665.5  169.97  4673.4  169.34  4679.9   171.4
  4700.8  171.84  4757.5  170.43  4935.2  168.29  4978.3  166.02  4992.6  164.88
  4994.7   163.5  5041.1  165.98  5173.1  170.23  5320.4  170.66  5335.6  171.63
  5386.4  171.61  5569.2  175.15  5873.8  173.14  5944.9  174.56    6209  176.21
#Mann= 5 ,-1 , 0
  3884.4     .11       0  4544.3     .15       0  4757.5     .11       0
  4978.3     .06       0  5041.1     .11       0
#XS Ineff= 2 , 0
       0  4807.6  169.89               0
Permanent Ineff=
       F       F
Bank Sta=4978.3,5041.1
XS Rating Curve= 0 ,0
Exp/Cntr=0.3,0.1

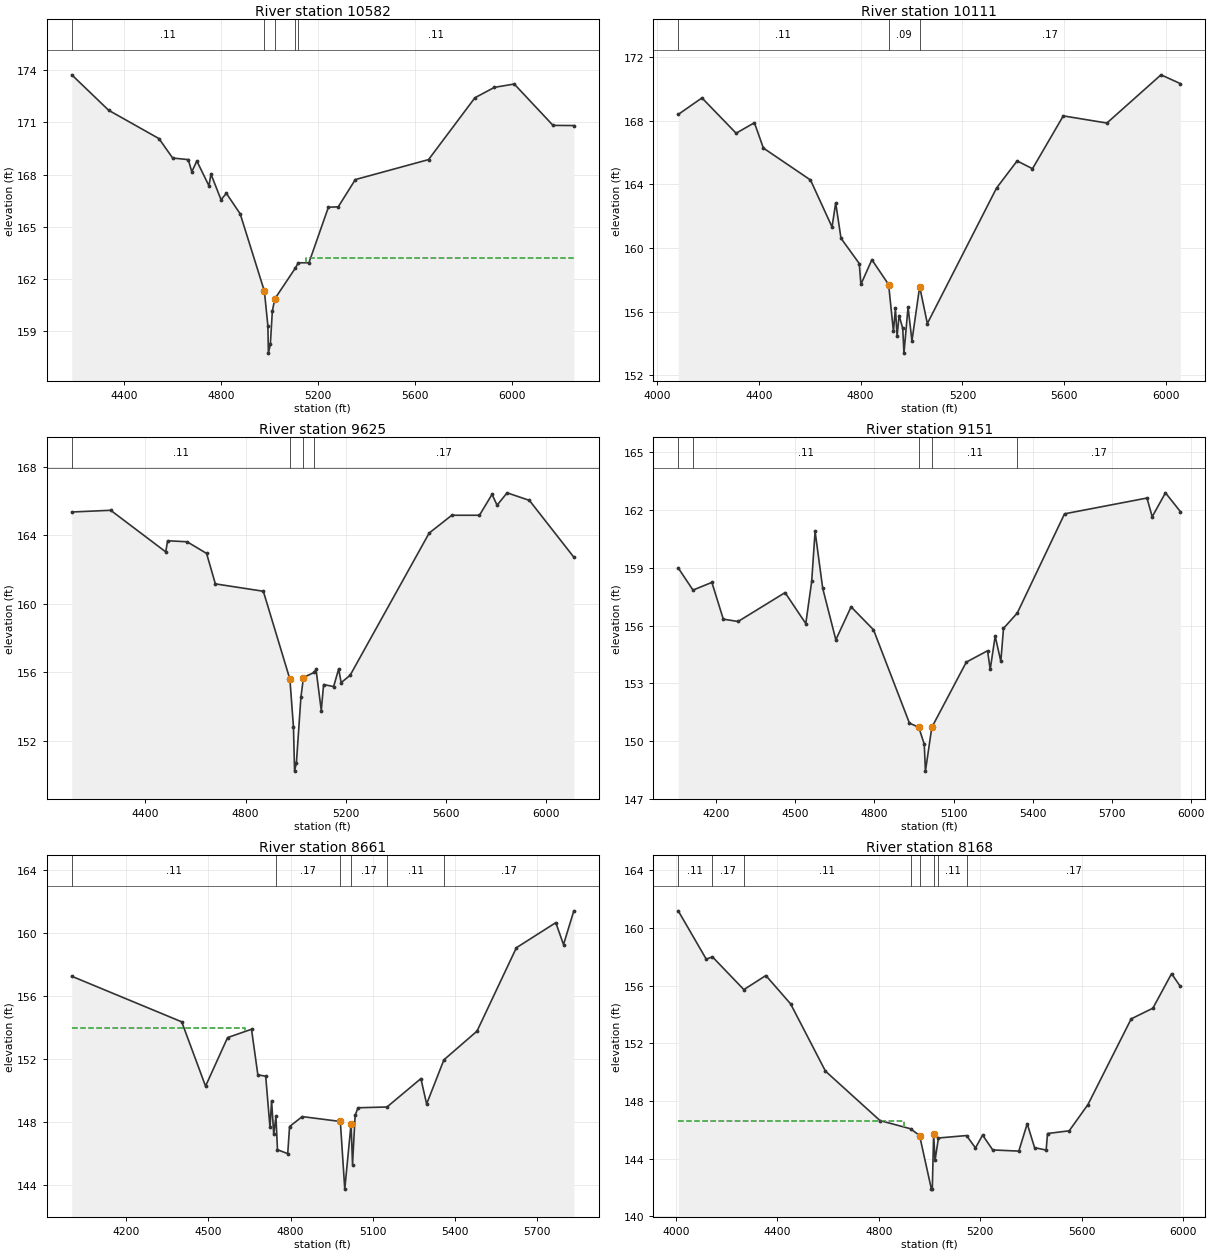
Type RM Length L Ch R = 1 ,10582   ,471,471,471
BEGIN DESCRIPTION:
Conroe Lake 117 16.0
END DESCRIPTION:
XS GIS Cut Line= 3
      3809113.23     10110299.45      3809758.97     10109802.37
      3809626.51     10108555.79
#Sta/Elev= 30
  4185.1  173.74  4337.1   171.7  4544.3  170.07  4600.8  168.95  4665.1  168.86
  4679.6  168.16  4700.4  168.78  4750.3  167.35  4758.5  168.03  4800.1  166.55
  4821.9  166.92  4878.9  165.74  4978.6  161.29  4993.1  159.29  4995.2  157.72
  5003.2  158.22  5011.4  160.13  5021.4  160.84  5105.5   162.6  5118.4  162.92
  5162.2  162.92  5242.4  166.12  5282.9  166.14  5353.3  167.71    5655  168.86
    5846  172.42  5926.5  173.02  6008.1  173.21  6167.8  170.83  6253.6  170.82
#Mann= 5 ,-1 , 0
  4185.1     .11       0  4978.6     .06       0  5021.4     .11       0
  5105.5     .17       0  5118.4     .11       0
#XS Ineff= 2 , 0
       0                  5149.8       0   163.2
Permanent Ineff=
       F       F
Bank Sta=4978.6,5021.4
XS Rating Curve= 0 ,0
Exp/Cntr=0.3,0.1

Type RM Length L Ch R = 1 ,10111   ,486,486,486
BEGIN DESCRIPTION:
Mapping XS ea3eb3e0
END DESCRIPTION:
XS GIS Cut Line= 3
      3809520.29     10110413.97      3810093.18     10109716.08
      3809963.13     10108654.83
#Sta/Elev= 30
  4083.8  168.39    4177  169.43  4311.2  167.21    4383  167.87  4418.1  166.28
  4603.3  164.27  4687.9  161.32  4702.3  162.83  4723.1  160.61  4794.9  159.02
  4801.3  157.71  4844.4  159.26 4910.21   157.7  4929.1  154.75  4936.9   156.2
  4943.4  154.46  4951.3  155.75  4965.6  154.95  4970.4  153.39  4986.5  156.28
  5001.8  154.16  5032.1  157.57  5062.3  155.25  5334.3  163.77  5414.9  165.47
  5475.3  164.98  5596.2   168.3  5767.5  167.85    5980  170.88  6055.9  170.33
#Mann= 3 , 0 , 0
  4083.8     .11       0 4910.21     .09       0  5032.1     .17       0
#XS Ineff= 2 , 0
       0  4702.3  162.83               0
Permanent Ineff=
       F       F
Bank Sta=4910.21,5032.1
XS Rating Curve= 0 ,0
Exp/Cntr=0.3,0.1

Type RM Length L Ch R = 1 ,9625    ,474,474,474
BEGIN DESCRIPTION:
Conroe Lake 117 14.0
END DESCRIPTION:
XS GIS Cut Line= 3
       3809873.1     10110546.15      3810471.04     10109881.94
      3810378.31     10108775.72
#Sta/Elev= 30
  4106.3  165.36  4261.6  165.46  4481.4  163.03  4488.8  163.68  4566.6  163.62
  4644.3  162.94  4679.4  161.16  4870.8  160.73  4976.9  155.59  4991.1  152.79
  4995.5  150.22  5002.9  150.72  5020.9  154.55    5031  155.69  5074.4  155.99
  5081.2  156.16  5102.1  153.76  5111.3  155.28  5151.4  155.16  5171.5  156.19
  5181.5  155.39  5217.2  155.82  5532.7  164.13    5623  165.17  5733.4  165.17
  5783.6  166.39  5803.7  165.76  5843.8  166.48  5932.6  166.04  6110.1  162.72
#Mann= 4 ,-1 , 0
  4106.3     .11       0  4976.9     .06       0    5031     .11       0
  5074.4     .17       0
Bank Sta=4976.9,5031
XS Rating Curve= 0 ,0
Exp/Cntr=0.3,0.1

Type RM Length L Ch R = 1 ,9151    ,490,490,490
BEGIN DESCRIPTION:
Conroe Lake 117 13.0
END DESCRIPTION:
XS GIS Cut Line= 3
      3810284.54       10110817.      3810870.52     10110078.55
        3810769.     10109125.14
#Sta/Elev= 30
  4057.3  158.99  4113.2  157.84  4184.7  158.24    4228  156.33    4284  156.21
  4461.9  157.71  4540.4   156.1  4562.7  158.29  4575.6  160.89  4604.5  157.93
  4654.2  155.26  4711.9  156.97  4796.8  155.78    4933  150.93  4968.2  150.72
    4989  149.84  4993.5  148.44  5017.6  150.71  5148.3   154.1  5228.8  154.69
  5238.8  153.72  5257.6  155.45  5279.1  154.14  5289.1  155.85  5341.4  156.65
  5520.4   161.8  5832.6  162.62  5852.3  161.65  5902.6  162.89  5958.8  161.92
#Mann= 5 ,-1 , 0
  4057.3     .17       0  4113.2     .11       0  4968.2     .06       0
  5017.6     .11       0  5341.4     .17       0
#XS Ineff= 2 , 0
       0                  5228.8       0  154.69
Permanent Ineff=
       F       F
Bank Sta=4968.2,5017.6
XS Rating Curve= 0 ,0
Exp/Cntr=0.3,0.1

Type RM Length L Ch R = 1 ,8661    ,493,493,493
BEGIN DESCRIPTION:
Conroe Lake 117 12.0
END DESCRIPTION:
XS GIS Cut Line= 3
      3810737.63     10110957.68      3811239.01     10110095.22
      3811003.28     10109296.17
#Sta/Elev= 30
  4002.4  157.26  4403.3  154.37  4490.2  150.29  4570.5  153.37  4657.8   153.9
  4680.9  151.01  4709.5  150.92  4725.2  147.67    4731  149.37  4738.8  147.24
  4746.8  148.37  4752.5  146.26  4789.8  146.01  4796.6  147.73  4842.8  148.36
  4981.7  148.05  4997.8  143.76  5020.9  147.92  5026.1  145.32  5035.6  148.43
    5046  148.92  5151.9  148.97  5275.4  150.77  5296.3  149.16  5359.3  151.96
    5480  153.78  5623.6  159.07  5767.3  160.66  5795.4  159.27  5833.1  161.41
#Mann= 6 ,-1 , 0
  4002.4     .11       0  4746.8     .17       0  4981.7     .09       0
  5020.9     .17       0  5151.9     .11       0  5359.3     .17       0
#XS Ineff= 2 , 0
       0    4635  153.97  5275.4       0  150.77
Permanent Ineff=
       T       F
Bank Sta=4981.7,5020.9
XS Rating Curve= 0 ,0
Exp/Cntr=0.3,0.1

Type RM Length L Ch R = 1 ,8168    ,494,494,494
BEGIN DESCRIPTION:
Conroe Lake 117 11.0
END DESCRIPTION:
XS GIS Cut Line= 3
      3811038.88     10111060.77      3811510.36     10110189.23
      3811088.02     10109295.28
#Sta/Elev= 30
  4009.1   161.2  4119.7  157.84  4143.7  158.01  4267.9  155.73  4354.6  156.71
  4452.2  154.74  4589.6  150.07  4804.6  146.64  4925.1  146.07  4960.7   145.6
  5007.3  141.88  5010.8  141.88  5016.1  145.72  5021.6  143.87    5035  145.43
  5145.7   145.6    5181  144.74  5209.2  145.63  5249.2   144.6  5351.9  144.52
  5385.1  146.42  5414.1  144.76  5459.7  144.59  5465.2  145.74  5550.7  145.93
  5624.5  147.75    5795   153.7  5880.5  154.44  5954.3  156.84  5988.7  155.95
#Mann= 8 ,-1 , 0
  4009.1     .11       0  4143.7     .17       0  4267.9     .11       0
  4925.1     .17       0  4960.7     .09       0  5016.1     .17       0
    5035     .11       0  5145.7     .17       0
#XS Ineff= 2 , 0
       0  4900.7  146.58  5385.1       0  146.42
Permanent Ineff=
       F       T
Bank Sta=4960.7,5016.1
XS Rating Curve= 0 ,0
Exp/Cntr=0.3,0.1

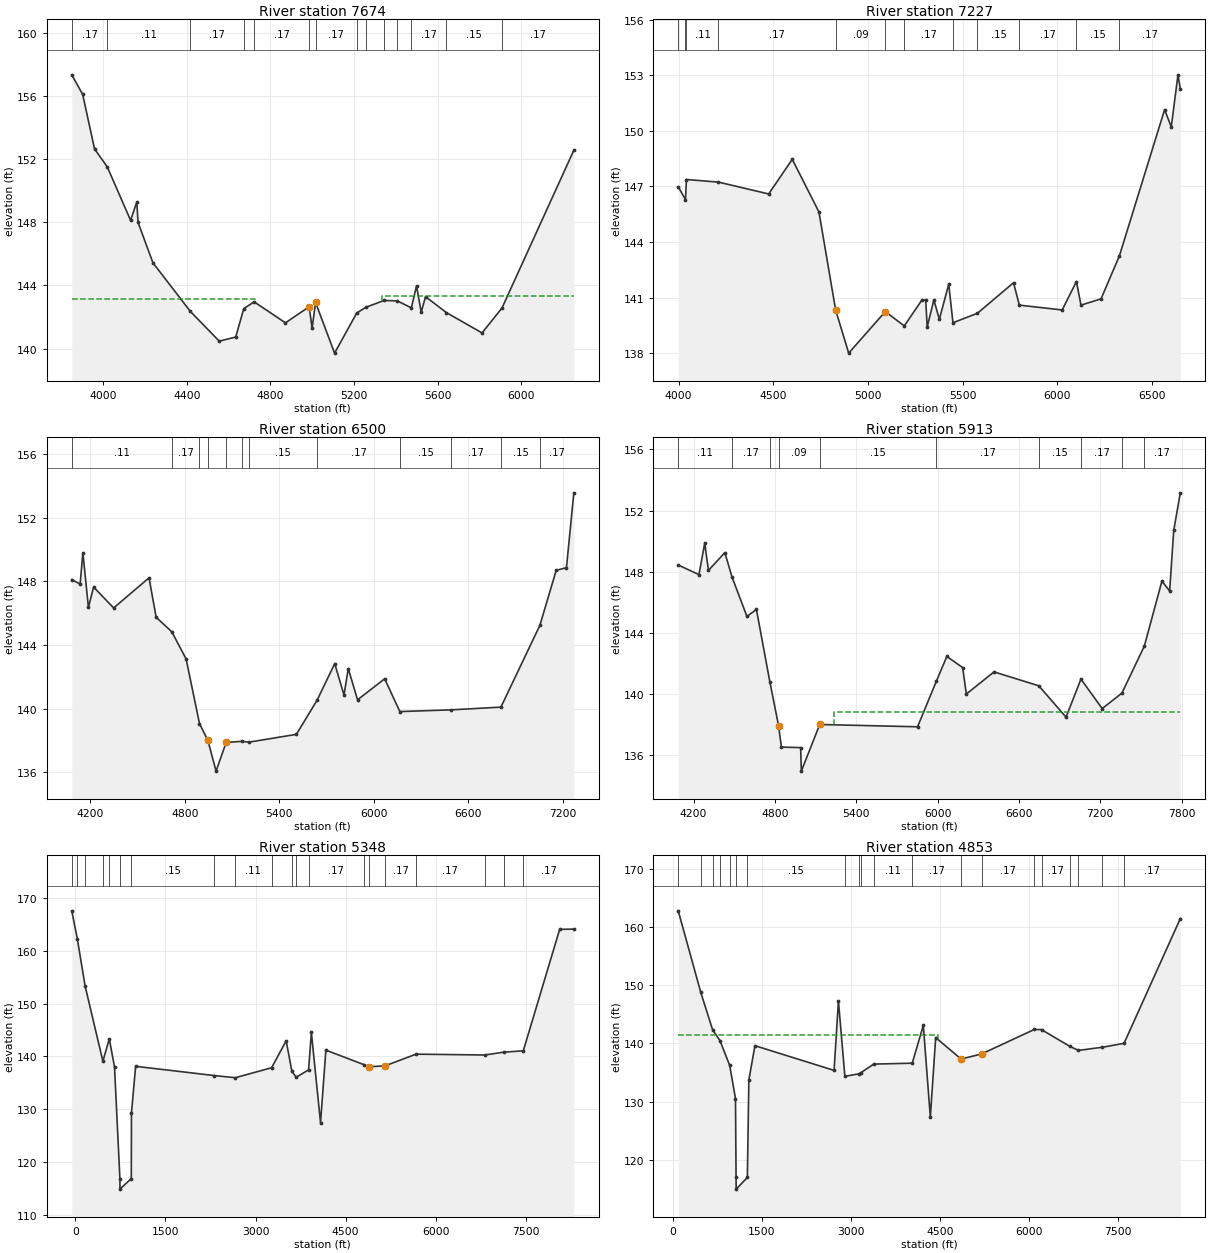
Type RM Length L Ch R = 1 ,7674    ,447,447,447
BEGIN DESCRIPTION:
Conroe Lake 117 10.0
END DESCRIPTION:
XS GIS Cut Line= 3
      3811302.33      10111177.9      3811963.75     10110237.15
      3811175.85      10109265.7
#Sta/Elev= 30
    3850  157.35  3902.1  156.11  3958.7  152.66  4019.9  151.51  4131.2  148.13
  4160.9  149.28    4167  147.99  4238.4  145.43  4417.3  142.35  4555.1  140.47
    4634  140.73  4672.5  142.53  4722.2  142.96  4871.8  141.63  4985.1  142.65
  4999.2  141.29  5015.8  142.92  5106.7  139.71  5212.5  142.25  5257.2  142.62
  5343.2  143.05  5406.8  143.02  5473.8  142.58  5498.5  143.97  5520.9  142.31
  5541.7  143.29  5641.4  142.28  5811.8  140.99  5907.2  142.57  6250.8  152.57
#Mann= 14 ,-1 , 0
    3850     .17       0  4019.9     .11       0  4417.3     .17       0
  4672.5     .11       0  4722.2     .17       0  4985.1     .09       0
  5015.8     .17       0  5212.5     .17       0  5257.2     .15       0
  5343.2     .17       0  5406.8     .11       0  5473.8     .17       0
  5641.4     .15       0  5907.2     .17       0
#XS Ineff= 2 , 0
       0  4726.3  143.13  5335.5       0  143.32
Permanent Ineff=
       T       T
Bank Sta=4985.1,5015.8
XS Rating Curve= 0 ,0
Exp/Cntr=0.3,0.1

Type RM Length L Ch R = 1 ,7227    ,727,727,727
BEGIN DESCRIPTION:
Conroe Lake 117 9.0
END DESCRIPTION:
XS GIS Cut Line= 4
      3812147.24     10111203.93      3812290.05     10110212.67
      3812307.44     10110021.53      3811157.49     10109124.95
#Sta/Elev= 30
  3998.5  146.97  4036.8  146.29  4041.8  147.37  4210.9  147.23  4476.2  146.59
  4600.7  148.46  4741.6  145.62  4829.9  140.32  4898.8     138    5092  140.24
  5192.5  139.47  5284.3  140.85  5305.5  140.88  5313.3  139.41  5348.5  140.87
  5377.5  139.83  5427.2  141.72  5449.4  139.64  5578.7  140.15  5769.2   141.8
    5800  140.59  6026.1  140.33  6101.4  141.86  6125.6  140.59  6231.5  140.93
  6328.4  143.25  6567.1  151.14  6602.4  150.21  6637.7  153.02  6650.1  152.27
#Mann= 12 ,-1 , 0
  3998.5     .11       0  4036.8     .17       0  4041.8     .11       0
  4210.9     .17       0  4829.9     .09       0    5092     .15       0
  5192.5     .17       0  5449.4     .11       0  5578.7     .15       0
    5800     .17       0  6101.4     .15       0  6328.4     .17       0
#XS Ineff= 2 , 0
       0                  5427.2       0  141.72
Permanent Ineff=
       F       T
Bank Sta=4829.9,5092
XS Rating Curve= 0 ,0
Exp/Cntr=0.3,0.1

Type RM Length L Ch R = 1 ,6500    ,587,587,587
BEGIN DESCRIPTION:
Conroe Lake 117 13.5
END DESCRIPTION:
XS GIS Cut Line= 4
      3812522.25     10111287.28      3812902.95     10110452.05
      3812931.97     10110299.63      3811211.29     10109071.27
#Sta/Elev= 30
  4082.1  148.11  4135.1  147.83  4152.6   149.8  4187.8  146.36  4220.8  147.64
    4348  146.33  4572.5  148.22    4618  145.74  4716.6  144.84  4807.8  143.13
  4892.8  139.07  4946.1  138.01  4998.1  136.08  5062.1  137.88  5160.4  137.95
  5207.4   137.9  5507.9  138.39  5639.1  140.53  5751.3  142.83  5810.3  140.86
  5837.3  142.52  5896.3  140.56  6068.4  141.88  6164.9  139.82  6492.4  139.93
  6806.3   140.1  7053.5  145.23  7157.3  148.69  7222.4  148.86  7269.3  153.56
#Mann= 12 ,-1 , 0
  4082.1     .11       0  4716.6     .17       0  4892.8     .15       0
  4946.1     .09       0  5062.1     .15       0  5160.4     .11       0
  5207.4     .15       0  5639.1     .17       0  6164.9     .15       0
  6492.4     .17       0  6806.3     .15       0  7053.5     .17       0
#XS Ineff= 2 , 0
       0                  5751.3       0  142.83
Permanent Ineff=
       F       T
Bank Sta=4946.1,5062.1
XS Rating Curve= 0 ,0
Exp/Cntr=0.3,0.1

Type RM Length L Ch R = 1 ,5913    ,565,565,565
BEGIN DESCRIPTION:
Conroe Lake 117 12.5
END DESCRIPTION:
XS GIS Cut Line= 4
      3812654.18     10111342.86      3813325.21     10110723.61
      3813263.75     10110367.94      3811248.67     10109011.54
#Sta/Elev= 30
  4086.9  148.44  4239.6  147.81  4282.1  149.86  4309.9  148.09  4430.7  149.25
  4484.1  147.64  4593.4  145.08  4663.7  145.53  4762.4  140.81  4826.7  137.94
    4848  136.53  4989.8   136.5  4994.8  134.96  5130.4  138.01    5852  137.86
  5991.2  140.85    6068  142.46  6184.9  141.73  6211.9     140  6415.8  141.45
  6746.1  140.54  6947.2  138.49  7057.3  140.98  7213.6  139.05  7359.1  140.06
  7524.8  143.14  7654.4  147.39  7711.4  146.74  7741.4   150.7    7790  153.16
#Mann= 10 ,-1 , 0
  4086.9     .11       0  4484.1     .17       0  4762.4     .15       0
  4826.7     .09       0  5130.4     .15       0  5991.2     .17       0
  6746.1     .15       0  7057.3     .17       0  7359.1     .15       0
  7524.8     .17       0
#XS Ineff= 2 , 0
       0                    5236       0  138.81
Permanent Ineff=
       F       T
Bank Sta=4826.7,5130.4
XS Rating Curve= 0 ,0
Exp/Cntr=0.3,0.1

Type RM Length L Ch R = 1 ,5348    ,495,495,495
BEGIN DESCRIPTION:
Conroe Lake 117 8.0
END DESCRIPTION:
XS GIS Cut Line= 3
      3818305.34     10112469.12      3813702.29     10110369.96
      3810878.69     10108665.63
#Sta/Elev= 30
   -59.1  167.54    32.6  162.28   163.3   153.3   458.9  139.09   565.5  143.32
   652.6  137.99     742   116.9   743.5   114.9   931.8   116.9   934.6  129.27
  1003.7  138.13  2306.1  136.39  2662.3  135.97  3267.1  137.86  3509.9  142.96
  3604.8  137.17  3676.8  136.06  3882.8  137.46  3929.1  144.53  4081.7  127.47
  4170.5  141.19  4807.2  138.43  4883.7  138.05  5156.8  138.22  5670.5  140.43
  6814.1  140.27  7133.5  140.81  7456.5  141.06  8062.3  164.04  8298.1  164.08
#Mann= 20 ,-1 , 0
   -59.1     .11       0    32.6     .17       0   163.3     .17       0
   458.9     .11       0   565.5     .17       0     742     .12       0
   931.8     .15       0  2306.1     .15       0  2662.3     .11       0
  3267.1     .15       0  3604.8     .11       0  3676.8     .15       0
  3882.8     .17       0  4807.2     .15       0  4883.7     .07       0
  5156.8     .17       0  5670.5     .17       0  6814.1     .17       0
  7133.5     .17       0  7456.5     .17       0
#XS Ineff= 2 , 0
       0  4170.5  141.19               0
Permanent Ineff=
       T       F
Bank Sta=4883.7,5156.8
XS Rating Curve= 0 ,0
Exp/Cntr=0.3,0.1

Type RM Length L Ch R = 1 ,4853    ,477,477,477
BEGIN DESCRIPTION:
Conroe Lake 117 7.0
END DESCRIPTION:
XS GIS Cut Line= 3
      3818477.25     10112250.38      3814073.64      10110093.4
      3810867.26     10108578.35
#Sta/Elev= 30
    96.5  162.75   475.9  148.75   673.9  142.37   799.4  140.47   962.1  136.24
  1060.1  130.54  1069.9     117  1071.4     115  1259.7     117  1285.1  133.73
  1387.5  139.61  2719.4  135.37  2792.5   147.3  2901.2  134.35  3143.6   134.8
    3172  134.99  3386.1  136.45  4034.7  136.61  4221.2  143.09  4339.3  127.36
  4429.3     141  4856.8  137.32  5202.2  138.19  6087.7  142.39  6210.6  142.37
  6681.9  139.52  6831.9   138.8  7230.5  139.34  7599.2  140.01  8546.3  161.42
#Mann= 20 ,-1 , 0
    96.5     .11       0   475.9     .17       0   673.9     .11       0
   799.4     .17       0   962.1     .15       0  1069.9     .12       0
  1259.7     .15       0  2901.2     .15       0  3143.6     .11       0
    3172     .15       0  3386.1     .11       0  4034.7     .17       0
  4856.8     .07       0  5202.2     .17       0  6087.7     .11       0
  6210.6     .17       0  6681.9     .15       0  6831.9     .17       0
  7230.5     .15       0  7599.2     .17       0
#XS Ineff= 2 , 0
       0  4468.7  141.47               0
Permanent Ineff=
       T       F
Bank Sta=4856.8,5202.2
XS Rating Curve= 0 ,0
Exp/Cntr=0.3,0.1

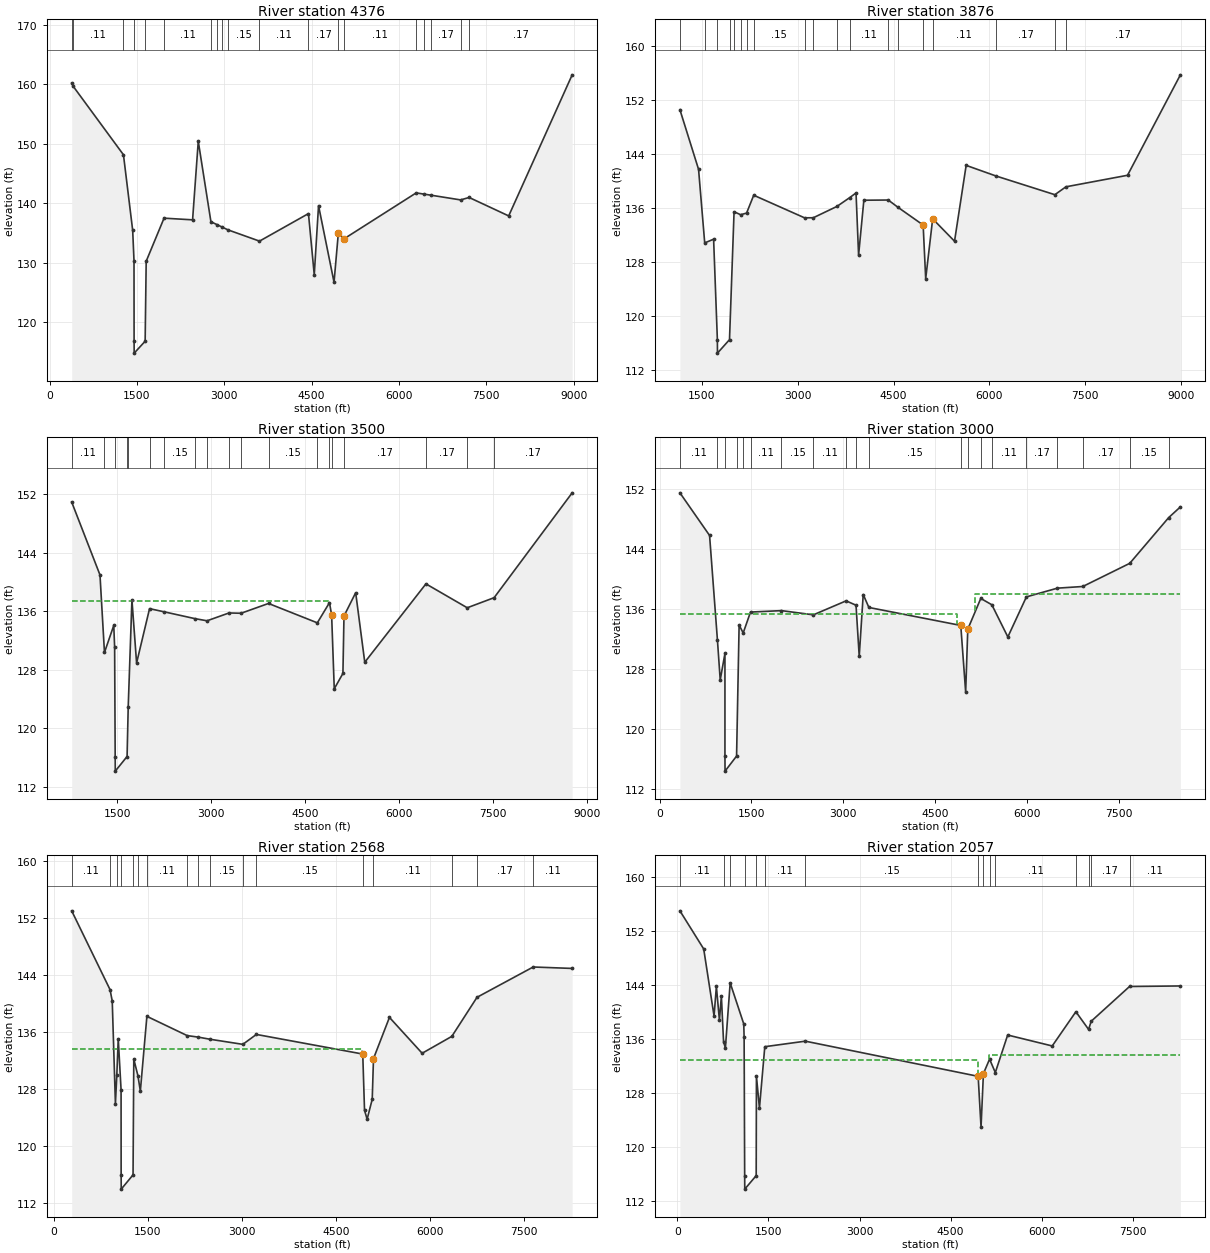
Type RM Length L Ch R = 1 ,4376    ,500,500,500
BEGIN DESCRIPTION:
Conroe Lake 117 6.0
END DESCRIPTION:
XS GIS Cut Line= 3
      3818659.54      10111948.3      3814495.26     10109949.13
      3810845.57     10108372.19
#Sta/Elev= 30
   380.7  160.19   407.4  159.65  1269.6  148.15  1428.2  135.44  1450.9  130.32
  1452.4   116.8  1453.9   114.8  1642.2   116.8  1660.2  130.25  1966.7  137.49
  2456.9  137.21  2554.5  150.42  2771.8  136.89  2879.2  136.39  2954.1  136.04
  3062.9  135.53    3606  133.63  4446.9  138.26  4546.4  127.97    4620   139.6
  4886.1  126.72  4959.6  134.93  5063.1  134.05  6296.9  141.74  6427.1  141.54
  6553.6  141.35  7059.6  140.56  7206.3  140.97  7885.6  137.87  8975.8  161.59
#Mann= 19 ,-1 , 0
   380.7     .17       0   407.4     .11       0  1269.6     .17       0
  1452.4     .12       0  1642.2     .17       0  1966.7     .11       0
  2771.8     .17       0  2879.2     .11       0  2954.1     .17       0
  3062.9     .15       0    3606     .11       0  4446.9     .17       0
  4959.6     .07       0  5063.1     .11       0  6296.9     .17       0
  6427.1     .11       0  6553.6     .17       0  7059.6     .15       0
  7206.3     .17       0
#XS Ineff= 2 , 0
       0    4620   139.6               0
Permanent Ineff=
       T       F
Bank Sta=4959.6,5063.1
XS Rating Curve= 0 ,0
Exp/Cntr=0.3,0.1

Type RM Length L Ch R = 1 ,3876    ,376,376,376
BEGIN DESCRIPTION:
Conroe Lake 117 5.0
END DESCRIPTION:
XS GIS Cut Line= 3
      3818215.29     10110709.14      3814562.76     10109518.15
      3810831.18     10108114.07
#Sta/Elev= 30
  1158.2  150.56    1450  141.71  1546.2   130.8  1685.4  131.35  1744.2  116.45
  1745.7  114.45  1934.1  116.45  2005.4  135.42  2107.9  134.98    2201  135.22
  2312.9  137.87  3107.9  134.52  3244.7  134.53  3614.5  136.21    3815  137.52
  3913.2  138.21  3953.3  128.99  4035.6  137.13  4417.5  137.16  4567.9  136.09
  4963.1  133.45  5002.9  125.49  5112.1  134.37    5454  131.05  5635.8   142.3
    6101  140.73  7023.4  137.95  7196.6  139.12  8160.2  140.83    8987  155.73
#Mann= 19 ,-1 , 0
  1158.2     .11       0  1546.2     .15       0  1744.2     .12       0
  1934.1     .15       0  2005.4     .17       0  2107.9     .11       0
    2201     .17       0  2312.9     .15       0  3107.9     .11       0
  3244.7     .15       0  3614.5     .17       0    3815     .11       0
  4417.5     .11       0  4567.9     .17       0  4963.1     .07       0
  5112.1     .11       0    6101     .17       0  7023.4     .15       0
  7196.6     .17       0
#XS Ineff= 2 , 0
       0  4035.6  137.13               0
Permanent Ineff=
       T       F
Bank Sta=4963.1,5112.1
XS Rating Curve= 0 ,0
Exp/Cntr=0.3,0.1

Type RM Length L Ch R = 1 ,3500    ,500,500,500
BEGIN DESCRIPTION:
Conroe Lake 117 7.5
END DESCRIPTION:
XS GIS Cut Line= 3
      3818362.91     10110613.67      3814386.25      10109186.2
      3810831.14     10107951.24
#Sta/Elev= 30
   774.9  150.96  1226.5  140.99  1298.1  130.39  1446.4  134.08  1460.3  131.11
  1469.1  116.16  1470.6  114.16    1659  116.16  1677.1  122.94  1736.5  137.58
  1810.9  128.95  2017.8  136.38    2255  135.94  2744.6  135.01  2935.3  134.72
  3285.6  135.79  3478.8  135.75  3916.6  137.09  4695.6  134.44  4889.7   137.2
  4923.9  135.52  4965.9  125.42  5104.2  127.52  5121.2  135.37  5307.9  138.56
  5452.9  129.05  6429.3  139.77  7088.4   136.5  7517.6  137.88  8763.5  152.22
#Mann= 19 ,-1 , 0
   774.9     .11       0  1298.1     .15       0  1469.1     .12       0
    1659     .15       0  1677.1     .17       0  2017.8     .11       0
    2255     .15       0  2744.6     .11       0  2935.3     .15       0
  3285.6     .17       0  3478.8     .11       0  3916.6     .15       0
  4695.6     .17       0  4889.7     .15       0  4923.9     .07       0
  5121.2     .17       0  6429.3     .17       0  7088.4     .15       0
  7517.6     .17       0
#XS Ineff= 2 , 0
       0  4884.4  137.46               0
Permanent Ineff=
       T       F
Bank Sta=4923.9,5121.2
XS Rating Curve= 0 ,0
Exp/Cntr=0.3,0.1

Type RM Length L Ch R = 1 ,3000    ,432,432,432
BEGIN DESCRIPTION:
Conroe Lake 117 6.5
END DESCRIPTION:
XS GIS Cut Line= 3
      3818475.76     10110535.54       3814160.8     10108754.71
      3810818.62     10107690.25
#Sta/Elev= 30
     332  151.44   816.6  145.77   945.5  131.81   990.5  126.55  1067.7  130.07
  1067.8  116.42  1069.3  114.42  1257.7  116.42  1299.2  133.85  1365.8   132.8
  1485.2  135.58  1991.2  135.77  2512.5  135.21    3047  137.07  3208.9  136.49
  3261.2  129.69  3326.4  137.91  3419.4  136.19  4919.9   133.8    5000  124.94
  5034.6   133.3  5246.9  137.39  5427.4  136.55    5689  132.27  5992.2   137.6
  6499.5  138.76  6913.4  138.98  7680.2  142.06  8315.9  148.14  8507.6  149.57
#Mann= 20 ,-1 , 0
     332     .11       0   945.5     .15       0  1067.8     .12       0
  1257.7     .15       0  1365.8     .17       0  1485.2     .11       0
  1991.2     .15       0  2512.5     .11       0    3047     .11       0
  3208.9     .17       0  3419.4     .15       0  4919.9     .07       0
  5034.6     .11       0  5246.9     .17       0  5427.4     .11       0
  5992.2     .17       0  6499.5     .15       0  6913.4     .17       0
  7680.2     .15       0  8315.9     .17       0
#XS Ineff= 2 , 0
       0  4851.7  135.35  5157.8       0  137.99
Permanent Ineff=
       T       F
Bank Sta=4919.9,5034.6
XS Rating Curve= 0 ,0
Exp/Cntr=0.3,0.1

Type RM Length L Ch R = 1 ,2568    ,511,511,511
BEGIN DESCRIPTION:
Conroe Lake 117 5.5
END DESCRIPTION:
XS GIS Cut Line= 3
      3818562.53     10110440.04      3814325.14      10108378.2
       3811192.8     10107436.59
#Sta/Elev= 30
   287.6  153.04   899.6  141.98   934.4  140.38   985.1  125.97  1007.3  129.98
  1030.2   135.1  1075.3  127.93  1076.4     116  1077.9     114  1266.3     116
  1278.2  132.24  1343.9  129.91  1382.7  127.76  1487.1  138.24  2128.9  135.54
  2301.2  135.33  2497.7  135.02  3017.2  134.31  3233.5   135.7  4930.3  132.95
  4958.6  125.06    5000  123.81  5081.4   126.6  5101.6  132.31  5356.1  138.09
  5877.7  133.06  6351.3  135.43    6753  140.91  7648.7  145.16  8270.8  144.96
#Mann= 17 ,-1 , 0
   287.6     .11       0   899.6     .17       0  1007.3     .15       0
  1076.4     .12       0  1266.3     .15       0  1343.9     .15       0
  1487.1     .11       0  2128.9     .15       0  2301.2     .11       0
  2497.7     .15       0  3017.2     .17       0  3233.5     .15       0
  4930.3     .07       0  5101.6     .11       0  6351.3     .15       0
    6753     .17       0  7648.7     .11       0
#XS Ineff= 2 , 0
       0  4919.1  133.65               0
Permanent Ineff=
       T       F
Bank Sta=4930.3,5101.6
XS Rating Curve= 0 ,0
Exp/Cntr=0.3,0.1

Type RM Length L Ch R = 1 ,2057    ,491,491,491
BEGIN DESCRIPTION:
Conroe Lake 117 4.0
END DESCRIPTION:
XS GIS Cut Line= 3
      3818753.54     10110327.21      3814368.26     10108010.75
      3811192.76      10107158.8
#Sta/Elev= 30
    40.5  155.02   432.7  149.37   603.2  139.44   641.5  143.82   691.6  138.82
   723.9   142.4   759.5  135.66     790   134.7   868.8  144.34  1092.5  138.27
  1098.7  136.26  1107.7  115.79  1109.2  113.79  1297.6  115.79  1301.4  130.55
  1351.1  125.78  1439.4  134.89  2107.1  135.71  4955.2   130.5  5002.8  122.97
  5041.8   130.9  5143.5  133.05    5238  131.06  5441.5  136.62  6175.7     135
  6565.6  140.07  6775.2  137.45  6817.9  138.66  7449.8  143.81  8287.8  143.89
#Mann= 15 ,-1 , 0
    40.5     .11       0   759.5     .17       0   868.8     .11       0
  1107.7     .12       0  1297.6     .11       0  1439.4     .11       0
  2107.1     .15       0  4955.2     .07       0  5041.8     .11       0
  5143.5     .15       0    5238     .11       0  6565.6     .17       0
  6775.2     .15       0  6817.9     .17       0  7449.8     .11       0
#XS Ineff= 2 , 0
       0  4947.7  132.93    5137       0  133.65
Permanent Ineff=
       T       F
Bank Sta=4955.2,5041.8
XS Rating Curve= 0 ,0
Exp/Cntr=0.3,0.1

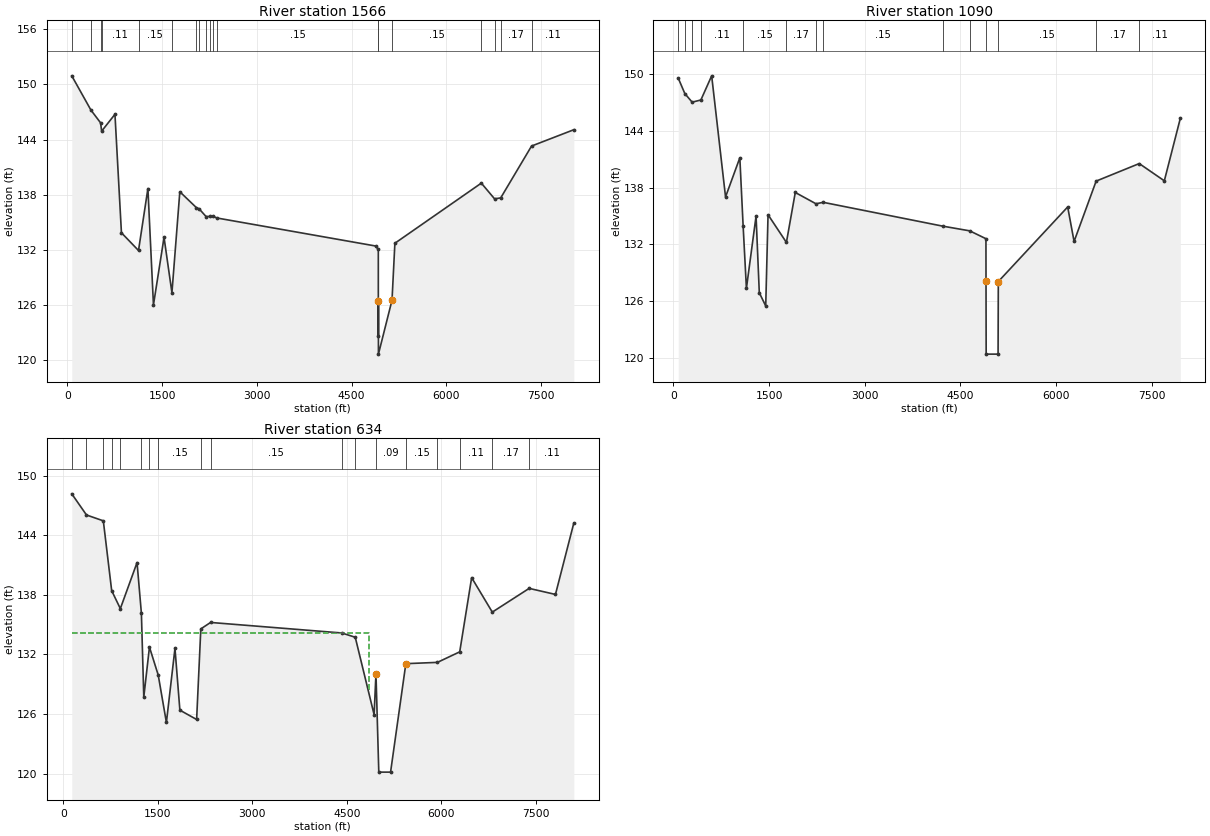
Type RM Length L Ch R = 1 ,1566    ,476,476,476
BEGIN DESCRIPTION:
Conroe Lake 117 3.0
END DESCRIPTION:
XS GIS Cut Line= 3
      3818727.48     10109962.63      3814433.09     10107538.39
      3811462.39     10107011.32
#Sta/Elev= 30
    68.6  150.94   371.8  147.21   524.8  145.82   541.3  144.91   752.3  146.75
   854.9  133.84  1125.2  131.91  1273.9  138.66  1361.8  125.98  1529.3  133.34
  1654.3  127.31  1779.2  138.31  2043.1  136.57  2083.5  136.46  2194.4  135.61
  2257.6  135.62  2305.3  135.63  2367.9  135.45  4878.3   132.4  4921.6  132.03
    4922  122.62 4922.51  126.46  4923.5  120.62 5138.59   126.5    5184   132.7
  6552.4  139.25  6761.9  137.54  6859.3  137.64  7347.6  143.29  8017.1  145.07
#Mann= 19 ,-1 , 0
    68.6     .17       0   371.8     .11       0   524.8     .17       0
   541.3     .11       0  1125.2     .15       0  1654.3     .11       0
  2043.1     .17       0  2083.5     .15       0  2194.4     .11       0
  2257.6     .15       0  2305.3     .11       0  2367.9     .15       0
    4922     .12       0 4922.51     .09       0 5138.59     .15       0
  6552.4     .17       0  6761.9     .15       0  6859.3     .17       0
  7347.6     .11       0
#XS Ineff= 2 , 0
       0  4921.6  132.03               0
Permanent Ineff=
       T       F
Bank Sta=4922.51,5138.59
XS Rating Curve= 0 ,0
Exp/Cntr=0.3,0.1

Type RM Length L Ch R = 1 ,1090    ,456,456,456
BEGIN DESCRIPTION:
Conroe Lake 117 2.0
END DESCRIPTION:
XS GIS Cut Line= 3
      3818710.09     10109754.27       3814557.9      10107105.5
      3811618.08     10106837.62
#Sta/Elev= 30
    74.9  149.56     179  147.92   293.3  147.02   430.1  147.25   599.5   149.8
   817.1  137.02  1041.3  141.15  1092.9  133.98  1144.6  127.37    1296     135
  1346.7  126.91  1447.5  125.51  1483.9  135.14  1772.1  132.22  1911.2  137.49
  2235.4   136.3  2349.6  136.45  4221.6  133.94  4648.3  133.44  4902.6  132.61
 4903.67   128.1    4906  120.43  5092.9  120.43 5096.75  128.09  6184.9  135.96
  6285.4  132.32  6631.4  138.69  7307.6  140.54  7701.2  138.72    7952  145.31
#Mann= 14 ,-1 , 0
    74.9     .17       0     179     .11       0   293.3     .17       0
   430.1     .11       0  1092.9     .15       0  1772.1     .17       0
  2235.4     .11       0  2349.6     .15       0  4221.6     .11       0
  4648.3     .15       0 4903.67     .09       0 5096.75     .15       0
  6631.4     .17       0  7307.6     .11       0
#XS Ineff= 2 , 0
       0  4902.6  132.61               0
Permanent Ineff=
       T       F
Bank Sta=4903.67,5096.75
XS Rating Curve= 0 ,0
Exp/Cntr=0.3,0.1

Type RM Length L Ch R = 1 ,634     ,0,0,0
BEGIN DESCRIPTION:
Conroe Lake 117 1.0
END DESCRIPTION:
XS GIS Cut Line= 3
      3818762.23      10109580.7      3814797.82     10106756.51
       3811696.2     10106664.01
#Sta/Elev= 30
   132.5  148.16   366.2  146.03   633.4  145.44   766.1  138.41   903.5   136.6
  1168.8  141.24  1237.8  136.13  1275.8  127.69  1365.7  132.73    1505  129.91
  1634.8  125.14  1770.8   132.6  1848.7  126.38  2114.6  125.44  2181.2  134.56
  2336.1  135.21  4418.7  134.15  4632.8  133.72  4932.1  125.93  4961.6  130.05
  5006.6  120.14  5193.5  120.14  5435.9  131.06  5937.4  131.19  6291.2  132.25
  6480.6  139.72  6808.4  136.25    7394  138.64  7811.2  138.03    8103  145.23
#Mann= 18 ,-1 , 0
   132.5     .17       0   366.2     .17       0   633.4     .11       0
   766.1     .11       0   903.5     .17       0  1237.8     .15       0
  1365.7     .11       0    1505     .15       0  2181.2     .11       0
  2336.1     .15       0  4418.7     .11       0  4632.8     .15       0
  4961.6     .09       0  5435.9     .15       0  5937.4     .15       0
  6291.2     .11       0  6808.4     .17       0    7394     .11       0
#XS Ineff= 2 , 0
       0  4846.1  134.15               0
Permanent Ineff=
       T       F
Bank Sta=4961.6,5435.9
XS Rating Curve= 0 ,0
Exp/Cntr=0.3,0.1

Chan Stop Cuts=-1
Use User Specified Reach Order=0
Composite Channel Slope=5