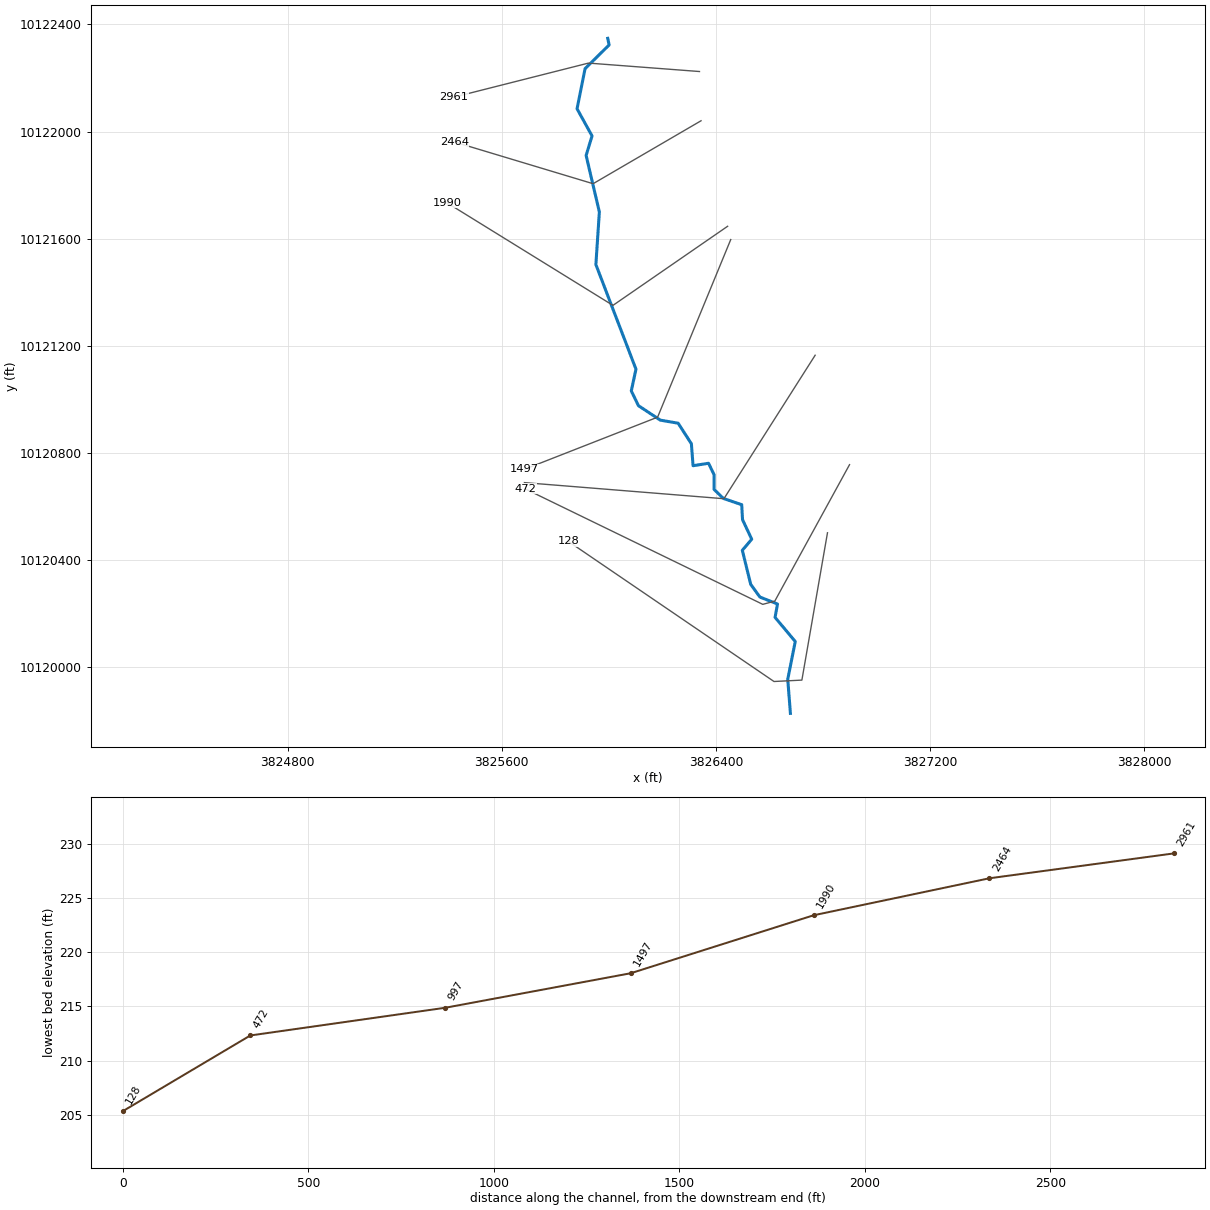
--- Conroe Lake 118.prj (project) ---

Proj Title=Conroe Lake 118 Base Level Engineering
Current Plan=p01
Default Exp/Contr=0.3,0.1
English Units
Geom File=g01
Flow File=f01
Flow File=f02
Plan File=p01
Y Axis Title=Elevation
X Axis Title(PF)=Main Channel Distance
X Axis Title(XS)=Station
BEGIN DESCRIPTION:
Conroe Lake 118
END DESCRIPTION:
DSS Export Rating Curves= 0
DSS Export Rating Curve Sorted= 0
DSS Export Volume Flow Curves= 0
DXF OffsetX= 0
DXF OffsetY= 0
DXF ScaleX= 1
DXF ScaleY= 10

--- Conroe Lake 118.p01 (plan) ---

Plan Title=Multiple Run
Short Identifier=Multiple
Geom File=g01
Flow File=f01
Subcritical Flow
K Sum by GR= 0
Std Step Tol= 0.01
Critical Tol= 0.01
Num of Std Step Trials= 20
Max Error Tol= 0.3
Flow Tol Ratio= 0.001
Split Flow NTrial= 30
Split Flow Tol= 0.02
Split Flow Ratio= 0.02
Log Output Level= 0
Friction Slope Method= 1
Unsteady Friction Slope Method= 2
Unsteady Bridges Friction Slope Method= 1
Parabolic Critical Depth
Global Vel Dist=  1 , 1 , 1
Global Log Level= 0
CheckData=True
Encroach Param= -1, 0, 0, 0
BEGIN DESCRIPTION:
Multiple Run
END DESCRIPTION:

--- Conroe Lake 118.f01 (steady flow) ---

Flow Title=Multiple
Program Version=4.10
Number of Profiles= 7
Profile Names=10-year,25-year,50-year,1pct_min,100-year,1pct_plu,500-year
River Rch & RM=Conroe Lake 118,Reach-1         ,2961
     168     206     261     110     332    1003     545
River Rch & RM=Conroe Lake 118,Reach-1         ,2464
     283     362     472     202     611    1845    1060
Boundary for River Rch & Prof#=Conroe Lake 118,Reach-1         , 1
Up Type= 0
Dn Type= 3
Dn Slope=0.02
Boundary for River Rch & Prof#=Conroe Lake 118,Reach-1         , 2
Up Type= 0
Dn Type= 3
Dn Slope=0.02
Boundary for River Rch & Prof#=Conroe Lake 118,Reach-1         , 3
Up Type= 0
Dn Type= 3
Dn Slope=0.02
Boundary for River Rch & Prof#=Conroe Lake 118,Reach-1         , 4
Up Type= 0
Dn Type= 3
Dn Slope=0.02
Boundary for River Rch & Prof#=Conroe Lake 118,Reach-1         , 5
Up Type= 0
Dn Type= 3
Dn Slope=0.02
Boundary for River Rch & Prof#=Conroe Lake 118,Reach-1         , 6
Up Type= 0
Dn Type= 3
Dn Slope=0.02
Boundary for River Rch & Prof#=Conroe Lake 118,Reach-1         , 7
Up Type= 0
Dn Type= 3
Dn Slope=0.02
DSS Import GetInterval= 0
DSS Import GetPeak= 0
DSS Import FillOption= 0

--- Conroe Lake 118.f02 (steady flow) ---

Flow Title=Orig_BLE_Flow
Program Version=4.10
Number of Profiles= 7
Profile Names=10-year,25-year,50-year,1pct_min,100-year,1pct_plu,500-year
River Rch & RM=Conroe Lake 118,Reach-1         ,2961
     168     202     227      84     255     769     317
River Rch & RM=Conroe Lake 118,Reach-1         ,2464
     283     355     410     156     470    1419     616
Boundary for River Rch & Prof#=Conroe Lake 118,Reach-1         , 1
Up Type= 0
Dn Type= 3
Dn Slope=0.02
Boundary for River Rch & Prof#=Conroe Lake 118,Reach-1         , 2
Up Type= 0
Dn Type= 3
Dn Slope=0.02
Boundary for River Rch & Prof#=Conroe Lake 118,Reach-1         , 3
Up Type= 0
Dn Type= 3
Dn Slope=0.02
Boundary for River Rch & Prof#=Conroe Lake 118,Reach-1         , 4
Up Type= 0
Dn Type= 3
Dn Slope=0.02
Boundary for River Rch & Prof#=Conroe Lake 118,Reach-1         , 5
Up Type= 0
Dn Type= 3
Dn Slope=0.02
Boundary for River Rch & Prof#=Conroe Lake 118,Reach-1         , 6
Up Type= 0
Dn Type= 3
Dn Slope=0.02
Boundary for River Rch & Prof#=Conroe Lake 118,Reach-1         , 7
Up Type= 0
Dn Type= 3
Dn Slope=0.02
DSS Import GetInterval= 0
DSS Import GetPeak= 0
DSS Import FillOption= 0

--- Conroe Lake 118.g01 (geometry) ---

Geom Title=Existing Conditions
Program Version=4.10

River Reach=Conroe Lake 118 ,Reach-1
Reach XY= 30
      3825995.92     10122348.11      3826001.13     10122323.37
      3825911.28     10122234.83      3825881.33     10122085.09
      3825937.32     10121983.53      3825915.19     10121910.61
      3825964.67     10121699.67      3825951.65     10121503.06
      3826101.39     10121112.43      3826083.94      10121031.3
      3826110.69     10120976.08      3826192.42     10120921.99
      3826258.94     10120910.61      3826308.42     10120833.79
      3826314.66      10120751.9      3826372.43     10120760.95
       3826393.4     10120717.86      3826392.99     10120663.56
      3826427.67     10120629.67      3826496.34      10120606.3
      3826499.43     10120550.24      3826533.73     10120477.32
      3826498.62     10120435.83      3826530.04     10120308.54
      3826564.33     10120261.28      3826630.04     10120235.35
      3826620.92     10120185.34      3826696.35     10120095.29
      3826668.26     10119954.43      3826678.23     10119826.84

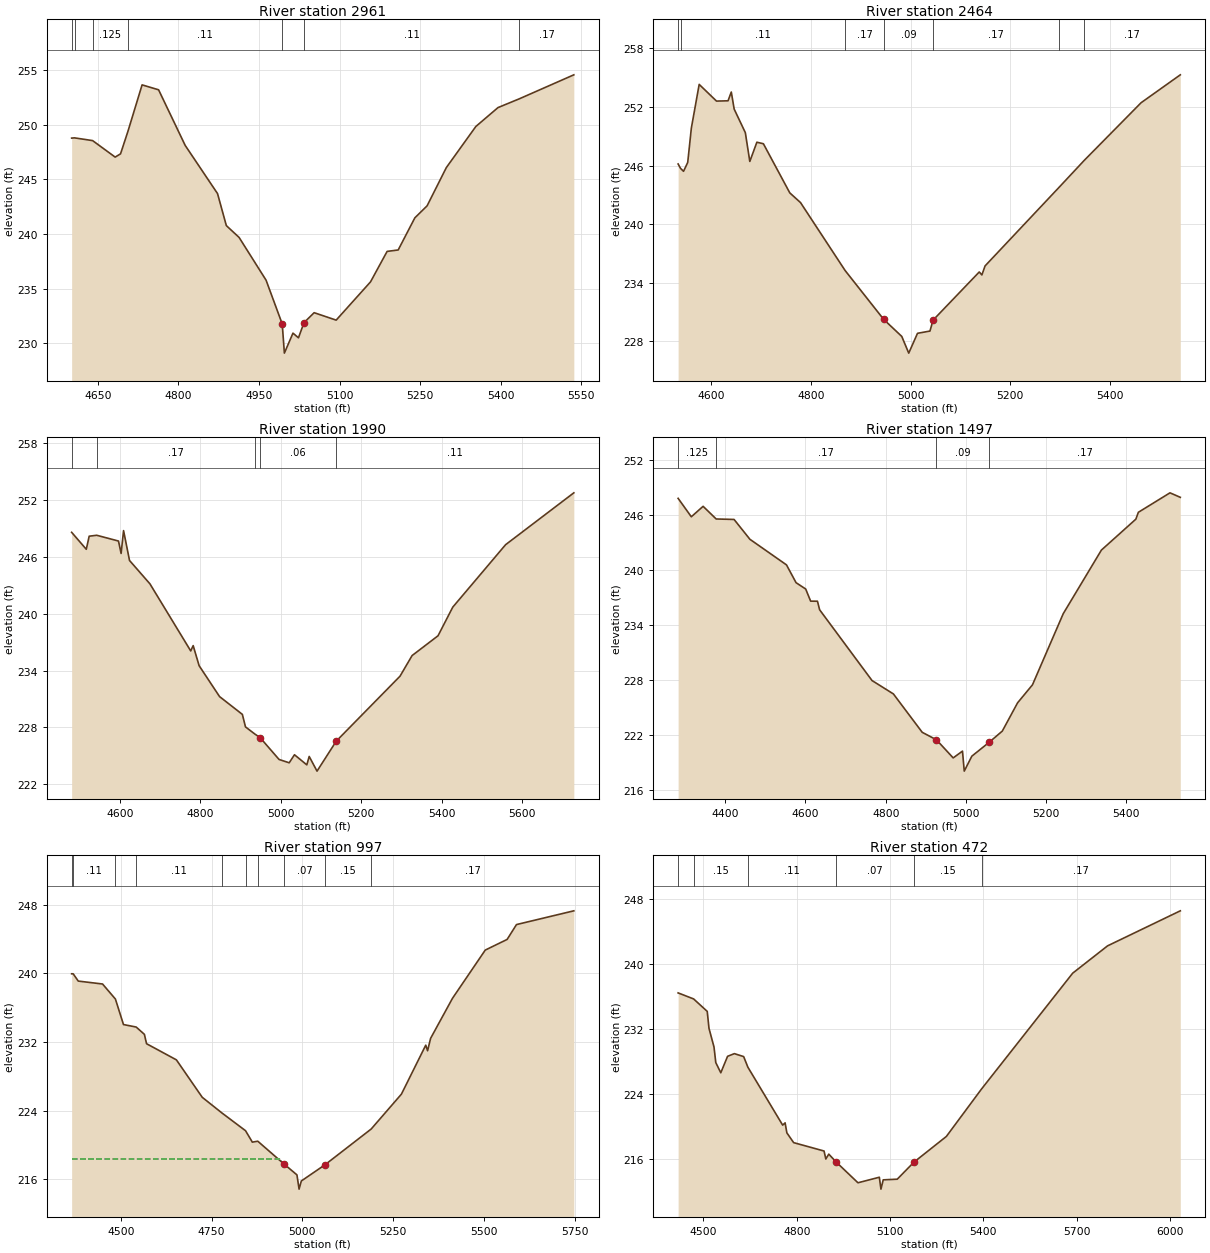
Type RM Length L Ch R = 1 ,2961    ,497,497,497
BEGIN DESCRIPTION:
Conroe Lake 118 6.0
END DESCRIPTION:
XS GIS Cut Line= 4
      3826338.58     10122224.15      3825941.23     10122254.36
      3825922.79     10122255.36        3825421.     10122128.29
#Sta/Elev= 30
  4601.5  248.77  4606.9  248.79  4640.5  248.54  4682.5  247.03  4692.5  247.33
  4706.2  249.38  4732.6  253.64  4763.3  253.19  4812.8   248.1    4873  243.69
  4889.4  240.76  4913.1  239.68  4963.3  235.77  4993.4  231.76  4997.4  229.09
  5013.4  230.92  5023.6  230.49  5033.9  231.88  5052.8  232.79  5093.8  232.11
  5157.7  235.61  5188.6   238.4  5209.2  238.53  5240.2  241.47    5263  242.57
  5298.8  246.07  5353.7  249.83  5394.9  251.56  5434.4  252.36  5536.1  254.56
#Mann= 7 ,-1 , 0
  4601.5    .125       0  4606.9     .11       0  4640.5    .125       0
  4706.2     .11       0  4993.4     .06       0  5033.9     .11       0
  5434.4     .17       0
Bank Sta=4993.4,5033.9
XS Rating Curve= 0 ,0
Exp/Cntr=0.3,0.1

Type RM Length L Ch R = 1 ,2464    ,474,474,474
BEGIN DESCRIPTION:
Conroe Lake 118 5.0
END DESCRIPTION:
XS GIS Cut Line= 3
      3826344.49     10122040.26      3825941.23     10121805.14
      3825422.43     10121961.31
#Sta/Elev= 30
  4533.2  246.17  4538.1  245.72  4544.1  245.42  4552.5  246.33  4559.8  249.85
  4575.5  254.32  4610.3  252.61  4633.5  252.64    4640  253.54  4645.8  251.79
  4668.2  249.38  4677.2  246.43  4691.4   248.4  4704.5  248.24  4757.5  243.21
    4779  242.22  4868.6  235.26    4946  230.26  4982.4  228.51  4996.4   226.8
    5014  228.83    5039  229.06  5045.3  230.18    5138  235.11  5143.3  234.81
  5149.7  235.73  5298.7   243.8  5348.9  246.54    5463  252.44  5541.8   255.3
#Mann= 7 ,-1 , 0
  4533.2    .125       0  4538.1     .11       0  4868.6     .17       0
    4946     .09       0  5045.3     .17       0  5298.7     .11       0
  5348.9     .17       0
Bank Sta=4946,5045.3
XS Rating Curve= 0 ,0
Exp/Cntr=0.3,0.1

Type RM Length L Ch R = 1 ,1990    ,493,493,493
BEGIN DESCRIPTION:
Conroe Lake 118 4.0
END DESCRIPTION:
XS GIS Cut Line= 3
      3826443.72     10121646.17      3826015.45     10121350.71
      3825395.77     10121733.74
#Sta/Elev= 30
  4479.7   248.6  4516.1  246.81  4523.3  248.19    4542  248.29  4596.2  247.68
  4602.7  246.37  4608.8  248.78  4623.6  245.63  4674.4  243.16  4775.8  236.08
  4781.9  236.64  4796.7  234.52  4847.5  231.26  4904.2  229.38    4912  228.06
  4934.8  227.32  4948.5  226.92  4995.5  224.62  5020.7  224.27  5033.8  225.12
  5064.5  224.05  5070.4  224.94  5089.9  223.39  5137.8  226.56  5296.2  233.41
  5326.3  235.59  5390.8  237.68  5427.4   240.7  5558.7  247.29  5728.5  252.77
#Mann= 5 ,-1 , 0
  4479.7    .125       0    4542     .17       0  4934.8     .11       0
  4948.5     .06       0  5137.8     .11       0
Bank Sta=4948.5,5137.8
XS Rating Curve= 0 ,0
Exp/Cntr=0.3,0.1

Type RM Length L Ch R = 1 ,1497    ,500,500,500
BEGIN DESCRIPTION:
Conroe Lake 118 3.0
END DESCRIPTION:
XS GIS Cut Line= 3
      3826455.38     10121596.52      3826182.22     10120933.16
      3825684.71     10120738.32
#Sta/Elev= 30
  4282.6  247.77  4315.5  245.76  4344.9   246.9  4377.5  245.52  4422.1  245.47
  4461.5  243.31  4552.7  240.52  4576.6  238.58  4600.6  237.89  4612.9  236.57
  4629.9  236.56  4635.3  235.63  4765.9  227.92  4819.2  226.46    4891  222.28
  4926.6  221.46  4968.2  219.49  4991.4  220.23  4995.8  218.05  5014.7  219.68
  5058.4  221.21  5090.6  222.41  5128.7  225.49  5165.8  227.45  5242.6  235.21
  5337.6  242.13  5423.5   245.5  5429.8  246.25  5508.6  248.37  5534.3  247.88
#Mann= 4 ,-1 , 0
  4282.6    .125       0  4377.5     .17       0  4926.6     .09       0
  5058.4     .17       0
Bank Sta=4926.6,5058.4
XS Rating Curve= 0 ,0
Exp/Cntr=0.3,0.1

Type RM Length L Ch R = 1 ,997     ,525,525,525
BEGIN DESCRIPTION:
Conroe Lake 118 2.0
END DESCRIPTION:
XS GIS Cut Line= 3
      3826770.66     10121164.54      3826429.92     10120628.59
      3825684.74     10120688.71
#Sta/Elev= 30
  4364.9  239.94  4369.1  239.94  4383.1  239.09    4450  238.75  4485.4     237
  4507.6  234.03  4542.6  233.74  4565.2  232.89  4571.1   231.8  4653.3  229.92
  4724.5  225.56  4778.9  223.73  4843.7  221.67  4862.4  220.34  4877.3  220.45
  4949.7  217.79  4985.2  216.53  4991.1  214.87  4997.3  215.82  5062.3   217.7
  5189.7  221.87  5272.9  225.93  5339.9  231.63  5344.9  230.98  5353.2  232.42
  5413.4  237.08  5503.7   242.7  5563.9  243.94  5589.7  245.67  5747.6  247.27
#Mann= 10 ,-1 , 0
  4364.9    .125       0  4369.1     .11       0  4485.4     .15       0
  4542.6     .11       0  4778.9     .17       0  4843.7     .11       0
  4877.3     .15       0  4949.7     .07       0  5062.3     .15       0
  5189.7     .17       0
#XS Ineff= 2 , 0
       0  4941.2  218.36               0
Permanent Ineff=
       F       F
Bank Sta=4949.7,5062.3
XS Rating Curve= 0 ,0
Exp/Cntr=0.3,0.1

Type RM Length L Ch R = 1 ,472     ,344,344,344
BEGIN DESCRIPTION:
Conroe Lake 118 1.0
END DESCRIPTION:
XS GIS Cut Line= 4
      3826899.08     10120755.84      3826619.83     10120246.01
      3826575.05     10120234.03      3825687.68     10120665.36
#Sta/Elev= 30
  4418.7  236.42  4468.5  235.68  4512.3  234.15    4518  232.06  4534.1  229.77
  4539.8  227.86  4555.9  226.61  4577.7  228.63  4599.5  228.96  4629.4   228.6
  4642.9   227.3  4754.8  220.18  4762.6  220.46  4768.3  219.23  4790.1  218.03
  4887.8     217  4893.5  216.02    4903  216.62  4925.7  215.69  4996.8   213.1
  5065.5  213.78  5070.7  212.32    5078  213.46  5123.1  213.54  5176.7  215.63
    5281  218.79  5394.1  224.62    5687  238.84  5799.3   242.2    6033   246.5
#Mann= 6 ,-1 , 0
  4418.7    .125       0  4468.5     .15       0  4642.9     .11       0
  4925.7     .07       0  5176.7     .15       0  5394.1     .17       0
#XS Ineff= 2 , 0
       0    4903  216.62               0
Permanent Ineff=
       F       F
Bank Sta=4925.7,5176.7
XS Rating Curve= 0 ,0
Exp/Cntr=0.3,0.1

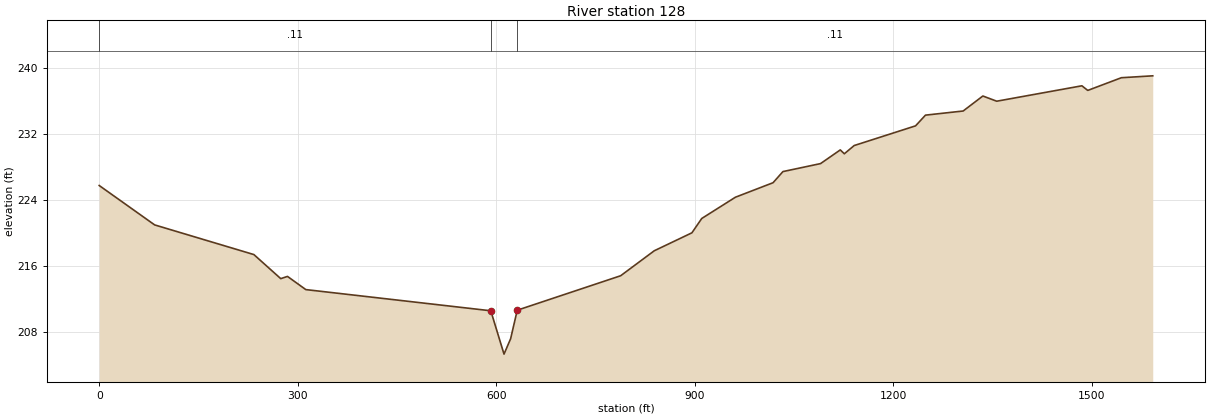
Type RM Length L Ch R = 1 ,128     ,0,0,0
XS GIS Cut Line= 4
      3826816.71     10120501.44       3826721.1      10119951.1
      3826616.93     10119945.89       3825848.7     10120469.33
#Sta/Elev= 30
       0   225.8    83.8  221.02   233.8  217.42   274.4   214.5   284.6  214.77
   312.3  213.17   591.9   210.6   611.9  205.34   621.9  207.21   631.9  210.67
   788.2  214.85     839  217.88   895.9  220.06   910.8   221.8   961.7  224.38
  1018.6  226.14  1033.5  227.49  1090.4  228.46  1120.2  230.12  1126.3  229.65
  1141.2  230.65    1234  233.04    1249  234.34  1305.9  234.84  1335.7  236.66
  1356.7  236.03  1485.4   237.9  1494.3  237.34  1545.1  238.88  1592.5  239.11
#Mann= 3 , 0 , 0
       0     .11       0   591.9     .07       0   631.9     .11       0
Bank Sta=591.9,631.9
XS Rating Curve= 0 ,0
Exp/Cntr=0.3,0.1

Chan Stop Cuts=-1
Use User Specified Reach Order=0
Composite Channel Slope=5