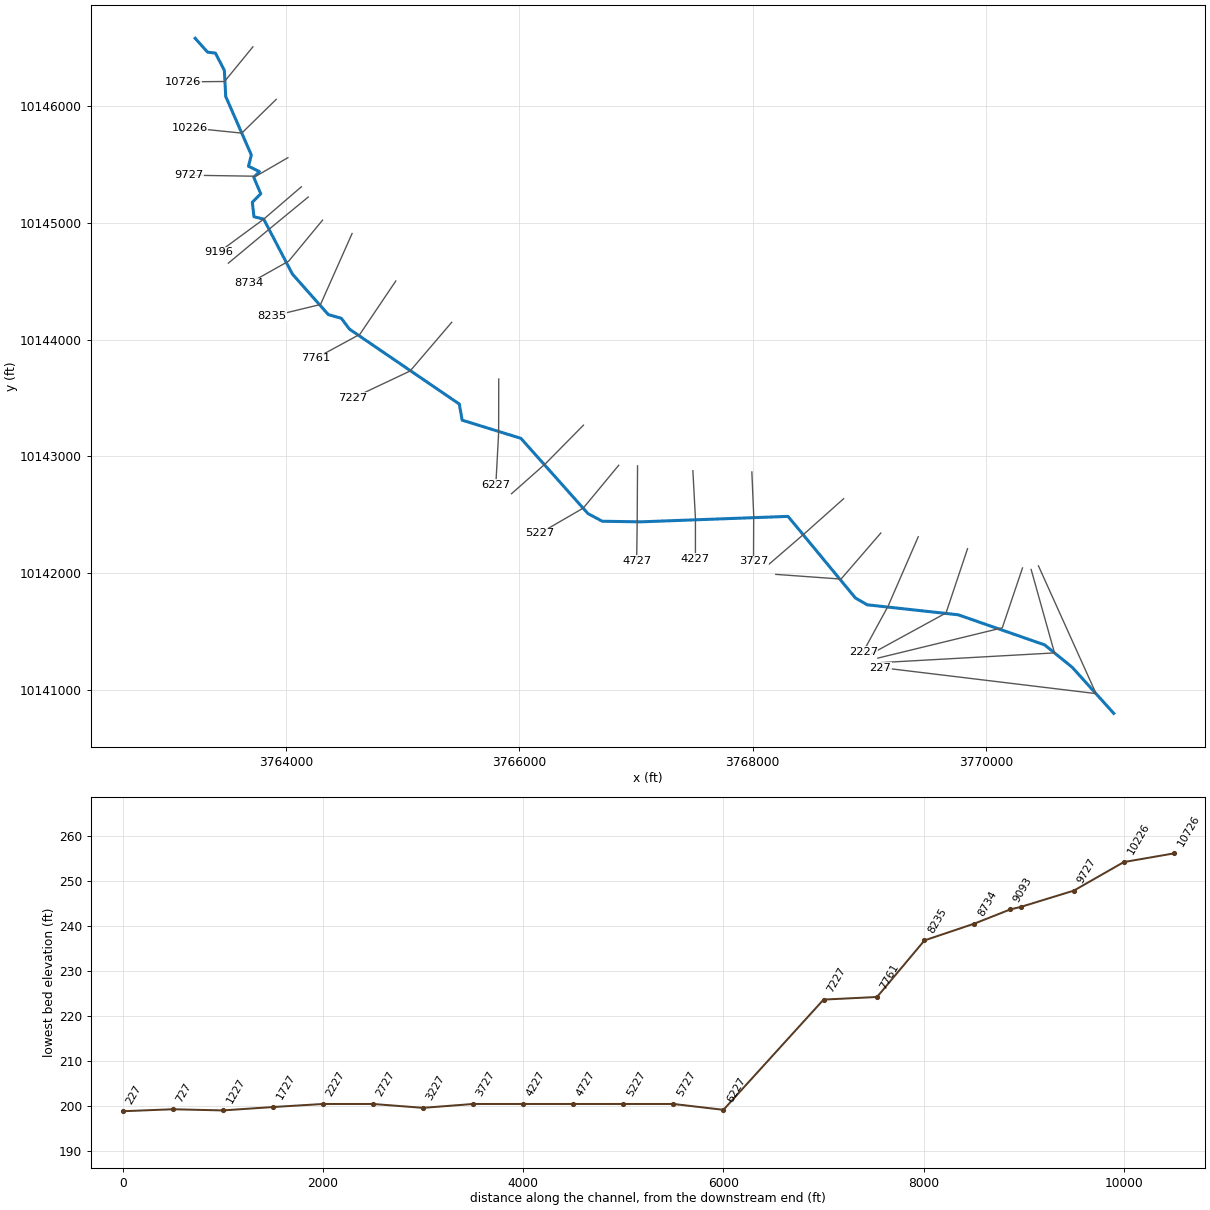
--- Conroe Lake 119.prj (project) ---

Proj Title=Conroe Lake 119 Base Level Engineering
Current Plan=p01
Default Exp/Contr=0.3,0.1
English Units
Geom File=g01
Flow File=f01
Flow File=f02
Plan File=p01
Y Axis Title=Elevation
X Axis Title(PF)=Main Channel Distance
X Axis Title(XS)=Station
BEGIN DESCRIPTION:
Conroe Lake 119
END DESCRIPTION:
DSS Export Rating Curves= 0
DSS Export Rating Curve Sorted= 0
DSS Export Volume Flow Curves= 0
DXF OffsetX= 0
DXF OffsetY= 0
DXF ScaleX= 1
DXF ScaleY= 10

--- Conroe Lake 119.p01 (plan) ---

Plan Title=Multiple Run
Short Identifier=Multiple
Geom File=g01
Flow File=f01
Subcritical Flow
K Sum by GR= 0
Std Step Tol= 0.01
Critical Tol= 0.01
Num of Std Step Trials= 20
Max Error Tol= 0.3
Flow Tol Ratio= 0.001
Split Flow NTrial= 30
Split Flow Tol= 0.02
Split Flow Ratio= 0.02
Log Output Level= 0
Friction Slope Method= 1
Unsteady Friction Slope Method= 2
Unsteady Bridges Friction Slope Method= 1
Parabolic Critical Depth
Global Vel Dist=  1 , 1 , 1
Global Log Level= 0
CheckData=True
Encroach Param= -1, 0, 0, 0
BEGIN DESCRIPTION:
Multiple Run
END DESCRIPTION:

--- Conroe Lake 119.f01 (steady flow) ---

Flow Title=Multiple
Program Version=4.10
Number of Profiles= 7
Profile Names=10-year,25-year,50-year,1pct_min,100-year,1pct_plu,500-year
River Rch & RM=Conroe Lake 119,Reach-1         ,10726
     771    1054    1433     640    1934    5841    3646
Boundary for River Rch & Prof#=Conroe Lake 119,Reach-1         , 1
Up Type= 0
Dn Type= 3
Dn Slope=0.005
Boundary for River Rch & Prof#=Conroe Lake 119,Reach-1         , 2
Up Type= 0
Dn Type= 3
Dn Slope=0.005
Boundary for River Rch & Prof#=Conroe Lake 119,Reach-1         , 3
Up Type= 0
Dn Type= 3
Dn Slope=0.005
Boundary for River Rch & Prof#=Conroe Lake 119,Reach-1         , 4
Up Type= 0
Dn Type= 3
Dn Slope=0.005
Boundary for River Rch & Prof#=Conroe Lake 119,Reach-1         , 5
Up Type= 0
Dn Type= 3
Dn Slope=0.005
Boundary for River Rch & Prof#=Conroe Lake 119,Reach-1         , 6
Up Type= 0
Dn Type= 3
Dn Slope=0.005
Boundary for River Rch & Prof#=Conroe Lake 119,Reach-1         , 7
Up Type= 0
Dn Type= 3
Dn Slope=0.005
DSS Import GetInterval= 0
DSS Import GetPeak= 0
DSS Import FillOption= 0

--- Conroe Lake 119.f02 (steady flow) ---

Flow Title=Orig_BLE_Flow
Program Version=4.10
Number of Profiles= 7
Profile Names=10-year,25-year,50-year,1pct_min,100-year,1pct_plu,500-year
River Rch & RM=Conroe Lake 119,Reach-1         ,10726
     771    1033    1246     493    1488    4495    2120
Boundary for River Rch & Prof#=Conroe Lake 119,Reach-1         , 1
Up Type= 0
Dn Type= 3
Dn Slope=0.005
Boundary for River Rch & Prof#=Conroe Lake 119,Reach-1         , 2
Up Type= 0
Dn Type= 3
Dn Slope=0.005
Boundary for River Rch & Prof#=Conroe Lake 119,Reach-1         , 3
Up Type= 0
Dn Type= 3
Dn Slope=0.005
Boundary for River Rch & Prof#=Conroe Lake 119,Reach-1         , 4
Up Type= 0
Dn Type= 3
Dn Slope=0.005
Boundary for River Rch & Prof#=Conroe Lake 119,Reach-1         , 5
Up Type= 0
Dn Type= 3
Dn Slope=0.005
Boundary for River Rch & Prof#=Conroe Lake 119,Reach-1         , 6
Up Type= 0
Dn Type= 3
Dn Slope=0.005
Boundary for River Rch & Prof#=Conroe Lake 119,Reach-1         , 7
Up Type= 0
Dn Type= 3
Dn Slope=0.005
DSS Import GetInterval= 0
DSS Import GetPeak= 0
DSS Import FillOption= 0

--- Conroe Lake 119.g01 (geometry) ---

Geom Title=Existing Conditions
Program Version=4.10

River Reach=Conroe Lake 119 ,Reach-1
Reach XY= 30
      3763223.61     10146584.23      3763329.96      10146465.6
      3763397.25     10146457.49      3763473.52     10146309.42
      3763485.27     10146085.72      3763704.75     10145584.34
      3763680.13     10145487.63      3763774.47     10145441.36
      3763725.03     10145392.97      3763785.53     10145251.68
      3763713.21      10145178.9      3763727.19     10145054.84
      3763810.74     10145034.22      3764056.47     10144563.54
      3764363.92     10144216.15      3764475.75      10144184.1
      3764545.33      10144091.3       3765486.2     10143449.17
      3765510.82     10143310.97      3766013.98     10143155.14
      3766589.04     10142509.52      3766711.43     10142444.42
      3767036.96     10142439.21      3768302.58     10142486.08
       3768878.1     10141788.17      3768979.66     10141728.27
      3769760.91     10141642.33       3770500.5     10141384.52
      3770737.48     10141191.81      3771092.79     10140797.35

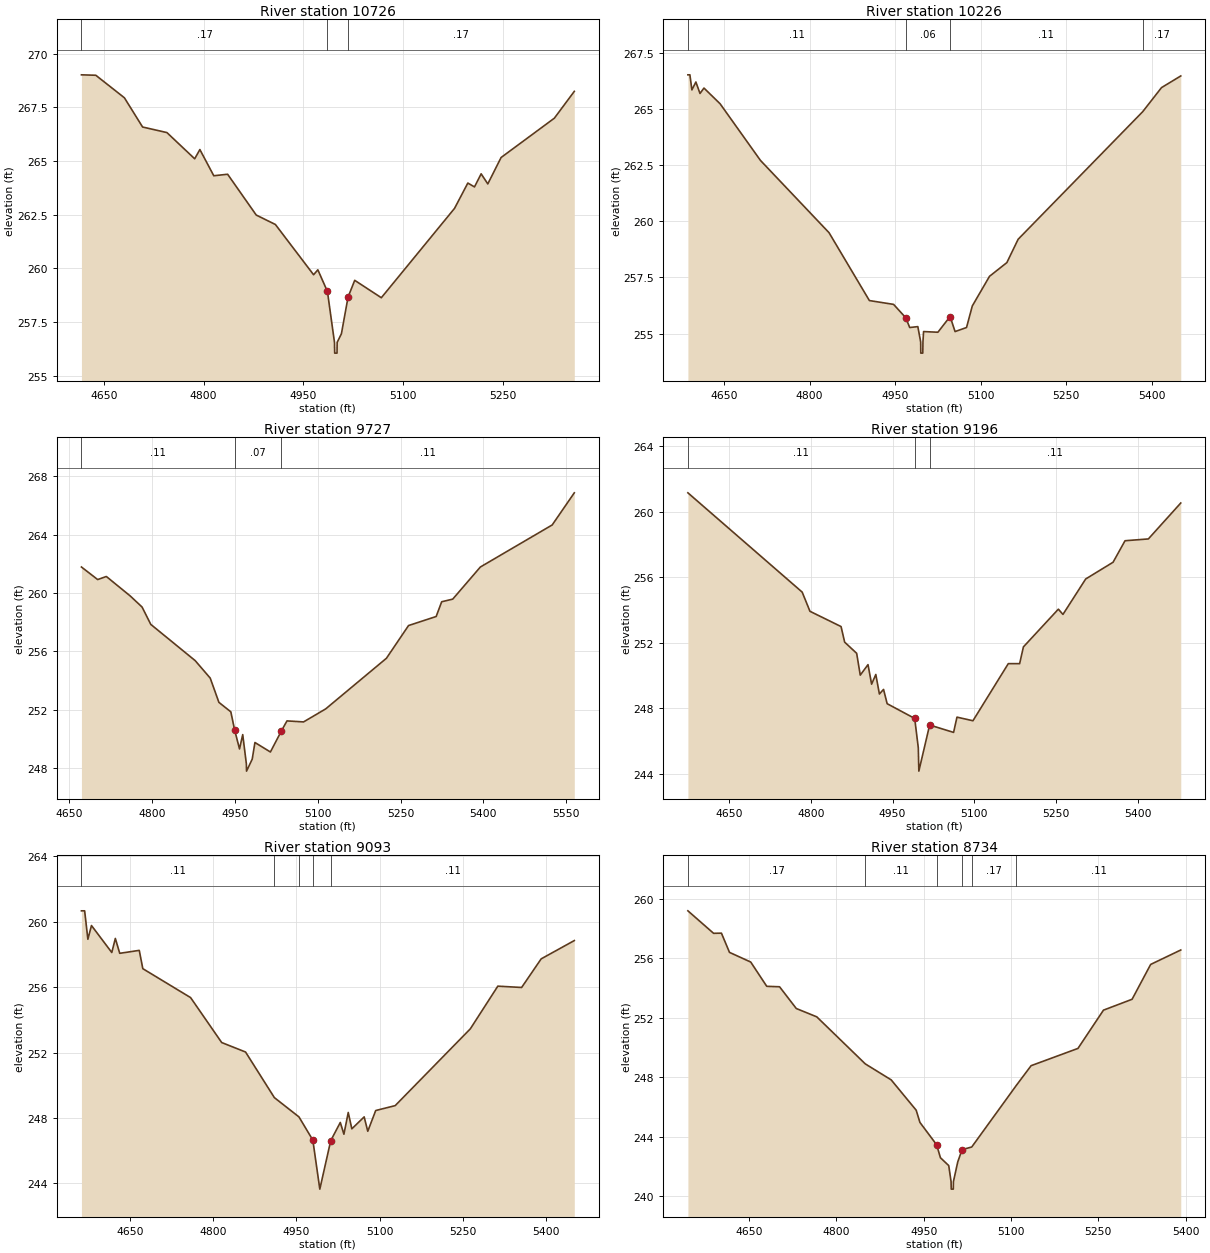
Type RM Length L Ch R = 1 ,10726   ,500,500,500
BEGIN DESCRIPTION:
Conroe Lake 119 1.0
END DESCRIPTION:
XS GIS Cut Line= 3
      3763717.87      10146511.1      3763475.02     10146214.29
      3763117.83     10146211.07
#Sta/Elev= 30
  4616.5  269.01  4638.1  268.99  4681.1  267.94  4708.4  266.58    4745  266.32
  4786.7   265.1  4794.5  265.53  4815.4  264.31  4836.2  264.38  4879.2  262.48
    4908  262.04  4965.4   259.7  4971.8  259.93  4986.2  258.92  4996.8  256.55
  4997.1  256.05  5000.6  256.05  5000.8  256.55  5007.2  256.95  5017.2  258.66
  5027.2  259.44  5067.2  258.63  5177.2  262.79  5197.2  263.97  5207.2  263.79
  5217.2   264.4  5227.2  263.93  5247.2  265.16  5327.2  266.99  5357.2  268.24
#Mann= 3 , 0 , 0
  4616.5     .17       0  4986.2     .09       0  5017.2     .17       0
Bank Sta=4986.2,5017.2
XS Rating Curve= 0 ,0
Exp/Cntr=0.3,0.1

Type RM Length L Ch R = 1 ,10226   ,499,499,499
BEGIN DESCRIPTION:
Conroe Lake 119 2.0
END DESCRIPTION:
XS GIS Cut Line= 3
      3763917.82     10146061.04      3763622.81     10145771.72
      3763174.24      10145817.5
#Sta/Elev= 30
  4586.8  266.52  4590.3  266.52  4593.8  265.85  4600.8   266.2    4608  265.69
    4615  265.93  4643.3  265.23    4714  262.71  4834.3  259.49    4905  256.47
  4947.4   256.3  4968.6  255.71  4975.7  255.27  4989.9  255.31  4994.9  254.63
  4995.1  254.13  4998.6  254.13  4998.9  254.63    5000  255.09  5025.1  255.06
  5046.5  255.76  5055.2  255.09  5075.3  255.27  5085.4  256.23  5115.6  257.55
    5146  258.16  5165.8   259.2  5384.2  264.88  5417.1  265.95  5450.9  266.47
#Mann= 4 ,-1 , 0
  4586.8     .11       0  4968.6     .06       0  5046.5     .11       0
  5384.2     .17       0
Bank Sta=4968.6,5046.5
XS Rating Curve= 0 ,0
Exp/Cntr=0.3,0.1

Type RM Length L Ch R = 1 ,9727    ,531,531,531
BEGIN DESCRIPTION:
Conroe Lake 119 3.0
END DESCRIPTION:
XS GIS Cut Line= 4
      3764017.83     10145561.06      3763752.37     10145407.11
      3763732.31     10145402.31      3763167.88     10145411.07
#Sta/Elev= 30
  4672.5  261.78  4701.9  260.92  4717.6  261.13  4760.7   259.8  4782.2  259.04
    4798  257.85  4878.3  255.37  4905.6  254.17  4921.3  252.51  4942.9  251.86
  4949.9  250.59  4958.6  249.32  4964.4   250.3    4971   248.3  4971.3   247.8
  4981.6  248.62  4986.5  249.76  5014.5  249.11  5034.5  250.56  5044.5  251.24
  5074.5  251.17  5114.5  252.06  5224.5  255.53  5264.5  257.77  5314.5  258.39
  5324.5   259.4  5344.5  259.58  5394.5  261.78  5524.5  264.66  5564.5  266.86
#Mann= 3 , 0 , 0
  4672.5     .11       0  4949.9     .07       0  5034.5     .11       0
Bank Sta=4949.9,5034.5
XS Rating Curve= 0 ,0
Exp/Cntr=0.3,0.1

Type RM Length L Ch R = 1 ,9196    ,103,103,103
BEGIN DESCRIPTION:
Conroe Lake 119 4.0
END DESCRIPTION:
XS GIS Cut Line= 3
      3764133.12     10145311.47      3763810.74     10145034.22
      3763425.53     10144750.53
#Sta/Elev= 30
  4574.8  261.14  4784.3  255.09  4798.6  253.92  4855.6  252.99  4862.2  252.04
  4884.2  251.36  4890.8  250.03    4905  250.67  4911.6  249.48  4919.3  250.07
  4925.9  248.88  4933.5  249.16  4940.1  248.29  4990.6  247.39  4997.2   245.6
  4998.2  244.18    5018  246.99  5061.9  246.54  5068.1  247.47  5097.4  247.25
  5162.2  250.73    5183  250.73  5189.9  251.75    5254  254.05  5262.4  253.73
  5304.1  255.89  5354.3  256.91  5376.2  258.22    5419  258.33  5478.4  260.52
#Mann= 3 , 0 , 0
  4574.8     .11       0  4990.6     .06       0    5018     .11       0
#XS Ineff= 2 ,-1
    4905  4884.2  250.67  4919.3    4905  250.07
Permanent Ineff=
       F       F
Bank Sta=4990.6,5018
XS Rating Curve= 0 ,0
Exp/Cntr=0.3,0.1

Type RM Length L Ch R = 1 ,9093    ,359,359,359
BEGIN DESCRIPTION:
Mapping XS 8e02ba44
END DESCRIPTION:
XS GIS Cut Line= 3
       3764191.8     10145223.49      3763854.35     10144945.67
      3763507.98       10144657.
#Sta/Elev= 30
  4562.9  260.67  4568.7  260.67  4574.5  258.93    4581  259.77  4617.6  258.12
    4624  258.98  4631.9  258.07  4667.1  258.25  4673.5  257.13  4759.6  255.36
  4815.6  252.61  4858.6  252.03  4910.5  249.24  4954.8  248.06  4979.8  246.64
  4992.4  243.64 5012.01   246.6  5029.3  247.72  5035.8     247  5043.6  248.33
  5050.1  247.33  5072.3  248.06  5078.8  247.18  5093.1  248.45  5128.2  248.75
  5263.6  253.45  5313.1  256.06    5356  255.98  5391.2  257.73  5450.9  258.85
#Mann= 5 ,-1 , 0
  4562.9     .11       0  4910.5     .17       0  4954.8     .11       0
  4979.8     .06       0 5012.01     .11       0
Bank Sta=4979.8,5012.01
XS Rating Curve= 0 ,0
Exp/Cntr=0.3,0.1

Type RM Length L Ch R = 1 ,8734    ,499,499,499
BEGIN DESCRIPTION:
Conroe Lake 119 5.0
END DESCRIPTION:
XS GIS Cut Line= 3
      3764314.67     10145025.53      3764025.27      10144674.7
        3763684.     10144482.85
#Sta/Elev= 30
  4545.2  259.18  4589.3  257.67  4602.8  257.68  4616.6  256.39  4653.1  255.74
  4680.6  254.11  4702.6  254.08  4731.3  252.62  4766.5  252.06  4849.8   248.9
  4894.2  247.83  4937.2  245.79  4943.6  244.97  4972.3  243.47  4978.8   242.6
  4993.1  242.07  4997.1  240.99  4997.4  240.49  5000.9  240.49  5001.1  240.99
  5008.5  242.31  5015.9  243.14  5032.6  243.32  5109.4  247.47  5134.5  248.78
    5215  249.94  5258.8  252.51  5307.9  253.24  5339.8  255.58  5391.5  256.55
#Mann= 6 ,-1 , 0
  4545.2     .17       0  4849.8     .11       0  4972.3     .07       0
  5015.9     .11       0  5032.6     .17       0  5109.4     .11       0
Bank Sta=4972.3,5015.9
XS Rating Curve= 0 ,0
Exp/Cntr=0.3,0.1

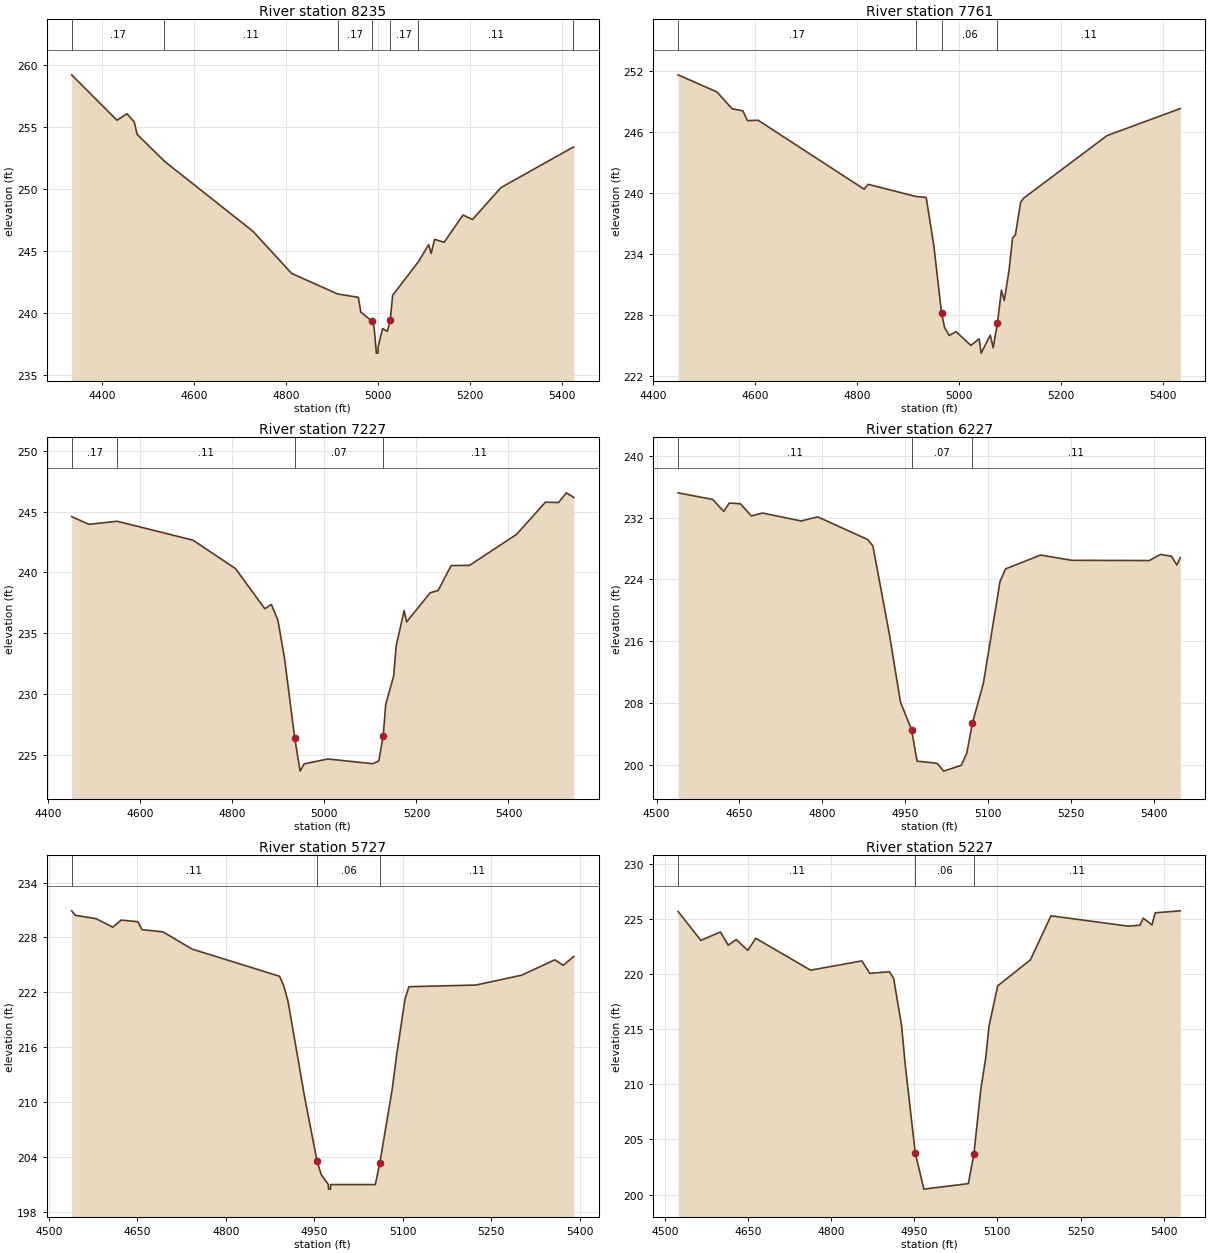
Type RM Length L Ch R = 1 ,8235    ,474,474,474
BEGIN DESCRIPTION:
Conroe Lake 119 6.0
END DESCRIPTION:
XS GIS Cut Line= 3
      3764567.87     10144911.12      3764297.36     10144302.64
      3763883.85     10144202.36
#Sta/Elev= 30
  4334.1  259.21  4432.6  255.55  4454.5  256.07  4470.2   255.4  4476.4  254.41
  4535.7  252.24  4728.1  246.59  4812.2  243.19  4912.4  241.53  4957.2  241.26
  4962.6  240.07  4985.9  239.37  4991.4  238.86  4996.4  236.76  4999.9  236.76
  5000.1  237.26  5009.8  238.74  5020.1  238.51  5026.5   239.4  5031.7  241.42
  5087.9  244.15  5110.1  245.51  5115.3   244.8    5123  245.94  5143.6   245.7
  5184.7   247.9  5205.3  247.54    5267  250.11  5424.2  253.38  5425.5  253.38
#Mann= 7 ,-1 , 0
  4334.1     .17       0  4535.7     .11       0  4912.4     .17       0
  4985.9     .09       0  5026.5     .17       0  5087.9     .11       0
  5424.2     .17       0
Bank Sta=4985.9,5026.5
XS Rating Curve= 0 ,0
Exp/Cntr=0.3,0.1

Type RM Length L Ch R = 1 ,7761    ,534,534,534
BEGIN DESCRIPTION:
Conroe Lake 119 7.0
END DESCRIPTION:
XS GIS Cut Line= 3
      3764942.14     10144504.04      3764634.31     10144046.81
       3764252.4      10143839.6
#Sta/Elev= 30
  4448.8  251.59  4524.9  249.91  4554.9  248.25  4575.9  248.05  4584.9  247.09
  4605.9  247.12    4814  240.34  4821.8  240.82  4915.3  239.63  4935.8  239.52
  4950.8  234.76  4965.8  228.18  4971.8  226.75  4980.7  225.95  4994.4  226.33
  5023.5  224.98  5039.6  225.62  5043.6  224.22  5061.5  225.99  5067.2  224.75
  5075.6   227.2  5083.4  230.41    5089   229.4  5098.4  232.38  5105.2  235.53
  5110.9  235.87  5121.1  239.06  5127.1  239.46  5290.6  245.61  5434.5  248.27
#Mann= 4 ,-1 , 0
  4448.8     .17       0  4915.3     .11       0  4965.8     .06       0
  5075.6     .11       0
#XS Ineff= 2 , 0
       0                  5083.4       0  230.41
Permanent Ineff=
       F       F
Bank Sta=4965.8,5075.6
XS Rating Curve= 0 ,0
Exp/Cntr=0.3,0.1

Type RM Length L Ch R = 1 ,7227    ,1000,1000,1000
BEGIN DESCRIPTION:
Conroe Lake 119 8.0
END DESCRIPTION:
XS GIS Cut Line= 3
      3765421.35     10144149.94      3765064.85     10143732.31
      3764574.79     10143500.77
#Sta/Elev= 30
  4450.9  244.59  4488.5  243.96  4549.8  244.21  4714.7  242.65  4806.9  240.31
  4870.6  237.01  4884.9  237.36  4899.1  236.05  4913.4  232.94  4935.4   226.4
  4947.3  223.64  4956.2  224.24  5007.7  224.64    5105  224.25  5118.3  224.48
  5127.8  226.55  5133.3  229.13  5150.5  231.47  5156.1  233.97  5173.3  236.86
  5178.8  235.93  5229.9  238.32  5247.1  238.51  5275.4  240.56  5315.4  240.58
  5417.5  243.13  5480.3  245.78  5508.6  245.75  5525.8  246.55    5542  246.17
#Mann= 4 ,-1 , 0
  4450.9     .17       0  4549.8     .11       0  4935.4     .07       0
  5127.8     .11       0
Bank Sta=4935.4,5127.8
XS Rating Curve= 0 ,0
Exp/Cntr=0.3,0.1

Type RM Length L Ch R = 1 ,6227    ,500,500,500
BEGIN DESCRIPTION:
Conroe Lake 119 10.0
END DESCRIPTION:
XS GIS Cut Line= 3
       3765824.1     10143663.76      3765823.32     10143202.66
       3765799.1     10142755.01
#Sta/Elev= 30
  4538.9   235.2  4601.6  234.34  4621.6   232.8  4631.6  233.88  4651.6  233.79
  4671.6   232.2  4691.6  232.59  4761.6  231.56  4791.6  232.09  4881.6  229.18
  4891.6  228.34  4921.6  216.86  4941.6  208.12  4961.6  204.57  4971.6  200.49
  5007.7  200.22  5019.9   199.2  5051.7  199.96  5061.7  201.53  5071.7  205.38
  5091.7  210.57  5121.8  223.72  5131.8  225.36  5195.3  227.15    5252  226.47
  5392.2  226.44  5412.2  227.23  5432.2     227  5442.2  225.86  5448.3  226.82
#Mann= 3 , 0 , 0
  4538.9     .11       0  4961.6     .07       0  5071.7     .11       0
Bank Sta=4961.6,5071.7
XS Rating Curve= 0 ,0
Exp/Cntr=0.3,0.1

Type RM Length L Ch R = 1 ,5727    ,500,500,500
BEGIN DESCRIPTION:
Conroe Lake 119 11.0
END DESCRIPTION:
XS GIS Cut Line= 3
      3766549.78     10143267.95      3766225.72     10142939.08
      3765933.63      10142680.2
#Sta/Elev= 30
  4538.3  230.91  4544.5  230.42  4579.9  230.05  4608.1  229.12  4622.3   229.9
  4650.6  229.72  4657.7  228.85    4693  228.62  4742.6  226.73    4891  223.76
  4898.1  222.73  4905.2  221.08  4933.4  210.61  4954.7  203.54  4961.7  202.09
  4973.9     201  4974.1   200.5  4977.6   200.5  4977.9     201  5053.5     201
  5061.1  203.34    5082  211.35  5089.5  215.08  5103.7  221.19  5110.4  222.62
  5224.2   222.8  5301.9  223.88    5358  225.56  5372.2  224.95  5390.3  225.93
#Mann= 3 , 0 , 0
  4538.3     .11       0  4954.7     .06       0  5061.1     .11       0
Bank Sta=4954.7,5061.1
XS Rating Curve= 0 ,0
Exp/Cntr=0.3,0.1

Type RM Length L Ch R = 1 ,5227    ,500,500,500
BEGIN DESCRIPTION:
Conroe Lake 119 12.0
END DESCRIPTION:
XS GIS Cut Line= 3
      3766851.87     10142924.21      3766548.61     10142557.32
      3766176.62     10142341.62
#Sta/Elev= 30
    4524  225.67    4565  223.05  4600.2  223.81  4614.5  222.62  4628.9  223.12
  4649.7  222.14    4664  223.24    4763  220.35  4855.5  221.19  4869.8  220.06
    4905  220.21  4912.8  219.62  4927.2  215.31  4933.7  211.78 4951.91  203.75
  4967.4   200.5  5047.6     201  5057.6  203.66  5070.2  209.59  5079.1  212.44
  5084.9  215.28  5100.6  218.93  5159.5  221.28  5196.7  225.28  5335.9  224.34
  5357.4  224.43  5363.2  225.07  5378.9  224.45  5384.7  225.55    5430  225.73
#Mann= 3 , 0 , 0
    4524     .11       0 4951.91     .06       0  5057.6     .11       0
Bank Sta=4951.91,5057.6
XS Rating Curve= 0 ,0
Exp/Cntr=0.3,0.1

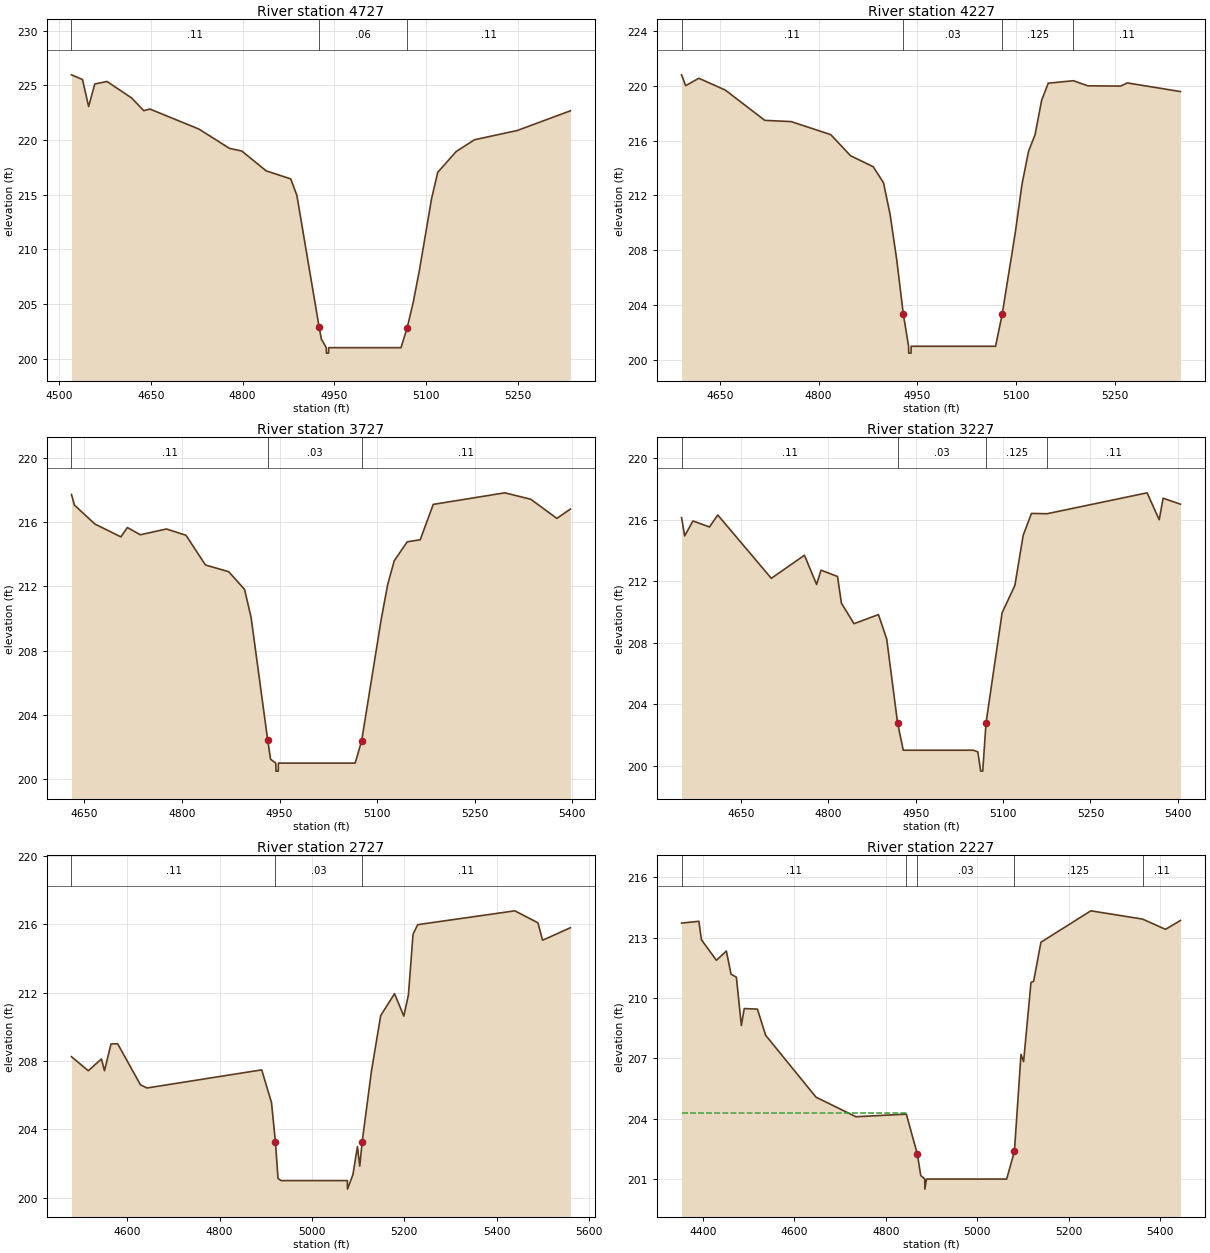
Type RM Length L Ch R = 1 ,4727    ,500,500,500
BEGIN DESCRIPTION:
Conroe Lake 119 13.0
END DESCRIPTION:
XS GIS Cut Line= 3
      3767013.34     10142919.03      3767010.15     10142439.64
      3767005.66     10142104.47
#Sta/Elev= 30
  4520.6  225.96  4538.6  225.53  4548.6  223.06  4558.6  225.12  4578.6  225.35
  4618.6  223.85  4638.6  222.68  4648.6  222.83  4728.6     221  4778.6  219.23
  4798.6  218.99  4838.6  217.17  4878.6  216.44  4888.6  214.93    4925  202.86
  4928.6  201.79  4936.6     201  4936.8   200.5  4940.3   200.5  4940.6     201
  5058.6     201  5068.6   202.8  5078.6  205.16  5088.6  208.06  5108.6  214.66
  5118.6  217.04  5148.6  218.94  5178.6  220.02  5248.6  220.87  5335.2  222.67
#Mann= 3 , 0 , 0
  4520.6     .11       0    4925     .06       0  5068.6     .11       0
Bank Sta=4925,5068.6
XS Rating Curve= 0 ,0
Exp/Cntr=0.3,0.1

Type RM Length L Ch R = 1 ,4227    ,500,500,500
BEGIN DESCRIPTION:
Conroe Lake 119 14.0
END DESCRIPTION:
XS GIS Cut Line= 3
      3767487.29     10142877.36      3767509.15     10142469.94
      3767509.11     10142120.24
#Sta/Elev= 30
    4592  220.79  4598.3     220  4618.3  220.54  4658.4  219.68  4718.5  217.47
  4758.5  217.38  4818.6  216.43  4848.7  214.89  4883.1  214.09  4898.7  212.92
  4908.7  210.62  4918.8  207.31  4928.8  203.35  4936.8     201    4937   200.5
  4940.5   200.5  4940.8     201  5068.9     201  5078.9  203.32  5098.9   209.3
  5108.9  212.77  5118.9   215.2  5128.9  216.43  5138.9  218.94  5148.9  220.18
  5187.1  220.36  5208.9  219.99  5258.9  219.97  5268.9   220.2  5349.7  219.57
#Mann= 4 ,-1 , 0
    4592     .11       0  4928.8     .03       0  5078.9    .125       0
  5187.1     .11       0
Bank Sta=4928.8,5078.9
XS Rating Curve= 0 ,0
Exp/Cntr=0.3,0.1

Type RM Length L Ch R = 1 ,3727    ,500,500,500
BEGIN DESCRIPTION:
Conroe Lake 119 15.0
END DESCRIPTION:
XS GIS Cut Line= 3
       3767992.5     10142866.89      3768008.28     10142497.33
      3768006.68     10142100.13
#Sta/Elev= 30
  4630.1  217.72  4634.6  217.06    4666  215.88    4706  215.08    4716  215.66
    4736  215.21  4776.1  215.57  4806.1  215.18  4836.1  213.33  4871.9  212.91
  4896.2  211.81  4906.2  210.08 4931.82  202.42  4936.2  201.24  4944.2     201
  4944.5   200.5    4948   200.5  4948.2     201  5066.3     201  5076.3   202.4
  5106.3  209.95  5116.3  212.12  5126.3  213.59  5146.3  214.77  5166.3   214.9
  5186.3   217.1  5296.3  217.82  5336.3  217.42  5376.3  216.23  5397.2  216.81
#Mann= 3 , 0 , 0
  4630.1     .11       0 4931.82     .03       0  5076.3     .11       0
Bank Sta=4931.82,5076.3
XS Rating Curve= 0 ,0
Exp/Cntr=0.3,0.1

Type RM Length L Ch R = 1 ,3227    ,500,500,500
BEGIN DESCRIPTION:
Conroe Lake 119 16.0
END DESCRIPTION:
XS GIS Cut Line= 3
      3768778.98     10142637.77       3768441.4      10142336.9
      3768135.14     10142072.35
#Sta/Elev= 30
  4547.8  216.13  4553.2  214.94  4567.4  215.91  4595.8  215.52    4610   216.3
    4702  212.18  4758.9  213.68  4779.8  211.78  4787.3  212.71  4815.7   212.3
  4822.4  210.56    4844  209.23    4886  209.82  4900.2  208.23 4918.86  202.77
  4928.6     201  5049.1     201  5056.7  200.89  5061.6  199.64  5065.1  199.64
  5070.8  202.79  5098.4  209.94  5120.3  211.72  5134.6  214.98  5148.8   216.4
  5175.5  216.38  5347.4  217.74  5368.2  215.99  5374.9  217.39  5404.7     217
#Mann= 4 ,-1 , 0
  4547.8     .11       0 4918.86     .03       0  5070.8    .125       0
  5175.5     .11       0
Bank Sta=4918.86,5070.8
XS Rating Curve= 0 ,0
Exp/Cntr=0.3,0.1

Type RM Length L Ch R = 1 ,2727    ,500,500,500
BEGIN DESCRIPTION:
Conroe Lake 119 17.0
END DESCRIPTION:
XS GIS Cut Line= 3
      3769096.96     10142343.19      3768756.42     10141948.62
      3768197.68     10141989.02
#Sta/Elev= 30
  4478.8  208.25  4515.2  207.43  4543.7  208.12  4550.3  207.43  4564.5     209
  4578.8  209.01  4628.2  206.61  4642.4  206.42  4891.1  207.48  4912.3  205.57
 4920.91  203.24  4926.5  201.12  4933.1     201  5076.8     201    5077   200.5
  5088.8  201.35  5098.6  202.99  5103.6  201.85  5108.9  203.28  5128.9   207.4
    5149  210.66    5179  211.94  5199.1  210.63  5209.1  211.87  5219.1  215.42
  5229.2  215.98  5439.7  216.79  5489.8  216.09  5499.9  215.07  5560.2   215.8
#Mann= 3 , 0 , 0
  4478.8     .11       0 4920.91     .03       0  5108.9     .11       0
Bank Sta=4920.91,5108.9
XS Rating Curve= 0 ,0
Exp/Cntr=0.3,0.1

Type RM Length L Ch R = 1 ,2227    ,500,500,500
BEGIN DESCRIPTION:
Conroe Lake 119 18.0
END DESCRIPTION:
XS GIS Cut Line= 3
      3769417.86     10142311.09      3769160.01     10141717.58
      3768947.38     10141327.01
#Sta/Elev= 30
  4352.9  213.73  4390.8  213.82  4396.5   212.9  4429.2  211.88    4451  212.34
  4461.2  211.19  4472.9  211.04  4483.8  208.64  4490.1  209.48    4519  209.45
    4537  208.15  4647.3  205.07  4734.5   204.1  4844.8  204.23  4869.1  202.23
  4876.3  201.18  4885.1     201  4885.3   200.5  4889.1     201  5064.3     201
 5081.36  202.38  5095.7   207.2  5101.4  206.84  5117.6  210.78  5123.3  210.83
  5139.4  212.78  5248.6  214.34  5361.7  213.93    5412  213.42  5444.7  213.86
#Mann= 5 ,-1 , 0
  4352.9     .11       0  4844.8    .125       0  4869.1     .03       0
 5081.36    .125       0  5361.7     .11       0
#XS Ineff= 2 , 0
       0  4845.6  204.27               0
Permanent Ineff=
       F       F
Bank Sta=4869.1,5081.36
XS Rating Curve= 0 ,0
Exp/Cntr=0.3,0.1

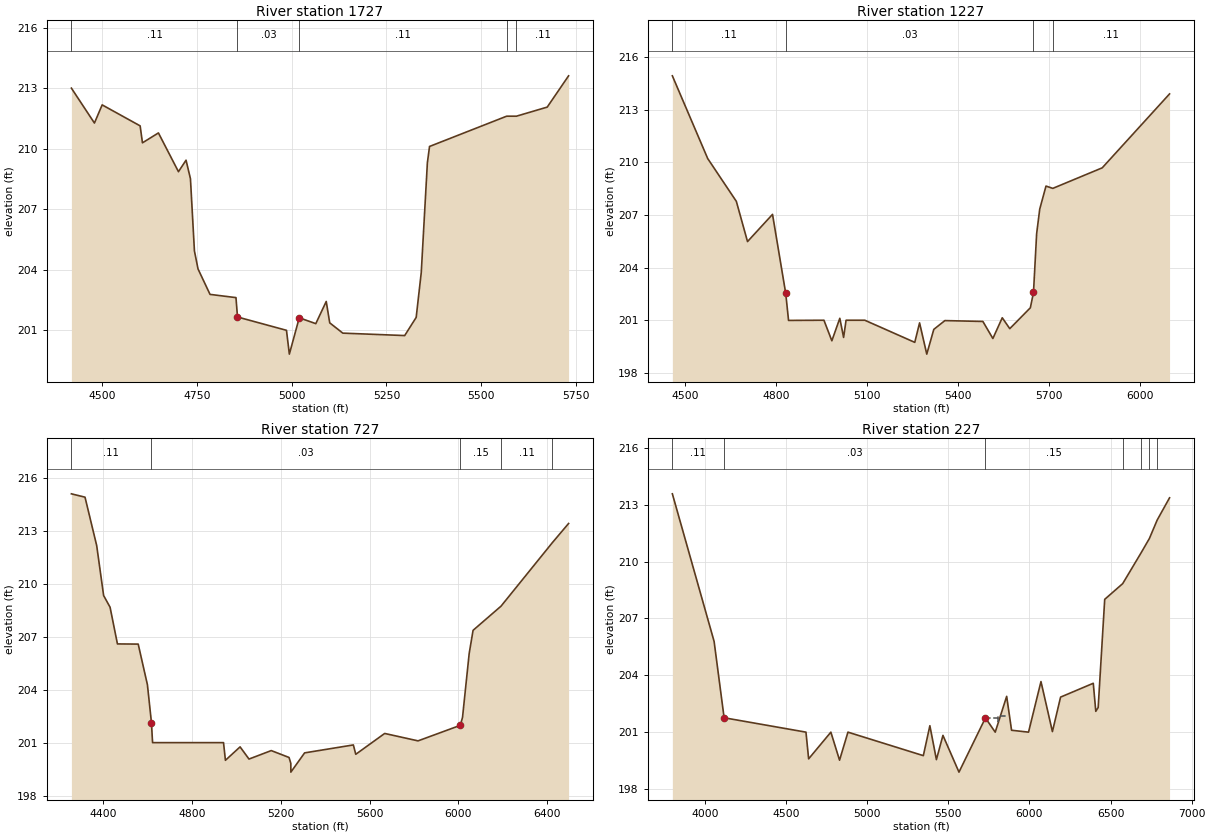
Type RM Length L Ch R = 1 ,1727    ,500,500,500
BEGIN DESCRIPTION:
Conroe Lake 119 19.0
END DESCRIPTION:
XS GIS Cut Line= 3
      3769840.03     10142208.68        3769656.     10141658.23
      3769015.36     10141308.04
#Sta/Elev= 30
  4419.6     213  4480.3  211.27  4500.7  212.17  4600.8  211.13  4606.9  210.29
    4649  210.78  4701.8  208.86  4721.8  209.43  4733.4  208.51  4743.9  204.93
  4753.4  204.04    4785  202.78  4853.4  202.62 4857.39  201.66  4986.5     201
  4994.1  199.82  5020.2  201.62  5063.8  201.33  5091.3  202.43  5100.5  201.37
    5135  200.86  5298.1  200.74  5328.4  201.64  5341.8  203.87  5357.9   209.3
  5363.6  210.11  5566.9  211.61  5592.7  211.61  5673.8  212.06  5730.1  213.61
#Mann= 5 ,-1 , 0
  4419.6     .11       0 4857.39     .03       0  5020.2     .11       0
  5566.9    .125       0  5592.7     .11       0
Bank Sta=4857.39,5020.2
XS Rating Curve= 0 ,0
Exp/Cntr=0.3,0.1

Type RM Length L Ch R = 1 ,1227    ,500,500,500
BEGIN DESCRIPTION:
Conroe Lake 119 20.0
END DESCRIPTION:
XS GIS Cut Line= 3
      3770310.95     10142043.76      3770137.88     10141530.77
      3769072.32     10141271.28
#Sta/Elev= 30
  4458.6  214.92    4575  210.21  4669.4  207.77  4706.2  205.48  4788.6  207.03
  4832.1  202.53  4841.4  200.99    4958     201  4984.1  199.83  5010.3  201.11
  5022.8  200.02  5030.9     201  5092.7     201  5257.3  199.74  5273.1  200.85
  5296.8  199.07    5320  200.48  5356.5  200.98  5481.7  200.93  5514.6  199.96
  5545.5  201.14  5570.3  200.52  5638.1  201.71  5648.4  202.58  5658.8  205.93
    5669  207.33  5689.6  208.64  5712.1  208.51  5874.9  209.68  6096.7  213.89
#Mann= 4 ,-1 , 0
  4458.6     .11       0  4832.1     .03       0  5648.4     .15       0
  5712.1     .11       0
Bank Sta=4832.1,5648.4
XS Rating Curve= 0 ,0
Exp/Cntr=0.3,0.1

Type RM Length L Ch R = 1 ,727     ,500,500,500
BEGIN DESCRIPTION:
Conroe Lake 119 21.0
END DESCRIPTION:
XS GIS Cut Line= 3
      3770385.14     10142030.73      3770585.06     10141315.75
        3769091.     10141232.19
#Sta/Elev= 30
  4257.6  215.09  4318.9   214.9  4371.5  212.16  4402.7  209.33  4431.7  208.67
  4464.9  206.59  4558.4  206.58  4599.9  204.28    4618  202.14  4623.1     201
  4942.6     201  4951.2     200  5017.2  200.76  5057.3  200.07  5157.5  200.55
  5237.6  200.16  5245.6  199.83  5245.8  199.33  5307.7  200.42  5527.2  200.87
  5538.1  200.34  5668.3  201.52  5818.5   201.1  6008.8  201.98  6018.8  202.43
  6048.8  206.05  6066.3  207.36  6192.3  208.73    6423  212.32  6496.4  213.41
#Mann= 5 ,-1 , 0
  4257.6     .11       0    4618     .03       0  6008.8     .15       0
  6192.3     .11       0    6423    .125       0
Bank Sta=4618,6008.8
XS Rating Curve= 0 ,0
Exp/Cntr=0.3,0.1

Type RM Length L Ch R = 1 ,227     ,0,0,0
BEGIN DESCRIPTION:
Conroe Lake 119 22.0
END DESCRIPTION:
XS GIS Cut Line= 3
      3770447.67     10142061.91      3770941.23      10140966.8
      3769091.02     10141190.62
#Sta/Elev= 30
  3798.8  213.58  4056.1  205.79  4117.8  201.76  4622.4     201  4638.9  199.59
  4775.9     201  4829.4  199.52  4881.2     201  5345.9  199.76  5386.2  201.34
  5426.5  199.55  5466.8  200.83  5565.6  198.89  5728.7  201.75  5789.1     201
  5859.6  202.89  5889.8   201.1  5994.4     201  6071.1  203.67  6141.6  201.03
    6192  202.85  6393.5  203.58    6409   202.1  6423.7   202.3    6464  208.01
  6574.9  208.84  6687.9  210.46  6739.3  211.22  6787.7   212.2  6863.7  213.37
#Mann= 7 ,-1 , 0
  3798.8     .11       0  4117.8     .03       0  5728.7     .15       0
  6574.9     .11       0  6687.9    .125       0  6739.3     .11       0
  6787.7    .125       0
#XS Ineff= 3 ,-1
  5728.7  5809.2  201.75  5809.2  5859.6  201.86  5859.6  6071.1  202.89
Permanent Ineff=
       F       F       F
Bank Sta=4117.8,5728.7
XS Rating Curve= 0 ,0
Exp/Cntr=0.3,0.1

Chan Stop Cuts=-1
Use User Specified Reach Order=0
Composite Channel Slope=5