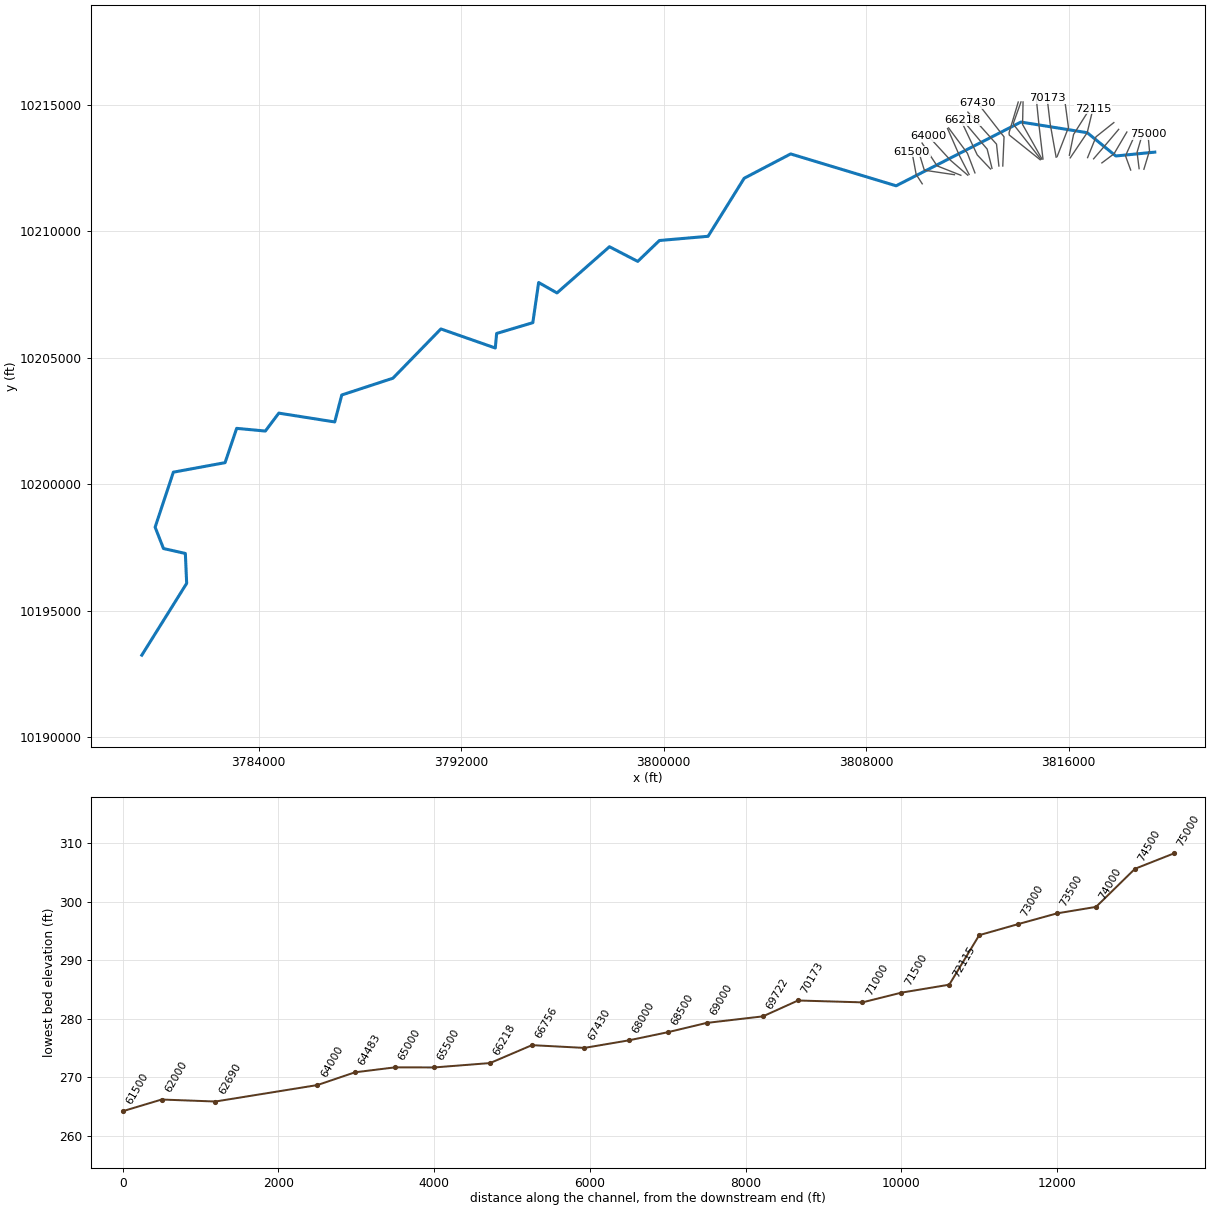
--- EAST SANDY CREEK.prj (project) ---

Proj Title=EAST SANDY CREEK Base Level Engineering
Current Plan=p01
Default Exp/Contr=0.3,0.1
English Units
Geom File=g01
Flow File=f01
Flow File=f02
Plan File=p01
Y Axis Title=Elevation
X Axis Title(PF)=Main Channel Distance
X Axis Title(XS)=Station
BEGIN DESCRIPTION:
EAST SANDY CREEK
END DESCRIPTION:
DSS File=dss
DSS Export Rating Curves= 0
DSS Export Rating Curve Sorted= 0
DSS Export Volume Flow Curves= 0
DXF OffsetX= 0
DXF OffsetY= 0
DXF ScaleX= 1
DXF ScaleY= 10

--- EAST SANDY CREEK.p01 (plan) ---

Plan Title=Multiple Run
Program Version=4.10
Short Identifier=Multiple Run
Geom File=g01
Flow File=f01
Subcritical Flow
K Sum by GR= 0
Std Step Tol= 0.01
Critical Tol= 0.01
Num of Std Step Trials= 20
Max Error Tol= 0.3
Flow Tol Ratio= 0.001
Split Flow NTrial= 30
Split Flow Tol= 0.02
Split Flow Ratio= 0.02
Log Output Level= 0
Friction Slope Method= 1
Unsteady Friction Slope Method= 2
Unsteady Bridges Friction Slope Method= 1
Parabolic Critical Depth
Global Vel Dist= 1 , 1 , 1
Global Log Level= 0
CheckData=True
Encroach Param=-1 ,0,0, 0
BEGIN DESCRIPTION:
Multiple Run
END DESCRIPTION:
Computation Interval=1HOUR
Output Interval=1HOUR
Run HTab= 0
Run UNet= 0
Run PostProcess= 0
Run WQNet= 0
UNET Theta= 1
UNET Theta Warmup= 1
UNET ZTol= 0.02
UNET ZSATol= 0.05
UNET MxIter= 20
UNET MaxInSteps= 0
UNET DtIC= 0
UNET DtMin= 0
UNET MaxCRTS= 20
UNET WFStab= 2
UNET SFStab= 1
UNET WFX= 1
UNET SFX= 1
UNET DSS MLevel= 4
UNET DZMax Abort= 100
UNET Convert EG Bridges= 0
UNET Use Existing IB Tables=-1
UNET Froude Reduction=False
UNET Froude Limit= 1
UNET Froude Power= 10
UNET Time Slicing=0,0, 5
UNET Junction Losses=0
Instantaneous Interval=1HOUR
DSS File=dss
Write IC File= 0
Write IC File at Sim End=0
Echo Input=False
Echo Parameters=False
Echo Output=False
Write Detailed= 0
WQ AD Non Conservative
WQ ULTIMATE=-1
WQ Max Comp Step=1HOUR
WQ Output Interval=15MIN
WQ Output Selected Increments= 0
WQ Output face flow=0
WQ Output face velocity=0
WQ Output face area=0
WQ Output face dispersion=0
WQ Output cell volume=0
WQ Output cell surface area=0
WQ Output cell continuity=0
WQ Output cumulative cell continuity=0
WQ Output face conc=0
WQ Output face dconc_dx=0
WQ Output face courant=0
WQ Output face peclet=0
WQ Output face adv mass=0
WQ Output face disp mass=0
WQ Output cell mass=0
WQ Output cell source sink temp=0
WQ Output cell source sink nsm=0
WQ Output MaxMinRange=-1
WQ Daily Max Min Mean=-1
WQ Daily Range=0
WQ Daily Time=0
WQ Create Restart=0
WQ Fixed Restart=0
WQ System Summary=0
WQ Use Fixed Temperature=0
Sorting and Armoring Iterations= 10
XS Update Threshold= 0.02
Hydraulics Update Threshold= 0.02
Energy Slope Method= 1
Volume Change Method= 0
XS Weighting Method= 0
Number of US Weighted Cross Sections= 1
Number of DS Weighted Cross Sections= 1
Upstream XS Weight=0.25
Main XS Weight=0.5
Downstream XS Weight=0.25
Number of DS XS's Weighted with US Boundary= 1
Upstream Boundary Weight= 1
Weight of XSs Associated with US Boundary= 0
Number of US XS's Weighted with DS Boundary= 1
Downstream Boundary Weight= 0.5
Weight of XSs Associated with DS Boundary= 0.5
Sediment Output Level= 4
Mass or Volume Output= 0
Output Increment Type= 1
Profile and TS Output Increment= 10
XS Output Flag= 0
XS Output Increment= 10
Disregard all LS=0
Disregard all Conn=0
Disregard all Breaches=0
Disregard all Pumps=0

--- EAST SANDY CREEK.f01 (steady flow) ---

Flow Title=Multiple
Program Version=4.10
Number of Profiles= 7
Profile Names=10-year,25-year,50-year,1pct_min,100-year,1pct_plu,500-year
River Rch & RM=EAST SANDY CREEK,Reach-1         ,75000
     804    1102    1502     673    2033    6140    3851
River Rch & RM=EAST SANDY CREEK,Reach-1         ,74000
     929    1283    1758     792    2393    7227    4579
River Rch & RM=EAST SANDY CREEK,Reach-1         ,71000
    1920    2727    3805    1739    5253   15864   10363
River Rch & RM=EAST SANDY CREEK,Reach-1         ,66756
    2010    2858    3992    1826    5515   16655   10893
River Rch & RM=EAST SANDY CREEK,Reach-1         ,62000
    2322    3324    4662    2141    6466   19527   12874
River Rch & RM=EAST SANDY CREEK,Reach-1         ,61500
    2479    3547    4970    2280    6886   20795   13679
River Rch & RM=EAST SANDY CREEK,Reach-1         ,58000
    2152    3023    4184    1894    5719   17271   11063
River Rch & RM=EAST SANDY CREEK,Reach-1         ,53968
    5929    8730   12481    5827   17596   53139   36182
River Rch & RM=EAST SANDY CREEK,Reach-1         ,48500
    5752    8429   12011    5588   16874   50959   34460
River Rch & RM=EAST SANDY CREEK,Reach-1         ,46236
    6412    9431   13470    6279   18963   57267   38886
River Rch & RM=EAST SANDY CREEK,Reach-1         ,45500
    6412    9431   13470    6279   18963   57267   38886
River Rch & RM=EAST SANDY CREEK,Reach-1         ,44623
    6412    9431   13470    6279   18963   57267   38886
River Rch & RM=EAST SANDY CREEK,Reach-1         ,43500
    6412    9431   13470    6279   18963   57267   38886
River Rch & RM=EAST SANDY CREEK,Reach-1         ,40500
    7301   10773   15422    7203   21754   65696   44784
River Rch & RM=EAST SANDY CREEK,Reach-1         ,37787
    7316   10780   15418    7194   21727   65614   44634
River Rch & RM=EAST SANDY CREEK,Reach-1         ,34873
    7345   10821   15471    7217   21795   65820   44748
River Rch & RM=EAST SANDY CREEK,Reach-1         ,31000
    7488   11043   15799    7374   22270   67254   45786
River Rch & RM=EAST SANDY CREEK,Reach-1         ,25768
    7043   10304   14663    6805   20552   62066   41774
River Rch & RM=EAST SANDY CREEK,Reach-1         ,21774
    7066   10333   14697    6819   20592   62187   41820
River Rch & RM=EAST SANDY CREEK,Reach-1         ,17000
    7743   11357   16189    7526   22729   68640   46344
River Rch & RM=EAST SANDY CREEK,Reach-1         ,10605
    7892   11586   16527    7689   23219   70120   47408
River Rch & RM=EAST SANDY CREEK,Reach-1         ,8685
    7654   11190   15915    7381   22291   67318   45234
River Rch & RM=EAST SANDY CREEK,Reach-1         ,3000
    8144   11972   17092    7958   24034   72582   49152
Boundary for River Rch & Prof#=EAST SANDY CREEK,Reach-1         , 1
Up Type= 0
Dn Type= 3
Dn Slope=0.005
Boundary for River Rch & Prof#=EAST SANDY CREEK,Reach-1         , 2
Up Type= 0
Dn Type= 3
Dn Slope=0.005
Boundary for River Rch & Prof#=EAST SANDY CREEK,Reach-1         , 3
Up Type= 0
Dn Type= 3
Dn Slope=0.005
Boundary for River Rch & Prof#=EAST SANDY CREEK,Reach-1         , 4
Up Type= 0
Dn Type= 3
Dn Slope=0.005
Boundary for River Rch & Prof#=EAST SANDY CREEK,Reach-1         , 5
Up Type= 0
Dn Type= 3
Dn Slope=0.005
Boundary for River Rch & Prof#=EAST SANDY CREEK,Reach-1         , 6
Up Type= 0
Dn Type= 3
Dn Slope=0.005
Boundary for River Rch & Prof#=EAST SANDY CREEK,Reach-1         , 7
Up Type= 0
Dn Type= 3
Dn Slope=0.005
DSS Import GetInterval= 0
DSS Import GetPeak= 0
DSS Import FillOption= 0

--- EAST SANDY CREEK.f02 (steady flow) ---

Flow Title=Orig_BLE_Flow
Program Version=4.10
Number of Profiles= 7
Profile Names=10-year,25-year,50-year,1pct_min,100-year,1pct_plu,500-year
River Rch & RM=EAST SANDY CREEK,Reach-1         ,75000
     804    1080    1306     518    1564    4722    2239
River Rch & RM=EAST SANDY CREEK,Reach-1         ,74000
     929    1258    1529     610    1841    5559    2662
River Rch & RM=EAST SANDY CREEK,Reach-1         ,71000
    1920    2674    3309    1338    4041   12204    6025
River Rch & RM=EAST SANDY CREEK,Reach-1         ,66756
    2010    2802    3471    1405    4242   12811    6333
River Rch & RM=EAST SANDY CREEK,Reach-1         ,62000
    2322    3259    4054    1647    4974   15023    7485
River Rch & RM=EAST SANDY CREEK,Reach-1         ,61500
    2479    3477    4322    1754    5297   15997    7953
River Rch & RM=EAST SANDY CREEK,Reach-1         ,58000
    2152    2964    3638    1457    4399   13286    6432
River Rch & RM=EAST SANDY CREEK,Reach-1         ,53968
    5929    8559   10853    4482   13535   40875   21036
River Rch & RM=EAST SANDY CREEK,Reach-1         ,48500
    5752    8264   10444    4298   12980   39200   20035
River Rch & RM=EAST SANDY CREEK,Reach-1         ,46000
    6412    9246   11713    4830   14587   44051   22608
River Rch & RM=EAST SANDY CREEK,Reach-1         ,45500
    6412    9246   11713    4830   14587   44051   22608
River Rch & RM=EAST SANDY CREEK,Reach-1         ,44623
    6412    9246   11713    4830   14587   44051   22608
River Rch & RM=EAST SANDY CREEK,Reach-1         ,43500
    6412    9246   11713    4830   14587   44051   22608
River Rch & RM=EAST SANDY CREEK,Reach-1         ,40500
    7301   10562   13410    5541   16734   50535   26037
River Rch & RM=EAST SANDY CREEK,Reach-1         ,37743
    7316   10569   13407    5534   16713   50471   25950
River Rch & RM=EAST SANDY CREEK,Reach-1         ,34873
    7345   10609   13453    5551   16765   50629   26016
River Rch & RM=EAST SANDY CREEK,Reach-1         ,31000
    7488   10826   13738    5673   17131   51736   26620
River Rch & RM=EAST SANDY CREEK,Reach-1         ,25768
    7043   10102   12750    5235   15809   47742   24287
River Rch & RM=EAST SANDY CREEK,Reach-1         ,21489
    7066   10130   12780    5245   15840   47836   24314
River Rch & RM=EAST SANDY CREEK,Reach-1         ,17000
    7743   11134   14077    5789   17484   52801   26944
River Rch & RM=EAST SANDY CREEK,Reach-1         ,10605
    7892   11359   14371    5914   17861   53939   27563
River Rch & RM=EAST SANDY CREEK,Reach-1         ,8685
    7654   10971   13839    5678   17147   51784   26299
River Rch & RM=EAST SANDY CREEK,Reach-1         ,3000
    8144   11737   14863    6122   18488   55832   28577
Boundary for River Rch & Prof#=EAST SANDY CREEK,Reach-1         , 1
Up Type= 0
Dn Type= 3
Dn Slope=0.005
Boundary for River Rch & Prof#=EAST SANDY CREEK,Reach-1         , 2
Up Type= 0
Dn Type= 3
Dn Slope=0.005
Boundary for River Rch & Prof#=EAST SANDY CREEK,Reach-1         , 3
Up Type= 0
Dn Type= 3
Dn Slope=0.005
Boundary for River Rch & Prof#=EAST SANDY CREEK,Reach-1         , 4
Up Type= 0
Dn Type= 3
Dn Slope=0.005
Boundary for River Rch & Prof#=EAST SANDY CREEK,Reach-1         , 5
Up Type= 0
Dn Type= 3
Dn Slope=0.005
Boundary for River Rch & Prof#=EAST SANDY CREEK,Reach-1         , 6
Up Type= 0
Dn Type= 3
Dn Slope=0.005
Boundary for River Rch & Prof#=EAST SANDY CREEK,Reach-1         , 7
Up Type= 0
Dn Type= 3
Dn Slope=0.005
DSS Import GetInterval= 0
DSS Import GetPeak= 0
DSS Import FillOption= 0

--- EAST SANDY CREEK.g01 (geometry) ---

Geom Title=Existing Conditions
Program Version=4.10

River Reach=EAST SANDY CREEK,Reach-1
Reach XY= 30
      3819406.83     10213136.76      3817867.53     10212984.62
      3816737.47     10213905.63      3814117.03     10214326.37
      3809188.25     10211805.79      3805020.69     10213065.53
      3803185.33     10212104.46      3801758.08     10209808.87
      3799835.63     10209642.17      3798979.37     10208816.81
      3797861.89     10209396.09      3795788.91     10207569.71
      3795064.14     10207981.71      3794834.17     10206393.66
      3793404.95     10205967.29      3793351.41     10205392.41
      3791201.34     10206145.94      3789307.26     10204197.62
      3787285.98     10203534.75      3787008.41     10202468.85
      3784798.87     10202817.04      3784266.62     10202108.45
      3783133.44     10202215.27      3782675.01     10200859.03
      3780632.27     10200482.78      3779912.03     10198307.81
      3780242.23     10197464.07      3781106.15     10197268.68
      3781158.24     10196087.17      3779386.06     10193247.19

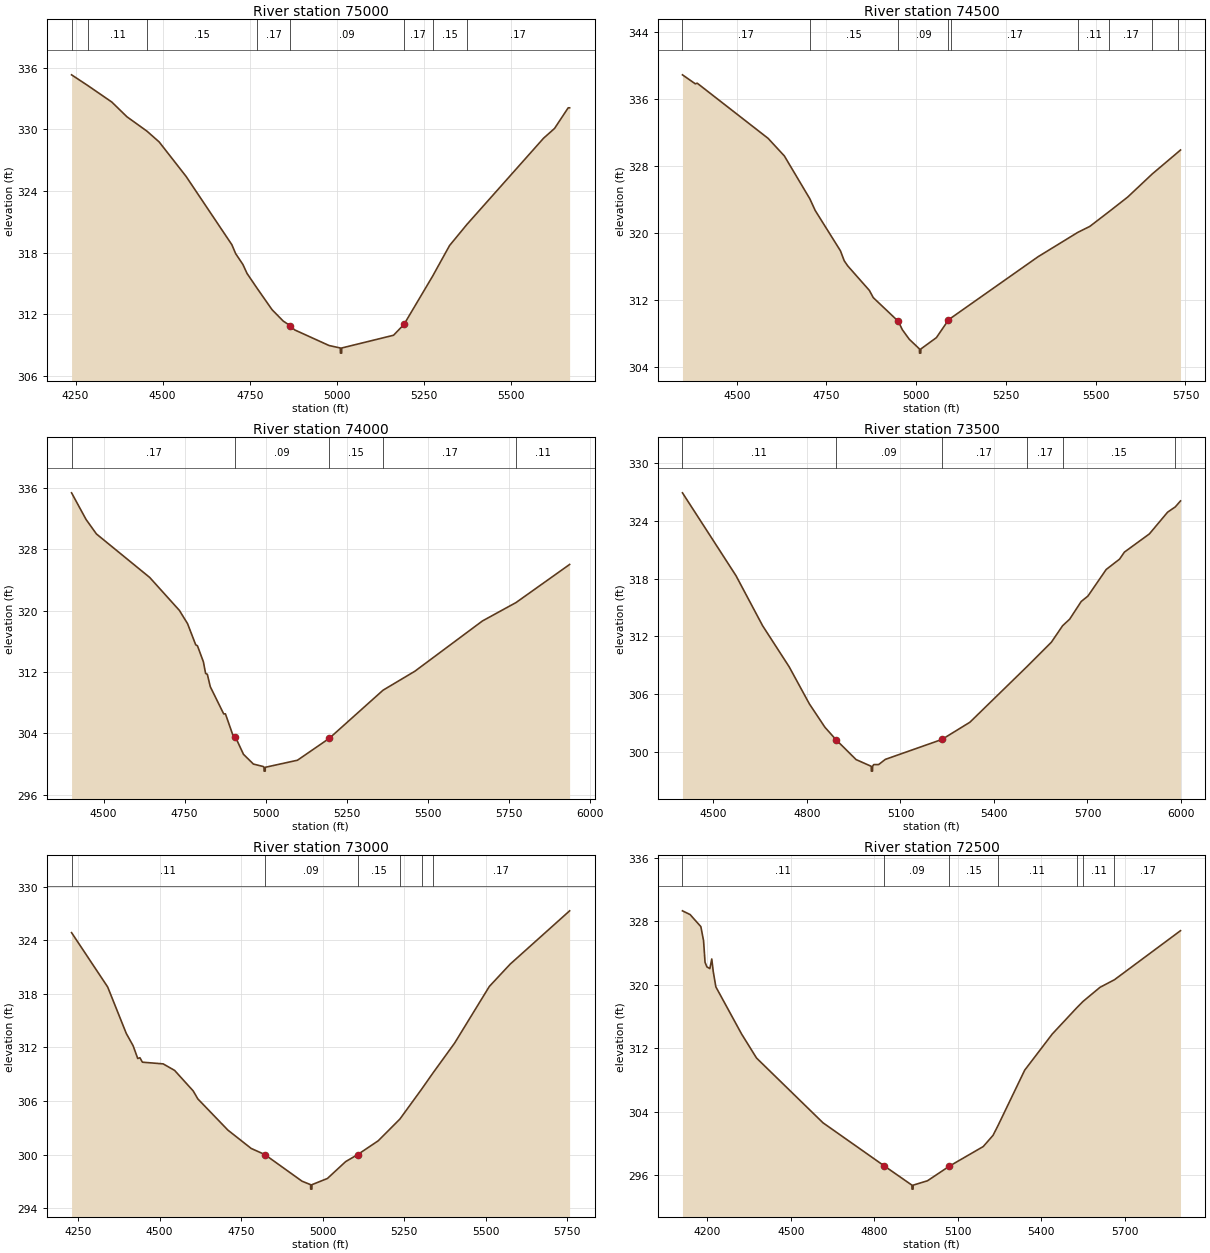
Type RM Length L Ch R = 1 ,75000   ,500,500,500
BEGIN DESCRIPTION:
EAST SANDY CREEK 144.0
END DESCRIPTION:
XS GIS Cut Line= 3
      3818977.82     10212460.58       3819198.8     10213189.11
      3819136.18     10213854.16
#Sta/Elev= 30
  4238.7  335.32    4286  334.26  4354.2  332.67  4397.5  331.24  4454.9  329.84
    4490  328.79  4567.2  325.44  4698.8  318.78  4709.5  317.92  4730.4  316.86
  4742.2  315.99  4770.8  314.56    4814  312.46  4846.1  311.35  4866.2   310.9
    4879  310.49  4977.7  308.97    5010  308.73  5010.3  308.23  5013.8  308.23
    5014  308.73  5162.7  309.97  5192.8  311.03  5274.8  315.72  5323.4   318.7
  5373.1  320.75  5593.2  329.15  5624.7   330.1  5663.9  332.11    5668  332.11
#Mann= 8 ,-1 , 0
  4238.7     .17       0    4286     .11       0  4454.9     .15       0
  4770.8     .17       0  4866.2     .09       0  5192.8     .17       0
  5274.8     .15       0  5373.1     .17       0
Bank Sta=4866.2,5192.8
XS Rating Curve= 0 ,0
Exp/Cntr=0.3,0.1

Type RM Length L Ch R = 1 ,74500   ,500,500,500
BEGIN DESCRIPTION:
EAST SANDY CREEK 143.0
END DESCRIPTION:
XS GIS Cut Line= 3
      3818787.79     10212484.31      3818707.57     10213130.55
      3818914.14     10213837.18
#Sta/Elev= 30
  4348.8  338.89  4384.8  337.81  4389.9  337.89  4587.4  331.29  4632.6  329.19
  4703.8  324.05  4718.5  322.67  4788.9  317.84  4799.4  316.65  4809.1  316.04
  4869.5   313.1  4880.3  312.24  4950.1   309.4  4961.2  308.41  4980.4  307.27
    5009   306.1  5009.2   305.6  5012.7   305.6    5013   306.1  5056.1  307.45
  5089.6  309.55  5098.2  309.84  5339.4  317.13  5449.9  320.04  5483.6  320.76
  5538.2  322.56  5589.1  324.27  5657.4  327.03  5728.4  329.61  5736.2   329.9
#Mann= 9 ,-1 , 0
  4348.8     .17       0  4703.8     .15       0  4950.1     .09       0
  5089.6     .15       0  5098.2     .17       0  5449.9     .11       0
  5538.2     .17       0  5657.4     .11       0  5728.4     .17       0
Bank Sta=4950.1,5089.6
XS Rating Curve= 0 ,0
Exp/Cntr=0.3,0.1

Type RM Length L Ch R = 1 ,74000   ,500,500,500
BEGIN DESCRIPTION:
EAST SANDY CREEK 142.0
END DESCRIPTION:
XS GIS Cut Line= 3
      3818455.23     10212428.91      3818249.94     10212991.52
      3818637.29     10213846.13
#Sta/Elev= 30
  4401.1  335.34    4446  331.86  4477.9  329.98  4642.2  324.32  4733.8  320.03
  4759.1   318.3  4784.3  315.54  4789.6  315.42  4807.9  313.34  4814.8  311.81
  4820.2   311.7  4829.2  310.09  4870.6  306.55    4876  306.55  4901.2  303.51
  4906.5  303.56  4931.7  301.28  4962.3  300.01  4992.8  299.69  4995.1  299.59
  4995.3  299.09  4998.8  299.09  4999.1  299.59  5098.3  300.51  5196.2  303.35
  5362.4  309.63  5460.6   312.1  5669.2  318.65    5773  321.05  5938.3  326.01
#Mann= 5 ,-1 , 0
  4401.1     .17       0  4906.5     .09       0  5196.2     .15       0
  5362.4     .17       0    5773     .11       0
Bank Sta=4906.5,5196.2
XS Rating Curve= 0 ,0
Exp/Cntr=0.3,0.1

Type RM Length L Ch R = 1 ,73500   ,500,500,500
BEGIN DESCRIPTION:
EAST SANDY CREEK 141.0
END DESCRIPTION:
XS GIS Cut Line= 3
      3817317.86     10212711.08      3817797.09     10213071.27
      3818303.84     10213931.74
#Sta/Elev= 30
  4400.5  326.91  4572.3   318.3  4657.7   313.1  4743.1  308.82  4807.7  304.98
  4857.6  302.55  4893.1  301.26  4957.6  299.19  5006.3  298.49  5006.6  297.99
  5010.3  297.99  5010.6  298.49  5014.3  298.67  5029.9  298.67  5051.4  299.21
  5232.9  301.28  5322.8  303.07  5505.6  308.84  5584.3  311.39  5620.3   313.1
  5642.9  313.78    5680  315.62  5701.5  316.18    5760  318.94    5803  320.02
  5818.6  320.75  5898.7  322.64  5957.2   324.9  5981.9  325.45  5998.6  326.07
#Mann= 6 ,-1 , 0
  4400.5     .11       0  4893.1     .09       0  5232.9     .17       0
  5505.6     .17       0  5620.3     .15       0  5981.9     .17       0
Bank Sta=4893.1,5232.9
XS Rating Curve= 0 ,0
Exp/Cntr=0.3,0.1

Type RM Length L Ch R = 1 ,73000   ,500,500,500
BEGIN DESCRIPTION:
EAST SANDY CREEK 140.0
END DESCRIPTION:
XS GIS Cut Line= 3
      3816990.38     10212872.32      3817491.34     10213456.94
      3817980.08      10214036.2
#Sta/Elev= 30
  4230.1  324.84  4340.9  318.76    4398  313.56  4418.9  312.19  4433.1  310.76
  4439.7  310.85  4447.4  310.35  4511.1  310.16  4546.2  309.43  4603.3  307.13
  4617.5  306.24  4709.7  302.75  4781.1   300.7  4822.8  300.02  4936.9  297.04
  4963.3  296.65  4963.6  296.15  4967.3  296.15  4967.6  296.65  5014.9  297.34
  5070.9  299.23  5107.2     300  5170.9  301.56  5237.3  303.99  5303.7  307.32
  5337.9   309.1    5405  312.48  5511.6  318.82  5575.3  321.31  5757.9  327.28
#Mann= 6 ,-1 , 0
  4230.1     .11       0  4822.8     .09       0  5107.2     .15       0
  5237.3     .17       0  5303.7     .15       0  5337.9     .17       0
Bank Sta=4822.8,5107.2
XS Rating Curve= 0 ,0
Exp/Cntr=0.3,0.1

Type RM Length L Ch R = 1 ,72500   ,385,385,385
BEGIN DESCRIPTION:
EAST SANDY CREEK 139.0
END DESCRIPTION:
XS GIS Cut Line= 3
      3816752.84     10212919.81      3817086.15     10213743.85
      3817790.14     10214305.52
#Sta/Elev= 30
  4111.1  329.29  4138.6  328.82  4177.2   327.3  4186.9  325.54  4192.3  322.81
  4198.8  322.24  4209.6  322.02  4216.4  323.23  4221.8  321.63  4231.1  319.72
  4323.7  313.78  4377.3  310.76    4616  302.61  4835.9  297.19  4935.6  294.76
  4935.9  294.26  4939.7  294.26    4940  294.76  4991.4  295.31  5070.1  297.15
  5191.8  299.62    5227  301.03  5244.9  302.26  5340.7  309.23    5440  313.79
  5527.1  317.06  5550.5  317.89  5611.3  319.66  5663.4  320.62  5900.6  326.79
#Mann= 7 ,-1 , 0
  4111.1     .11       0  4835.9     .09       0  5070.1     .15       0
  5244.9     .11       0  5527.1     .17       0  5550.5     .11       0
  5663.4     .17       0
Bank Sta=4835.9,5070.1
XS Rating Curve= 0 ,0
Exp/Cntr=0.3,0.1

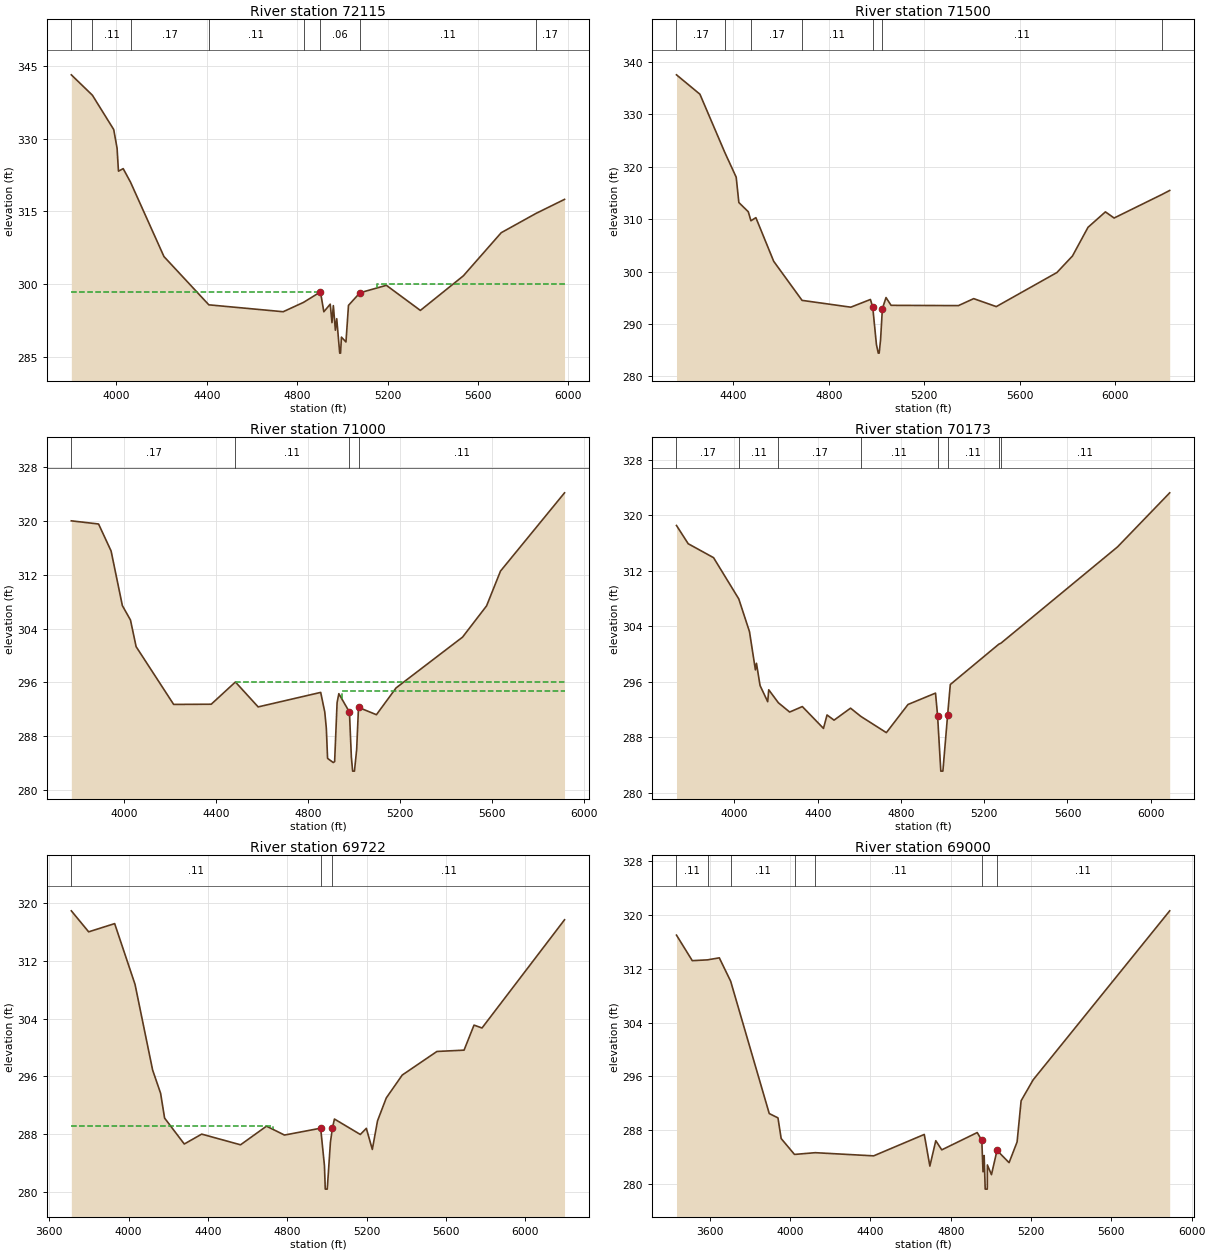
Type RM Length L Ch R = 1 ,72115   ,615,615,615
BEGIN DESCRIPTION:
EAST SANDY CREEK 138.0
END DESCRIPTION:
XS GIS Cut Line= 3
      3816067.84     10212911.05      3816737.47     10213905.63
      3816967.85     10214861.05
#Sta/Elev= 30
    3801  343.14  3894.2  338.94  3988.5  331.87  4003.4  328.02  4009.5  323.29
  4030.5  323.81  4062.9  321.02  4210.9  305.69  4409.3  295.75  4738.2  294.33
  4828.2  296.26  4903.1  298.41  4918.1  294.32  4946.3  295.89  4954.1  292.08
  4960.1  295.59  4969.1  290.52  4975.1   292.9  4988.2   285.8    4992   285.8
  4995.9   289.1  5015.9   288.1  5027.1  295.64  5077.6  298.23  5194.7  299.77
  5345.1   294.6  5535.1  301.72  5702.7  310.61    5856  314.57  5982.8  317.48
#Mann= 8 ,-1 , 0
    3801     .17       0  3894.2     .11       0  4062.9     .17       0
  4409.3     .11       0  4828.2     .15       0  4903.1     .06       0
  5077.6     .11       0    5856     .17       0
#XS Ineff= 2 , 0
       0  4897.1  298.42  5152.8       0  300.08
Permanent Ineff=
       T       T
Bank Sta=4903.1,5077.6
XS Rating Curve= 0 ,0
Exp/Cntr=0.3,0.1

Type RM Length L Ch R = 1 ,71500   ,500,500,500
BEGIN DESCRIPTION:
EAST SANDY CREEK 137.0
END DESCRIPTION:
XS GIS Cut Line= 3
      3816032.31     10213014.85      3816198.78     10213836.56
      3816855.77     10214875.57
#Sta/Elev= 30
  4161.6  337.56  4259.8  333.86  4364.4  322.72  4411.9  318.02    4423  313.19
  4462.6  311.42  4473.7   309.7  4494.4   310.3  4569.1  301.97    4688  294.51
  4892.4  293.21  4974.6  294.68  4984.2  293.26  4999.8  286.08  5007.5  284.44
  5011.3  284.44  5017.2     287  5024.7  292.91    5040  295.05  5061.2  293.56
  5343.5  293.51  5407.6  294.84  5502.3  293.32  5756.3  299.82  5821.7  302.98
  5886.9  308.46  5959.8   311.4  5996.3  310.23  6195.9   314.7  6229.3  315.49
#Mann= 7 ,-1 , 0
  4161.6     .17       0  4364.4     .11       0  4473.7     .17       0
    4688     .11       0  4984.2     .06       0  5024.7     .11       0
  6195.9     .17       0
Bank Sta=4984.2,5024.7
XS Rating Curve= 0 ,0
Exp/Cntr=0.3,0.1

Type RM Length L Ch R = 1 ,71000   ,827,827,827
BEGIN DESCRIPTION:
EAST SANDY CREEK 136.0
END DESCRIPTION:
XS GIS Cut Line= 3
       3815550.7     10212963.59      3815995.86     10214109.46
      3815874.08     10215017.12
#Sta/Elev= 30
  3770.7  320.04  3889.2  319.57  3943.7  315.55  3992.7  307.42    4028  305.27
  4052.5  301.31  4215.8  292.71  4379.2  292.74  4484.4  296.05  4583.3  292.34
  4855.3   294.5    4873  291.58  4879.8  289.16  4885.2  284.68  4909.7  284.06
  4915.9  284.19  4926.6  292.98  4934.2  294.31  4980.3  291.57  4988.7  284.85
  4994.2  282.78  5002.1  282.78  5011.7  285.99  5019.7  292.27  5097.7  291.18
  5183.2  295.17  5472.3  302.73  5576.7  307.38  5637.3  312.56  5915.8  324.21
#Mann= 4 ,-1 , 0
  3770.7     .17       0  4484.4     .11       0  4980.3     .06       0
  5019.7     .11       0
#XS Ineff= 2 ,-1
  4486.8  4143.5  296.06  4948.1  4486.8  294.69
Permanent Ineff=
       T       T
Bank Sta=4980.3,5019.7
XS Rating Curve= 0 ,0
Exp/Cntr=0.3,0.1

Type RM Length L Ch R = 1 ,70173   ,451,451,451
BEGIN DESCRIPTION:
EAST SANDY CREEK 134.0
END DESCRIPTION:
XS GIS Cut Line= 3
      3815509.72     10212935.68      3815274.49     10214259.65
       3815153.6     10215277.79
#Sta/Elev= 30
  3721.3  318.52  3777.6  315.89  3899.4  313.88  4020.5  307.94  4072.1  303.21
  4100.5   297.7  4105.6  298.65  4122.9  295.44  4159.6  293.11  4164.6  294.83
  4210.8  292.96  4265.1  291.62    4326  292.41  4427.6  289.26  4444.7   291.2
  4478.4  290.45  4557.7  292.18  4607.3  290.99  4729.8  288.65  4833.8  292.71
    4966  294.35    4976  291.07  4991.4   283.1  5001.4   283.1 5023.98  291.13
    5037  295.59    5270   301.4  5280.8  301.56  5840.5  315.43  6091.3  323.23
#Mann= 8 ,-1 , 0
  3721.3     .17       0  4020.5     .11       0  4210.8     .17       0
  4607.3     .11       0    4976     .07       0 5023.98     .11       0
    5270    .125       0  5280.8     .11       0
#XS Ineff= 2 , 0
       0    4966  294.35               0
Permanent Ineff=
       T       F
Bank Sta=4976,5023.98
XS Rating Curve= 0 ,0
Exp/Cntr=0.3,0.1

Type RM Length L Ch R = 1 ,69722   ,722,722,722
BEGIN DESCRIPTION:
EAST SANDY CREEK 133.0
END DESCRIPTION:
XS GIS Cut Line= 3
      3814990.25     10212864.23       3814838.6     10214144.08
      3814717.91     10215334.88
#Sta/Elev= 30
  3711.2  318.94  3798.6  316.03  3929.6  317.17  4032.2  308.76  4120.9  296.89
  4161.2  293.66  4181.3  290.23  4280.5  286.64  4368.3  288.01    4564  286.53
  4694.9  289.11  4785.5  287.88  4967.8  288.83  4986.9  283.66    4991  280.39
    5001  280.39  5017.1   286.9  5027.1  288.83  5037.2   290.1  5167.8  287.96
    5198  288.81  5228.2  285.89  5254.3  289.84  5298.5  293.02  5378.9  296.19
  5553.8  299.46  5690.5  299.64  5740.8  303.11    5781  302.71  6196.9   317.7
#Mann= 3 ,-1 , 0
  3711.2     .11       0  4967.8     .06       0  5027.1     .11       0
#XS Ineff= 2 , 0
       0  4725.1  289.16               0
Permanent Ineff=
       T       T
Bank Sta=4967.8,5027.1
XS Rating Curve= 0 ,0
Exp/Cntr=0.3,0.1

Type RM Length L Ch R = 1 ,69000   ,500,500,500
BEGIN DESCRIPTION:
EAST SANDY CREEK 132.0
END DESCRIPTION:
XS GIS Cut Line= 3
      3814949.51     10212864.25      3814183.68     10214230.67
      3814203.24     10215121.06
#Sta/Elev= 30
  3433.6  316.98  3512.3  313.19  3588.2  313.31  3646.9  313.61  3703.4  310.14
  3895.7  290.49  3939.1  289.85  3955.1  286.78  4021.5  284.42  4124.9  284.68
  4415.8  284.21    4668  287.39  4695.8  282.69  4725.3  286.46  4755.1   285.1
  4931.7  287.67  4954.6  286.51  4960.6  281.84  4966.3  284.26  4971.5  279.27
  4981.6  279.27  4982.1  279.77  4982.3  282.86  5002.7  281.42  5030.4  285.02
  5090.4   283.2  5130.4  286.28  5150.4  292.39  5210.4   295.5  5890.6  320.59
#Mann= 7 ,-1 , 0
  3433.6     .11       0  3588.2     .17       0  3703.4     .11       0
  4021.5     .15       0  4124.9     .11       0  4954.6     .06       0
  5030.4     .11       0
Bank Sta=4954.6,5030.4
XS Rating Curve= 0 ,0
Exp/Cntr=0.3,0.1

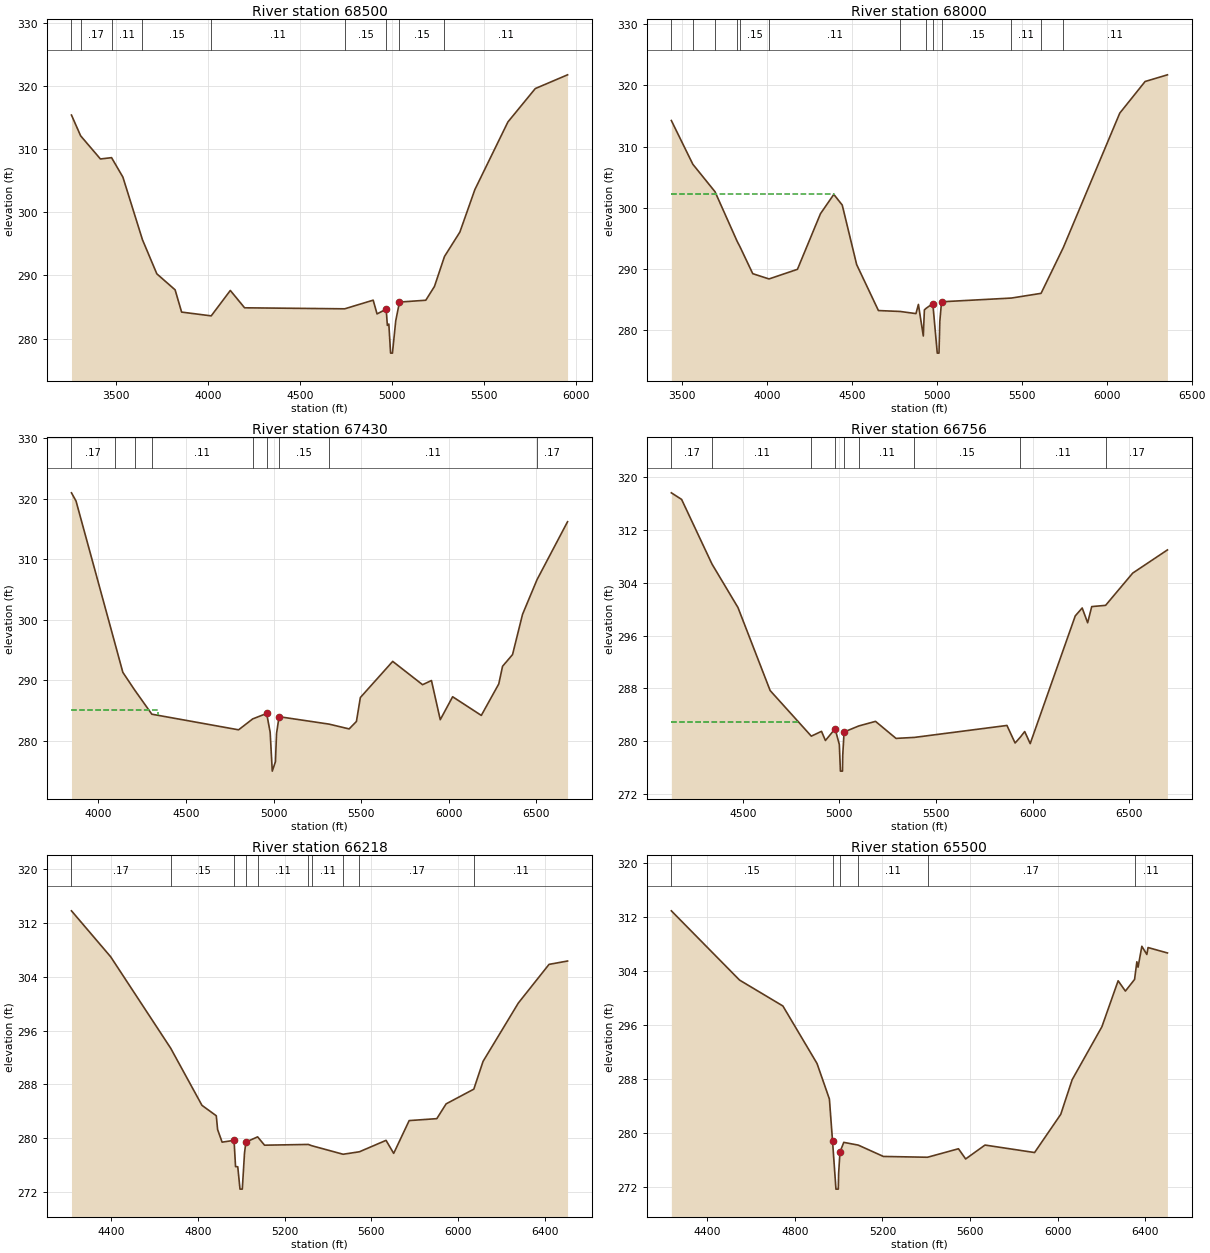
Type RM Length L Ch R = 1 ,68500   ,500,500,500
BEGIN DESCRIPTION:
EAST SANDY CREEK 131.0
END DESCRIPTION:
XS GIS Cut Line= 4
      3814908.78     10212850.66      3813832.68     10214223.08
      3813821.54     10214281.32      3814121.35     10215122.39
#Sta/Elev= 30
    3256  315.45  3305.7  312.16  3413.4  308.48  3473.9  308.69  3535.4  305.61
    3642  295.66  3719.9  290.26  3819.3  287.72  3854.6  284.19  4015.5  283.59
  4119.4  287.62  4196.9  284.87  4740.9  284.71  4895.8  286.08  4916.8   283.9
  4966.5  284.65  4972.8  282.08  4980.9  282.29  4990.4  277.68  5000.5  277.68
  5018.3  282.79  5038.7  285.78  5181.7  286.07  5228.9  288.26  5283.3  293.01
  5366.9  296.88  5448.4  303.62    5628  314.35  5776.8  319.65  5952.2  321.83
#Mann= 9 ,-1 , 0
    3256     .11       0  3305.7     .17       0  3473.9     .11       0
    3642     .15       0  4015.5     .11       0  4740.9     .15       0
  4966.5     .09       0  5038.7     .15       0  5283.3     .11       0
#XS Ineff= 2 , 0
       0  4119.4  287.62               0
Permanent Ineff=
       T       F
Bank Sta=4966.5,5038.7
XS Rating Curve= 0 ,0
Exp/Cntr=0.3,0.1

Type RM Length L Ch R = 1 ,68000   ,570,570,570
BEGIN DESCRIPTION:
EAST SANDY CREEK 130.0
END DESCRIPTION:
XS GIS Cut Line= 4
      3814877.14     10212837.04      3813657.96     10213813.01
      3813649.67     10213902.85      3814012.48     10215116.98
#Sta/Elev= 30
  3438.3  314.26  3564.8  307.12  3695.2  302.64  3825.7  294.53  3842.8  293.62
  3917.3  289.26    4013   288.4  4180.3  289.97  4315.8  299.05  4394.3   302.2
  4443.9  300.46  4528.7  290.75  4656.8  283.24  4785.3  283.09  4877.7  282.74
  4892.1  284.24  4920.9  279.09  4927.3  283.35  4938.3  283.62  4976.9  284.38
    5003  276.29  5013.2  276.29  5018.1  281.47  5028.2  284.67  5439.5  285.28
  5613.9  286.05  5744.8  293.53    6077  315.47    6226  320.63  6357.4  321.72
#Mann= 13 ,-1 , 0
  3438.3     .17       0  3564.8     .11       0  3695.2     .15       0
  3825.7     .11       0  3842.8     .15       0    4013     .11       0
  4785.3     .15       0  4938.3     .11       0  4976.9     .06       0
  5028.2     .15       0  5439.5     .11       0  5613.9     .15       0
  5744.8     .11       0
#XS Ineff= 2 , 0
         4395.16  302.25
Permanent Ineff=
       F       F
Bank Sta=4976.9,5028.2
XS Rating Curve= 0 ,0
Exp/Cntr=0.3,0.1

Type RM Length L Ch R = 1 ,67430   ,674,674,674
BEGIN DESCRIPTION:
EAST SANDY CREEK 129.0
END DESCRIPTION:
XS GIS Cut Line= 3
      3813401.81     10212588.12       3813451.7     10213740.34
      3812419.75     10215063.63
#Sta/Elev= 30
  3846.7  320.95  3872.7   319.6  4094.2  296.17  4139.9  291.31  4206.7  288.42
  4305.3   284.4  4800.5  281.82  4880.9  283.62  4960.7  284.52  4980.7  281.43
  4992.8     275  5010.8  276.55  5017.2  281.23  5031.6  283.99  5317.1  282.76
  5431.5  281.97  5473.1   283.2  5495.5  287.15  5680.2  293.12  5850.6  289.27
  5901.3  289.96  5951.6  283.49  6022.2  287.28  6185.9   284.2  6285.4  289.39
  6307.1  292.31  6364.1  294.24  6421.2  300.89    6504  306.62  6678.1  316.18
#Mann= 9 ,-1 , 0
  3846.7     .17       0  4094.2     .11       0  4206.7     .17       0
  4305.3     .11       0  4880.9     .15       0  4960.7     .09       0
  5031.6     .15       0  5317.1     .11       0    6504     .17       0
#XS Ineff= 2 , 0
       0  4340.1  285.09  5680.2       0  293.12
Permanent Ineff=
       F       T
Bank Sta=4960.7,5031.6
XS Rating Curve= 0 ,0
Exp/Cntr=0.3,0.1

Type RM Length L Ch R = 1 ,66756   ,538,538,538
BEGIN DESCRIPTION:
EAST SANDY CREEK 128.0
END DESCRIPTION:
XS GIS Cut Line= 3
      3813247.95     10212588.14      3813154.39      10213452.8
       3812022.2     10214718.92
#Sta/Elev= 30
  4130.3  317.64  4183.5  316.64  4340.7  306.85  4475.2  300.26  4641.8  287.68
  4854.9  280.77  4907.7   281.5  4927.9  280.11  4978.1  281.88    5000  279.49
  5005.6  275.47  5016.2  275.47  5017.6  277.86  5024.5   281.4  5101.1  282.32
  5187.3  283.01  5293.4  280.43  5388.9  280.58  5867.7  282.39  5909.9  279.73
  5936.7  280.61  5959.6  281.47  5988.1  279.64  6221.3  298.99  6257.2  300.19
  6285.5  297.95  6306.6   300.4  6378.4  300.59  6518.9  305.48  6698.5  308.99
#Mann= 9 ,-1 , 0
  4130.3     .17       0  4340.7     .11       0  4854.9     .15       0
  4978.1     .09       0  5024.5     .15       0  5101.1     .11       0
  5388.9     .15       0  5936.7     .11       0  6378.4     .17       0
#XS Ineff= 2 , 0
       0    4787  282.98  5187.3       0  283.01
Permanent Ineff=
       F       T
Bank Sta=4978.1,5024.5
XS Rating Curve= 0 ,0
Exp/Cntr=0.3,0.1

Type RM Length L Ch R = 1 ,66218   ,718,718,718
BEGIN DESCRIPTION:
EAST SANDY CREEK 126.0
END DESCRIPTION:
XS GIS Cut Line= 3
      3812976.42     10212497.63      3812784.38      10213256.4
      3811813.93     10214406.73
#Sta/Elev= 30
  4217.3  313.83  4398.1  306.99  4674.9  293.38  4819.1  284.88  4885.1  283.33
  4891.3  281.27    4912   279.4  4967.1  279.67  4973.9  275.76  4984.2  275.74
  4994.5  272.41  5005.1  272.41  5015.3  277.79  5021.8  279.41  5075.8  280.19
  5107.6  278.95  5309.7  279.06  5325.5  278.87    5470   277.6  5545.1  277.97
    5668  279.67  5703.2  277.73  5774.6  282.61  5902.1   282.9    5945   285.1
  6072.7  287.29  6115.3  291.42  6277.9   300.1  6419.6  305.86    6505  306.36
#Mann= 10 ,-1 , 0
  4217.3     .17       0  4674.9     .15       0  4967.1     .09       0
  5021.8     .15       0  5075.8     .11       0  5309.7     .15       0
  5325.5     .11       0    5470     .15       0  5545.1     .17       0
  6072.7     .11       0
Bank Sta=4967.1,5021.8
XS Rating Curve= 0 ,0
Exp/Cntr=0.3,0.1

Type RM Length L Ch R = 1 ,65500   ,500,500,500
BEGIN DESCRIPTION:
EAST SANDY CREEK 125.0
END DESCRIPTION:
XS GIS Cut Line= 3
      3812917.55     10212470.53      3812393.34     10213026.45
      3811754.55     10214384.74
#Sta/Elev= 30
  4235.9  312.96  4547.4  302.68  4745.2  298.84    4901  290.31  4957.6  285.03
  4971.8  278.84  4987.5  271.66  4998.2  271.66  4999.7  273.97  5005.9  277.17
  5023.2   278.6  5089.5  278.19    5204  276.51  5405.5  276.39  5546.9  277.65
  5579.7  276.14  5668.1   278.2  5894.4  277.09  6013.9  282.76    6066   287.9
  6201.8  295.76  6275.9  302.58  6309.1  301.05    6351  302.78  6361.4   305.4
  6366.9   304.6  6384.2   307.7    6407  306.48  6412.5  307.51    6501  306.71
#Mann= 6 ,-1 , 0
  4235.9     .15       0  4971.8     .09       0  5005.9     .15       0
  5089.5     .11       0  5405.5     .17       0    6351     .11       0
Bank Sta=4971.8,5005.9
XS Rating Curve= 0 ,0
Exp/Cntr=0.3,0.1

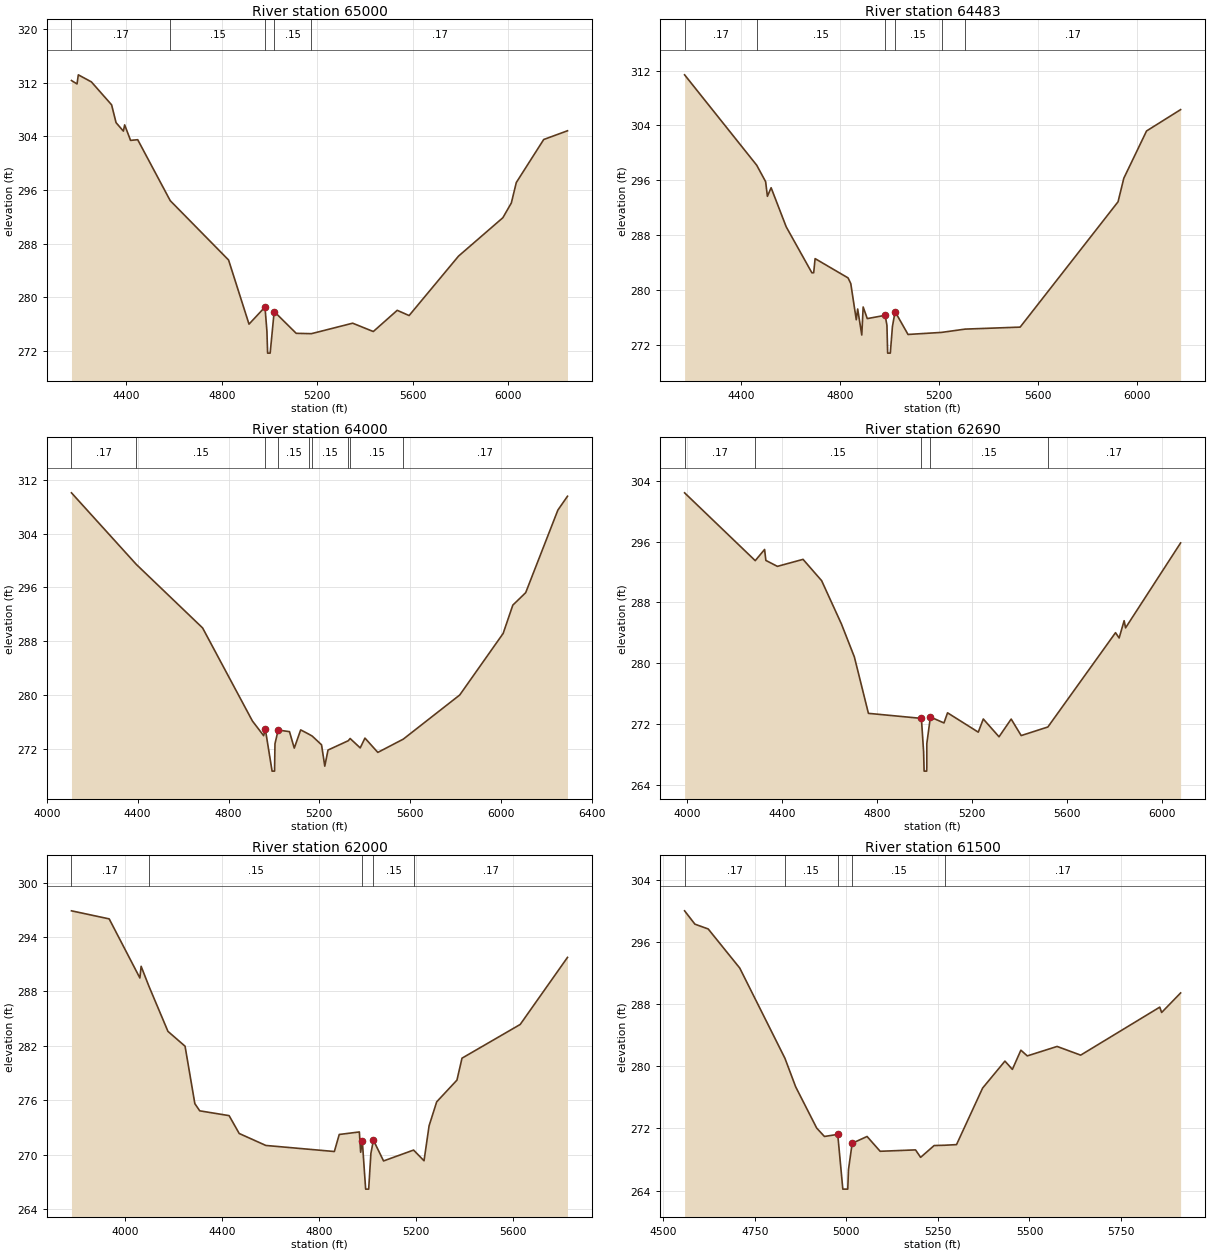
Type RM Length L Ch R = 1 ,65000   ,517,517,517
BEGIN DESCRIPTION:
EAST SANDY CREEK 124.0
END DESCRIPTION:
XS GIS Cut Line= 3
      3812302.11     10212316.64      3812005.01     10213091.43
      3811262.05     10214094.07
#Sta/Elev= 30
  4170.2  312.31  4193.5   311.8  4198.9  313.16  4253.6  312.11  4338.3  308.69
    4357  306.03  4387.7  304.77    4393   305.7  4417.7  303.39  4447.7  303.49
    4584   294.4  4828.3  285.56  4913.9     276  4980.8  278.55  4988.9  274.94
  4991.8  271.68  5002.5  271.68  5019.3  277.88  5111.6  274.63  5175.3  274.58
    5348  276.14  5434.6   274.9  5534.7  278.06  5584.5  277.28  5791.5  286.14
  5977.2  291.86  6012.7  294.06  6033.5  297.11  6148.3  303.52  6247.9  304.82
#Mann= 5 ,-1 , 0
  4170.2     .17       0    4584     .15       0  4980.8     .09       0
  5019.3     .15       0  5175.3     .17       0
Bank Sta=4980.8,5019.3
XS Rating Curve= 0 ,0
Exp/Cntr=0.3,0.1

Type RM Length L Ch R = 1 ,64483   ,483,483,483
BEGIN DESCRIPTION:
EAST SANDY CREEK 123.0
END DESCRIPTION:
XS GIS Cut Line= 3
      3812071.33     10212253.25      3811693.89     10212990.56
      3811220.94     10214067.05
#Sta/Elev= 30
  4171.7  311.38  4463.1  298.21  4499.1  295.82  4506.3  293.68  4521.3  294.93
  4582.3  289.23    4686  282.54  4693.3  282.54    4699   284.6  4832.2  281.79
  4843.2  280.96  4865.4  275.69    4871  277.26  4887.6  273.47  4893.2  277.55
  4909.8  275.86    4982  276.34  4989.3  274.87  4992.1  270.83  5002.9  270.83
  5011.5  274.72  5022.2  276.88  5074.4  273.55    5210  273.85  5305.5  274.33
  5527.5  274.62    5923  292.88  5946.3  296.31  6038.2   303.2  6175.8  306.31
#Mann= 6 ,-1 , 0
  4171.7     .17       0  4463.1     .15       0    4982     .09       0
  5022.2     .15       0    5210     .11       0  5305.5     .17       0
Bank Sta=4982,5022.2
XS Rating Curve= 0 ,0
Exp/Cntr=0.3,0.1

Type RM Length L Ch R = 1 ,64000   ,1310,1310,1310
BEGIN DESCRIPTION:
EAST SANDY CREEK 122.0
END DESCRIPTION:
XS GIS Cut Line= 3
        3812017.     10212226.13       3811342.5     10212809.23
      3810467.83     10213761.09
#Sta/Elev= 30
  4108.4   310.1  4394.2  299.43  4685.8  289.98  4905.2  276.12  4954.6  273.93
  4962.2  274.88  4991.9  268.65  5002.7  268.65  5004.6  272.72  5018.6  274.77
  5068.5  274.53  5089.5  272.08  5117.8  274.79    5153  274.17  5168.9  273.86
  5209.7  272.57  5223.9  269.39  5238.1  271.79  5327.5  273.18  5335.5  273.51
  5379.9  272.11  5400.8  273.57  5457.5  271.44  5569.4  273.41  5818.2  279.99
  6009.4  289.16  6051.9  293.37  6108.6  295.23  6250.4  307.53  6292.7  309.59
#Mann= 9 ,-1 , 0
  4108.4     .17       0  4394.2     .15       0  4962.2     .09       0
  5018.6     .15       0    5153     .11       0  5168.9     .15       0
  5327.5     .11       0  5335.5     .15       0  5569.4     .17       0
Bank Sta=4962.2,5018.6
XS Rating Curve= 0 ,0
Exp/Cntr=0.3,0.1

Type RM Length L Ch R = 1 ,62690   ,690,690,690
BEGIN DESCRIPTION:
EAST SANDY CREEK 120.0
END DESCRIPTION:
XS GIS Cut Line= 3
      3811745.51     10212221.58      3810805.56     10212594.18
      3810212.65     10213495.79
#Sta/Elev= 30
  3988.9   302.4  4286.6  293.49    4326  294.96  4331.4  293.52    4380  292.74
  4488.1  293.66  4566.4  290.86  4650.1  285.15  4704.2  280.85  4763.6  273.43
  4986.8  272.77  4996.1  268.38  4998.2  265.84    5009  265.84  5009.5  266.34
  5009.6  269.45  5024.7  272.95  5081.9  272.17    5097   273.5  5226.5  270.96
  5247.6  272.69  5313.9  270.35  5365.1  272.68  5407.3  270.51  5519.8  271.64
  5804.9  284.03    5820  283.33  5841.1   285.6  5847.1  284.66  6079.1  295.82
#Mann= 5 ,-1 , 0
  3988.9     .17       0  4286.6     .15       0  4986.8     .09       0
  5024.7     .15       0  5519.8     .17       0
Bank Sta=4986.8,5024.7
XS Rating Curve= 0 ,0
Exp/Cntr=0.3,0.1

Type RM Length L Ch R = 1 ,62000   ,500,500,500
BEGIN DESCRIPTION:
EAST SANDY CREEK 119.0
END DESCRIPTION:
XS GIS Cut Line= 4
      3811492.04     10212244.22      3810320.24     10212419.34
      3810294.92     10212446.84      3810053.53     10213237.94
#Sta/Elev= 30
  3777.8  296.89  3933.7     296  4060.5  289.48  4065.6  290.77  4097.2  288.61
  4176.4  283.59  4247.1  281.95  4287.6  275.61  4307.8  274.82  4429.1  274.29
  4470.8  272.32  4580.8     271  4863.9  270.33  4884.1  272.21  4967.2  272.49
  4972.6  270.25  4979.4  271.49  4993.2  266.18  5005.7  266.18  5014.9  270.12
  5025.3  271.58  5067.2  269.29  5191.2  270.49  5234.4  269.31  5255.3  273.17
  5286.7  275.81  5370.4  278.21  5391.3  280.63  5631.7  284.35  5827.1  291.75
#Mann= 5 ,-1 , 0
  3777.8     .17       0  4097.2     .15       0  4979.4     .09       0
  5025.3     .15       0  5191.2     .17       0
Bank Sta=4979.4,5025.3
XS Rating Curve= 0 ,0
Exp/Cntr=0.3,0.1

Type RM Length L Ch R = 1 ,61500   ,500,500,500
BEGIN DESCRIPTION:
EAST SANDY CREEK 118.0
END DESCRIPTION:
XS GIS Cut Line= 3
      3810219.55     10211884.56      3809979.78     10212255.41
      3809812.52     10213152.55
#Sta/Elev= 30
  4558.4  300.07  4586.6  298.35  4622.9  297.73    4709  292.69  4832.3  281.06
  4861.7  277.37  4919.1  272.05  4940.2  270.97  4976.5  271.24  4990.4  264.18
  5003.9  264.18  5005.8  266.68  5015.9  270.09  5056.6  270.97  5092.3  269.06
  5188.9  269.24  5202.8  268.28  5239.7   269.8  5268.8  269.84  5300.8  269.92
    5372  277.21    5433  280.69  5453.3  279.62  5476.5   282.1    5494  281.36
  5575.4  282.58  5639.8  281.46  5855.7  287.65  5860.8  286.96  5912.6  289.48
#Mann= 5 ,-1 , 0
  4558.4     .17       0  4832.3     .15       0  4976.5     .09       0
  5015.9     .15       0  5268.8     .17       0
Bank Sta=4976.5,5015.9
XS Rating Curve= 0 ,0
Exp/Cntr=0.3,0.1