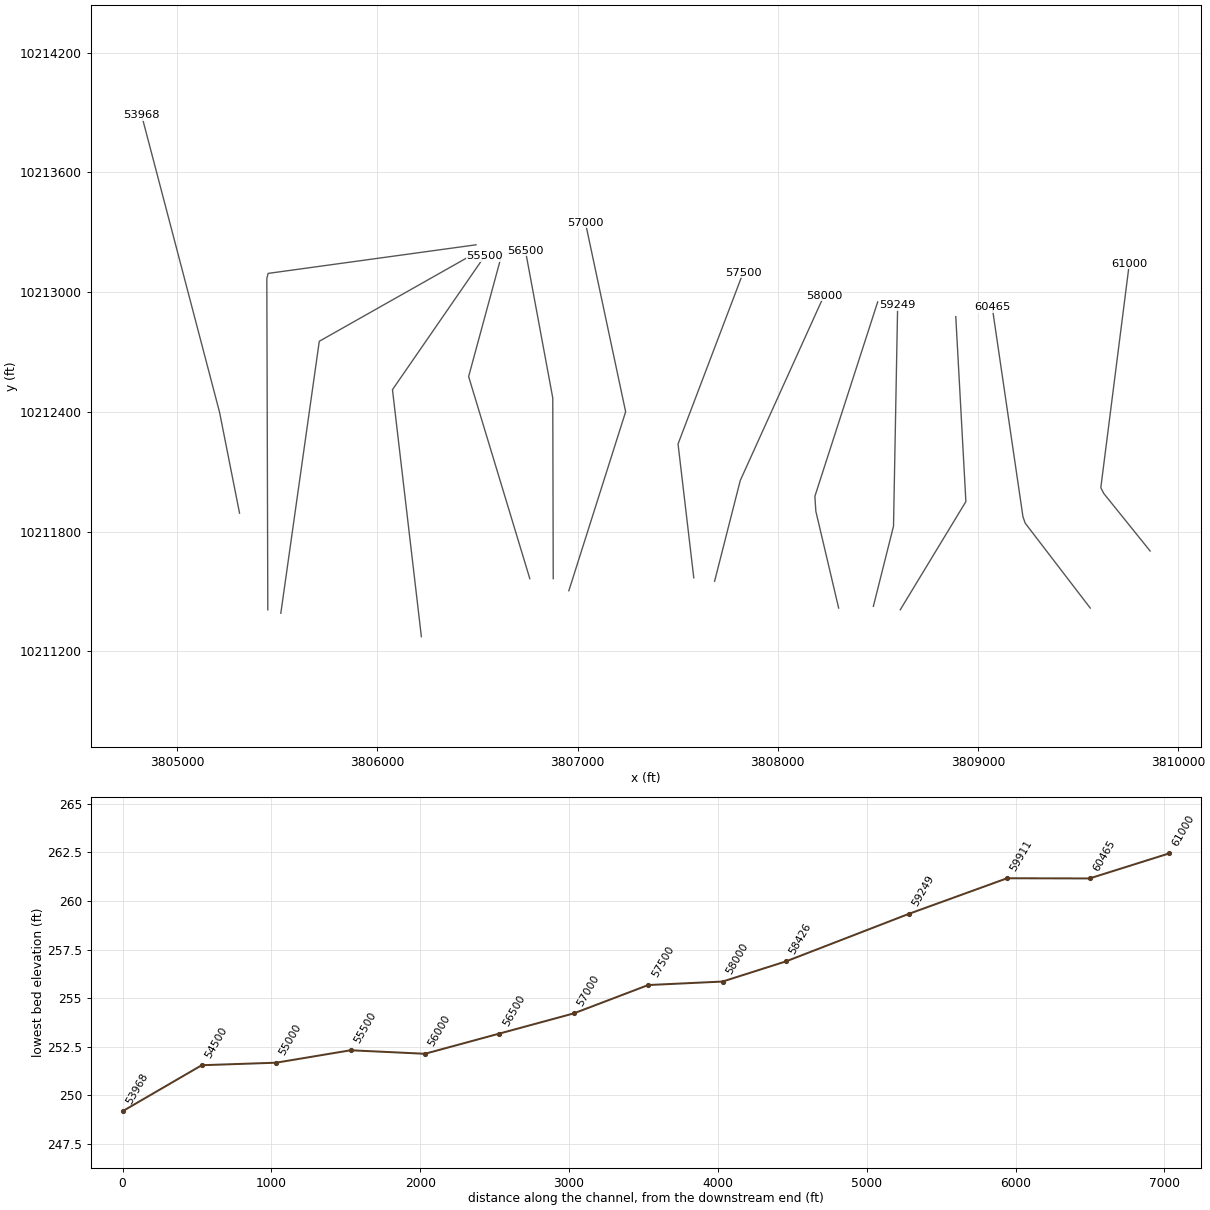
HEC-RAS study EAST SANDY CREEK.prj: EAST SANDY CREEK Base Level Engineering

--- EAST SANDY CREEK.g01 (geometry) --- (continued)

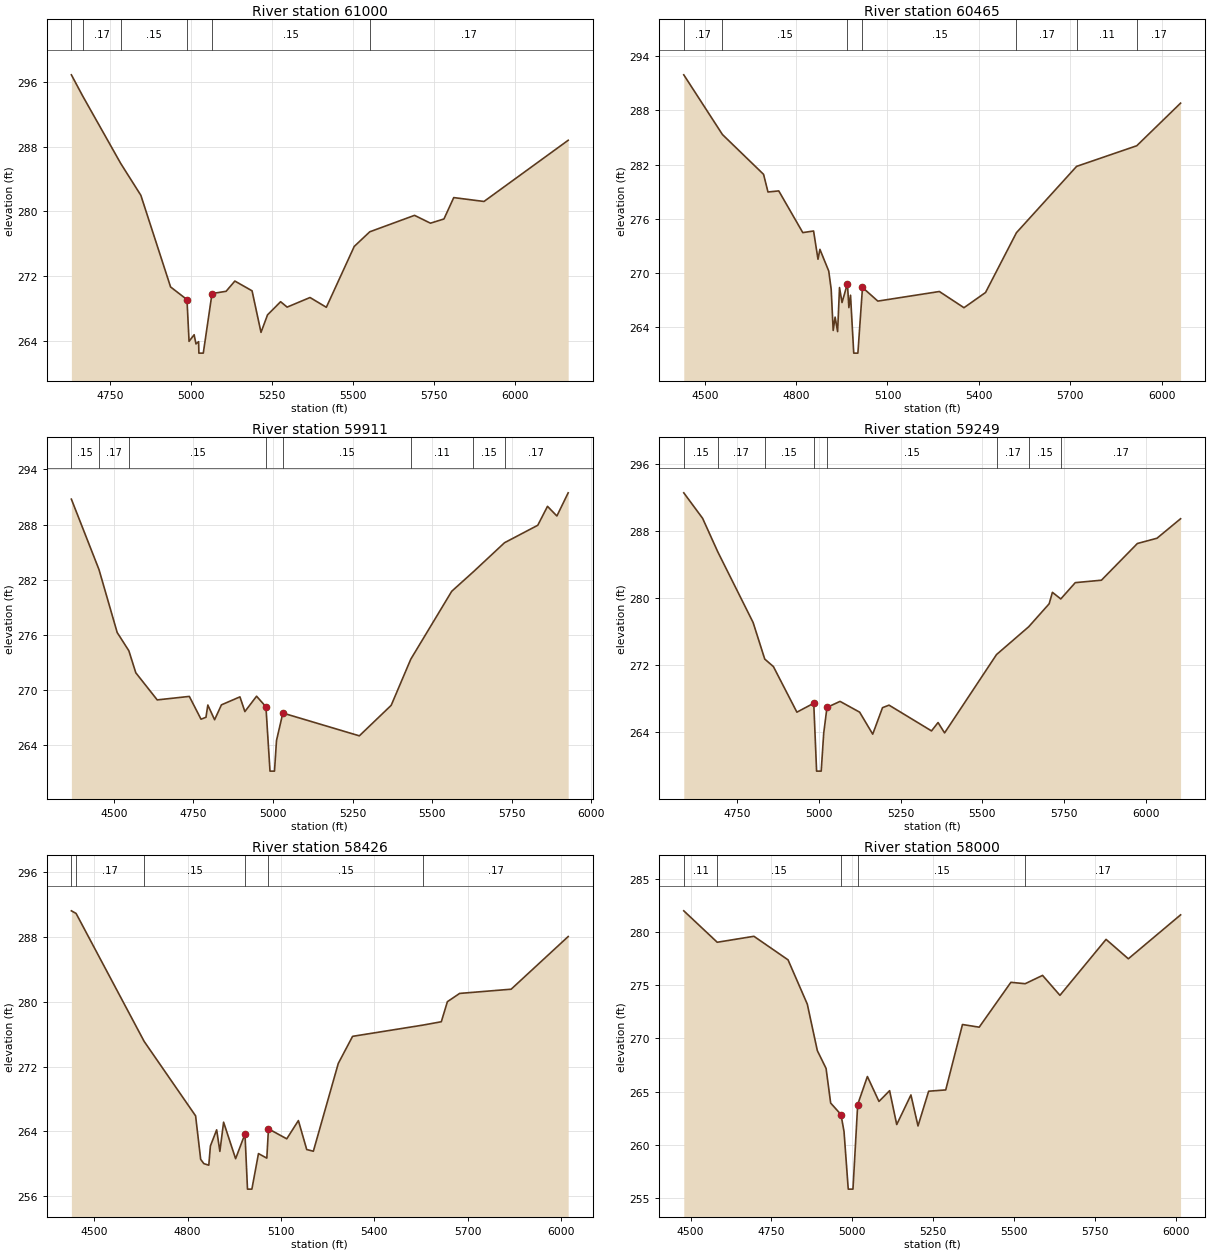
Type RM Length L Ch R = 1 ,61000   ,535,535,535
BEGIN DESCRIPTION:
EAST SANDY CREEK 117.0
END DESCRIPTION:
XS GIS Cut Line= 4
      3809859.88     10211702.46      3809628.35     10211990.68
      3809613.61     10212019.64      3809755.84     10213141.37
#Sta/Elev= 30
  4630.3  296.93  4664.9  294.33  4782.7  285.94  4844.6  282.01  4936.4  270.65
    4987  269.08  4993.4  263.91  5009.1  264.73  5014.7  263.59  5022.9  263.87
  5023.7  262.45  5037.3  262.45  5064.2  269.83  5107.7  270.11  5134.7  271.38
  5187.8  270.17  5215.4  265.02  5235.5  267.19  5275.9  268.82    5296  268.15
  5366.6  269.34    5417  268.13  5503.1  275.67  5550.9  277.48  5689.1  279.52
  5738.2  278.55  5779.9  279.07  5810.1  281.72  5903.4  281.24  6163.2  288.82
#Mann= 6 ,-1 , 0
  4630.3     .15       0  4664.9     .17       0  4782.7     .15       0
    4987     .09       0  5064.2     .15       0  5550.9     .17       0
Bank Sta=4987,5064.2
XS Rating Curve= 0 ,0
Exp/Cntr=0.3,0.1

Type RM Length L Ch R = 1 ,60465   ,554,554,554
BEGIN DESCRIPTION:
EAST SANDY CREEK 116.0
END DESCRIPTION:
XS GIS Cut Line= 4
      3809560.81     10211416.46      3809236.01     10211841.69
      3809224.74     10211873.57      3809071.07     10212924.69
#Sta/Elev= 30
  4431.1  291.92  4558.1  285.32  4693.1  280.92  4707.6  278.97    4743  279.09
  4821.9  274.48  4857.3  274.66  4871.8  271.54  4878.1  272.63  4907.1  270.23
  4915.1  268.22  4921.7  263.67    4928  265.14  4936.2  263.54  4942.5  268.41
  4950.7  266.75  4968.5  268.85  4973.2  266.19  4978.6  267.56  4989.2  261.16
  5002.8  261.16  5017.9  268.42  5068.2  266.91  5270.3  267.97  5351.2  266.18
  5421.9  267.86  5523.4  274.47  5720.9   281.8  5918.4  284.08  6062.3  288.79
#Mann= 7 ,-1 , 0
  4431.1     .17       0  4558.1     .15       0  4968.5     .09       0
  5017.9     .15       0  5523.4     .17       0  5720.9     .11       0
  5918.4     .17       0
#XS Ineff= 2 , 0
       0  4878.1  272.63               0
Permanent Ineff=
       F       F
Bank Sta=4968.5,5017.9
XS Rating Curve= 0 ,0
Exp/Cntr=0.3,0.1

Type RM Length L Ch R = 1 ,59911   ,662,662,662
BEGIN DESCRIPTION:
EAST SANDY CREEK 115.0
END DESCRIPTION:
XS GIS Cut Line= 3
      3808611.69     10211407.82      3808939.56     10211949.99
      3808889.07     10212876.52
#Sta/Elev= 30
  4366.4  290.76  4453.2   283.1  4510.4  276.25    4547  274.27  4568.9  271.87
  4636.2  268.92  4737.1   269.3  4773.9  266.82  4789.4  267.03  4795.3  268.36
  4816.6  266.76    4838  268.38  4896.2  269.25  4911.7  267.65  4948.5  269.32
  4977.9  268.17  4990.7  261.17  5004.8  261.17  5011.1   264.5  5031.1  267.49
  5271.5  265.01  5371.6  268.33  5433.2  273.35  5561.9  280.74  5629.6  282.85
  5727.8  286.02  5832.3  287.92  5862.9  289.98  5892.4  288.93  5927.9  291.45
#Mann= 8 ,-1 , 0
  4366.4     .15       0  4453.2     .17       0    4547     .15       0
  4977.9     .09       0  5031.1     .15       0  5433.2     .11       0
  5629.6     .15       0  5727.8     .17       0
Bank Sta=4977.9,5031.1
XS Rating Curve= 0 ,0
Exp/Cntr=0.3,0.1

Type RM Length L Ch R = 1 ,59249   ,823,823,823
BEGIN DESCRIPTION:
EAST SANDY CREEK 113.0
END DESCRIPTION:
XS GIS Cut Line= 3
      3808477.32     10211425.12      3808578.02     10211826.69
      3808598.67      10212933.3
#Sta/Elev= 30
    4586  292.61  4643.7  289.56  4689.8  285.58  4798.3   277.1  4833.9  272.73
  4860.4  271.83  4932.3  266.38  4983.9  267.45  4992.6  259.33  5006.7  259.33
  5014.4  263.87  5024.4  266.95  5064.4  267.67  5124.4  266.38  5164.4  263.75
  5194.4  266.92  5214.4  267.22  5344.4  264.14  5364.4  265.14  5384.4   263.9
  5543.4  273.27  5641.8  276.59  5704.5  279.34  5714.5  280.71  5740.1  279.92
  5784.5  281.87  5864.5  282.16  5974.6  286.55  6034.6  287.18  6106.8  289.51
#Mann= 8 ,-1 , 0
    4586     .15       0  4689.8     .17       0  4833.9     .15       0
  4983.9     .09       0  5024.4     .15       0  5543.4     .17       0
  5641.8     .15       0  5740.1     .17       0
Bank Sta=4983.9,5024.4
XS Rating Curve= 0 ,0
Exp/Cntr=0.3,0.1

Type RM Length L Ch R = 1 ,58426   ,426,426,426
BEGIN DESCRIPTION:
EAST SANDY CREEK 112.0
END DESCRIPTION:
XS GIS Cut Line= 4
      3808303.97     10211416.44        3808190.     10211901.58
      3808185.22     10211976.48        3808499.      10212950.7
#Sta/Elev= 30
  4426.6  291.19  4441.7  290.87  4660.5   275.1  4825.9  265.92  4842.2  260.56
  4852.5  260.03  4868.3  259.84  4873.5  262.21  4893.6   264.2  4903.9  261.54
  4915.9  265.14  4954.5  260.64  4984.6  263.69  4992.7  256.89  5006.8  256.89
    5028  261.27  5054.8  260.71  5060.1  264.32  5118.9  263.09  5156.3  265.34
  5183.1  261.77  5204.4  261.56  5284.5  272.38  5330.5  275.72  5555.7   277.1
  5615.7  277.52  5635.2  279.99  5674.6  281.01  5840.2  281.53  6023.5  288.02
#Mann= 6 ,-1 , 0
  4426.6     .15       0  4441.7     .17       0  4660.5     .15       0
  4984.6     .09       0  5060.1     .15       0  5555.7     .17       0
Bank Sta=4984.6,5060.1
XS Rating Curve= 0 ,0
Exp/Cntr=0.3,0.1

Type RM Length L Ch R = 1 ,58000   ,500,500,500
BEGIN DESCRIPTION:
EAST SANDY CREEK 111.0
END DESCRIPTION:
XS GIS Cut Line= 3
      3807684.21     10211550.82      3807812.41     10212055.59
      3808230.29     10212981.02
#Sta/Elev= 30
  4479.2  281.97  4582.7  279.02  4696.1  279.58  4801.6  277.37  4861.2  273.21
  4892.2  268.85  4919.2  267.18  4933.4  263.93  4965.3  262.85  4974.7  261.26
  4987.8  255.85  5002.4  255.85    5017  263.79    5047  266.42  5082.8  264.08
  5115.7  265.09  5137.7  261.91  5181.6  264.69  5203.5  261.78  5236.4  265.04
  5289.2  265.16    5341   271.3  5392.7  271.05  5490.7  275.26  5534.9  275.13
  5588.6  275.91  5642.4  274.04    5785  279.29  5853.9  277.47  6015.4  281.59
#Mann= 5 ,-1 , 0
  4479.2     .11       0  4582.7     .15       0  4965.3     .09       0
    5017     .15       0  5534.9     .17       0
Bank Sta=4965.3,5017
XS Rating Curve= 0 ,0
Exp/Cntr=0.3,0.1

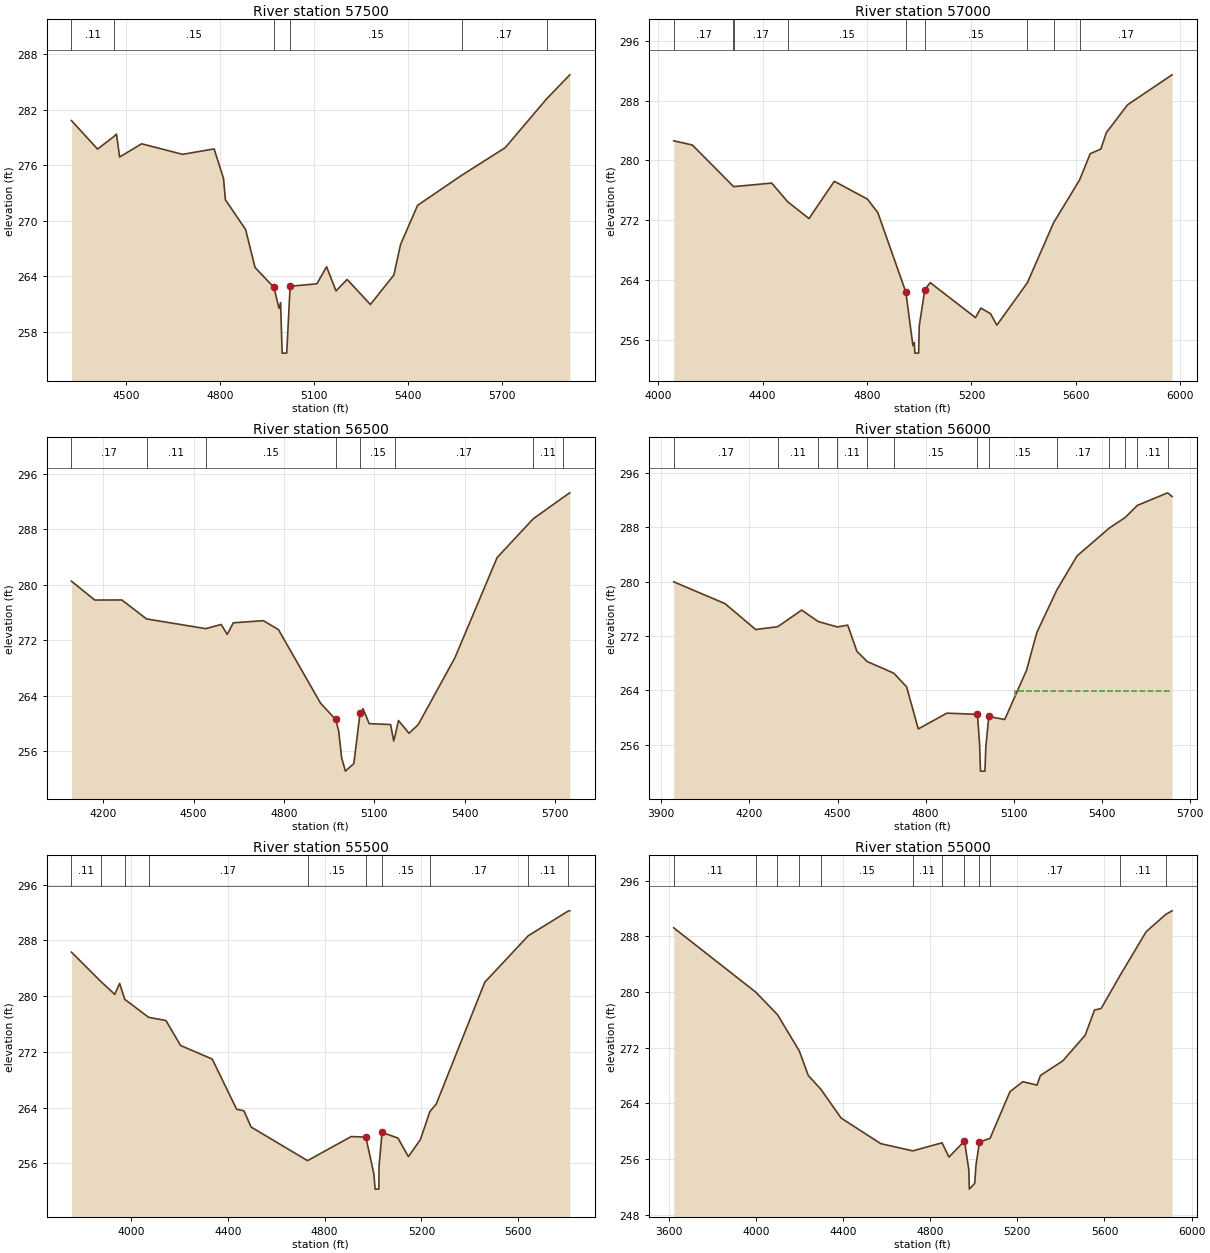
Type RM Length L Ch R = 1 ,57500   ,500,500,500
BEGIN DESCRIPTION:
EAST SANDY CREEK 110.0
END DESCRIPTION:
XS GIS Cut Line= 3
      3807580.19     10211568.17      3807501.61     10212238.68
      3807826.85     10213097.02
#Sta/Elev= 30
  4324.9  280.82  4408.4  277.74  4460.7   279.1  4468.8  279.36  4478.9  276.88
  4549.3  278.31  4680.2  277.17  4780.9  277.76  4811.1  274.55  4816.8  272.27
  4881.6  269.04  4911.8  264.93  4972.2  262.78  4988.3  260.52  4993.4  261.13
  4998.4  255.67    5013  255.67  5023.9   262.9  5109.5  263.17  5140.4  265.01
  5170.6   262.4  5206.1  263.64  5280.5  260.93  5355.5  264.12  5376.8   267.4
  5431.2  271.65  5571.7  274.89  5711.4  277.89  5843.8  283.17  5917.9  285.77
#Mann= 6 ,-1 , 0
  4324.9     .11       0  4460.7     .15       0  4972.2     .09       0
  5023.9     .15       0  5571.7     .17       0  5843.8     .11       0
Bank Sta=4972.2,5023.9
XS Rating Curve= 0 ,0
Exp/Cntr=0.3,0.1

Type RM Length L Ch R = 1 ,57000   ,500,500,500
BEGIN DESCRIPTION:
EAST SANDY CREEK 109.0
END DESCRIPTION:
XS GIS Cut Line= 3
       3806956.1     10211503.11      3807239.83     10212400.11
      3807038.81     10213347.72
#Sta/Elev= 30
  4059.2  282.63  4130.5  282.07  4287.3  276.55  4290.1   276.5  4434.6  276.97
    4496  274.47  4577.6  272.22  4674.5  277.21  4801.7  274.82  4841.3  273.02
  4948.8  262.37  4975.8  255.21  4981.1  255.63  4983.2  254.21  4997.8  254.21
    5000  257.83  5021.4  262.69  5041.9  263.65  5215.7  258.96  5236.1  260.24
  5273.2  259.49  5297.4  257.95  5414.5  263.64    5515  271.67  5614.6   277.4
  5655.1   280.9  5696.1  281.53  5716.6   283.7  5798.3  287.45  5968.7  291.46
#Mann= 9 ,-1 , 0
  4059.2     .17       0  4287.3     .11       0  4290.1     .17       0
    4496     .15       0  4948.8     .09       0  5021.4     .15       0
  5414.5     .17       0    5515     .15       0  5614.6     .17       0
Bank Sta=4948.8,5021.4
XS Rating Curve= 0 ,0
Exp/Cntr=0.3,0.1

Type RM Length L Ch R = 1 ,56500   ,500,500,500
BEGIN DESCRIPTION:
EAST SANDY CREEK 108.0
END DESCRIPTION:
XS GIS Cut Line= 3
       3806878.1      10211563.8      3806875.79      10212469.2
      3806739.45      10213206.2
#Sta/Elev= 30
  4094.6  280.53  4171.9  277.81  4261.9  277.82    4344  275.09  4540.5  273.69
  4591.9  274.29  4611.9  272.86  4631.9  274.53  4731.9  274.84  4781.9  273.55
  4921.9  262.95  4971.9  260.61  4981.9  258.97  4991.9  255.08  5004.3  253.17
  5032.4  254.27  5052.8  261.47  5062.9  262.16  5083.3  260.01  5154.4  259.88
  5164.6  257.52  5169.4  258.29  5180.5  260.46  5215.5  258.62    5246  259.86
    5368   269.5  5508.1  283.92  5627.5  289.49  5726.7  292.57  5749.5  293.25
#Mann= 8 ,-1 , 0
  4094.6     .17       0    4344     .11       0  4540.5     .15       0
  4971.9     .09       0  5052.8     .15       0  5169.4     .17       0
  5627.5     .11       0  5726.7     .17       0
Bank Sta=4971.9,5052.8
XS Rating Curve= 0 ,0
Exp/Cntr=0.3,0.1

Type RM Length L Ch R = 1 ,56000   ,500,500,500
BEGIN DESCRIPTION:
EAST SANDY CREEK 107.0
END DESCRIPTION:
XS GIS Cut Line= 3
      3806761.09     10211563.77      3806455.47     10212576.56
      3806622.39     10213193.37
#Sta/Elev= 30
  3942.1  279.98  4116.9  276.77  4221.3  272.96  4296.5  273.38    4378  275.82
  4433.9  274.14  4499.5  273.34  4534.7  273.61    4566  269.75    4601  268.25
  4691.5  266.54  4735.2  264.53  4774.9  258.34  4872.4  260.66  4976.5  260.48
  4983.8  256.02  4986.8  252.13  5001.8  252.13  5004.9  255.64    5015  260.17
  5069.3  259.72  5143.8     267  5178.5  272.51  5246.4  278.75  5315.5  283.79
  5425.8   287.9    5479  289.43  5521.2  291.23  5624.1  293.07    5639  292.53
#Mann= 13 ,-1 , 0
  3942.1     .17       0  4296.5     .11       0  4433.9     .17       0
  4499.5     .11       0    4601     .17       0  4691.5     .15       0
  4976.5     .09       0    5015     .15       0  5246.4     .17       0
  5425.8     .11       0    5479     .17       0  5521.2     .11       0
  5624.1     .17       0
#XS Ineff= 2 , 0
       0                    5104       0  263.88
Permanent Ineff=
       F       F
Bank Sta=4976.5,5015
XS Rating Curve= 0 ,0
Exp/Cntr=0.3,0.1

Type RM Length L Ch R = 1 ,55500   ,500,500,500
BEGIN DESCRIPTION:
EAST SANDY CREEK 106.0
END DESCRIPTION:
XS GIS Cut Line= 3
      3806219.34     10211273.39      3806074.97      10212510.8
      3806535.73     10213180.39
#Sta/Elev= 30
  3754.2  286.31    3876  282.09  3933.1  280.25  3953.2  281.83  3974.5  279.54
    4073  276.96  4144.5   276.5  4204.9  272.92  4335.8  270.97  4436.5  263.77
  4466.7  263.55  4496.2  261.22  4729.4   256.4  4909.7  259.85  4970.1  259.78
  5003.2  254.55  5008.7  252.31  5023.7  252.31  5024.2  252.81  5024.6  255.52
  5037.2  260.44  5102.8  259.64    5146  256.97  5195.5  259.41  5235.1  263.46
  5261.1  264.52  5461.6     282  5641.1  288.66  5807.1  292.23  5812.8  292.24
#Mann= 10 ,-1 , 0
  3754.2     .11       0    3876     .17       0  3974.5     .15       0
    4073     .17       0  4729.4     .15       0  4970.1     .09       0
  5037.2     .15       0  5235.1     .17       0  5641.1     .11       0
  5807.1     .17       0
Bank Sta=4970.1,5037.2
XS Rating Curve= 0 ,0
Exp/Cntr=0.3,0.1

Type RM Length L Ch R = 1 ,55000   ,500,500,500
BEGIN DESCRIPTION:
EAST SANDY CREEK 105.0
END DESCRIPTION:
XS GIS Cut Line= 3
      3805517.24     10211390.48      3805709.39     10212753.31
      3806501.05     10213202.05
#Sta/Elev= 30
  3623.7  289.25  4000.1     280  4099.8  276.76  4199.6  271.57  4241.1  268.02
  4299.4  266.01  4391.8  261.89  4573.6  258.21  4720.6  257.17  4854.8  258.33
  4886.7  256.28  4957.8  258.59  4977.5  254.51  4980.1  251.67  5004.8   252.5
  5010.5  255.11  5026.4  258.45  5075.1  258.97  5166.4  265.68  5225.5  267.12
  5290.4  266.63  5306.3  268.02  5408.7  270.11  5511.2  273.79  5554.4  277.43
  5584.5  277.64  5671.9  282.41  5791.1  288.68  5881.4  291.18    5910  291.69
#Mann= 12 ,-1 , 0
  3623.7     .11       0  4000.1     .15       0  4099.8     .11       0
  4199.6     .17       0  4299.4     .15       0  4720.6     .11       0
  4854.8     .15       0  4957.8     .09       0  5026.4     .15       0
  5075.1     .17       0  5671.9     .11       0  5881.4     .17       0
Bank Sta=4957.8,5026.4
XS Rating Curve= 0 ,0
Exp/Cntr=0.3,0.1

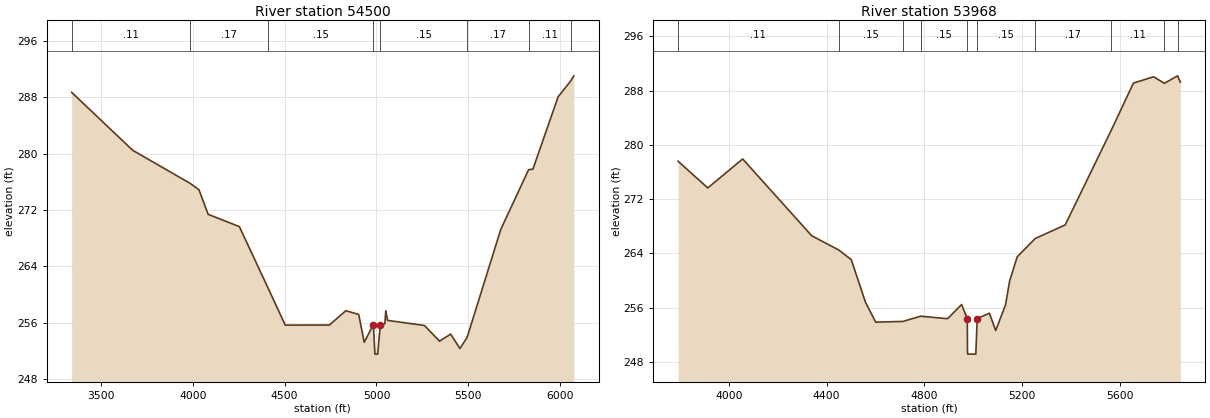
Type RM Length L Ch R = 1 ,54500   ,532,532,532
BEGIN DESCRIPTION:
EAST SANDY CREEK 104.0
END DESCRIPTION:
XS GIS Cut Line= 4
      3805452.23     10211407.82       3805447.3     10213067.81
      3805453.89     10213093.42       3806492.4     10213236.72
#Sta/Elev= 30
    3340  288.72  3673.3  280.48  3985.6  275.79  4033.3  274.89  4083.3   271.4
  4253.3  269.65  4411.2  260.84  4503.3  255.66  4743.3  255.67  4833.3  257.71
  4903.3  257.17  4933.3  253.22  4983.3  255.74  4991.6  251.54  5006.6  251.54
  5020.6  255.63  5045.7  255.86  5050.7  257.71  5060.7  256.33  5261.4  255.61
  5343.4  253.38    5404  254.39  5454.4  252.33  5494.1  253.95  5676.5  269.22
  5828.4  277.74  5851.9  277.81  5989.4   288.1  6056.7   290.3  6074.8  291.07
#Mann= 8 ,-1 , 0
    3340     .11       0  3985.6     .17       0  4411.2     .15       0
  4983.3     .09       0  5020.6     .15       0  5494.1     .17       0
  5828.4     .11       0  6056.7     .17       0
Bank Sta=4983.3,5020.6
XS Rating Curve= 0 ,0
Exp/Cntr=0.3,0.1

Type RM Length L Ch R = 1 ,53968   ,468,468,468
BEGIN DESCRIPTION:
EAST SANDY CREEK 103.0
END DESCRIPTION:
XS GIS Cut Line= 3
      3805311.02     10211891.99      3805211.16     10212397.72
      3804821.71     10213886.63
#Sta/Elev= 30
  3792.6  277.59    3914  273.66  4056.7  277.93  4339.2  266.61  4449.1  264.53
  4500.9   263.1  4559.6  256.77    4601  253.88  4712.6  253.99  4784.8  254.76
  4894.9  254.39  4952.4  256.48  4975.7   254.4  4976.4  249.67  4977.1  249.17
  5010.5  249.17  5016.2  254.41  5066.1   255.2  5091.9  252.65  5132.3  256.45
  5148.8  259.93  5179.8  263.51  5253.6  266.21  5376.2  268.21  5564.6  282.16
  5655.3  289.11    5738  290.04  5782.1  289.08    5836  290.18  5847.1  289.26
#Mann= 10 ,-1 , 0
  3792.6     .11       0  4449.1     .15       0  4712.6     .11       0
  4784.8     .15       0  4975.7     .09       0  5016.2     .15       0
  5253.6     .17       0  5564.6     .11       0  5782.1     .17       0
    5836     .11       0
Bank Sta=4975.7,5016.2
XS Rating Curve= 0 ,0
Exp/Cntr=0.3,0.1