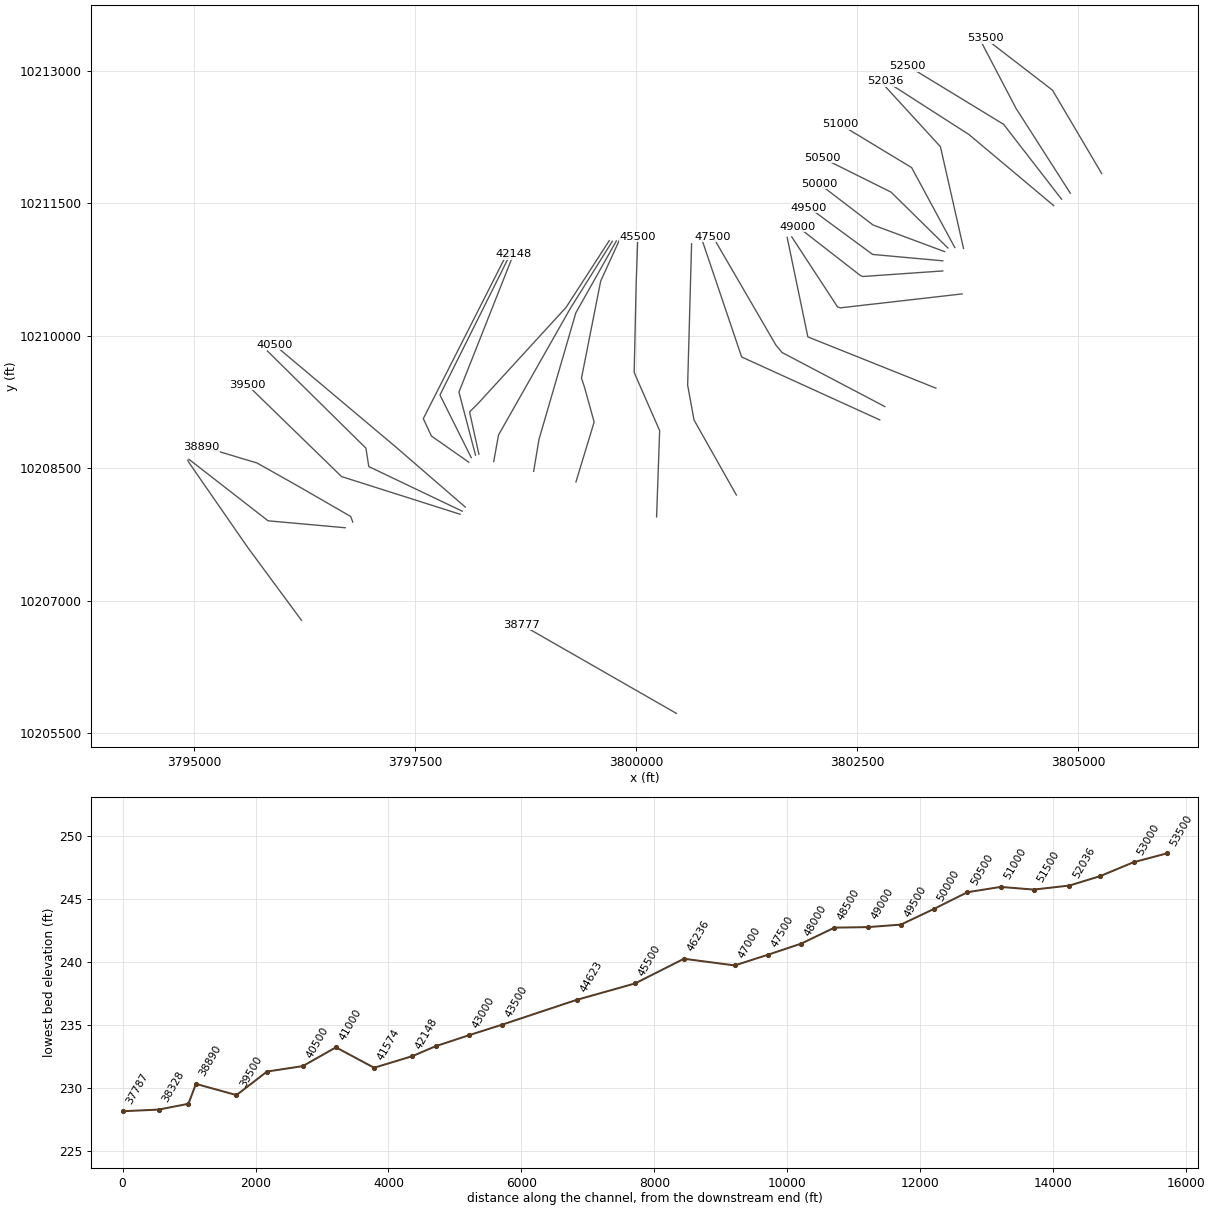
HEC-RAS study EAST SANDY CREEK.prj: EAST SANDY CREEK Base Level Engineering

--- EAST SANDY CREEK.g01 (geometry) --- (continued)

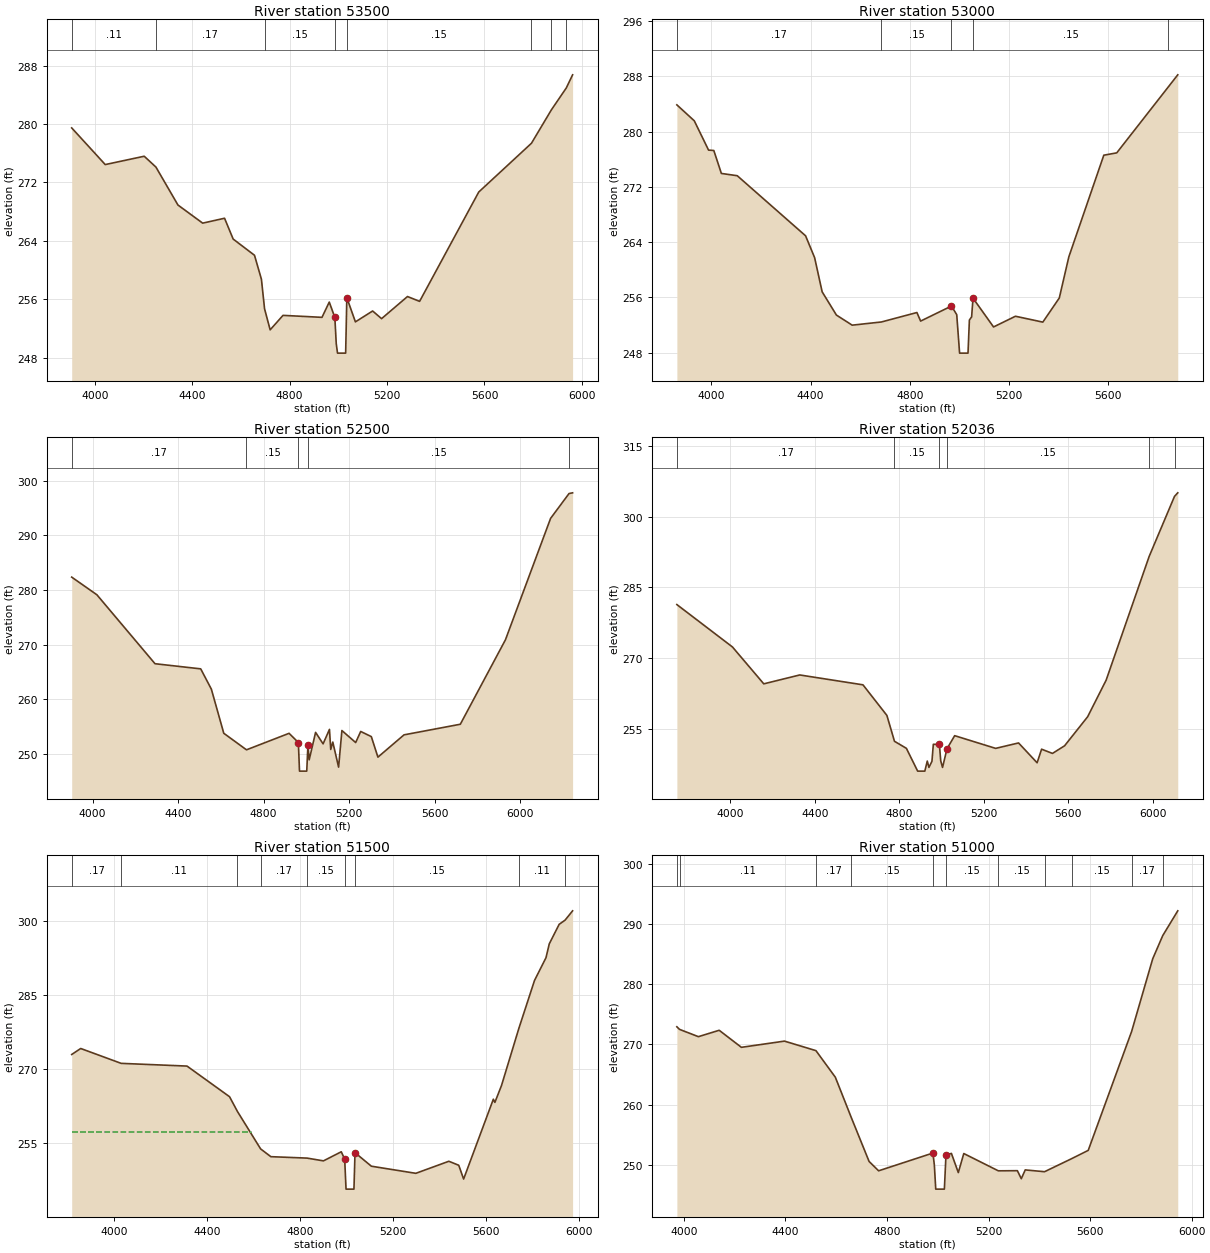
Type RM Length L Ch R = 1 ,53500   ,500,500,500
BEGIN DESCRIPTION:
EAST SANDY CREEK 102.0
END DESCRIPTION:
XS GIS Cut Line= 3
      3805264.16     10211839.88      3804708.29      10212783.3
      3803946.75     10213370.77
#Sta/Elev= 30
    3905  279.47  4042.7  274.45  4202.7  275.59  4250.8  274.11  4341.3  268.91
  4442.8  266.43  4532.6   267.1    4568  264.25  4655.6  262.03    4684  258.75
  4696.9   254.7  4719.9  251.82  4772.7   253.8  4932.7  253.53  4962.6  255.62
  4985.5  253.52  4991.3  249.91  4996.5  248.63  5029.9  248.63  5034.7  256.22
    5070  252.91  5140.7   254.4  5177.4  253.35  5283.8  256.38  5333.6  255.72
  5576.4  270.69  5792.9  277.37  5874.8  281.95  5935.9  284.94  5961.8  286.74
#Mann= 8 ,-1 , 0
    3905     .11       0  4250.8     .17       0  4696.9     .15       0
  4985.5     .09       0  5034.7     .15       0  5792.9     .17       0
  5874.8     .15       0  5935.9     .17       0
Bank Sta=4985.5,5034.7
XS Rating Curve= 0 ,0
Exp/Cntr=0.3,0.1

Type RM Length L Ch R = 1 ,53000   ,500,500,500
BEGIN DESCRIPTION:
EAST SANDY CREEK 101.0
END DESCRIPTION:
XS GIS Cut Line= 3
      3804910.06       10211616.      3804297.09     10212575.64
      3803889.51     10213355.11
#Sta/Elev= 30
  3861.3  283.88  3931.5  281.57    3989  277.33  4010.2  277.27  4040.6  273.95
  4104.6  273.62  4379.9  264.92  4416.3  261.76  4446.7  256.81  4504.2  253.44
  4567.7  251.98  4685.4  252.44  4828.5  253.81  4843.5  252.57  4967.8  254.75
    4989   253.5  5000.5  247.93  5034.4  247.93    5040  252.72    5049  253.18
  5054.6  255.89  5137.3  251.72  5225.6  253.27  5335.9  252.42  5402.2  255.91
  5440.7  261.87  5581.6  276.59  5633.7  276.93  5842.2  286.51  5879.6  288.23
#Mann= 5 ,-1 , 0
  3861.3     .17       0  4685.4     .15       0  4967.8     .09       0
  5054.6     .15       0  5842.2     .17       0
Bank Sta=4967.8,5054.6
XS Rating Curve= 0 ,0
Exp/Cntr=0.3,0.1

Type RM Length L Ch R = 1 ,52500   ,464,464,464
BEGIN DESCRIPTION:
EAST SANDY CREEK 100.0
END DESCRIPTION:
XS GIS Cut Line= 4
      3804811.18     10211548.24      3804154.02     10212398.78
      3804134.45     10212409.61      3803072.37     10213058.09
#Sta/Elev= 30
  3902.8  282.34  4020.5  279.11  4292.2  266.49  4505.9  265.55  4555.7  261.83
  4613.7  253.76  4719.9  250.73  4918.9  253.75  4962.4  252.07  4967.7  246.83
  5001.6  246.83  5007.1  251.59    5013   248.9  5042.9  253.92    5078  251.82
  5107.8  254.47  5113.7  250.79  5123.3  252.15  5150.5  247.56  5165.9  254.26
  5230.3  252.06  5253.8  254.09  5303.4  253.15  5334.3  249.39  5456.3  253.47
  5719.5  255.41  5930.5  270.87  6141.5  293.09  6227.8  297.64  6244.4  297.77
#Mann= 5 ,-1 , 0
  3902.8     .17       0  4719.9     .15       0  4962.4     .09       0
  5007.1     .15       0  6227.8     .17       0
Bank Sta=4962.4,5007.1
XS Rating Curve= 0 ,0
Exp/Cntr=0.3,0.1

Type RM Length L Ch R = 1 ,52036   ,536,536,536
BEGIN DESCRIPTION:
EAST SANDY CREEK 99.0
END DESCRIPTION:
XS GIS Cut Line= 3
      3804722.61      10211475.4      3803763.05     10212281.47
      3802822.74     10212886.05
#Sta/Elev= 30
  3746.8  281.36  4009.9  272.38  4158.2  264.57  4328.6  266.45  4627.8  264.36
    4741  257.88  4776.9   252.4  4833.3  250.91  4886.6  246.08  4920.6  246.08
  4932.2  248.21    4940  246.87  4954.3  248.16  4960.8  251.76  4989.4  251.74
  4995.8  248.28  5004.4  246.86  5025.5  250.81  5061.8  253.59  5255.8   250.9
  5364.3  252.05  5452.1  247.85  5473.3  250.73  5524.8  249.83  5582.2  251.45
  5691.2  257.59  5778.9  265.35  5982.2  291.52  6102.5  304.28  6117.9  305.03
#Mann= 6 ,-1 , 0
  3746.8     .17       0  4776.9     .15       0  4989.4     .09       0
  5025.5     .15       0  5982.2     .11       0  6102.5     .17       0
Bank Sta=4989.4,5025.5
XS Rating Curve= 0 ,0
Exp/Cntr=0.3,0.1

Type RM Length L Ch R = 1 ,51500   ,500,500,500
BEGIN DESCRIPTION:
EAST SANDY CREEK 98.0
END DESCRIPTION:
XS GIS Cut Line= 3
      3803702.03     10210991.13      3803440.87     10212143.61
       3802785.6     10212860.45
#Sta/Elev= 30
  3818.3  273.02    3857  274.23  4030.9  271.22  4313.9  270.67  4496.7  264.47
  4530.4   261.5  4630.3   253.9  4674.3  252.33  4830.1  252.04  4900.3  251.48
  4976.9  253.32  4991.6  251.84  4997.4  245.76  5031.4  245.76    5036  253.14
  5106.3   250.4  5297.4  248.96  5439.3   251.4  5481.8  250.59  5502.8   247.8
  5630.5  263.96  5637.2  263.32  5665.6  266.73    5740  278.27  5807.5     288
  5856.8  292.61    5871  295.42  5913.5  299.37  5938.8  300.21  5971.2   302.1
#Mann= 9 ,-1 , 0
  3818.3     .17       0  4030.9     .11       0  4530.4     .15       0
  4630.3     .17       0  4830.1     .15       0  4991.6     .09       0
    5036     .15       0    5740     .11       0  5938.8     .17       0
#XS Ineff= 2 , 0
       0  4588.1  257.42               0
Permanent Ineff=
       F       F
Bank Sta=4991.6,5036
XS Rating Curve= 0 ,0
Exp/Cntr=0.3,0.1

Type RM Length L Ch R = 1 ,51000   ,500,500,500
BEGIN DESCRIPTION:
EAST SANDY CREEK 97.0
END DESCRIPTION:
XS GIS Cut Line= 3
      3803603.09     10211001.55      3803115.59     10211906.15
      3802307.33     10212396.55
#Sta/Elev= 30
  3972.4  272.92  3982.9  272.49  4057.1  271.28  4139.1  272.34  4226.6  269.51
  4396.2  270.54  4520.2  268.96  4596.6  264.55  4659.3  257.87  4729.5  250.57
    4767  249.01  4980.9  251.96  4986.6  249.98  4992.1  245.97  5026.1  245.97
  5032.4  251.62  5053.8   251.9    5081  248.72  5102.6  251.88  5238.5  249.01
  5313.7  249.03  5329.1   247.7  5344.6  249.16  5420.6  248.86  5527.1  251.02
  5592.7   252.4  5763.5  272.12  5846.7   284.2  5886.3  288.06  5945.4  292.17
#Mann= 11 ,-1 , 0
  3972.4     .17       0  3982.9     .11       0  4520.2     .17       0
  4659.3     .15       0  4980.9     .06       0  5032.4     .15       0
  5238.5     .15       0  5420.6     .11       0  5527.1     .15       0
  5763.5     .17       0  5886.3     .11       0
Bank Sta=4980.9,5032.4
XS Rating Curve= 0 ,0
Exp/Cntr=0.3,0.1

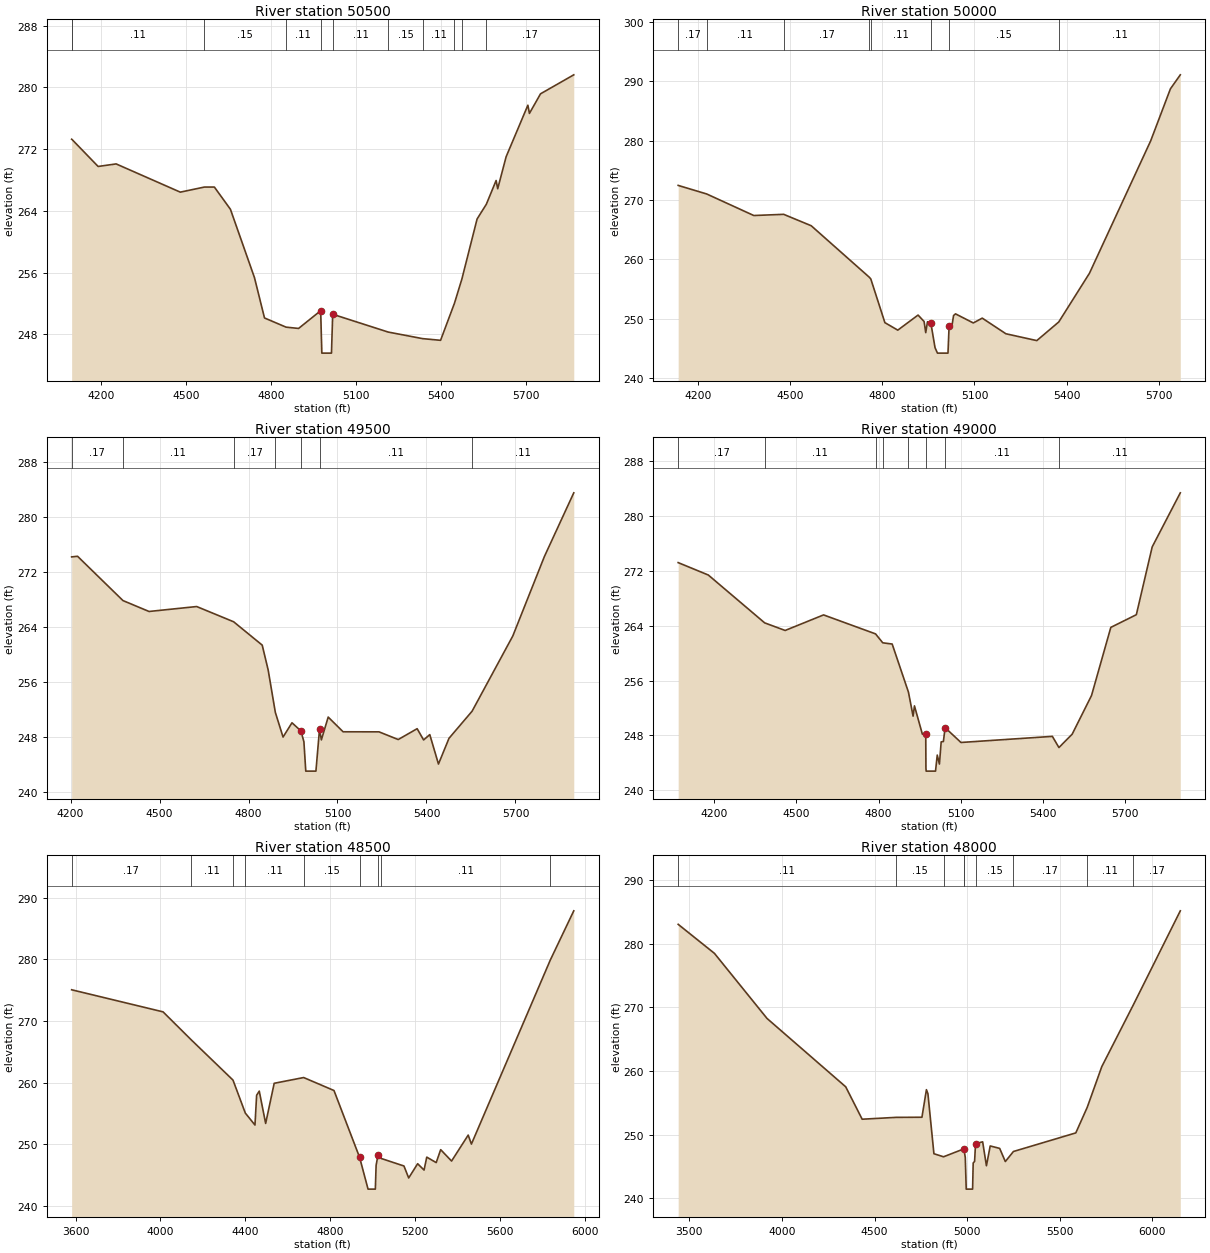
Type RM Length L Ch R = 1 ,50500   ,500,500,500
BEGIN DESCRIPTION:
EAST SANDY CREEK 96.0
END DESCRIPTION:
XS GIS Cut Line= 3
      3803525.02      10210996.3       3802881.8     10211629.22
      3802104.31     10212016.49
#Sta/Elev= 30
  4097.6  273.28  4098.6  273.26    4191  269.75  4254.5  270.08  4480.8  266.42
  4565.9  267.08    4601  267.08  4657.6   264.2  4742.4  255.34  4777.8  250.11
  4853.7  248.92    4898  248.75  4975.9  251.05    4980  245.55    5014  245.55
  5018.3  250.59  5214.1  248.28  5335.4  247.43  5398.8  247.21  5447.8  252.02
  5473.9  255.15  5527.6  262.94  5560.2  264.85  5594.7  267.93  5600.3  266.86
    5630  271.01  5706.7  277.69  5712.2  276.63  5751.4  279.17  5868.6  281.63
#Mann= 11 ,-1 , 0
  4097.6     .17       0  4098.6     .11       0  4565.9     .15       0
  4853.7     .11       0  4975.9     .06       0  5018.3     .11       0
  5214.1     .15       0  5335.4     .11       0  5447.8     .15       0
  5473.9     .11       0  5560.2     .17       0
Bank Sta=4975.9,5018.3
XS Rating Curve= 0 ,0
Exp/Cntr=0.3,0.1

Type RM Length L Ch R = 1 ,50000   ,500,500,500
BEGIN DESCRIPTION:
EAST SANDY CREEK 95.0
END DESCRIPTION:
XS GIS Cut Line= 3
      3803488.55     10210954.67      3802678.22     10211256.74
      3802066.97     10211725.34
#Sta/Elev= 30
  4135.2  272.47    4228  271.03  4381.4   267.4  4478.8   267.6  4568.4  265.68
  4757.5  257.01  4762.4  256.72  4808.3  249.36  4850.3   248.1  4916.3  250.64
  4935.9  249.56  4941.3  247.68    4947  249.51  4957.7  249.37  4971.6  245.14
  4979.5  244.23  5013.7  244.23  5017.4  248.79  5025.6  248.48  5031.9  250.56
  5038.3  250.84  5096.2  249.31  5125.3  250.12  5202.3  247.49  5302.9  246.34
  5374.5  249.48  5474.3  257.67  5673.7  279.97  5738.1  288.74  5770.2  291.09
#Mann= 8 ,-1 , 0
  4135.2     .17       0    4228     .11       0  4478.8     .17       0
  4757.5     .15       0  4762.4     .11       0  4957.7     .09       0
  5017.4     .15       0  5374.5     .11       0
Bank Sta=4957.7,5017.4
XS Rating Curve= 0 ,0
Exp/Cntr=0.3,0.1

Type RM Length L Ch R = 1 ,49500   ,500,500,500
BEGIN DESCRIPTION:
EAST SANDY CREEK 94.0
END DESCRIPTION:
XS GIS Cut Line= 3
       3803467.7     10210850.53      3802674.68     10210922.73
      3801952.62     10211454.42
#Sta/Elev= 30
  4203.7  274.18  4223.6  274.27  4376.7  267.82  4464.6  266.23  4625.3  266.95
  4749.9  264.73  4846.2  261.33  4866.3  257.71  4890.5  251.53  4916.5  247.94
  4946.6  250.02  4976.7  248.84  4986.8  247.26  4993.1  242.98  5027.3  242.98
  5039.5  249.11  5045.7  247.53  5068.7  250.85  5118.9  248.71    5240   248.7
  5304.8  247.58  5368.6  249.16  5390.4  247.52  5411.2   248.3  5440.5  244.01
    5476  247.76  5553.9  251.71  5691.2  262.67  5797.7  274.24  5896.7  283.51
#Mann= 7 ,-1 , 0
  4203.7     .17       0  4376.7     .11       0  4749.9     .17       0
  4890.5     .11       0  4976.7     .06       0  5039.5     .11       0
  5553.9     .11       0
Bank Sta=4976.7,5039.5
XS Rating Curve= 0 ,0
Exp/Cntr=0.3,0.1

Type RM Length L Ch R = 1 ,49000   ,500,500,500
BEGIN DESCRIPTION:
EAST SANDY CREEK 93.0
END DESCRIPTION:
XS GIS Cut Line= 4
      3803467.68     10210735.97      3802565.56     10210672.94
      3802539.19     10210681.36      3801827.49     10211235.84
#Sta/Elev= 30
    4068   273.2  4178.1  271.39  4383.9  264.41  4458.8   263.3  4599.1  265.57
    4789   262.8  4815.3   261.5  4849.7  261.32  4909.2   254.3  4926.1   250.8
  4931.1   252.3    4960  248.17  4972.3  248.26    4973  243.28  4973.8  242.78
    5008  242.78  5014.4  245.12  5022.3  243.81  5028.7  247.05  5036.8   247.1
  5043.1  249.12    5101  246.96  5434.9  247.85  5458.8  246.22  5507.2  248.17
  5577.8   253.8  5648.4  263.75  5741.6   265.6  5799.5  275.49  5902.2  283.38
#Mann= 8 ,-1 , 0
    4068     .17       0  4383.9     .11       0    4789     .17       0
  4815.3     .15       0  4909.2     .11       0  4972.3     .06       0
  5043.1     .11       0  5458.8     .11       0
Bank Sta=4972.3,5043.1
XS Rating Curve= 0 ,0
Exp/Cntr=0.3,0.1

Type RM Length L Ch R = 1 ,48500   ,500,500,500
BEGIN DESCRIPTION:
EAST SANDY CREEK 92.0
END DESCRIPTION:
XS GIS Cut Line= 4
      3803686.46     10210475.62      3802309.49      10210317.9
      3802278.46     10210326.96      3801759.78     10211121.31
#Sta/Elev= 30
  3581.7  275.06  4012.6  271.48  4144.4  266.98  4342.2  260.42  4400.4  255.07
  4445.9  253.13  4453.7  257.96  4466.1  258.63  4496.2  253.39  4536.5   259.9
  4675.4  260.83  4818.3  258.73  4939.1  247.89  4978.9  242.74  5013.3  242.74
  5016.9  246.59  5025.7  248.26  5040.9  247.71  5148.2  246.49  5170.5  244.55
  5212.7  246.86  5242.9  245.83  5255.7  247.93  5300.2  247.04  5321.3  249.14
  5372.6  247.29    5451   251.5  5466.1  250.04  5838.3   279.9  5948.7  287.86
#Mann= 9 ,-1 , 0
  3581.7     .17       0  4144.4     .11       0  4342.2     .15       0
  4400.4     .11       0  4675.4     .15       0  4939.1     .09       0
  5025.7     .15       0  5040.9     .11       0  5838.3     .17       0
#XS Ineff= 2 , 0
       0  4818.3  258.73               0
Permanent Ineff=
       F       F
Bank Sta=4939.1,5025.7
XS Rating Curve= 0 ,0
Exp/Cntr=0.3,0.1

Type RM Length L Ch R = 1 ,48000   ,500,500,500
BEGIN DESCRIPTION:
EAST SANDY CREEK 91.0
END DESCRIPTION:
XS GIS Cut Line= 3
       3803389.6     10209408.16      3801941.58     10209988.83
      3801707.71     10211116.13
#Sta/Elev= 30
  3439.9  283.06  3635.7   278.5  3919.6  268.28  4344.6  257.54  4433.4  252.45
  4615.5  252.74  4756.2  252.76  4780.4  257.09  4788.5  256.45  4820.9  247.03
  4872.8  246.55  4980.8  247.77  4982.5  247.81  4990.2  246.45  4995.3  241.47
  5029.7  241.47  5032.9  245.57  5040.5  245.83  5045.6   248.6    5084   248.9
  5104.4  245.14  5124.8  248.25  5175.9  247.87  5206.5   245.8  5250.2  247.38
    5587   250.3  5648.9  254.33  5727.2   260.7  5897.5   270.4  6151.3  285.18
#Mann= 9 ,-1 , 0
  3439.9     .11       0  4615.5     .15       0  4872.8     .11       0
  4980.8     .15       0  4982.5     .09       0  5045.6     .15       0
  5250.2     .17       0  5648.9     .11       0  5897.5     .17       0
#XS Ineff= 2 , 0
       0  4780.4  257.09               0
Permanent Ineff=
       F       F
Bank Sta=4982.5,5045.6
XS Rating Curve= 0 ,0
Exp/Cntr=0.3,0.1

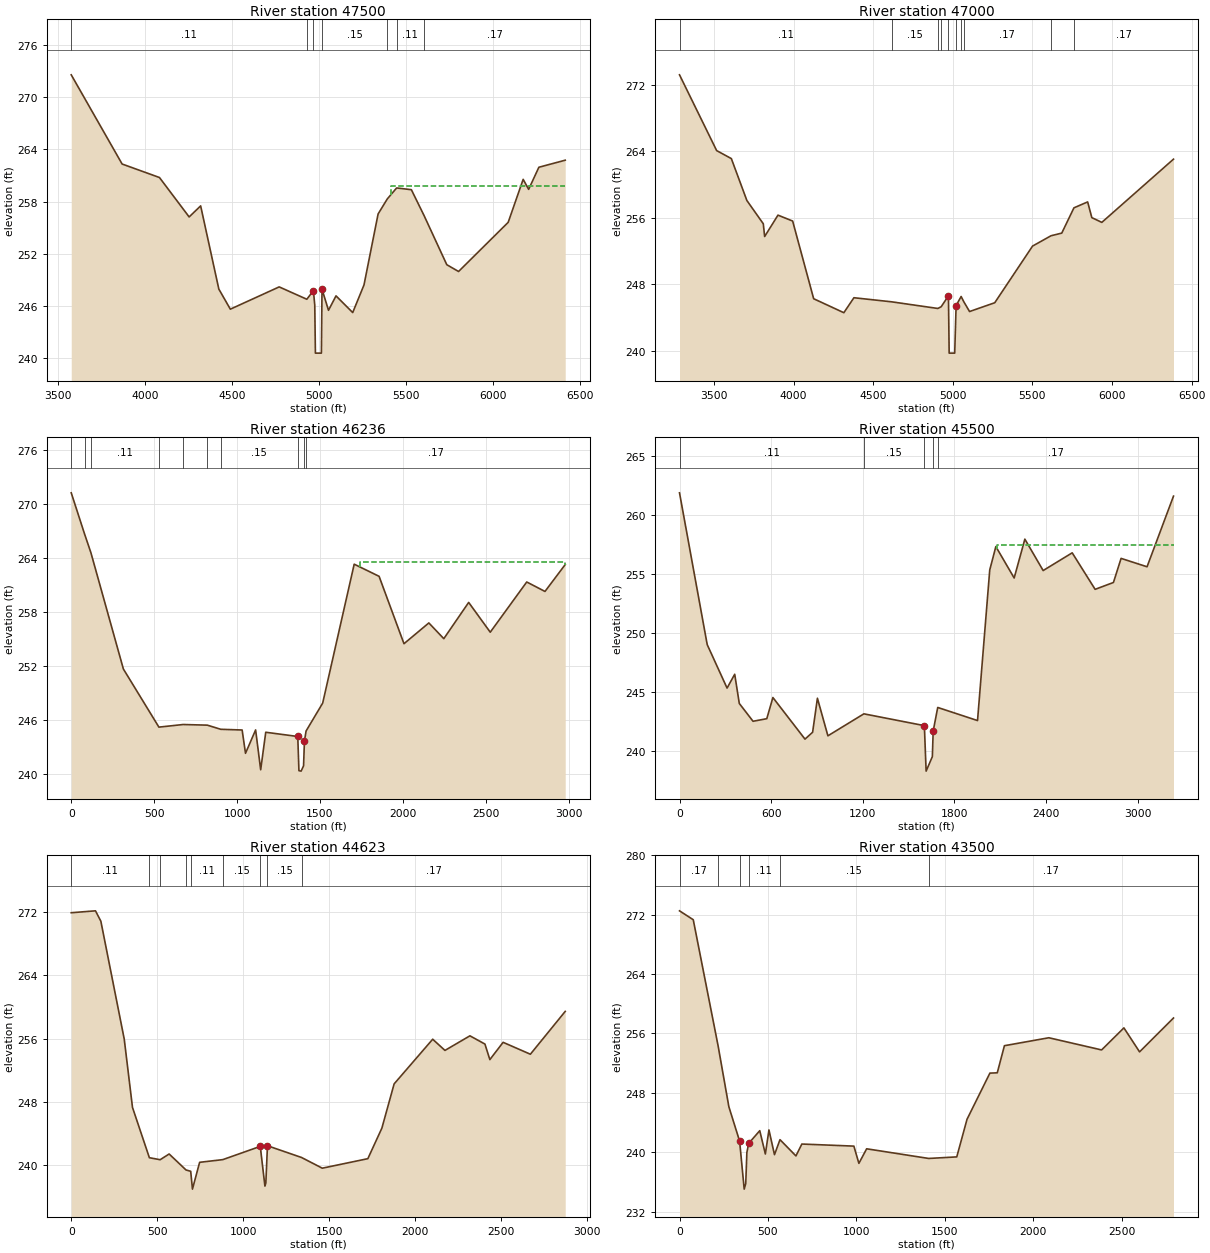
Type RM Length L Ch R = 1 ,47500   ,500,500,500
BEGIN DESCRIPTION:
EAST SANDY CREEK 90.0
END DESCRIPTION:
XS GIS Cut Line= 4
      3802811.61     10209199.88      3801649.76     10209811.83
      3801579.29     10209897.52      3800869.37     10211121.31
#Sta/Elev= 30
  3575.9  272.57  3868.3  262.32  4082.9  260.77  4253.5  256.24  4319.6  257.51
  4424.1  247.95  4490.2  245.64    4771   248.2  4929.8  246.78  4967.6  247.77
  4975.4   246.1  4979.1  240.59  5013.5  240.59  5017.1  247.93  5054.4  245.51
  5097.5  247.17  5193.5  245.25  5258.4  248.43  5339.4  256.58  5392.3  258.31
  5445.9  259.57  5530.6  259.37  5603.5   256.4  5734.2  250.75  5801.8  249.97
    6087  255.62  6173.1  260.56  6204.6  259.41  6263.4  261.95  6414.8  262.76
#Mann= 7 ,-1 , 0
  3575.9     .11       0  4929.8     .15       0  4967.6     .09       0
  5017.1     .15       0  5392.3     .17       0  5445.9     .11       0
  5603.5     .17       0
#XS Ineff= 2 , 0
       0                    5413       0  259.85
Permanent Ineff=
       F       F
Bank Sta=4967.6,5017.1
XS Rating Curve= 0 ,0
Exp/Cntr=0.3,0.1

Type RM Length L Ch R = 1 ,47000   ,764,764,764
BEGIN DESCRIPTION:
EAST SANDY CREEK 89.0
END DESCRIPTION:
XS GIS Cut Line= 3
      3802754.34     10209048.87        3801193.     10209761.29
       3800749.6     10211074.45
#Sta/Elev= 30
  3283.8   273.2  3517.1  264.09  3609.3  263.13  3706.9  258.09    3810  255.29
  3818.5  253.76  3902.2  256.33  3994.3  255.62  4126.3  246.28  4315.8   244.6
  4379.1   246.4  4615.4  245.91  4906.2  245.11  4927.2  245.32  4972.7  246.63
  4977.2  239.74    5012  239.74  5020.9  245.46  5052.5  246.55  5068.2  245.95
  5105.3  244.74  5263.6   245.8  5500.9  252.61  5616.7  253.85  5684.3  254.17
  5760.9  257.21  5846.9  257.92  5873.1  256.03    5936  255.46    6386  263.06
#Mann= 10 ,-1 , 0
  3283.8     .11       0  4615.4     .15       0  4906.2     .11       0
  4927.2     .15       0  4972.7     .09       0  5020.9     .15       0
  5052.5     .11       0  5068.2     .17       0  5616.7     .11       0
  5760.9     .17       0
#XS Ineff= 2 , 0
       0                  5453.6       0  251.16
Permanent Ineff=
       F       F
Bank Sta=4972.7,5020.9
XS Rating Curve= 0 ,0
Exp/Cntr=0.3,0.1

Type RM Length L Ch R = 1 ,46236   ,736,736,736
BEGIN DESCRIPTION:
EAST SANDY CREEK 87.0
END DESCRIPTION:
XS GIS Cut Line= 4
      3801133.29      10208197.1      3800654.12      10209047.8
      3800582.23     10209443.34      3800626.78     10211043.02
#Sta/Elev= 30
       0   271.2    80.8   266.6   118.4  264.56   314.4  251.62   528.7  245.16
   674.6  245.45   820.6  245.38   901.5  244.92  1030.5  244.84  1050.8  242.25
  1111.8  244.85  1142.3  240.42  1172.8  244.59  1365.9  244.12    1373  240.32
  1386.1  240.27  1400.9  240.86  1406.1   243.6  1416.1  244.73  1516.2  247.83
  1706.2  263.27  1856.3  261.92  2006.4  254.43  2156.4  256.74  2246.5  254.99
  2396.5  259.02  2526.6  255.71  2746.6  261.29  2856.7  260.24  2978.7  263.23
#Mann= 10 ,-1 , 0
       0     .11       0    80.8     .17       0   118.4     .11       0
   528.7     .17       0   674.6     .15       0   820.6     .11       0
   901.5     .15       0  1365.9     .09       0  1406.1     .15       0
  1416.1     .17       0
#XS Ineff= 2 , 0
                         1743.94          263.51
Permanent Ineff=
       F       F
Bank Sta=1365.9,1406.1
XS Rating Curve= 0 ,0
Exp/Cntr=0.3,0.1

Type RM Length L Ch R = 1 ,45500   ,877,877,877
BEGIN DESCRIPTION:
EAST SANDY CREEK 86.0
END DESCRIPTION:
XS GIS Cut Line= 6
      3800230.98     10207949.72      3800265.62     10208926.96
      3799995.08     10209545.52      3799977.45     10209588.66
      3799999.79     10210584.96       3800018.7     10211124.18
#Sta/Elev= 30
       0  261.87   181.5  249.02   311.5  245.34   361.6  246.51   391.6  244.04
   481.7  242.53   571.7  242.75   611.7  244.54   821.9  241.02   871.9   241.6
   903.3  244.48     972   241.3  1207.7  243.16  1603.8  242.16  1615.4  238.31
  1656.2  239.54  1661.6   241.7  1691.4   243.7  1952.1  242.59  2032.1  255.34
  2072.1  257.32  2192.1  254.66  2262.1  257.95  2381.9  255.29  2572.2  256.79
  2722.3   253.7  2842.3  254.28  2892.4  256.32  3062.5  255.61  3235.7  261.59
#Mann= 5 ,-1 , 0
       0     .11       0  1207.7     .15       0  1603.8     .09       0
  1661.6     .15       0  1691.4     .17       0
#XS Ineff= 2 , 0
                         2080.62          257.48
Permanent Ineff=
       F       F
Bank Sta=1603.8,1661.6
XS Rating Curve= 0 ,0
Exp/Cntr=0.3,0.1

Type RM Length L Ch R = 1 ,44623   ,1123,1123,1123
BEGIN DESCRIPTION:
EAST SANDY CREEK 84.0
END DESCRIPTION:
XS GIS Cut Line= 6
      3799319.06     10208346.17      3799524.87     10209024.23
      3799414.33     10209423.51       3799381.5     10209520.96
      3799598.84     10210621.41      3799817.32     10211099.88
#Sta/Elev= 30
       0  271.86     141   272.1   172.3  270.79   308.2  255.94   356.3  247.31
   454.5  240.97   517.2  240.72   569.5  241.44     668  239.42   694.9  239.26
   705.1  237.01   746.8  240.39   881.7  240.73  1099.6   242.4  1126.6  237.39
  1131.9  237.77  1141.4  242.48  1339.5     241  1460.3  239.65  1725.3  240.85
  1806.9   244.7  1878.2  250.28  2102.5  255.91  2173.8   254.5  2319.1  256.34
  2406.4   255.3    2435  253.34    2512  255.52  2670.7  254.02  2873.4  259.42
#Mann= 9 ,-1 , 0
       0     .11       0   454.5     .15       0   517.2     .11       0
     668     .12       0   694.9     .11       0   881.7     .15       0
  1099.6     .09       0  1141.4     .15       0  1339.5     .17       0
Bank Sta=1099.6,1141.4
XS Rating Curve= 0 ,0
Exp/Cntr=0.3,0.1

Type RM Length L Ch R = 1 ,43500   ,500,500,500
BEGIN DESCRIPTION:
EAST SANDY CREEK 83.0
END DESCRIPTION:
XS GIS Cut Line= 4
      3798840.68     10208465.67      3798900.87     10208827.07
      3799317.85     10210261.07      3799775.65     10211075.57
#Sta/Elev= 30
       0  272.51    77.8  271.31   218.4  254.32   279.2  246.13     340   241.5
   365.9  235.04   374.6  235.78     381  239.97   391.4   241.2   453.9  242.91
   485.6  239.77   505.9  243.01   537.2  239.68   568.4   241.7   658.5  239.51
     692  241.11   986.3  240.83  1014.6  238.51  1058.5  240.47  1409.4  239.17
  1568.2  239.38  1626.2  244.44  1755.6  250.66  1797.3   250.7  1837.8  254.35
    2089  255.42  2387.5  253.78  2513.6  256.75  2602.2  253.52  2794.1  258.08
#Mann= 6 ,-1 , 0
       0     .17       0   218.4     .11       0     340     .06       0
   391.4     .11       0   568.4     .15       0  1409.4     .17       0
Bank Sta=340,391.4
XS Rating Curve= 0 ,0
Exp/Cntr=0.3,0.1

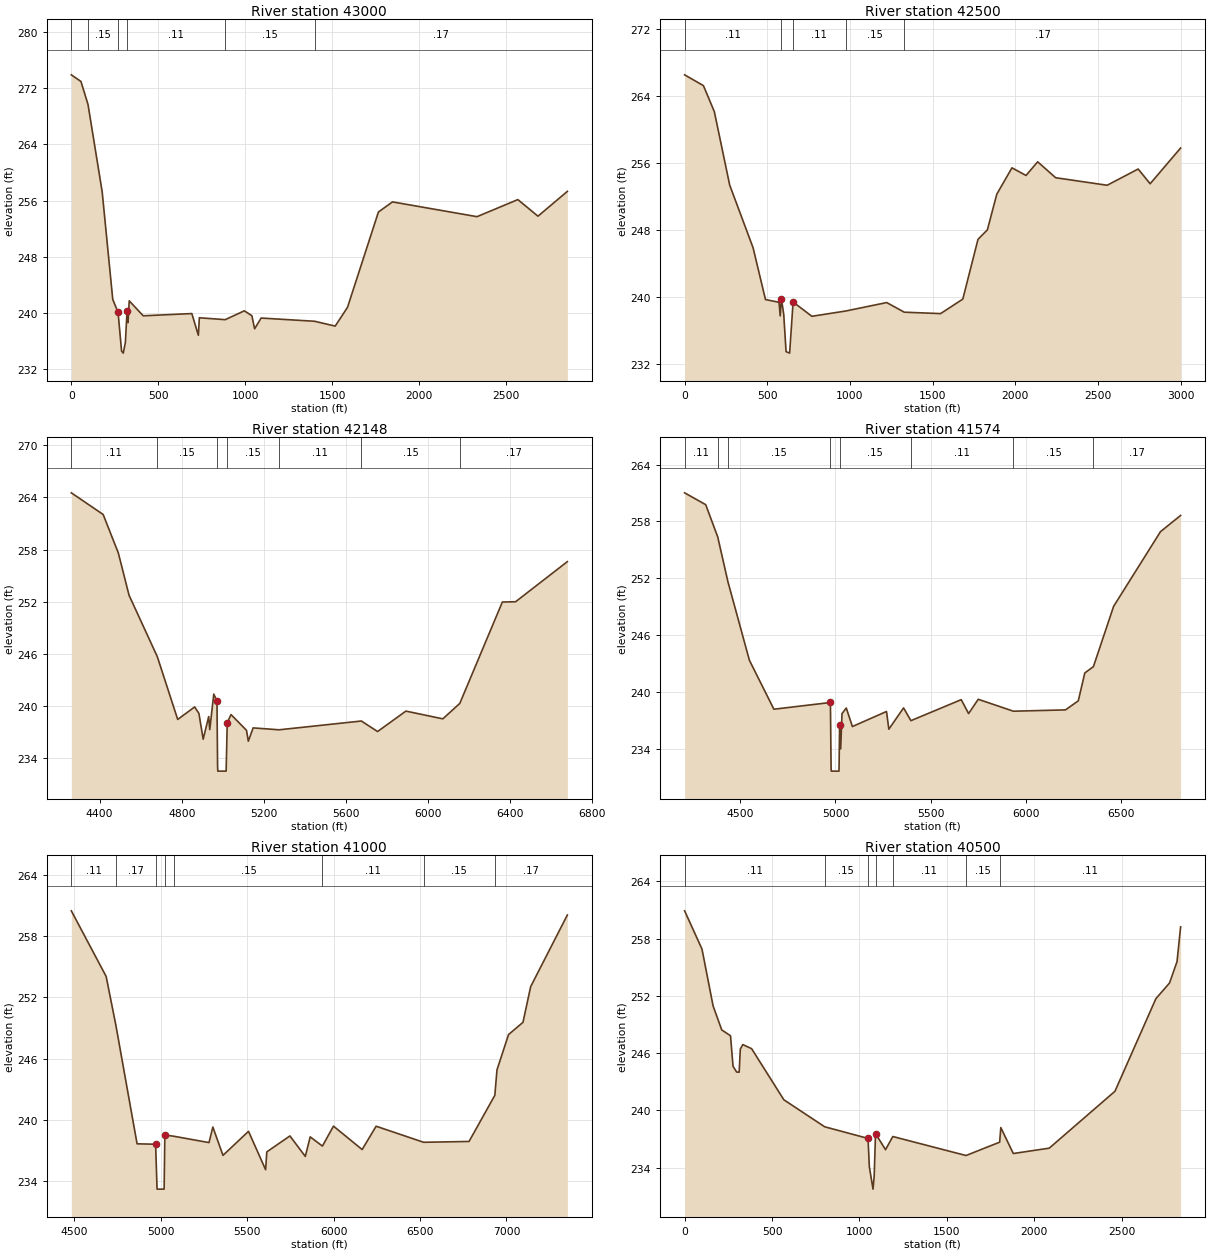
Type RM Length L Ch R = 1 ,43000   ,500,500,500
BEGIN DESCRIPTION:
EAST SANDY CREEK 82.0
END DESCRIPTION:
XS GIS Cut Line= 4
      3798389.29     10208576.78      3798443.37     10208877.56
      3799256.05     10210312.71      3799730.51      10211072.1
#Sta/Elev= 30
       0  273.95    55.2     273    95.8  269.72   177.1  257.26     238  241.88
   268.5  240.01   288.8  234.48   298.3   234.2   310.5  235.71   320.1  240.16
   325.9  238.56   332.6  241.67   413.1  239.53   692.4  239.85   729.9  236.75
   735.7  239.25   884.2  238.98     994  240.24  1037.3  239.55  1053.2  237.67
  1090.7  239.21    1398  238.75  1516.3  238.06    1587  240.74  1764.6  254.35
  1845.4   255.8  2331.2  253.69  2565.9  256.13  2681.5  253.76  2850.3   257.3
#Mann= 6 ,-1 , 0
       0     .11       0    95.8     .15       0   268.5     .06       0
   320.1     .11       0   884.2     .15       0    1398     .17       0
Bank Sta=268.5,320.1
XS Rating Curve= 0 ,0
Exp/Cntr=0.3,0.1

Type RM Length L Ch R = 1 ,42500   ,352,352,352
BEGIN DESCRIPTION:
EAST SANDY CREEK 81.0
END DESCRIPTION:
XS GIS Cut Line= 5
      3798221.33     10208659.94      3798116.03     10209139.27
      3798208.47     10209230.48      3799207.44     10210323.13
      3799695.79     10211079.05
#Sta/Elev= 30
       0  266.57   113.8  265.28   179.8  262.17   272.5  253.41   414.1  245.91
   489.1  239.73   571.1   239.4   578.1  237.78   585.3  239.83   599.4  237.95
   613.5  233.51     635  233.33     656  239.44   769.5  237.73   974.2  238.36
  1222.2  239.37  1328.2  238.22  1547.8  238.05  1682.2  239.78  1774.1  246.92
  1830.8  248.05  1887.6  252.31  1979.5  255.46  2064.6  254.55  2134.9  256.18
  2243.8  254.28  2555.2  253.38  2742.6  255.32  2815.1  253.56  2999.3  257.83
#Mann= 5 ,-1 , 0
       0     .11       0   585.3     .06       0     656     .11       0
   974.2     .15       0  1328.2     .17       0
Bank Sta=585.3,656
XS Rating Curve= 0 ,0
Exp/Cntr=0.3,0.1

Type RM Length L Ch R = 1 ,42148   ,574,574,574
BEGIN DESCRIPTION:
EAST SANDY CREEK 80.0
END DESCRIPTION:
XS GIS Cut Line= 3
      3798183.13     10208649.55      3797995.76     10209363.37
      3798613.04     10210925.64
#Sta/Elev= 30
    4262  264.53  4417.1  262.04    4491  257.62  4543.3  252.76  4681.2  245.69
  4780.5  238.48  4863.2  239.92  4883.9  239.17  4904.6  236.21  4931.6  238.81
  4936.7  237.31  4956.3  241.39  4971.9  240.62  4974.9  233.04  4975.9  232.54
  5016.6  232.54  5021.9  238.11  5040.5  239.04  5115.8  237.23  5124.7  235.98
  5148.1  237.51  5274.6  237.29  5675.9   238.3  5754.8  237.09  5892.7  239.44
  6072.8  238.55  6155.5  240.32  6363.1  251.98  6427.6  252.01  6679.8  256.62
#Mann= 7 ,-1 , 0
    4262     .11       0  4681.2     .15       0  4971.9     .09       0
  5021.9     .15       0  5274.6     .11       0  5675.9     .15       0
  6155.5     .17       0
Bank Sta=4971.9,5021.9
XS Rating Curve= 0 ,0
Exp/Cntr=0.3,0.1

Type RM Length L Ch R = 1 ,41574   ,574,574,574
BEGIN DESCRIPTION:
EAST SANDY CREEK 79.0
END DESCRIPTION:
XS GIS Cut Line= 3
      3798134.54     10208621.71      3797781.33     10209330.36
       3798589.4     10210951.64
#Sta/Elev= 30
  4208.2  261.02  4318.9  259.77  4381.9  256.37  4435.4  251.64  4548.3  243.33
  4676.8  238.16  4973.5  238.87  4976.9  232.12  4977.9  231.62  5018.6  231.62
  5021.7  236.52  5027.3  233.97  5034.3  237.69  5056.7  238.29  5088.8  236.33
  5267.9  237.92  5280.1  236.05  5357.4   238.3    5396  236.95    5660  239.17
  5698.7   237.7  5749.4  239.21  5933.9  237.95  6207.5  238.09  6274.5  239.05
  6308.6  241.99  6353.9  242.66  6459.7  249.02  6705.9  256.92  6811.5  258.63
#Mann= 8 ,-1 , 0
  4208.2     .11       0  4381.9     .17       0  4435.4     .15       0
  4973.5     .09       0  5021.7     .15       0    5396     .11       0
  5933.9     .15       0  6353.9     .17       0
Bank Sta=4973.5,5021.7
XS Rating Curve= 0 ,0
Exp/Cntr=0.3,0.1

Type RM Length L Ch R = 1 ,41000   ,500,500,500
BEGIN DESCRIPTION:
EAST SANDY CREEK 78.0
END DESCRIPTION:
XS GIS Cut Line= 4
      3798106.71     10208569.69      3797684.23     10208866.11
      3797592.86     10209062.71      3798557.41     10210967.52
#Sta/Elev= 30
  4483.9  260.45  4685.3  254.03  4741.8  249.23    4864  237.67  4971.2  237.63
  4979.6  233.24  5020.4  233.24  5024.5  238.54  5080.1   238.4  5279.9  237.79
  5302.2  239.31  5360.7  236.54  5508.3  238.89  5607.3  235.14  5614.1  236.88
  5747.7  238.44  5836.8  236.44  5865.1  238.35  5935.7  237.45  5999.6   239.4
  6165.4  237.11  6246.2  239.39  6520.9  237.82  6783.5   237.9  6932.6  242.41
  6945.1   244.9  7011.9  248.35  7095.4  249.55  7139.9  253.04  7351.9  260.04
#Mann= 8 ,-1 , 0
  4483.9     .11       0  4741.8     .17       0  4971.2     .09       0
  5024.5     .17       0  5080.1     .15       0  5935.7     .11       0
  6520.9     .15       0  6932.6     .17       0
Bank Sta=4971.2,5024.5
XS Rating Curve= 0 ,0
Exp/Cntr=0.3,0.1

Type RM Length L Ch R = 1 ,40500   ,537,537,537
BEGIN DESCRIPTION:
EAST SANDY CREEK 77.0
END DESCRIPTION:
XS GIS Cut Line= 3
      3798067.85     10208061.07      3797265.25     10208755.86
      3795907.59     10209899.69
#Sta/Elev= 30
       0   260.9    99.3   256.9   162.9  250.94   212.3  248.43   262.6  247.81
   276.9  244.62   297.8  244.01     312     244   318.6  246.42   332.9  246.89
   383.3  246.46   567.5  241.11   801.2  238.28  1049.1  237.06  1056.5   234.1
  1077.6  231.75  1084.3  233.12  1091.9  237.57  1149.1  235.88  1190.7  237.26
  1609.5  235.27  1801.9  236.67  1808.4   238.2  1879.9  235.48  2085.4  236.04
  2461.3     242  2695.4   251.7  2773.4  253.34  2816.3  255.58  2836.8  259.22
#Mann= 7 ,-1 , 0
       0     .11       0   801.2     .15       0  1049.1     .09       0
  1091.9     .15       0  1190.7     .11       0  1609.5     .15       0
  1801.9     .11       0
Bank Sta=1049.1,1091.9
XS Rating Curve= 0 ,0
Exp/Cntr=0.3,0.1

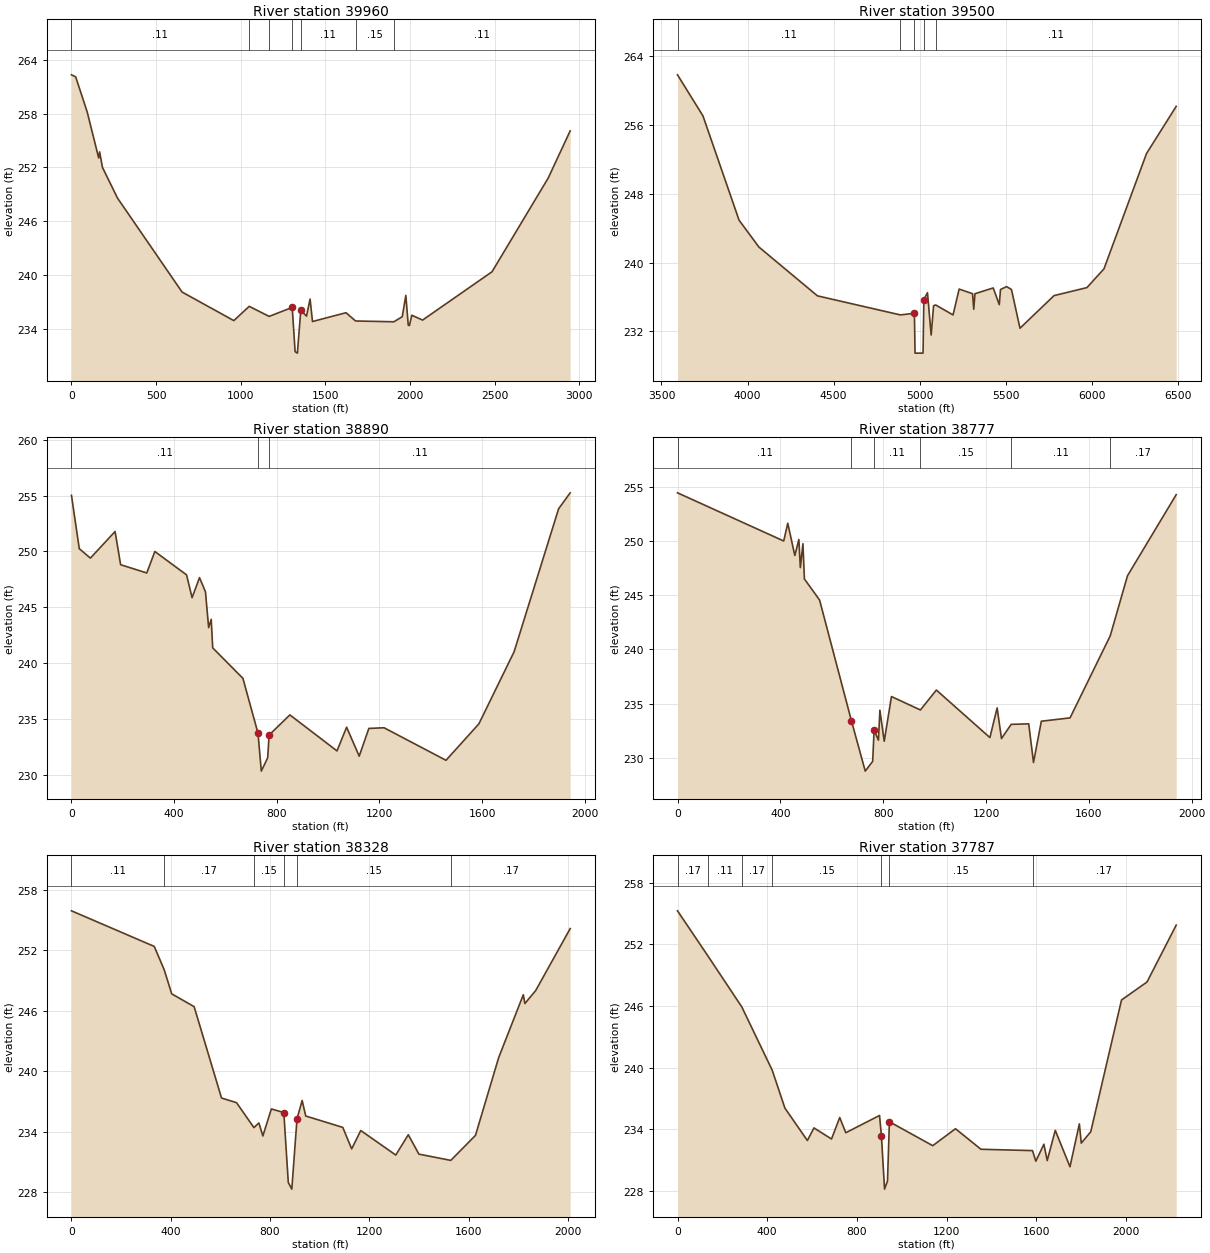
Type RM Length L Ch R = 1 ,39960   ,460,460,460
BEGIN DESCRIPTION:
EAST SANDY CREEK 76.0
END DESCRIPTION:
XS GIS Cut Line= 4
      3798033.06     10208014.35       3796976.3     10208519.89
       3796943.6     10208728.58      3795829.85      10209828.8
#Sta/Elev= 30
       0  262.31    24.8  262.09    92.8  258.18   160.8  253.05   166.3  253.73
   183.1     252   271.8  248.59   653.5  238.12   959.3  234.94    1050  236.53
  1167.8  235.41  1304.2  236.41  1321.2  231.48  1334.6  231.32  1354.8  236.09
  1388.5  235.44  1409.7  237.34  1423.9  234.84  1621.9  235.82  1678.4   234.9
  1904.7  234.81  1954.2  235.38  1975.4  237.75  1989.6  234.44  1996.6  234.39
  2010.7  235.54  2074.4     235  2484.6  240.38  2816.9  250.83  2946.3  256.07
#Mann= 7 ,-1 , 0
       0     .11       0    1050     .15       0  1167.8     .11       0
  1304.2     .06       0  1354.8     .11       0  1678.4     .15       0
  1904.7     .11       0
Bank Sta=1304.2,1354.8
XS Rating Curve= 0 ,0
Exp/Cntr=0.3,0.1

Type RM Length L Ch R = 1 ,39500   ,610,610,610
BEGIN DESCRIPTION:
EAST SANDY CREEK 75.0
END DESCRIPTION:
XS GIS Cut Line= 3
      3798008.79     10207979.62      3796668.34     10208406.56
      3795600.19     10209447.25
#Sta/Elev= 30
  3593.2  261.86  3741.1  257.08    3951  244.93  4066.5   241.8  4406.4  236.12
  4888.4   233.9  4969.9  234.09  4973.6  229.45    5020  229.45  5024.8  235.69
  5045.9  236.49  5067.2  231.56  5081.4  234.97  5093.3  235.06  5194.5   233.9
  5229.8  236.91  5307.7  236.37  5314.7  234.56  5321.8  236.37  5427.9  237.04
  5463.1   235.1  5470.3  236.86  5505.6   237.2  5533.9  236.86  5583.5  232.35
  5781.5  236.15  5972.4  237.08  6071.4  239.26  6318.9   252.7  6491.3  258.19
#Mann= 5 ,-1 , 0
  3593.2     .11       0  4888.4     .15       0  4969.9     .09       0
  5024.8     .15       0  5093.3     .11       0
Bank Sta=4969.9,5024.8
XS Rating Curve= 0 ,0
Exp/Cntr=0.3,0.1

Type RM Length L Ch R = 1 ,38890   ,113,113,113
BEGIN DESCRIPTION:
EAST SANDY CREEK 74.0
END DESCRIPTION:
XS GIS Cut Line= 6
      3796795.09     10207891.41      3796770.92     10207954.93
      3796186.01     10208293.09      3795712.05     10208560.33
      3795126.81     10208736.57      3795082.28     10208736.26
#Sta/Elev= 30
       0  255.01    30.4  250.24    73.8   249.4   169.9  251.78   191.5  248.81
   293.4  248.07   324.9  249.99   448.4   247.9   469.9  245.86   498.9  247.65
     522  246.39   534.5  243.18   544.5  243.92   550.3  241.37     668  238.64
   726.9  233.72   739.6  230.34   764.4  231.53   770.1  233.57     851  235.37
  1034.5  232.15    1072  234.27  1121.1  231.68  1158.7  234.16  1217.9  234.22
  1459.2  231.31  1587.4  234.57  1724.6  241.02    1898  253.81  1943.1  255.24
#Mann= 3 , 0 , 0
       0     .11       0   726.9     .06       0   770.1     .11       0
Bank Sta=726.9,770.1
XS Rating Curve= 0 ,0
Exp/Cntr=0.3,0.1

Type RM Length L Ch R = 1 ,38777   ,449,449,449
BEGIN DESCRIPTION:
EAST SANDY CREEK 73.0
END DESCRIPTION:
XS GIS Cut Line= 2
3800454.59997769 10205724.0769923798700.8713160310206730.7383873
#Sta/Elev= 30
       0  254.47   413.1  250.02   428.9  251.66   456.3  248.68   472.1  250.16
   477.8  247.56   487.9  249.77   493.6  246.51   552.6  244.57   676.3  233.43
   730.3  228.76   759.1  229.66   764.7  232.54   781.6  231.62   787.2  234.39
   804.1  231.52   832.2  235.65   944.8  234.41  1006.9  236.25  1215.1  231.86
  1243.2   234.6  1260.2  231.77  1297.8  233.08  1366.1  233.13  1384.7  229.56
  1415.2  233.37  1526.9  233.68  1683.2  241.26  1750.3  246.81  1939.8   254.3
#Mann= 6 ,-1 , 0
       0     .11       0   676.3     .06       0   764.7     .11       0
   944.8     .15       0  1297.8     .11       0  1683.2     .17       0
Bank Sta=676.3,764.7
XS Rating Curve= 0 ,0
Exp/Cntr=0.3,0.1

Type RM Length L Ch R = 1 ,38328   ,541,541,541
BEGIN DESCRIPTION:
EAST SANDY CREEK 73.5
END DESCRIPTION:
XS GIS Cut Line= 3
      3796710.14     10207826.85      3795837.11     10207905.45
      3794943.24     10208601.63
#Sta/Elev= 30
       0  255.89   333.6  252.36   373.8  250.04   403.9  247.66   494.3  246.39
   604.7  237.33   665.2  236.87   735.2   234.4   755.3  234.86   771.2  233.57
   805.5  236.25   855.7  235.89   873.7  228.96   887.9   228.3   908.7  235.24
   929.5  237.09     944  235.55  1093.3  234.42  1129.1  232.29  1165.7  234.11
  1306.8  231.68  1357.3  233.69    1400  231.77  1528.5  231.15    1628  233.63
  1721.2  241.32  1820.7  247.57    1827   246.7  1870.5  247.98  2009.6  254.13
#Mann= 6 ,-1 , 0
       0     .11       0   373.8     .17       0   735.2     .15       0
   855.7     .09       0   908.7     .15       0  1528.5     .17       0
Bank Sta=855.7,908.7
XS Rating Curve= 0 ,0
Exp/Cntr=0.3,0.1

Type RM Length L Ch R = 1 ,37787   ,1221,1221,1221
BEGIN DESCRIPTION:
EAST SANDY CREEK 71.0
END DESCRIPTION:
XS GIS Cut Line= 4
      3796214.94     10206778.28       3795607.3     10207603.37
      3794949.58     10208555.18      3794928.53     10208590.74
#Sta/Elev= 30
       0  255.26   136.1  250.85   286.5  245.91   422.3  239.74   478.7  236.06
   578.9   232.9   608.2  234.13   686.5  233.05   723.1  235.14   750.2  233.66
   900.6  235.34     909  233.33  922.95  228.17   936.1  228.97   944.5  234.73
  1137.7   232.4  1239.1  234.05  1352.7  232.05  1582.5  231.92  1597.3  230.89
  1633.2  232.54    1648  230.95  1683.9  233.89  1749.4  230.35  1791.3  234.52
  1799.8  232.65    1842  233.75  1979.2  246.58  2092.8  248.33    2223  253.87
#Mann= 7 ,-1 , 0
       0     .17       0   136.1     .11       0   286.5     .17       0
   422.3     .15       0     909     .09       0   944.5     .15       0
  1582.5     .17       0
Bank Sta=909,944.5
XS Rating Curve= 0 ,0
Exp/Cntr=0.3,0.1