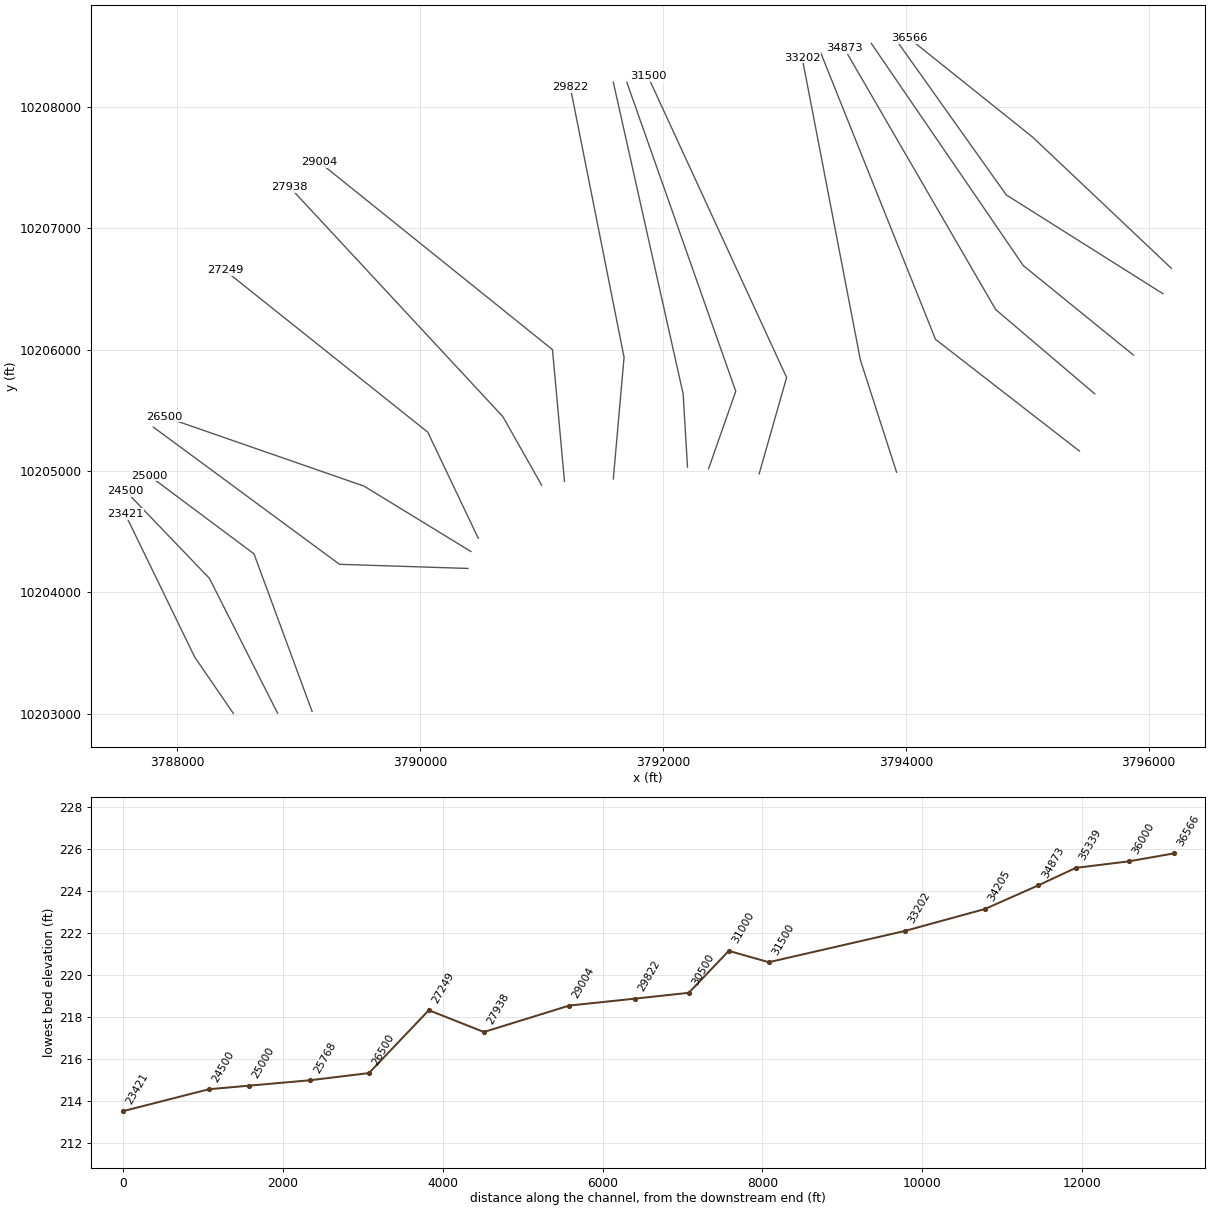
HEC-RAS study EAST SANDY CREEK.prj: EAST SANDY CREEK Base Level Engineering

--- EAST SANDY CREEK.g01 (geometry) --- (continued)

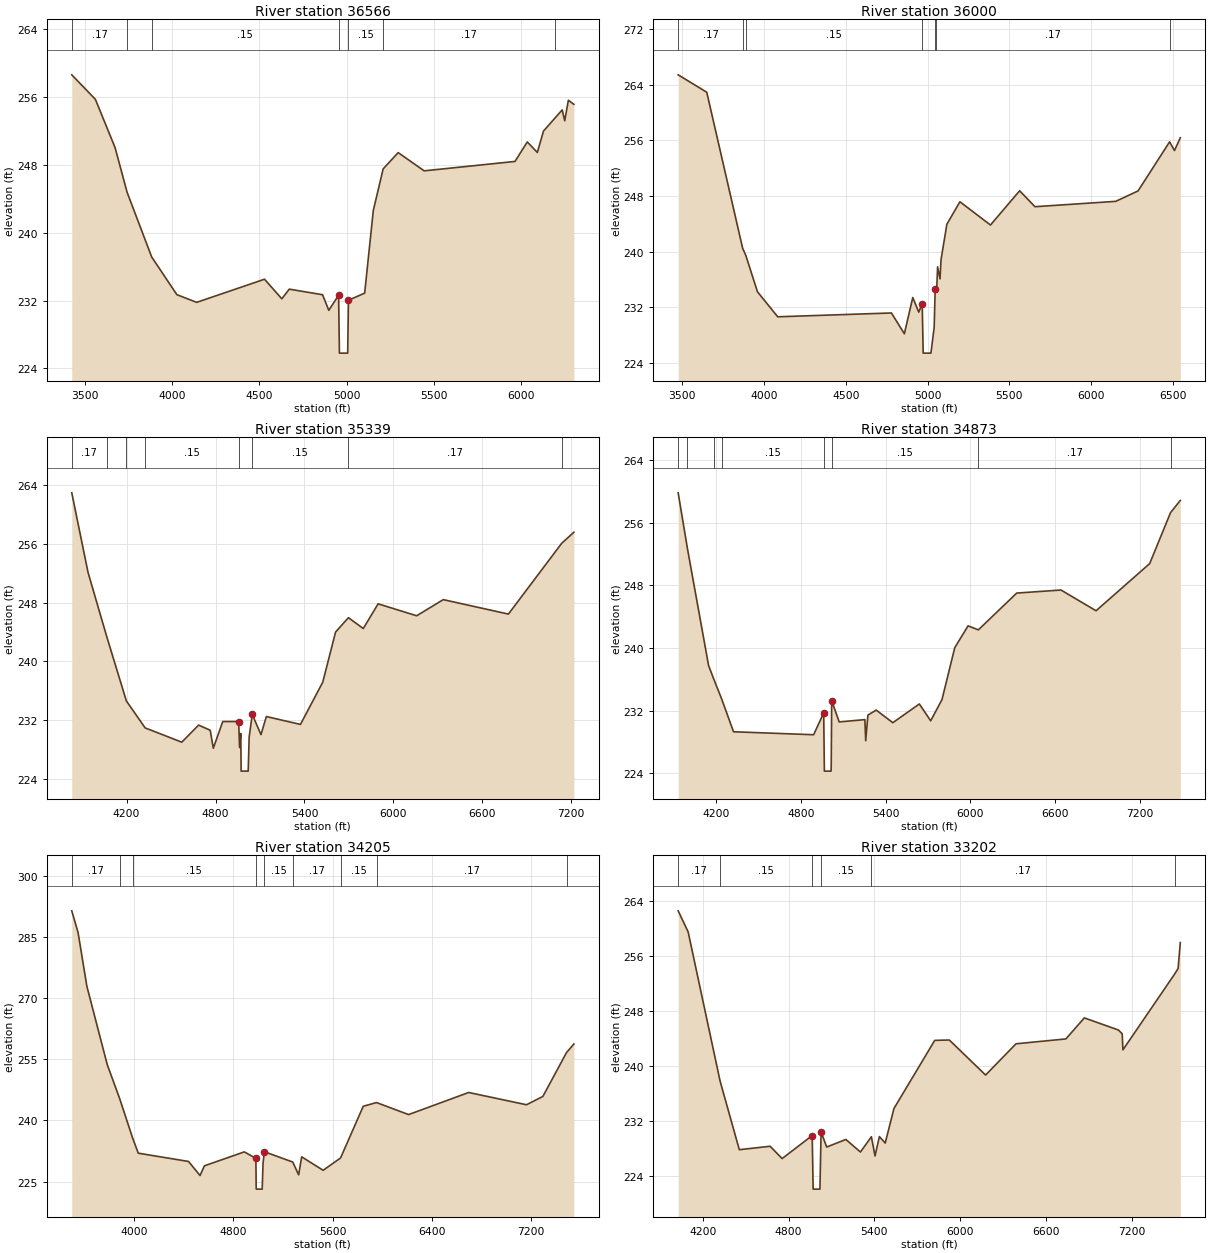
Type RM Length L Ch R = 1 ,36566   ,566,566,566
BEGIN DESCRIPTION:
EAST SANDY CREEK 69.0
END DESCRIPTION:
XS GIS Cut Line= 3
      3796187.95      10206670.2      3795044.15     10207752.36
      3794028.22     10208566.03
#Sta/Elev= 30
  3425.4  258.64  3560.6  255.75  3673.5  250.05  3742.3  244.78  3883.3  237.14
  4027.4   232.7  4140.7  231.79  4529.5  234.52  4628.6  232.21  4671.1  233.35
    4862  232.69  4897.6  230.85  4953.8  232.63  4958.5   225.8  5005.9   225.8
  5010.2  232.04    5103  232.88  5152.7  242.65  5209.1  247.54  5295.1  249.46
    5444  247.31  5964.1  248.42  6034.6  250.72  6092.2  249.48  6127.4     252
  6194.9  253.58  6234.6   254.5    6249  253.22  6269.9  255.64  6301.6  255.16
#Mann= 7 ,-1 , 0
  3425.4     .17       0  3742.3     .11       0  3883.3     .15       0
  4953.8     .09       0  5010.2     .15       0  5209.1     .17       0
  6194.9     .11       0
Bank Sta=4953.8,5010.2
XS Rating Curve= 0 ,0
Exp/Cntr=0.3,0.1

Type RM Length L Ch R = 1 ,36000   ,661,661,661
BEGIN DESCRIPTION:
EAST SANDY CREEK 68.0
END DESCRIPTION:
XS GIS Cut Line= 3
      3796117.88     10206461.05      3794827.98     10207275.12
       3793932.7     10208535.88
#Sta/Elev= 30
  3474.7  265.41  3649.5  262.91  3869.1  240.49  3888.2  239.48  3959.6  234.24
  4083.7  230.64  4779.2  231.19  4858.3   228.2  4909.8  233.41  4946.3  231.31
  4967.5  232.52  4973.4  225.42  5020.8  225.42  5040.7  229.12  5046.8  234.61
  5051.1   234.4  5055.5  234.19  5061.6  237.82  5076.4  236.09  5082.5  238.82
  5118.2  243.93  5198.1  247.17  5385.1  243.83  5563.5  248.75  5657.3  246.46
  6151.4  247.23    6288  248.73  6480.9  255.78  6510.6  254.53  6546.3  256.37
#Mann= 7 ,-1 , 0
  3474.7     .17       0  3869.1     .11       0  3888.2     .15       0
  4967.5     .09       0  5046.8     .15       0  5051.1     .17       0
  6480.9     .11       0
Bank Sta=4967.5,5046.8
XS Rating Curve= 0 ,0
Exp/Cntr=0.3,0.1

Type RM Length L Ch R = 1 ,35339   ,466,466,466
BEGIN DESCRIPTION:
EAST SANDY CREEK 67.0
END DESCRIPTION:
XS GIS Cut Line= 3
      3795875.46     10205954.91      3794967.64     10206692.99
      3793715.78     10208524.31
#Sta/Elev= 30
    3830  262.89  3939.6   252.1  4066.9  243.31  4198.2  234.65  4325.1  230.98
  4572.4  229.04  4685.9  231.36  4764.2  230.66    4785  228.22  4848.9  231.84
    4956  231.84  4962.4  228.31  4970.3  230.22  4972.9  225.11  5020.4  225.11
  5027.1  229.76  5048.1   232.8  5106.7  230.06    5143  232.52  5373.2  231.45
  5523.5  237.18  5610.2  243.99  5696.9  245.94  5797.1  244.47  5897.3  247.82
  6157.4   246.2  6336.8  248.39  6776.4  246.43  7136.8  256.06  7218.3  257.54
#Mann= 8 ,-1 , 0
    3830     .17       0  4066.9     .15       0  4198.2     .11       0
  4325.1     .15       0    4956     .09       0  5048.1     .15       0
  5696.9     .17       0  7136.8     .11       0
Bank Sta=4956,5048.1
XS Rating Curve= 0 ,0
Exp/Cntr=0.3,0.1

Type RM Length L Ch R = 1 ,34873   ,668,668,668
BEGIN DESCRIPTION:
EAST SANDY CREEK 66.0
END DESCRIPTION:
XS GIS Cut Line= 3
      3795556.01     10205635.47      3794740.43     10206330.41
      3793493.52      10208482.7
#Sta/Elev= 30
  3928.5  259.84  3994.4  252.69  4144.1  237.77  4180.4  236.06  4237.8  233.45
  4320.8  229.31  4888.5  228.93  4959.9  231.72  4964.7  224.28  5012.2  224.28
  5013.2  224.78  5016.6  233.28  5069.6  230.57  5251.9  230.86  5257.6  228.16
  5273.4  231.44  5332.2  232.08  5449.8  230.47  5637.8  232.86  5718.2  230.71
  5798.5  233.43  5888.9  240.06  5983.1  242.84  6056.2  242.33  6327.9  247.03
  6641.9  247.42  6890.3  244.77  7270.5   250.8  7418.2  257.31  7487.4  258.87
#Mann= 8 ,-1 , 0
  3928.5     .17       0  3994.4     .15       0  4180.4     .11       0
  4237.8     .15       0  4959.9     .09       0  5016.6     .15       0
  6056.2     .17       0  7418.2     .11       0
#XS Ineff= 2 , 0
       0                  5888.9       0  240.06
Permanent Ineff=
       F       F
Bank Sta=4959.9,5016.6
XS Rating Curve= 0 ,0
Exp/Cntr=0.3,0.1

Type RM Length L Ch R = 1 ,34205   ,1003,1003,1003
BEGIN DESCRIPTION:
EAST SANDY CREEK 65.0
END DESCRIPTION:
XS GIS Cut Line= 3
      3795431.04     10205163.22      3794244.81     10206084.57
      3793299.46     10208447.04
#Sta/Elev= 30
    3498  291.43  3548.9  286.09  3619.5  272.95  3783.4  253.75  3883.8  245.38
  3988.2  235.71  4033.8  231.97    4439  229.94  4531.8  226.49  4567.1  228.87
  4888.4  232.29  4981.7   230.7  4984.1  223.65  4985.1  223.15  5032.6  223.15
  5039.3  229.41  5050.1  232.32  5278.7   229.8  5326.5  226.65  5350.7  231.07
    5524  227.77  5664.3   230.8  5847.1  243.48  5953.9  244.39  6212.2  241.44
  6696.8  246.86  7162.6  243.85  7294.5  245.89  7485.8  256.68  7544.6  258.76
#Mann= 9 ,-1 , 0
    3498     .17       0  3883.8     .11       0  3988.2     .15       0
  4981.7     .09       0  5050.1     .15       0  5278.7     .17       0
  5664.3     .15       0  5953.9     .17       0  7485.8     .11       0
Bank Sta=4981.7,5050.1
XS Rating Curve= 0 ,0
Exp/Cntr=0.3,0.1

Type RM Length L Ch R = 1 ,33202   ,1702,1702,1702
BEGIN DESCRIPTION:
EAST SANDY CREEK 63.0
END DESCRIPTION:
XS GIS Cut Line= 3
       3793924.1     10204989.59      3793626.17     10205913.75
      3793146.34     10208406.18
#Sta/Elev= 30
    4029  262.62  4098.6  259.56    4322  237.83  4456.4  227.84  4671.5  228.34
  4755.5  226.55  4965.7   229.9  4972.2   222.1  5019.7   222.1  5027.8  230.43
    5067  228.23  5200.9  229.33  5302.8   227.5  5379.2  229.73  5404.6  226.93
  5435.2  229.75  5475.9  228.81    5537  233.84  5822.1  243.76    5924  243.81
  6177.4  238.71  6390.1  243.26  6738.7  243.97  6867.5  247.03  7105.3  245.27
  7132.1  244.71  7137.2  242.38  7499.2  253.43  7522.8  254.23  7538.2     258
#Mann= 6 ,-1 , 0
    4029     .17       0    4322     .15       0  4965.7     .09       0
  5027.8     .15       0  5379.2     .17       0  7499.2     .11       0
Bank Sta=4965.7,5027.8
XS Rating Curve= 0 ,0
Exp/Cntr=0.3,0.1

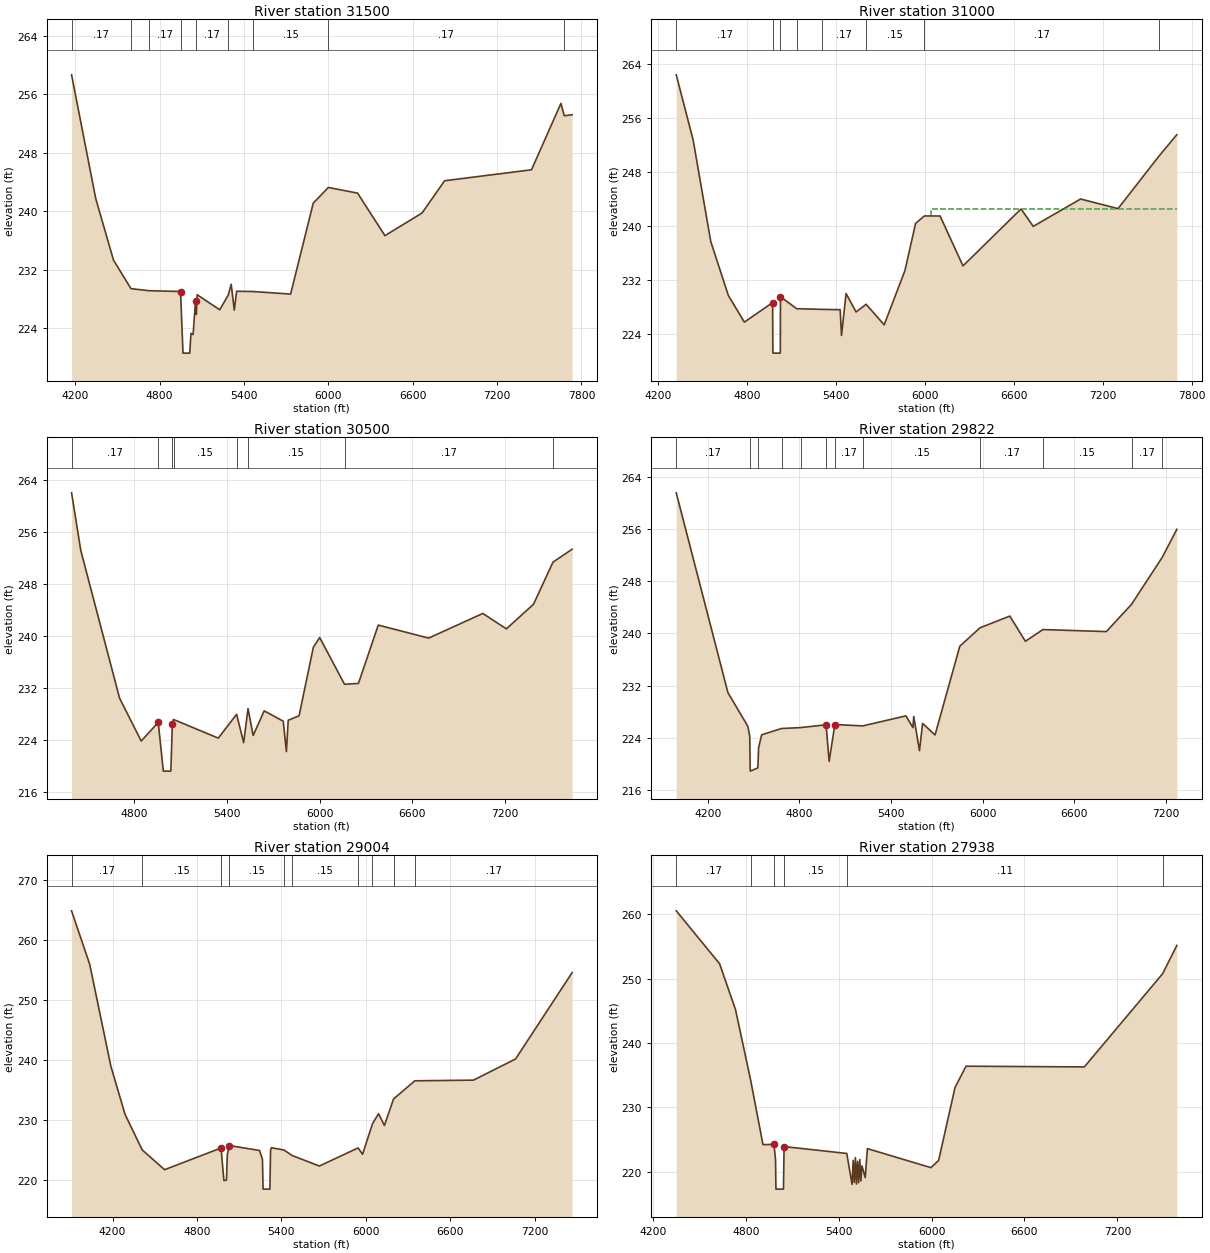
Type RM Length L Ch R = 1 ,31500   ,500,500,500
BEGIN DESCRIPTION:
EAST SANDY CREEK 60.0
END DESCRIPTION:
XS GIS Cut Line= 3
      3792792.16     10204975.76      3793018.32     10205770.19
      3791875.47     10208253.54
#Sta/Elev= 30
    4174  258.68  4345.9  241.75  4472.3  233.33  4596.4  229.43  4724.9  229.15
  4948.9  229.04  4966.5  220.61  5014.5  220.61    5023   223.3  5038.3  223.15
  5055.7  227.79  5061.2  225.91    5067   228.6  5227.5  226.54  5287.9  228.53
  5309.2  230.03  5331.2  226.49  5347.8  229.07  5461.7  229.04  5731.8  228.69
  5892.6  241.12  5999.8  243.27  6207.7   242.5  6402.5  236.68  6666.1  239.77
  6826.9  244.19  7444.8  245.69  7653.9  254.77  7677.8  253.08  7733.7  253.22
#Mann= 9 ,-1 , 0
    4174     .17       0  4596.4     .15       0  4724.9     .17       0
  4948.9     .09       0  5055.7     .17       0  5287.9     .17       0
  5461.7     .15       0  5999.8     .17       0  7677.8     .11       0
Bank Sta=4948.9,5055.7
XS Rating Curve= 0 ,0
Exp/Cntr=0.3,0.1

Type RM Length L Ch R = 1 ,31000   ,500,500,500
BEGIN DESCRIPTION:
EAST SANDY CREEK 59.0
END DESCRIPTION:
XS GIS Cut Line= 3
      3792375.47     10205017.35       3792599.4     10205656.88
      3791702.36     10208203.51
#Sta/Elev= 30
  4322.4  262.36  4436.5   252.7  4555.3  237.68  4674.1  229.68  4781.9  225.74
  4972.7  228.63  4974.3  221.65  4975.3  221.15  5023.8  221.15  5024.8  221.65
  5025.6  229.51  5134.4  227.73  5307.7  227.63  5428.5  227.58  5437.5  223.77
  5468.4  229.98  5535.6  227.24  5603.6  228.38  5725.4  225.34  5865.5  233.37
  5937.4  240.36  5996.6  241.46  6102.5  241.46  6257.3  234.07  6649.1   242.5
  6731.3  239.92  7050.7  243.97  7303.5  242.55  7578.4  250.29    7700  253.49
#Mann= 8 ,-1 , 0
  4322.4     .17       0  4972.7     .09       0  5025.6     .17       0
  5134.4     .15       0  5307.7     .17       0  5603.6     .15       0
  5996.6     .17       0  7578.4     .11       0
#XS Ineff= 2 , 0
       0                  6040.6       0  242.43
Permanent Ineff=
       F       F
Bank Sta=4972.7,5025.6
XS Rating Curve= 0 ,0
Exp/Cntr=0.3,0.1

Type RM Length L Ch R = 1 ,30500   ,678,678,678
BEGIN DESCRIPTION:
EAST SANDY CREEK 58.0
END DESCRIPTION:
XS GIS Cut Line= 3
      3792201.88     10205031.24      3792166.19     10205634.49
      3791590.77     10208204.86
#Sta/Elev= 30
  4395.7  261.99  4455.6  253.09  4706.1  230.39  4846.3  223.78  4956.5  226.66
  4989.3  219.15  5037.8  219.15  5047.7  226.35  5055.2   227.1  5344.9  224.23
  5463.4   227.9  5508.9  223.54  5537.3  228.78  5570.4  224.64  5642.1  228.43
  5765.1  226.83  5785.6  222.16  5797.2  226.98  5867.5  227.67  5959.8  238.22
  6000.8  239.72  6161.5  232.52  6251.5  232.65  6379.9  241.63  6705.8  239.63
  7056.3  243.42  7208.7  241.05  7384.2  244.84  7510.2  251.32    7634  253.31
#Mann= 8 ,-1 , 0
  4395.7     .17       0  4956.5     .09       0  5047.7     .17       0
  5055.2     .15       0  5463.4     .17       0  5537.3     .15       0
  6161.5     .17       0  7510.2     .11       0
#XS Ineff= 2 , 0
       0                  6000.8       0  239.72
Permanent Ineff=
       F       F
Bank Sta=4956.5,5047.7
XS Rating Curve= 0 ,0
Exp/Cntr=0.3,0.1

Type RM Length L Ch R = 1 ,29822   ,818,818,818
BEGIN DESCRIPTION:
EAST SANDY CREEK 56.0
END DESCRIPTION:
XS GIS Cut Line= 3
      3791590.76     10204934.05      3791679.35     10205936.84
      3791236.59     10208163.24
#Sta/Elev= 30
  3993.3  261.57  4331.6  230.91  4462.1  225.75  4474.4  224.22  4477.1  219.37
  4478.1  218.87  4527.6  219.37  4532.4  222.46  4552.5  224.44  4682.6  225.41
  4808.5  225.55  4974.1  225.98  4994.2  220.38  5031.6  226.02  5214.1  225.81
  5496.8  227.35  5542.8  225.55  5547.9  227.26  5585.5  222.01  5605.9  226.19
  5687.4  224.42  5849.6  238.04  5981.9  240.86  6176.8  242.66  6278.8  238.79
  6393.5  240.59    6809  240.28  6974.2  244.48  7176.2  251.73    7270  255.97
#Mann= 12 ,-1 , 0
  3993.3     .17       0  4477.1     .12       0  4527.6     .17       0
  4682.6     .15       0  4808.5     .17       0  4974.1     .09       0
  5031.6     .17       0  5214.1     .15       0  5981.9     .17       0
  6393.5     .15       0  6974.2     .17       0  7176.2     .11       0
Bank Sta=4974.1,5031.6
XS Rating Curve= 0 ,0
Exp/Cntr=0.3,0.1

Type RM Length L Ch R = 1 ,29004   ,1066,1066,1066
BEGIN DESCRIPTION:
EAST SANDY CREEK 54.0
END DESCRIPTION:
XS GIS Cut Line= 3
      3791188.59     10204912.49      3791089.76      10205999.8
      3789167.71     10207546.67
#Sta/Elev= 30
  3908.2  264.94  4037.3  256.01  4187.7  239.03  4288.3  231.01  4410.4  225.08
  4569.5  221.78  4971.1   225.4  4991.2  219.97  5009.4  220.04  5015.8  224.34
  5030.2  225.81  5244.6  224.98  5265.4  223.51  5269.9  218.54  5318.4  218.54
    5323  225.05  5329.4  225.44  5417.9  225.07  5475.9  224.15  5670.1  222.39
  5945.4  225.41  5977.3  224.35  6047.8  229.44  6090.8  231.12  6132.5  229.15
  6197.4  233.57  6348.7   236.6  6765.9  236.71  7065.1  240.24  7467.2  254.64
#Mann= 10 ,-1 , 0
  3908.2     .17       0  4410.4     .15       0  4971.1     .09       0
  5030.2     .15       0  5417.9     .11       0  5475.9     .15       0
  5945.4     .11       0  6047.8     .17       0  6197.4     .15       0
  6348.7     .17       0
#XS Ineff= 2 , 0
       0                  6090.8       0  231.12
Permanent Ineff=
       F       F
Bank Sta=4971.1,5030.2
XS Rating Curve= 0 ,0
Exp/Cntr=0.3,0.1

Type RM Length L Ch R = 1 ,27938   ,689,689,689
BEGIN DESCRIPTION:
EAST SANDY CREEK 53.0
END DESCRIPTION:
XS GIS Cut Line= 3
       3791000.4     10204882.12      3790681.49     10205447.02
      3788924.13     10207340.87
#Sta/Elev= 30
  4351.3  260.57  4631.3  252.34  4733.8  245.22    4831  234.32  4911.5   224.2
  4982.2  224.24  4992.3  221.91    4995  217.28  5043.6  217.28  5047.7   223.9
  5452.4  222.83  5486.5  218.03  5493.8  221.75  5500.7  218.31    5508  222.18
  5514.8  218.07  5522.2   221.6    5529  218.28  5536.4  221.89  5543.2  218.54
  5550.5   220.9  5571.5  219.09  5585.7  223.58  5996.1  220.62  6045.5  221.74
  6151.5  233.09  6222.4   236.4  6986.6  236.29  7491.7  250.78  7583.6  255.18
#Mann= 6 ,-1 , 0
  4351.3     .17       0    4831     .15       0  4982.2     .09       0
  5047.7     .15       0  5452.4     .11       0  7491.7     .17       0
Bank Sta=4982.2,5047.7
XS Rating Curve= 0 ,0
Exp/Cntr=0.3,0.1

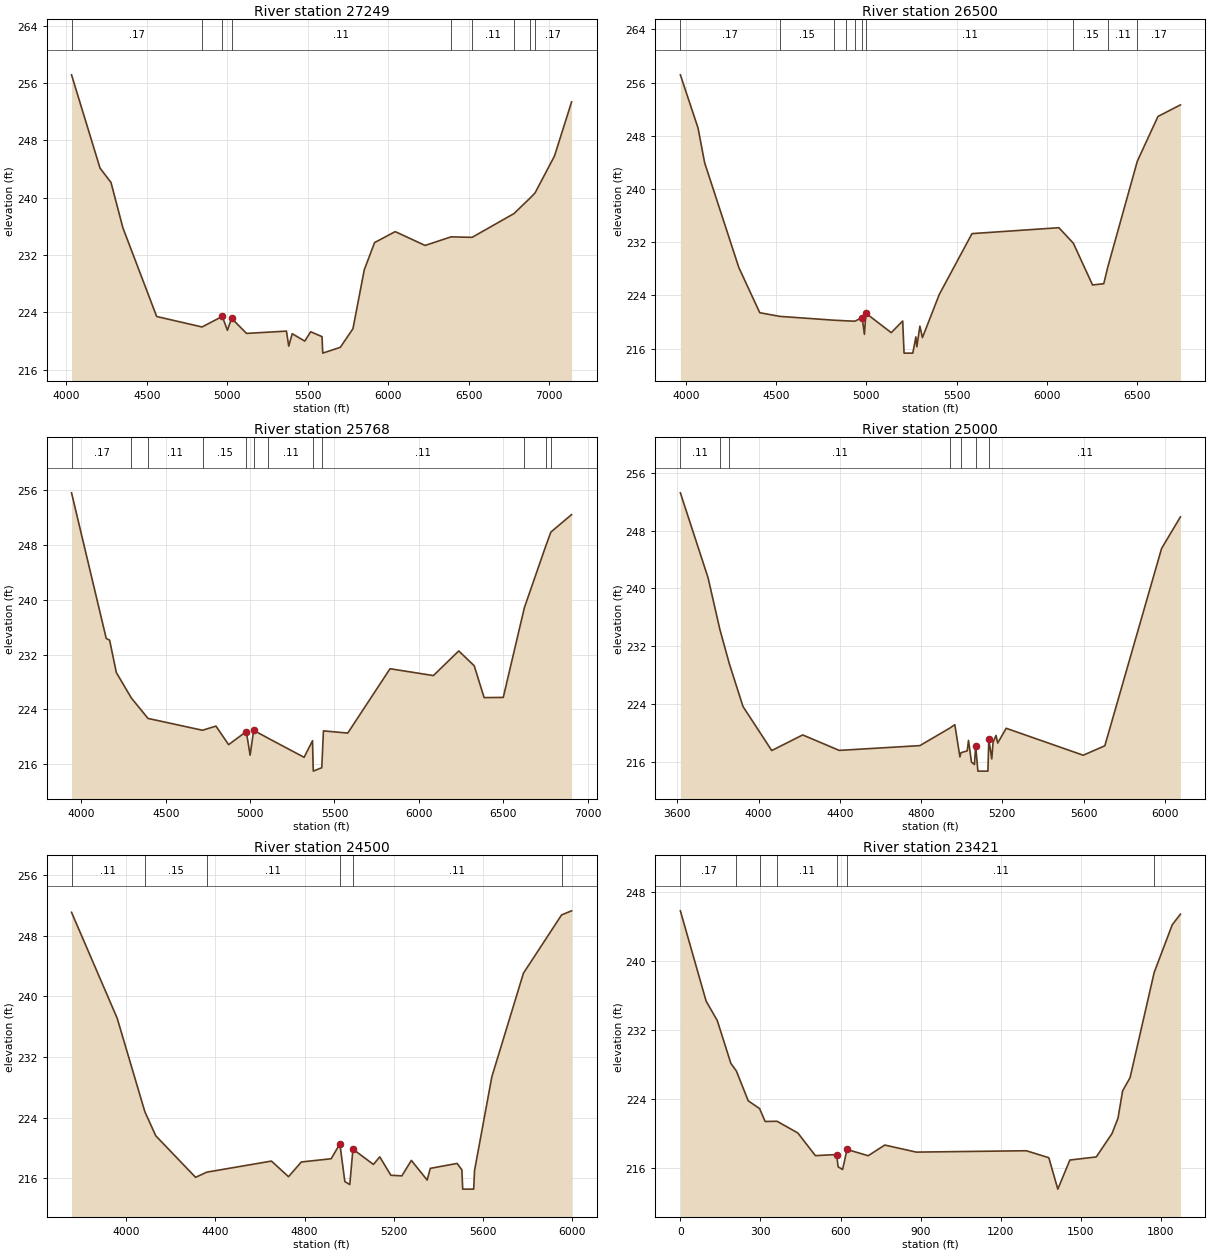
Type RM Length L Ch R = 1 ,27249   ,749,749,749
BEGIN DESCRIPTION:
EAST SANDY CREEK 51.0
END DESCRIPTION:
XS GIS Cut Line= 3
       3790478.3     10204445.01      3790062.47     10205319.58
      3788391.38     10206653.66
#Sta/Elev= 30
  4031.6  257.14  4208.6  244.13  4276.8  242.12  4350.5  235.81  4560.5  223.43
  4842.4  221.97  4968.4  223.44    5000   221.5  5025.8  223.18  5118.6  221.07
  5366.8  221.39  5381.2  219.29  5402.6  221.03  5480.5     220  5517.3   221.3
  5587.8  220.62  5592.3  218.32  5701.5  219.13  5779.9  221.72  5850.4  229.95
  5914.4  233.74  6042.5  235.27  6228.2  233.34  6389.9  234.54  6520.2  234.47
  6780.8  237.79  6882.3  239.99  6911.1  240.66    7032  245.81  7138.3  253.36
#Mann= 9 ,-1 , 0
  4031.6     .17       0  4842.4     .15       0  4968.4     .06       0
  5025.8     .11       0  6389.9     .17       0  6520.2     .11       0
  6780.8     .15       0  6882.3     .11       0  6911.1     .17       0
Bank Sta=4968.4,5025.8
XS Rating Curve= 0 ,0
Exp/Cntr=0.3,0.1

Type RM Length L Ch R = 1 ,26500   ,732,732,732
BEGIN DESCRIPTION:
EAST SANDY CREEK 50.0
END DESCRIPTION:
XS GIS Cut Line= 3
      3790417.61     10204335.73      3789538.03     10204874.55
      3787893.37     10205446.28
#Sta/Elev= 30
  3968.5  257.17  4066.4  249.18  4103.1  243.95  4292.7  228.19  4408.7   221.4
  4518.6  220.85  4820.4  220.27  4886.8  220.18  4935.7  220.12  4976.8  220.67
  4989.1  218.14  4997.2  221.32  5137.8   218.4  5201.3  220.15  5208.8  215.32
  5257.4  215.32  5274.4  217.76  5279.7  216.27  5296.6  219.38  5310.8  217.65
  5404.2  224.15  5585.5  233.29  6067.4  234.18  6147.7  231.84    6254  225.57
  6316.2  225.76  6338.6  228.27  6502.1  244.17  6616.7  250.91  6741.2  252.65
#Mann= 10 ,-1 , 0
  3968.5     .17       0  4518.6     .15       0  4820.4     .11       0
  4886.8     .15       0  4935.7     .11       0  4976.8     .06       0
  4997.2     .11       0  6147.7     .15       0  6338.6     .11       0
  6502.1     .17       0
#XS Ineff= 2 , 0
       0                  5585.5       0  233.29
Permanent Ineff=
       F       F
Bank Sta=4976.8,4997.2
XS Rating Curve= 0 ,0
Exp/Cntr=0.3,0.1

Type RM Length L Ch R = 1 ,25768   ,768,768,768
BEGIN DESCRIPTION:
EAST SANDY CREEK 49.0
END DESCRIPTION:
XS GIS Cut Line= 3
      3790393.33     10204196.12      3789335.48     10204230.17
      3787801.96     10205361.04
#Sta/Elev= 30
  3941.6  255.64  4147.2  234.37  4167.2  234.12  4207.2  229.38    4296  225.67
  4394.8  222.68    4718  220.95  4797.5  221.56  4872.6  218.85  4977.6  220.76
    5000  217.31  5021.2  220.94  5106.1   219.8  5320.1     217  5369.9  219.43
  5373.7  215.48  5374.7  214.98  5424.7  215.48  5434.7  220.86  5578.8  220.54
  5829.4  229.94  6086.3  228.94  6236.6  232.54  6328.4  230.37    6387  225.72
  6500.5  225.75  6625.6  238.86  6751.8  247.83  6782.8  249.91  6905.4  252.46
#Mann= 12 ,-1 , 0
  3941.6     .17       0    4296     .15       0  4394.8     .11       0
    4718     .15       0  4977.6     .09       0  5021.2     .15       0
  5106.1     .11       0  5373.7     .12       0  5424.7     .11       0
  6625.6     .17       0  6751.8     .11       0  6782.8     .17       0
#XS Ineff= 2 , 0
       0                  5829.4       0  229.94
Permanent Ineff=
       F       F
Bank Sta=4977.6,5021.2
XS Rating Curve= 0 ,0
Exp/Cntr=0.3,0.1

Type RM Length L Ch R = 1 ,25000   ,500,500,500
BEGIN DESCRIPTION:
EAST SANDY CREEK 47.0
END DESCRIPTION:
XS GIS Cut Line= 3
      3789109.63     10203017.19       3788630.8     10204316.78
      3787767.88     10204961.05
#Sta/Elev= 30
    3615  253.24  3751.3  241.49  3809.5  234.33  3855.6  229.63  3923.4  223.66
  4064.9  217.57  4217.2  219.73  4397.1  217.59  4794.2  218.25  4941.8  220.68
  4966.2  221.15  4991.3  216.69  4996.6  217.27  5027.3  217.52  5033.6  218.97
  5048.2  215.97  5062.8  215.64    5069  218.21  5079.8  214.72  5129.1  214.72
  5133.6  219.12  5148.2  216.41  5154.5  218.71  5169.1  219.66  5177.4  218.61
  5219.1  220.65  5598.5  216.92  5704.8  218.23  5984.2  245.54  6076.9  249.91
#Mann= 7 ,-1 , 0
    3615     .11       0  3809.5     .15       0  3855.6     .11       0
  4941.8     .15       0  4996.6     .11       0    5069     .06       0
  5133.6     .11       0
Bank Sta=5069,5133.6
XS Rating Curve= 0 ,0
Exp/Cntr=0.3,0.1

Type RM Length L Ch R = 1 ,24500   ,1079,1079,1079
BEGIN DESCRIPTION:
EAST SANDY CREEK 46.0
END DESCRIPTION:
XS GIS Cut Line= 3
       3788824.9     10203003.31      3788264.15     10204113.98
      3787574.92     10204833.13
#Sta/Elev= 30
  3755.8  251.07  3960.3   237.1  4084.2  224.77  4133.1  221.59  4311.4  216.11
  4361.9  216.79  4651.5  218.25  4727.9  216.19  4785.2  218.13    4919  218.56
    4958  220.52  4980.3  215.55  5002.4  215.15  5016.5  219.82  5108.4  217.81
  5136.7  218.81  5186.4  216.38  5235.7   216.3  5278.2  218.34    5349  215.75
  5363.1  217.29  5483.2  217.94  5504.6   217.1  5508.3  214.55  5557.6  214.55
  5561.2  216.99  5638.9  229.38  5780.4  243.04  5951.3  250.73  5996.1  251.27
#Mann= 6 ,-1 , 0
  3755.8     .11       0  4084.2     .15       0  4361.9     .11       0
    4958     .06       0  5016.5     .11       0  5951.3     .17       0
Bank Sta=4958,5016.5
XS Rating Curve= 0 ,0
Exp/Cntr=0.3,0.1

Type RM Length L Ch R = 1 ,23421   ,552,552,552
BEGIN DESCRIPTION:
EAST SANDY CREEK 44.0
END DESCRIPTION:
XS GIS Cut Line= 3
       3788460.6     10203001.37      3788142.89     10203464.91
      3787569.97      10204644.6
#Sta/Elev= 30
       0  245.83    96.4  235.35   138.3  233.08   189.1  228.12     210  227.21
   254.2  223.76   296.7  222.86   317.7  221.36   362.4  221.38   440.2  220.02
   505.9  217.39   585.2  217.52   591.1  216.09   607.8  215.78   624.4  218.11
   703.6  217.38   765.7  218.62   884.1   217.8  1295.8  217.96  1380.4  217.15
  1414.1   213.5  1459.3  216.88  1558.2  217.24  1617.2  219.96  1639.8  221.76
  1656.8  224.91  1684.9  226.46  1775.1  238.67  1842.8  244.21  1873.4  245.44
#Mann= 7 ,-1 , 0
       0     .17       0     210     .11       0   296.7     .15       0
   362.4     .11       0   585.2     .06       0   624.4     .11       0
  1775.1     .17       0
Bank Sta=585.2,624.4
XS Rating Curve= 0 ,0
Exp/Cntr=0.3,0.1