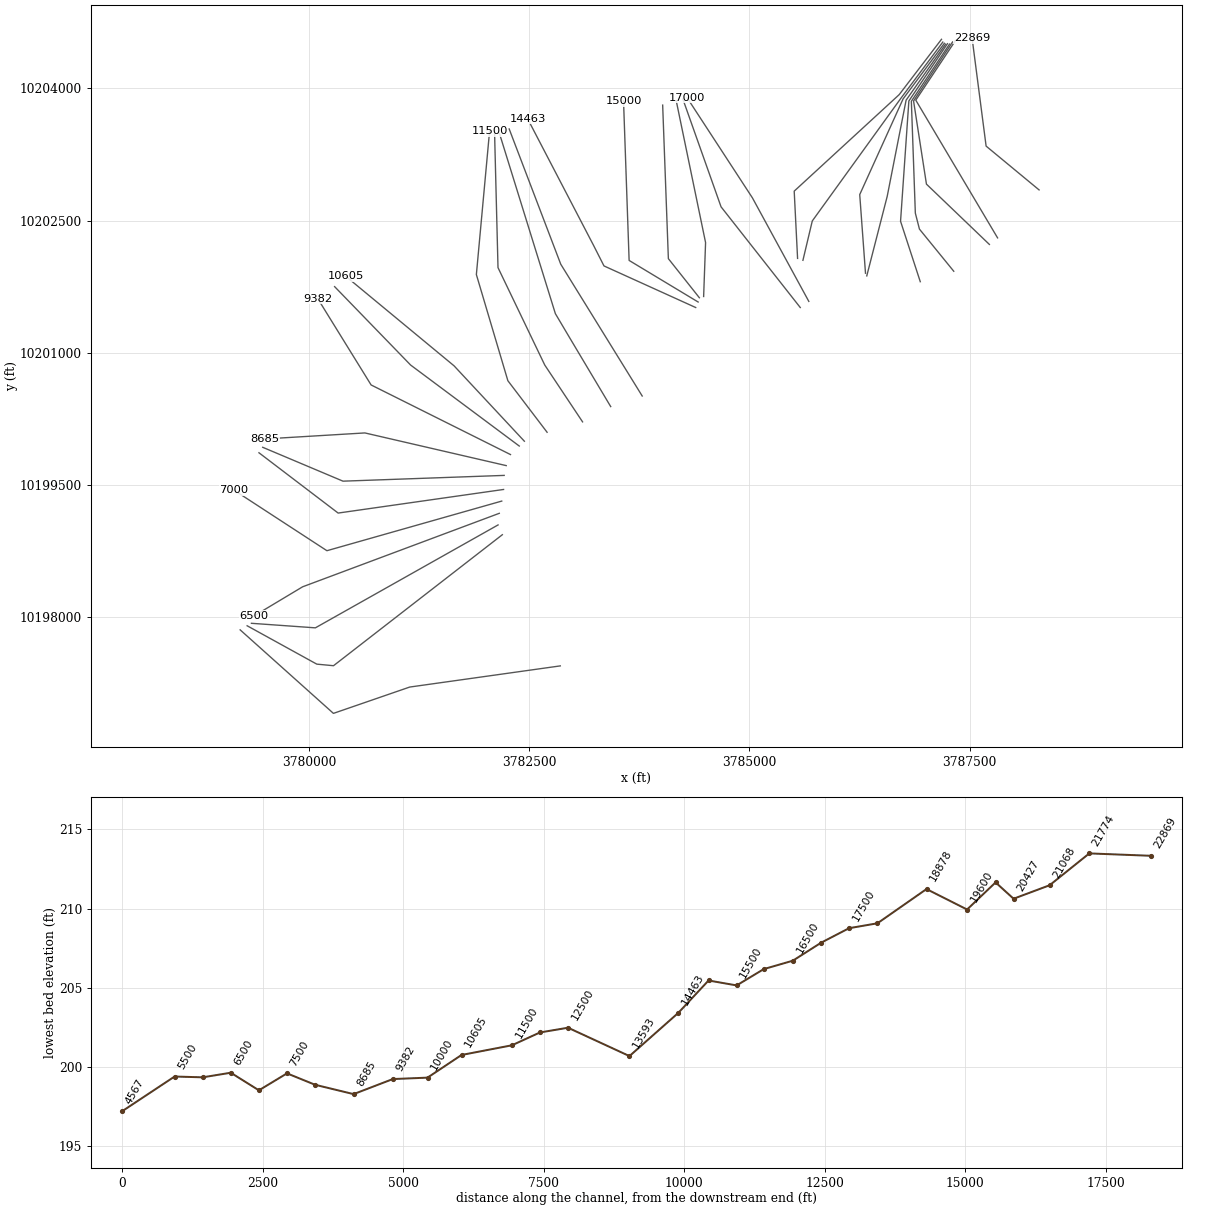
HEC-RAS study EAST SANDY CREEK.prj: EAST SANDY CREEK Base Level Engineering

--- EAST SANDY CREEK.g01 (geometry) --- (continued)

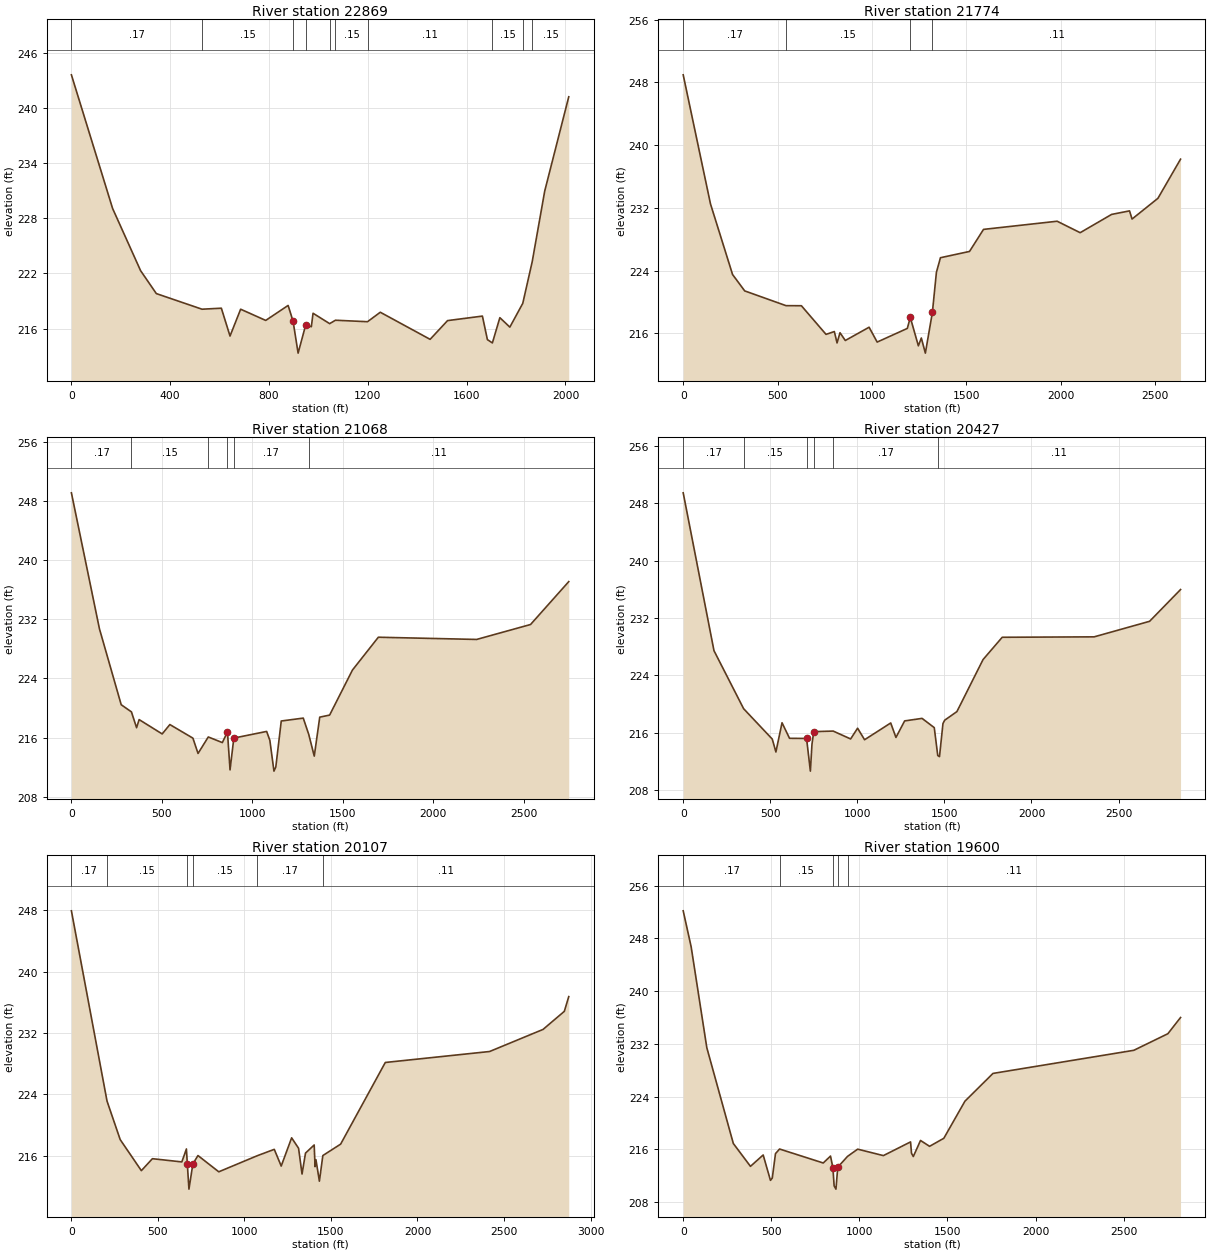
Type RM Length L Ch R = 1 ,22869   ,1095,1095,1095
BEGIN DESCRIPTION:
EAST SANDY CREEK 43.0
END DESCRIPTION:
XS GIS Cut Line= 3
      3788288.72     10202847.72      3787687.16     10203345.12
      3787528.31     10204569.08
#Sta/Elev= 30
       0  243.62   166.7  229.08     280  222.31   343.8  219.81   528.8  218.11
     607  218.22   642.1  215.19   685.1  218.11   786.6  216.89   877.3  218.52
   897.5  216.78   917.7  213.33   947.9  216.34   971.3  216.21   978.2  217.67
  1045.4  216.54  1068.9  216.91  1198.7  216.75  1250.4  217.78  1452.1  214.83
  1522.7  216.87  1663.8  217.36    1684   214.8  1704.2  214.44  1734.4  217.19
  1774.8  216.16  1827.2  218.75  1865.5   223.3    1916  230.97  2013.3  241.23
#Mann= 10 ,-1 , 0
       0     .17       0   528.8     .15       0   897.5     .09       0
   947.9     .15       0  1045.4     .11       0  1068.9     .15       0
  1198.7     .11       0  1704.2     .15       0  1827.2     .17       0
  1865.5     .15       0
Bank Sta=897.5,947.9
XS Rating Curve= 0 ,0
Exp/Cntr=0.3,0.1

Type RM Length L Ch R = 1 ,21774   ,706,706,706
BEGIN DESCRIPTION:
EAST SANDY CREEK 42.0
END DESCRIPTION:
XS GIS Cut Line= 3
      3787817.37     10202303.02      3786888.41     10203867.09
      3787339.94     10204544.77
#Sta/Elev= 30
       0  248.95   144.5   232.5   261.4   223.5   325.7  221.41   544.4  219.53
   625.8  219.52   756.3  215.87   800.3  216.23   814.7  214.78   830.3  216.08
   858.4  215.09   984.3  216.78  1027.1  214.89  1186.8  216.63  1202.5  218.03
  1245.3  214.41  1260.9  215.41  1282.3  213.48  1319.4  218.66  1340.8  223.78
  1362.2  225.64  1516.1  226.44  1590.2  229.25  1980.1  230.29    2102  228.83
  2268.5  231.16  2363.4  231.61  2376.7  230.57  2513.7  233.21  2633.5   238.2
#Mann= 4 ,-1 , 0
       0     .17       0   544.4     .15       0  1202.5     .09       0
  1319.4     .11       0
Bank Sta=1202.5,1319.4
XS Rating Curve= 0 ,0
Exp/Cntr=0.3,0.1

Type RM Length L Ch R = 1 ,21068   ,641,641,641
BEGIN DESCRIPTION:
EAST SANDY CREEK 41.0
END DESCRIPTION:
XS GIS Cut Line= 4
       3787724.4     10202228.45      3787009.56     10202913.35
       3786863.3     10203857.68      3787306.52     10204528.28
#Sta/Elev= 30
       0  249.11     155  230.71   275.2  220.45   331.8  219.48   360.1  217.34
   374.2  218.44   501.6   216.5     544  217.77   671.4  215.93   699.7  213.86
   756.3  216.09     834  215.33   862.3  216.77   876.5  211.64   897.5  215.94
  1078.8  216.84  1096.5  215.64  1119.2  211.47  1129.4  212.03  1159.6  218.25
  1281.1  218.64  1311.5  216.43  1341.9   213.5  1372.2  218.77  1426.8  219.05
  1552.9  225.14    1696  229.58  2239.1  229.28    2537   231.3  2748.1   237.1
#Mann= 6 ,-1 , 0
       0     .17       0   331.8     .15       0   756.3     .17       0
   862.3     .09       0   897.5     .17       0  1311.5     .11       0
Bank Sta=862.3,897.5
XS Rating Curve= 0 ,0
Exp/Cntr=0.3,0.1

Type RM Length L Ch R = 1 ,20427   ,320,320,320
BEGIN DESCRIPTION:
EAST SANDY CREEK 40.0
END DESCRIPTION:
XS GIS Cut Line= 5
      3787319.67     10201923.98      3786930.13      10202402.5
      3786883.47     10202583.71      3786838.19     10203854.54
      3787271.71     10204503.63
#Sta/Elev= 30
       0  249.46   176.8  227.43   347.1  219.33   511.6  215.09   532.4  213.29
   567.6  217.37   610.7   215.2   708.5  215.18   730.4  210.62   739.5  214.36
   749.8  216.13   861.5  216.21   961.6  215.11  1001.6  216.61  1041.7     215
  1191.8  217.34  1221.8  215.32  1271.8  217.63  1371.9  217.98  1441.9  216.69
  1461.9   212.8  1471.9  212.64  1491.9  217.27  1501.9  217.73    1572  218.93
  1722.1  226.19  1832.2   229.3  2360.2  229.36  2678.6  231.53  2856.3  235.96
#Mann= 6 ,-1 , 0
       0     .17       0   347.1     .15       0   708.5     .09       0
   749.8     .15       0   861.5     .17       0  1461.9     .11       0
Bank Sta=708.5,749.8
XS Rating Curve= 0 ,0
Exp/Cntr=0.3,0.1

Type RM Length L Ch R = 1 ,20107   ,507,507,507
BEGIN DESCRIPTION:
EAST SANDY CREEK 39.0
END DESCRIPTION:
XS GIS Cut Line= 4
       3786939.5     10201805.35       3786715.5     10202491.58
      3786809.95     10203857.68      3787248.05     10204508.18
#Sta/Elev= 30
       0  247.95   205.9  223.13     282  218.11   404.3  214.06   468.1  215.62
   638.1   215.2   664.7  216.89     670  214.88   679.3  211.65   701.9  214.93
   731.4  216.03   851.7  213.91  1072.2  215.99  1172.4  216.84  1212.5  214.66
  1272.7  218.34  1312.8  216.98  1332.8  213.62  1352.9  216.35    1403  217.41
  1408.2  214.58  1413.2  215.49  1433.1  212.69  1453.1  216.03  1555.9  217.52
    1814  228.17  2416.7   229.6  2725.6  232.48  2848.6  234.84  2874.2  236.76
#Mann= 6 ,-1 , 0
       0     .17       0   205.9     .15       0     670     .09       0
   701.9     .15       0  1072.2     .17       0  1453.1     .11       0
Bank Sta=670,701.9
XS Rating Curve= 0 ,0
Exp/Cntr=0.3,0.1

Type RM Length L Ch R = 1 ,19600   ,722,722,722
BEGIN DESCRIPTION:
EAST SANDY CREEK 37.0
END DESCRIPTION:
XS GIS Cut Line= 4
      3786331.87     10201871.32      3786563.93     10202774.54
      3786778.56     10203867.09      3787226.25     10204502.08
#Sta/Elev= 30
       0   252.2    45.2  246.73     134  231.42   284.5  216.87   381.8   213.4
     454  215.13   495.3  211.27   505.7  211.63   523.8  215.33     547  216.03
   794.8  213.91   836.1  214.96   849.7  213.19   856.7  210.43     867  209.94
   877.3  213.27   932.6  214.91   990.2  216.01  1136.2  215.03  1290.5  217.11
  1295.9  215.38  1306.1  214.89    1347  217.33  1398.4  216.44  1479.3  217.66
    1599  223.29  1758.3  227.51  2557.7  231.02    2751  233.54  2822.9     236
#Mann= 5 ,-1 , 0
       0     .17       0     547     .15       0   849.7     .09       0
   877.3     .15       0   932.6     .11       0
Bank Sta=849.7,877.3
XS Rating Curve= 0 ,0
Exp/Cntr=0.3,0.1

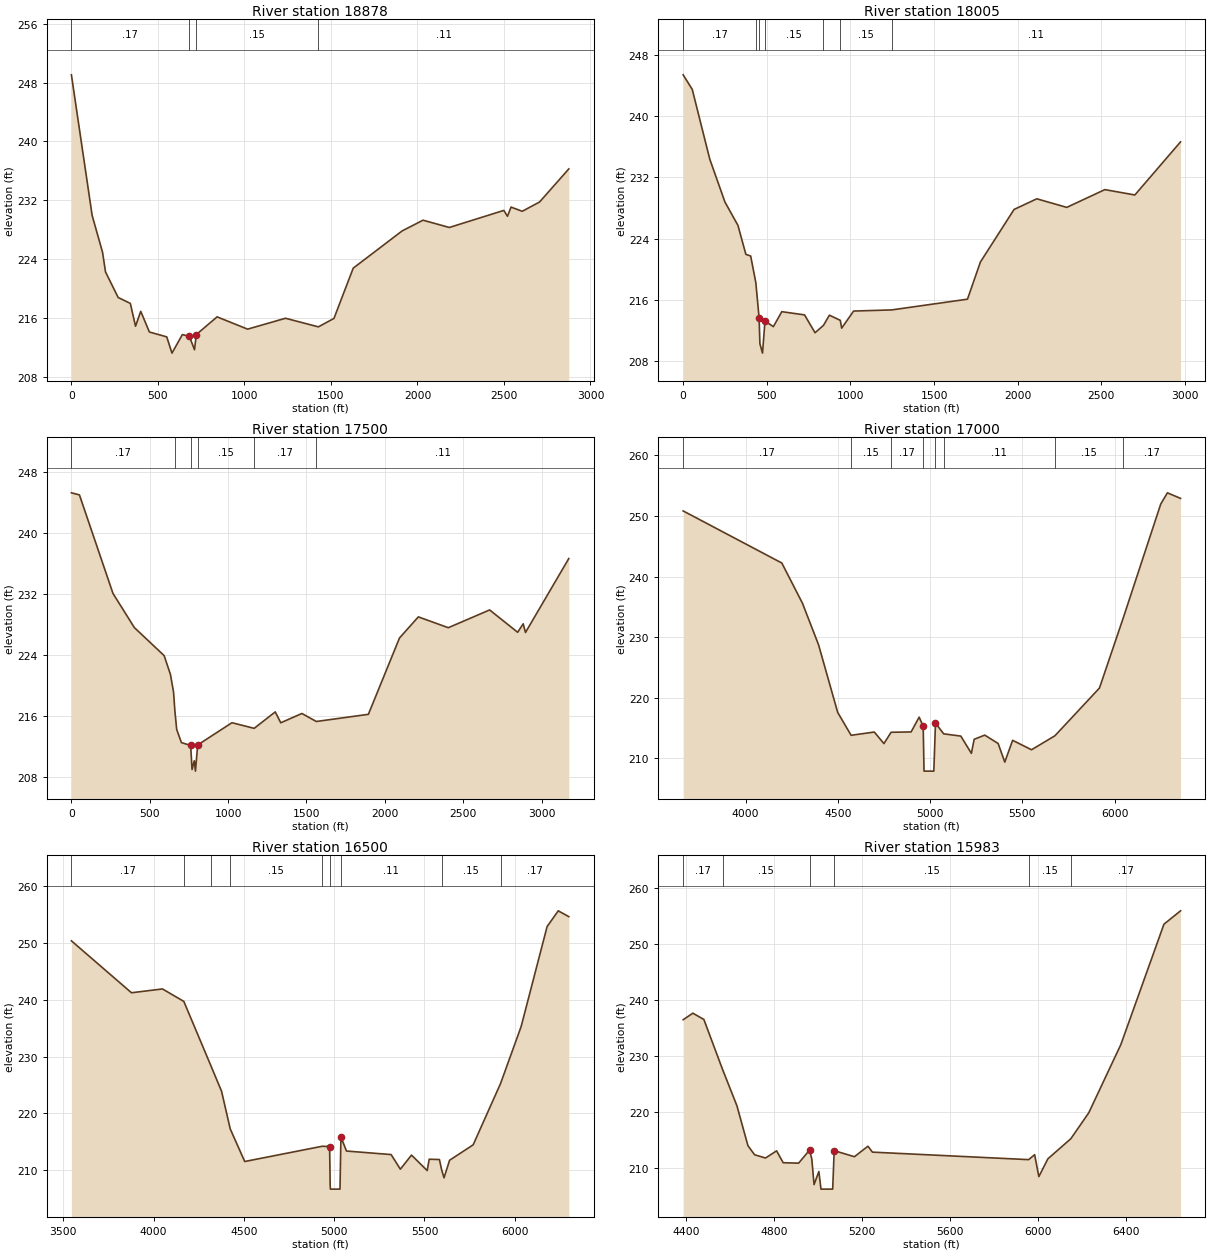
Type RM Length L Ch R = 1 ,18878   ,873,873,873
BEGIN DESCRIPTION:
EAST SANDY CREEK 36.0
END DESCRIPTION:
XS GIS Cut Line= 4
      3786317.41     10201901.46      3786251.88     10202794.52
      3786743.98     10203880.43      3787213.25     10204512.57
#Sta/Elev= 30
       0  249.06   119.9  229.94   180.1  224.93   197.1  222.27   270.3  218.79
   340.6  217.99   370.6  214.89   400.7  216.91   450.8   214.1   551.1  213.44
   581.2  211.23   641.3  213.75   681.4  213.52   711.5  211.69   721.6  213.75
   841.9  216.16  1018.4  214.49  1237.3  215.97  1427.5   214.8  1517.5  215.95
  1628.7  222.78  1911.3  227.84  2032.2   229.3  2184.2  228.31  2499.2  230.63
  2520.1  229.83  2540.9  231.08  2605.6  230.51  2705.7  231.77  2874.6  236.27
#Mann= 4 ,-1 , 0
       0     .17       0   681.4     .09       0   721.6     .15       0
  1427.5     .11       0
Bank Sta=681.4,721.6
XS Rating Curve= 0 ,0
Exp/Cntr=0.3,0.1

Type RM Length L Ch R = 1 ,18005   ,505,505,505
BEGIN DESCRIPTION:
EAST SANDY CREEK 35.0
END DESCRIPTION:
XS GIS Cut Line= 4
      3785606.85     10202048.28      3785713.14     10202495.25
      3786722.07      10203892.2      3787195.39     10204526.57
#Sta/Elev= 30
       0  245.39    54.3  243.49   158.9   234.4   249.6   228.8   327.6  225.74
   374.9  221.96   403.7  221.74   434.6  218.25   454.1  213.66   458.8   210.3
   474.4  209.07   489.1  213.25   539.4  212.53   589.7  214.48   725.7  214.06
   788.5  211.73   838.8  212.69   874.4  214.02   939.4  213.35   947.7  212.33
  1019.1  214.56  1247.3  214.71  1699.9  216.11  1777.2  220.96  1978.4  227.82
  2114.5  229.21  2293.5  228.09  2521.4  230.41  2700.7  229.71  2973.8  236.64
#Mann= 7 ,-1 , 0
       0     .17       0   434.6     .15       0   454.1     .09       0
   489.1     .15       0   838.8     .17       0   939.4     .15       0
  1247.3     .11       0
Bank Sta=454.1,489.1
XS Rating Curve= 0 ,0
Exp/Cntr=0.3,0.1

Type RM Length L Ch R = 1 ,17500   ,500,500,500
BEGIN DESCRIPTION:
EAST SANDY CREEK 34.0
END DESCRIPTION:
XS GIS Cut Line= 4
      3785546.09     10202069.98      3785507.79     10202833.84
       3786700.1     10203929.86      3787180.43     10204558.08
#Sta/Elev= 30
       0  245.26    51.2  244.99   265.4  232.06   401.6  227.59   591.8  223.91
   631.9  221.45   651.9  219.11   660.4  216.62   671.9  214.22     702   212.5
   760.9  212.13   769.9  208.97   784.1  210.12   791.5  208.76   805.7  212.19
  1024.5  215.11  1166.3  214.37  1300.8  216.53  1335.9   215.1  1470.9  216.32
  1562.8  215.27  1895.1  216.21  2093.6  226.22  2213.9  228.99    2405  227.57
  2668.9   229.9  2847.6  226.97  2882.9  228.08  2897.5  226.94  3173.9  236.64
#Mann= 6 ,-1 , 0
       0     .17       0   660.4     .15       0   760.9     .09       0
   805.7     .15       0  1166.3     .17       0  1562.8     .11       0
Bank Sta=760.9,805.7
XS Rating Curve= 0 ,0
Exp/Cntr=0.3,0.1

Type RM Length L Ch R = 1 ,17000   ,500,500,500
BEGIN DESCRIPTION:
EAST SANDY CREEK 33.0
END DESCRIPTION:
XS GIS Cut Line= 3
      3785673.67     10201581.61      3785033.64     10202756.71
      3784292.32      10203893.2
#Sta/Elev= 30
  3661.9  250.84  4196.5  242.23  4308.2  235.59  4395.6  228.71  4499.1  217.55
  4571.9  213.76  4697.5   214.3  4749.8  212.39  4788.5  214.26    4897  214.32
  4940.6  216.76  4962.5  215.25    4967  207.84  5020.1  207.84  5029.1  215.78
  5073.5     214  5166.3  213.63  5223.6  210.78  5238.7   213.1    5296  213.79
  5368.4  212.41  5404.6  209.33    5447  212.93  5549.5  211.37  5676.1  213.68
  5917.6  221.57  6046.6  233.17  6249.5  251.97  6285.7  253.83  6356.9  252.91
#Mann= 8 ,-1 , 0
  3661.9     .17       0  4571.9     .15       0  4788.5     .17       0
  4962.5     .09       0  5029.1     .17       0  5073.5     .11       0
  5676.1     .15       0  6046.6     .17       0
Bank Sta=4962.5,5029.1
XS Rating Curve= 0 ,0
Exp/Cntr=0.3,0.1

Type RM Length L Ch R = 1 ,16500   ,517,517,517
BEGIN DESCRIPTION:
EAST SANDY CREEK 32.0
END DESCRIPTION:
XS GIS Cut Line= 3
      3785576.49      10201512.1      3784676.99     10202655.75
      3784243.15     10203880.16
#Sta/Elev= 30
    3545  250.32  3877.6   241.2  4049.3  241.87  4167.5  239.68  4318.8  228.27
  4376.4   223.9  4424.5  217.28  4504.7  211.56  4933.9  214.24  4974.7  214.18
  4977.8  207.41  4979.1  206.71  5032.2  206.71  5037.3  215.86  5068.1   213.4
  5315.2  212.78  5366.4  210.21  5428.1  212.69  5514.9  209.97  5526.1  211.96
  5582.6  211.91  5594.8  210.14  5608.1   208.7    5639  211.78  5769.5  214.49
  5921.2  225.26  6035.2  235.27    6179  252.83  6240.8  255.59    6299  254.57
#Mann= 9 ,-1 , 0
    3545     .17       0  4167.5     .15       0  4318.8     .17       0
  4424.5     .15       0  4933.9     .11       0  4974.7     .06       0
  5037.3     .11       0  5594.8     .15       0  5921.2     .17       0
Bank Sta=4974.7,5037.3
XS Rating Curve= 0 ,0
Exp/Cntr=0.3,0.1

Type RM Length L Ch R = 1 ,15983   ,483,483,483
BEGIN DESCRIPTION:
EAST SANDY CREEK 31.0
END DESCRIPTION:
XS GIS Cut Line= 3
      3784479.24     10201637.15      3784501.29     10202249.76
      3784167.84     10203861.12
#Sta/Elev= 30
    4387  236.45  4430.9  237.62    4481   236.5    4566  227.56  4631.1  221.08
  4681.1  213.95  4711.1  212.33  4760.8  211.74  4811.2  213.02  4841.2   210.9
  4911.3  210.82  4961.3  213.18  4971.3  211.51  4981.3  206.99  5003.2  209.33
  5012.8  206.18  5065.9  206.18  5072.8  213.06  5164.7  211.97    5226  213.85
  5246.4  212.79  5955.6  211.45    5983  212.33  6002.1  208.42    6043  211.59
  6147.4  215.19  6228.9  219.83  6374.4  232.01  6570.1  253.52  6645.5  255.91
#Mann= 6 ,-1 , 0
    4387     .17       0    4566     .15       0  4961.3     .09       0
  5072.8     .15       0  5955.6     .15       0  6147.4     .17       0
Bank Sta=4961.3,5072.8
XS Rating Curve= 0 ,0
Exp/Cntr=0.3,0.1

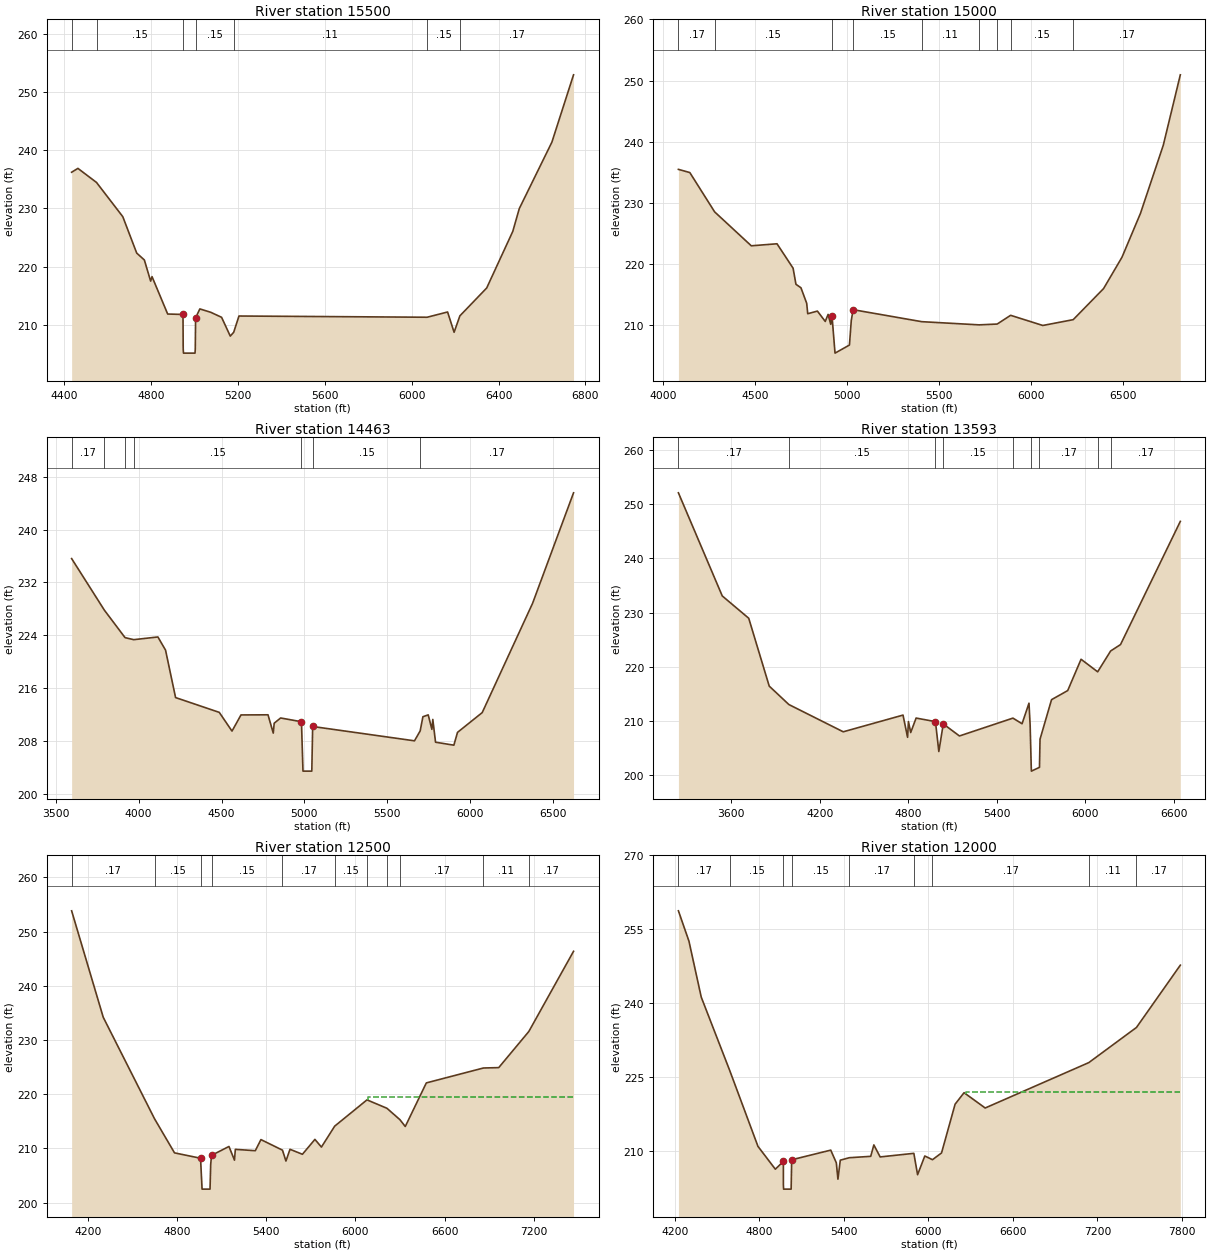
Type RM Length L Ch R = 1 ,15500   ,500,500,500
BEGIN DESCRIPTION:
EAST SANDY CREEK 30.0
END DESCRIPTION:
XS GIS Cut Line= 3
      3784430.65     10201623.23      3784078.74     10202066.92
      3784013.97     10203810.72
#Sta/Elev= 30
  4433.7   236.2  4462.6  236.86  4548.2  234.45  4669.3  228.57  4733.4  222.32
  4768.6  221.14  4797.5  217.51  4803.9  218.28    4876  211.86  4946.5  211.79
  4947.5  205.85  4948.7  205.15  5001.9  205.15  5003.1  205.85  5004.6  211.21
  5024.2  212.74  5074.2  212.16  5124.2   211.3  5164.3  208.07    5180  208.73
  5204.3  211.52  6070.7  211.31    6165  212.21    6195  208.73  6221.7  211.55
  6345.1  216.33  6465.2  226.04  6495.2  229.96  6645.3  241.36    6745  252.92
#Mann= 7 ,-1 , 0
  4433.7     .17       0  4548.2     .15       0  4946.5     .09       0
  5004.6     .15       0    5180     .11       0  6070.7     .15       0
  6221.7     .17       0
Bank Sta=4946.5,5004.6
XS Rating Curve= 0 ,0
Exp/Cntr=0.3,0.1

Type RM Length L Ch R = 1 ,15000   ,537,537,537
BEGIN DESCRIPTION:
EAST SANDY CREEK 29.0
END DESCRIPTION:
XS GIS Cut Line= 3
      3784416.74     10201574.64      3783632.99     10202046.83
      3783569.58     10203857.72
#Sta/Elev= 30
    4085  235.49  4146.9  234.97  4281.9  228.54  4480.9     223  4620.7  223.33
  4708.1  219.34  4723.6  216.71  4750.8  216.14  4781.9  213.61  4787.7   211.9
  4840.1  212.33  4882.8  210.64  4898.4  211.79  4912.6  210.17  4919.7  211.46
  4935.9  205.46  5014.2  206.78  5024.3  210.82  5034.3  212.56  5407.1   210.6
  5718.7  210.08  5816.9  210.21    5890  211.64  6064.9  209.98  6230.1  210.93
  6395.1  216.01  6495.2  221.14  6595.2  228.28  6719.4  239.43    6812  250.94
#Mann= 9 ,-1 , 0
    4085     .17       0  4281.9     .15       0  4919.7     .09       0
  5034.3     .15       0  5407.1     .11       0  5718.7     .15       0
  5816.9     .11       0    5890     .15       0  6230.1     .17       0
Bank Sta=4919.7,5034.3
XS Rating Curve= 0 ,0
Exp/Cntr=0.3,0.1

Type RM Length L Ch R = 1 ,14463   ,870,870,870
BEGIN DESCRIPTION:
EAST SANDY CREEK 28.0
END DESCRIPTION:
XS GIS Cut Line= 4
      3784388.98     10201512.13      3783347.52      10201984.4
      3783229.58     10202216.85      3782479.73     10203657.03
#Sta/Elev= 30
  3595.8  235.61  3793.3   227.8    3918  223.64  3970.4  223.33  4116.2  223.74
  4162.4  221.74  4222.9  214.56  4486.4  212.32  4563.3  209.48  4617.5  211.93
  4780.5  211.95  4812.2  209.18  4817.8  210.68  4856.8  211.47  4982.3   210.9
  4991.5  203.42  5044.7  203.42  5049.9  210.18  5664.2  208.01  5698.5  209.51
    5715  211.66    5747  211.94  5769.1  209.75  5774.7  211.25  5791.2   207.8
  5901.7  207.35  5923.8  209.29  6072.9  212.29  6376.7  228.84  6623.7  245.57
#Mann= 7 ,-1 , 0
  3595.8     .17       0  3793.3     .15       0    3918     .17       0
  3970.4     .15       0  4982.3     .09       0  5049.9     .15       0
  5698.5     .17       0
Bank Sta=4982.3,5049.9
XS Rating Curve= 0 ,0
Exp/Cntr=0.3,0.1

Type RM Length L Ch R = 1 ,13593   ,1093,1093,1093
BEGIN DESCRIPTION:
EAST SANDY CREEK 27.0
END DESCRIPTION:
XS GIS Cut Line= 3
      3783781.55      10200507.3      3782856.67     10202003.76
      3782270.93     10203539.87
#Sta/Elev= 30
  3240.8  252.14    3538  233.08  3717.6  228.95  3856.5  216.41  3989.8     213
  4358.4  207.96  4763.8  211.05  4794.6  206.94  4800.5  209.85  4815.8  207.83
  4852.5   210.5  4983.7  209.84  5006.6  204.32  5036.7  209.42  5146.3  207.19
  5509.2  210.49  5570.9  209.45  5617.9  213.25  5625.7  209.15  5633.2  201.39
  5634.4  200.69    5689  201.39  5692.8   206.6  5770.8   213.9  5880.4  215.58
    5971  221.37  6083.6  219.05  6171.4   222.9  6238.6  224.09    6644  246.86
#Mann= 9 ,-1 , 0
  3240.8     .17       0  3989.8     .15       0  4983.7     .09       0
  5036.7     .15       0  5509.2     .17       0  5633.2     .12       0
    5689     .17       0  6083.6     .11       0  6171.4     .17       0
#XS Ineff= 2 , 0
       0                    5971       0  221.37
Permanent Ineff=
       F       F
Bank Sta=4983.7,5036.7
XS Rating Curve= 0 ,0
Exp/Cntr=0.3,0.1

Type RM Length L Ch R = 1 ,12500   ,500,500,500
BEGIN DESCRIPTION:
EAST SANDY CREEK 24.0
END DESCRIPTION:
XS GIS Cut Line= 4
      3783423.71     10200387.11      3782958.96     10201166.57
      3782795.43     10201442.48       3782159.8     10203491.32
#Sta/Elev= 30
  4092.5  253.83  4304.9  234.19  4649.7  215.46    4784  209.17  4958.9  208.18
  4969.2  202.48  5022.7  202.48  5027.1  207.03  5032.9  208.71  5149.9  210.35
    5187  207.83  5192.8  209.82    5327  209.57  5364.8  211.62  5509.7  209.67
  5532.9  207.66  5560.1  209.83  5643.8  208.91  5727.6  211.66  5771.4  210.24
  5860.6   214.1  6077.6  218.95  6211.6   217.4  6298.8   215.3  6334.9  214.03
  6476.5  222.08  6860.3  224.83  6963.1   224.9  7165.3  231.56  7465.9  246.36
#Mann= 11 ,-1 , 0
  4092.5     .17       0  4649.7     .15       0  4958.9     .09       0
  5032.9     .15       0  5509.7     .17       0  5860.6     .15       0
  6077.6     .17       0  6211.6     .15       0  6298.8     .17       0
  6860.3     .11       0  7165.3     .17       0
#XS Ineff= 2 , 0
       0                  6083.6       0  219.56
Permanent Ineff=
       F       F
Bank Sta=4958.9,5032.9
XS Rating Curve= 0 ,0
Exp/Cntr=0.3,0.1

Type RM Length L Ch R = 1 ,12000   ,500,500,500
BEGIN DESCRIPTION:
EAST SANDY CREEK 23.0
END DESCRIPTION:
XS GIS Cut Line= 4
      3783104.24     10200213.53       3782674.9     10200858.98
      3782144.01     10201965.22      3782104.25     10203525.98
#Sta/Elev= 30
  4224.8  258.71  4299.7  252.54  4386.9  241.18  4589.8  226.22  4789.7  210.86
  4912.9  206.23    4970  207.81  4970.2  202.98  4971.5  202.18  5025.1  202.18
  5028.9  208.14  5306.3   210.1    5346  207.52  5357.3   204.2  5374.2  208.06
    5438  208.56  5590.2  208.84  5612.4  211.16  5657.1  208.72  5896.3  209.45
  5922.9  205.11  5974.2  208.91  6028.5  208.16    6093  209.53  6189.2  219.43
  6252.9  221.77  6402.9  218.66  7138.6  227.88    7477  235.02  7788.3  247.67
#Mann= 9 ,-1 , 0
  4224.8     .17       0  4589.8     .15       0    4970     .09       0
  5028.9     .15       0    5438     .17       0  5896.3     .15       0
  6028.5     .17       0  7138.6     .11       0    7477     .17       0
#XS Ineff= 2 , 0
       0                  6270.1       0  221.99
Permanent Ineff=
       F       F
Bank Sta=4970,5028.9
XS Rating Curve= 0 ,0
Exp/Cntr=0.3,0.1

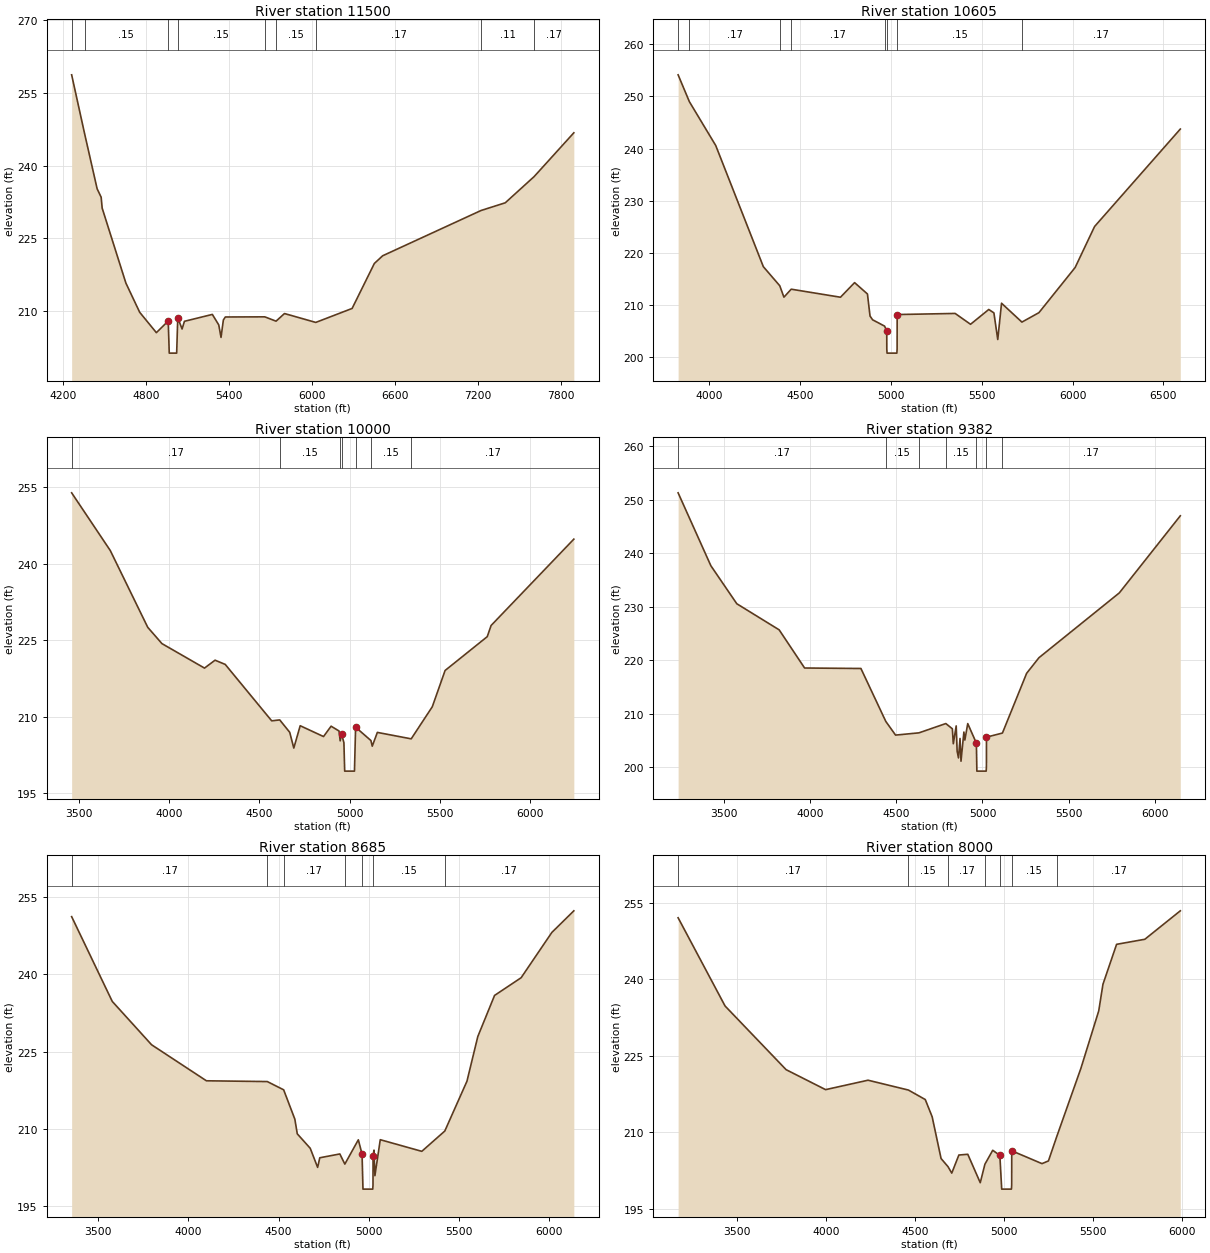
Type RM Length L Ch R = 1 ,11500   ,895,895,895
BEGIN DESCRIPTION:
EAST SANDY CREEK 22.0
END DESCRIPTION:
XS GIS Cut Line= 4
       3782701.5     10200095.43        3782256.     10200680.79
      3781898.27     10201886.38      3782048.55     10203517.53
#Sta/Elev= 30
  4264.4  258.74  4357.4   246.7  4448.7  235.24  4477.8  233.51  4485.1  231.26
  4656.6  215.81  4756.4  209.79    4877  205.59  4962.7  207.99  4970.2  201.37
  5023.8  201.37  5031.6  208.67  5062.9  206.34    5080  207.93  5281.9  209.35
  5328.2  207.18  5344.5  204.61  5361.4   208.2  5375.8  208.82  5660.9  208.85
  5742.3  207.96  5803.5  209.53  6029.7   207.7  6292.4  210.58  6453.1  219.85
  6513.3  221.44  7224.5  230.77  7399.8  232.36  7608.8  237.77  7895.6  246.79
#Mann= 9 ,-1 , 0
  4264.4     .17       0  4357.4     .15       0  4962.7     .09       0
  5031.6     .15       0  5660.9     .17       0  5742.3     .15       0
  6029.7     .17       0  7224.5     .11       0  7608.8     .17       0
Bank Sta=4962.7,5031.6
XS Rating Curve= 0 ,0
Exp/Cntr=0.3,0.1

Type RM Length L Ch R = 1 ,10605   ,605,605,605
BEGIN DESCRIPTION:
EAST SANDY CREEK 20.0
END DESCRIPTION:
XS GIS Cut Line= 3
      3782443.36     10199993.79      3781644.62     10200850.23
      3780417.34      10201865.2
#Sta/Elev= 30
  3828.9  254.13  3890.9  248.98    4036  240.57  4297.9  217.34  4388.3  213.68
  4411.2  211.49  4451.3  213.02  4722.4  211.48  4800.1  214.28  4870.9   212.1
  4885.1  207.87  4899.3  207.15  4965.2  205.94    4977  205.06  4977.4  201.56
  4978.7  200.76  5032.8  200.76  5034.1  201.56  5034.4  208.16  5353.5  208.37
  5438.2  206.29  5538.5  209.13  5566.8  208.48    5588  203.37  5608.8  210.33
  5720.9  206.71  5814.6  208.52  6013.9  217.18  6120.8  225.04  6592.6  243.73
#Mann= 8 ,-1 , 0
  3828.9     .15       0  3890.9     .17       0  4388.3     .15       0
  4451.3     .17       0  4965.2     .15       0    4977     .09       0
  5034.4     .15       0  5720.9     .17       0
Bank Sta=4977,5034.4
XS Rating Curve= 0 ,0
Exp/Cntr=0.3,0.1

Type RM Length L Ch R = 1 ,10000   ,618,618,618
BEGIN DESCRIPTION:
EAST SANDY CREEK 19.0
END DESCRIPTION:
XS GIS Cut Line= 3
      3782385.42       10199939.      3781151.78     10200858.64
      3780288.45     10201749.29
#Sta/Elev= 30
  3461.3  253.89  3675.2  242.57  3882.3  227.53  3960.9  224.33  4196.5  219.53
  4254.9  221.08  4311.2  220.25  4568.3  209.19  4612.9  209.37  4668.1  206.94
  4690.7  203.85  4726.1  208.23  4855.2  206.11  4897.1  208.14  4940.9   207.2
  4947.4  205.27    4955  206.58    4968  204.91  4972.3  199.33  5026.4  199.33
  5032.7  207.94  5117.4  205.33  5124.8  204.22  5153.1  206.92  5340.4  205.66
  5457.1  211.95  5527.9  219.06  5761.2  225.69  5782.5  227.88  6240.4  244.81
#Mann= 7 ,-1 , 0
  3461.3     .17       0  4612.9     .15       0  4947.4     .17       0
    4955     .09       0  5032.7     .17       0  5117.4     .15       0
  5340.4     .17       0
Bank Sta=4955,5032.7
XS Rating Curve= 0 ,0
Exp/Cntr=0.3,0.1

Type RM Length L Ch R = 1 ,9382    ,697,697,697
BEGIN DESCRIPTION:
EAST SANDY CREEK 18.0
END DESCRIPTION:
XS GIS Cut Line= 3
      3782285.53     10199842.39      3780702.92     10200632.76
      3780098.44     10201610.73
#Sta/Elev= 30
    3231   251.3  3421.2  237.67  3572.1  230.55  3818.2  225.67  3966.1  218.53
  4293.5  218.44  4437.9  208.55  4494.8  205.98  4630.8   206.4  4786.9  208.14
  4824.8  207.16  4830.4  204.36  4847.2   207.7  4852.7  202.97  4860.4  201.71
  4869.5  205.35  4875.1  201.09  4891.9  206.55  4897.5  205.05  4914.3  208.13
  4964.6  204.47  4967.3  199.24  5021.5  199.24  5022.8  200.04  5023.3   205.6
  5115.9  206.36  5256.6  217.54  5328.3  220.46  5795.2  232.58  6149.7     247
#Mann= 7 ,-1 , 0
    3231     .17       0  4437.9     .15       0  4630.8     .17       0
  4786.9     .15       0  4964.6     .09       0  5023.3     .15       0
  5115.9     .17       0
Bank Sta=4964.6,5023.3
XS Rating Curve= 0 ,0
Exp/Cntr=0.3,0.1

Type RM Length L Ch R = 1 ,8685    ,685,685,685
BEGIN DESCRIPTION:
EAST SANDY CREEK 17.0
END DESCRIPTION:
XS GIS Cut Line= 3
      3782237.22     10199716.76      3780632.17     10200087.87
      3779496.12     10200019.54
#Sta/Elev= 30
  3352.6  251.21  3577.8  234.75  3795.9  226.33  4100.1  219.33  4437.8  219.18
  4528.5  217.58  4590.6  211.88  4604.1  209.03    4676  206.22    4717  202.51
    4729  204.38  4840.2  205.12  4867.9  203.15  4942.7  207.87  4963.4   205.1
  4968.5  198.29  5022.8  198.29  5024.1  199.09  5024.4  204.79  5029.7  205.86
  5034.7   200.9  5064.4  207.89  5294.8  205.63  5422.3  209.57  5545.3  219.25
  5605.4  227.92  5698.4  235.91  5845.8  239.35  6016.1  248.14  6138.1  252.34
#Mann= 7 ,-1 , 0
  3352.6     .17       0  4437.8     .15       0  4528.5     .17       0
  4867.9     .15       0  4963.4     .09       0  5024.4     .15       0
  5422.3     .17       0
Bank Sta=4963.4,5024.4
XS Rating Curve= 0 ,0
Exp/Cntr=0.3,0.1

Type RM Length L Ch R = 1 ,8000    ,500,500,500
BEGIN DESCRIPTION:
EAST SANDY CREEK 16.0
END DESCRIPTION:
XS GIS Cut Line= 3
      3782214.07     10199605.58      3780383.74     10199540.09
      3779471.92     10199924.66
#Sta/Elev= 30
  3168.5   252.1  3432.2   234.8  3775.1  222.31    3997  218.39  4235.4  220.24
  4462.3  218.31  4556.9  216.45  4595.6  213.07  4645.7  204.88  4684.8  203.28
  4705.7  202.02  4745.7  205.57  4795.8  205.71  4865.8  200.14  4891.9  203.76
  4935.9   206.5  4975.9  205.49  4986.3  198.88  5040.9  198.88  5042.3  199.68
  5042.7   206.4  5212.6  203.88  5248.8  204.41  5294.3  209.06  5431.1  222.56
  5531.4  233.84  5555.1  239.06  5631.7  246.89  5790.3  247.88  5989.6  253.46
#Mann= 7 ,-1 , 0
  3168.5     .17       0  4462.3     .15       0  4684.8     .17       0
  4891.9     .15       0  4975.9     .09       0  5042.7     .15       0
  5294.3     .17       0
Bank Sta=4975.9,5042.7
XS Rating Curve= 0 ,0
Exp/Cntr=0.3,0.1

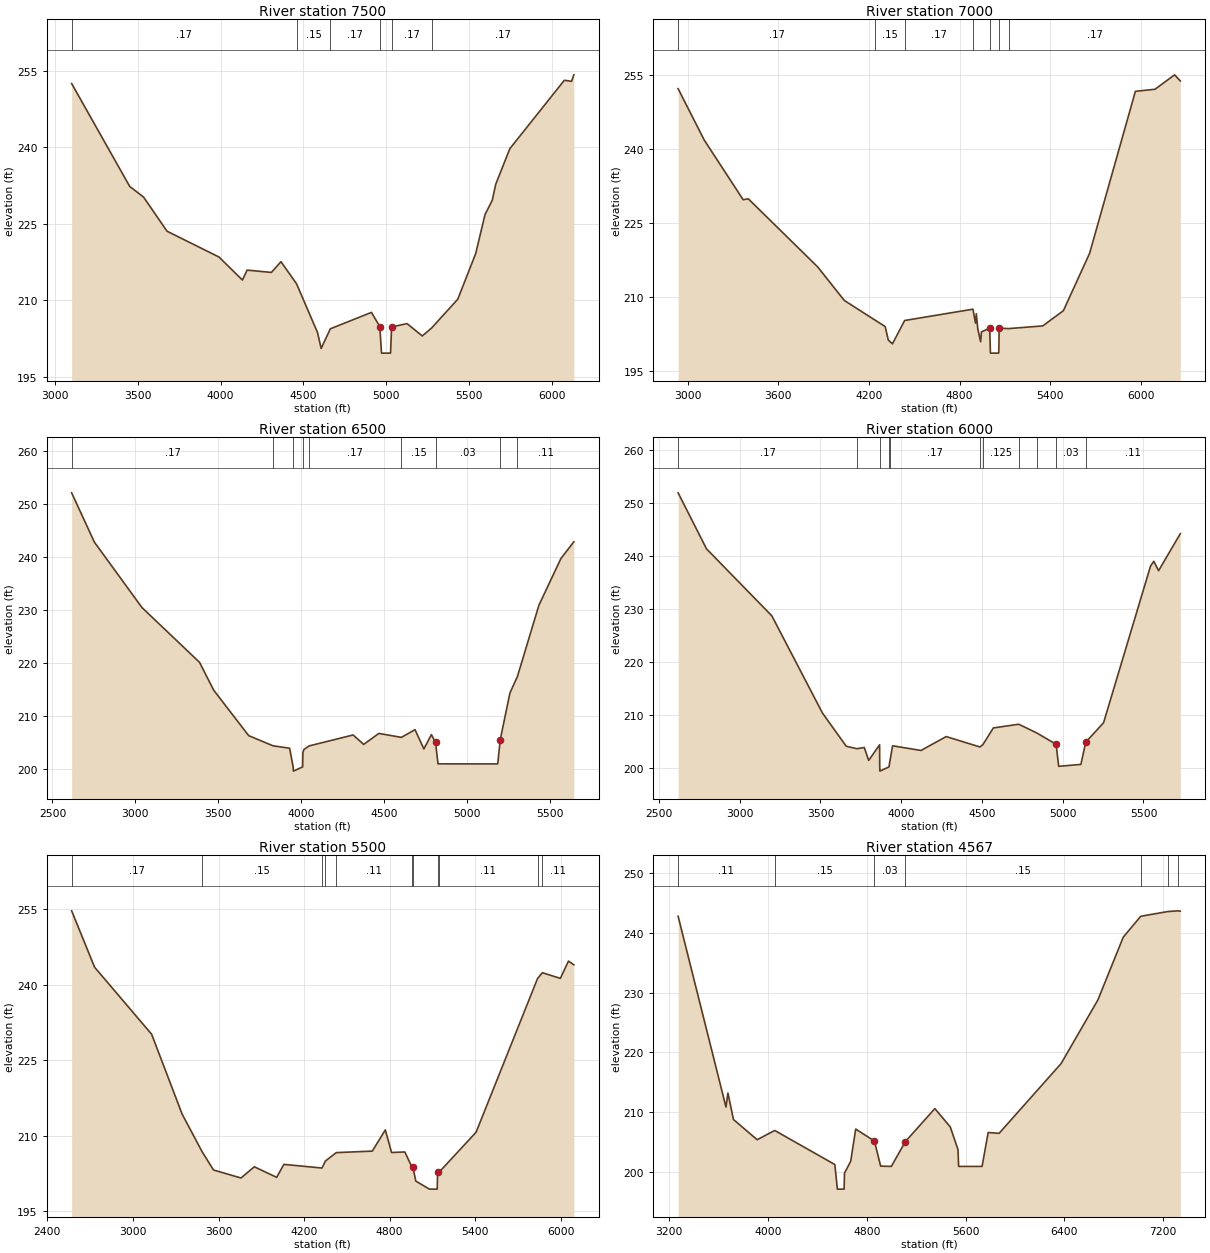
Type RM Length L Ch R = 1 ,7500    ,500,500,500
BEGIN DESCRIPTION:
EAST SANDY CREEK 15.0
END DESCRIPTION:
XS GIS Cut Line= 3
      3782207.19     10199445.86      3780328.51     10199177.84
      3779429.43     10199862.51
#Sta/Elev= 30
  3102.3  252.47  3452.5  232.29    3536   230.2  3677.4  223.51  3990.5  218.45
    4132  213.93    4160  215.88  4306.6  215.43  4364.3  217.54  4458.4  213.19
  4584.6  203.65  4606.7  200.52    4662  204.37  4909.8  207.59  4960.3   204.8
  4970.5   199.6  5025.1   199.6  5031.2  204.73  5124.7  205.39  5216.2  202.97
  5272.4  204.52  5430.4  210.18  5538.4  219.13  5594.6  226.77  5638.2  229.57
    5659   232.7  5744.3   239.7  6072.7  253.11  6116.4  252.91  6130.1  254.18
#Mann= 6 ,-1 , 0
  3102.3     .17       0  4458.4     .15       0    4662     .17       0
  4960.3     .09       0  5031.2     .17       0  5272.4     .17       0
Bank Sta=4960.3,5031.2
XS Rating Curve= 0 ,0
Exp/Cntr=0.3,0.1

Type RM Length L Ch R = 1 ,7000    ,500,500,500
BEGIN DESCRIPTION:
EAST SANDY CREEK 14.0
END DESCRIPTION:
XS GIS Cut Line= 3
      3782186.37     10199313.92       3780201.1     10198750.41
      3779144.66     10199438.93
#Sta/Elev= 30
  2936.3   252.2  3108.9  241.79    3367  229.66  3400.9  229.85  3859.9  216.04
  4036.6  209.22    4240  205.23  4306.9  203.93  4327.7   201.2  4355.2  200.41
    4436  205.15  4888.1  207.45  4905.3  204.62  4910.5  206.52  4920.2  203.44
  4939.2  200.85  4944.4  202.83  4999.1   203.6  5003.9  198.53  5058.5  198.53
  5059.8  199.33  5061.4   203.6  5124.2  203.51    5350  204.05  5486.9  207.14
  5660.4  218.77  5963.7  251.66  6093.5  252.08  6223.2  255.01    6261  253.76
#Mann= 7 ,-1 , 0
  2936.3     .17       0    4240     .15       0    4436     .17       0
  4888.1     .15       0  4999.1     .09       0  5061.4     .15       0
  5124.2     .17       0
Bank Sta=4999.1,5061.4
XS Rating Curve= 0 ,0
Exp/Cntr=0.3,0.1

Type RM Length L Ch R = 1 ,6500    ,500,500,500
BEGIN DESCRIPTION:
EAST SANDY CREEK 13.0
END DESCRIPTION:
XS GIS Cut Line= 3
      3782158.59     10199175.04      3779925.31     10198340.54
       3779371.2     10198008.46
#Sta/Elev= 30
  2615.9  252.13    2753  242.84  3039.9   230.5  3387.5  220.16    3473  214.91
  3684.2  206.33  3831.6  204.41  3931.1  203.96  3952.4  200.44  3953.7  199.64
  4009.7  200.44  4011.3   203.1  4016.7   203.7  4047.3  204.38  4314.1  206.46
  4378.1  204.68  4469.4  206.75  4605.4  206.01  4687.7  207.46  4741.1  203.83
  4786.7  206.53  4811.6  205.04  4826.5  201.01  5186.6     201  5202.1  205.59
  5260.5  214.39  5305.4  217.47  5435.4  230.94  5567.7  239.72    5646   242.9
#Mann= 9 ,-1 , 0
  2615.9     .17       0  3831.6     .15       0  3952.4     .08       0
  4009.7     .15       0  4047.3     .17       0  4605.4     .15       0
  4811.6     .03       0  5202.1    .125       0  5305.4     .11       0
Bank Sta=4811.6,5202.1
XS Rating Curve= 0 ,0
Exp/Cntr=0.3,0.1

Type RM Length L Ch R = 1 ,6000    ,500,500,500
BEGIN DESCRIPTION:
EAST SANDY CREEK 12.0
END DESCRIPTION:
XS GIS Cut Line= 3
      3782144.67     10199043.08      3780069.99     10197874.38
      3779343.92     10197925.96
#Sta/Elev= 30
  2618.8  251.87  2794.6   241.3  3199.2  228.65  3512.7   210.3  3659.6  204.05
  3725.3  203.58  3771.3  203.81  3798.7  201.37  3866.2  204.32  3866.9  200.15
  3868.2  199.35  3924.2  200.15  3933.6  201.83  3946.5  204.13  4122.4  203.25
  4278.5  205.87  4487.5  203.91  4505.7  204.35  4570.4   207.5  4727.5   208.2
  4838.4  206.57    4959  204.42    4975  200.26  5112.4  200.62  5142.5  204.81
  5252.8  208.48  5543.5  238.04  5563.6  238.95  5593.6  237.18  5727.9  244.16
#Mann= 11 ,-1 , 0
  2618.8     .17       0  3725.3     .15       0  3866.9     .12       0
  3924.2     .15       0  3933.6     .17       0  4487.5     .11       0
  4505.7    .125       0  4727.5     .11       0  4838.4     .15       0
    4959     .03       0  5142.5     .11       0
Bank Sta=4959,5142.5
XS Rating Curve= 0 ,0
Exp/Cntr=0.3,0.1

Type RM Length L Ch R = 1 ,5500    ,933,933,933
BEGIN DESCRIPTION:
EAST SANDY CREEK 11.0
END DESCRIPTION:
XS GIS Cut Line= 4
      3782193.32     10198931.99      3780275.93      10197444.3
      3780085.87     10197462.21      3779295.04     10197897.99
#Sta/Elev= 30
  2570.4  254.66  2731.2  243.47  3131.3  230.15  3344.9   214.3    3486  206.78
  3564.9   203.2  3757.7  201.61  3850.9  203.84  4007.6  201.74  4058.2  204.31
  4325.3  203.59  4349.3  204.97  4425.3  206.65  4678.2  206.95  4769.6  211.16
  4813.1  206.67  4906.2  206.78  4956.3  203.77  4962.5  203.77  4983.3     201
  5078.5   199.4  5133.2   199.4  5135.9  202.74  5142.7  202.65  5405.9   210.7
  5836.7  241.22  5870.6  242.37  5996.5  241.25  6053.6  244.68  6091.1  243.94
#Mann= 11 ,-1 , 0
  2570.4     .17       0    3486     .15       0  4325.3     .11       0
  4349.3    .125       0  4425.3     .11       0  4956.3     .15       0
  4962.5     .03       0  5135.9     .15       0  5142.7     .11       0
  5836.7    .125       0  5870.6     .11       0
#XS Ineff= 2 , 0
       0  4769.6  211.16               0
Permanent Ineff=
       T       F
Bank Sta=4962.5,5135.9
XS Rating Curve= 0 ,0
Exp/Cntr=0.3,0.1

Type RM Length L Ch R = 1 ,4567    ,567,567,567
BEGIN DESCRIPTION:
EAST SANDY CREEK 10.0
END DESCRIPTION:
XS GIS Cut Line= 4
      3782851.47     10197442.31      3781141.57       10197202.
      3780274.89     10196903.02      3779215.87     10197851.39
#Sta/Elev= 30
  3273.3  242.72  3660.7   210.9  3676.6  213.23  3721.3  208.82  3913.1  205.45
  4055.5  206.99    4542  201.31  4562.4  197.21  4617.1  197.21    4620  199.86
  4670.5  201.87  4710.9  207.23  4862.4  205.22  4912.9  201.04  4999.4     201
  5112.6  205.13  5351.6  210.64  5476.4  207.58  5538.8  203.81  5544.1     201
  5733.8     201  5783.1  206.65  5871.4  206.51  6373.5  218.15  6671.1  228.75
  6876.7  239.23  7018.1  242.71  7237.4   243.5    7322  243.62  7338.4  243.56
#Mann= 7 ,-1 , 0
  3273.3     .11       0  4055.5     .15       0  4862.4     .03       0
  5112.6     .15       0  7018.1    .125       0  7237.4     .11       0
    7322    .125       0
Bank Sta=4862.4,5112.6
XS Rating Curve= 0 ,0
Exp/Cntr=0.3,0.1