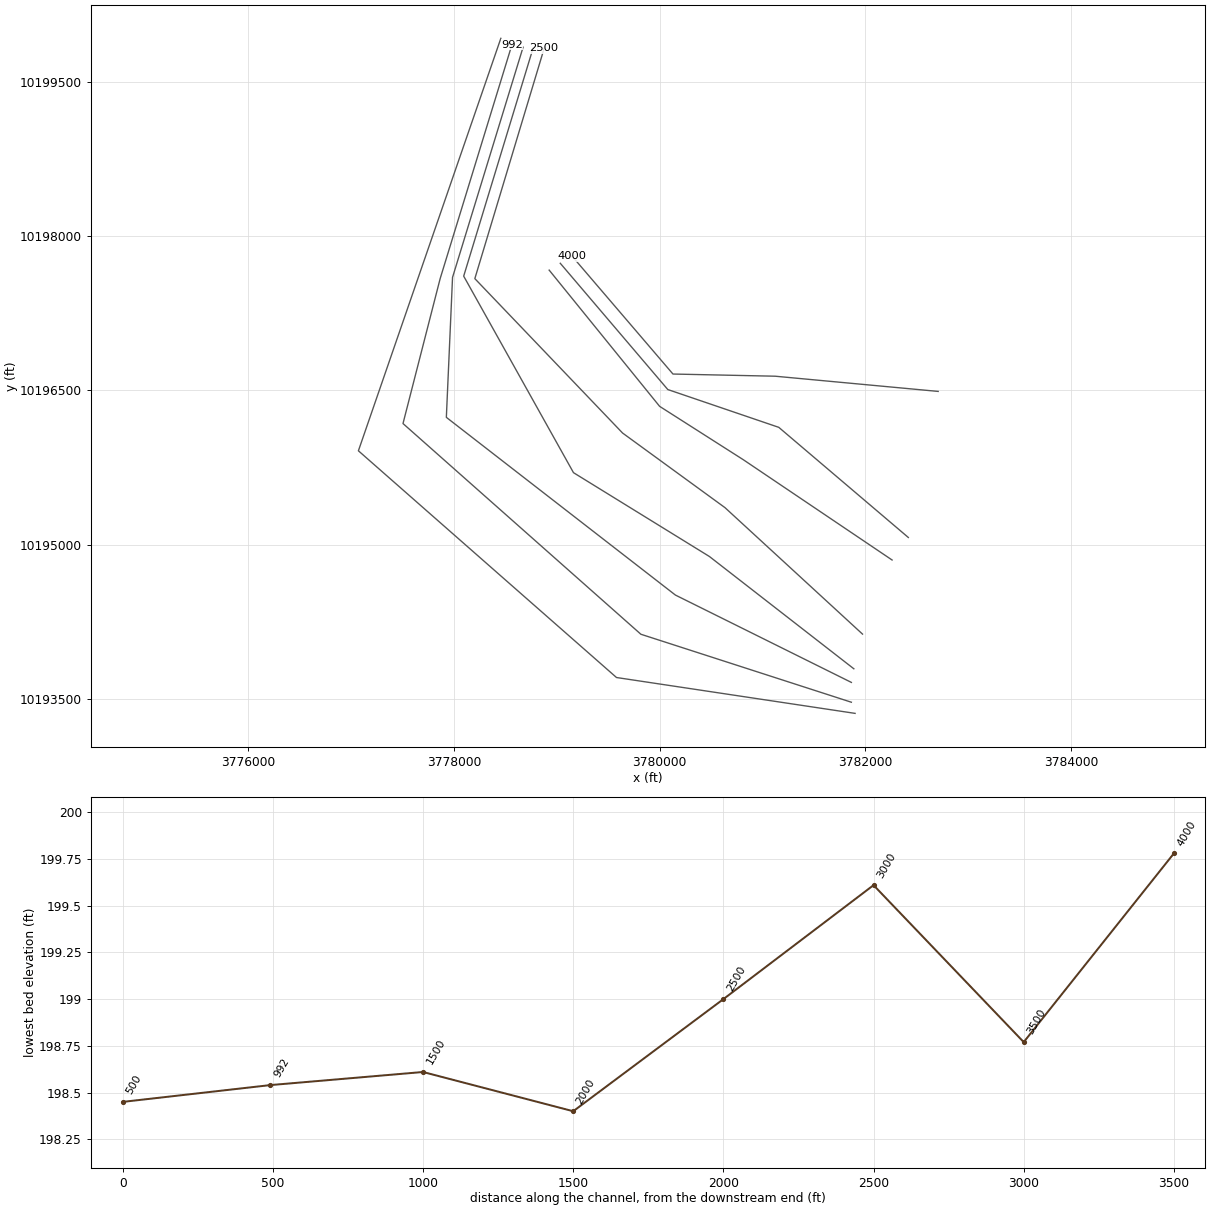
HEC-RAS study EAST SANDY CREEK.prj: EAST SANDY CREEK Base Level Engineering

--- EAST SANDY CREEK.g01 (geometry) --- (continued)

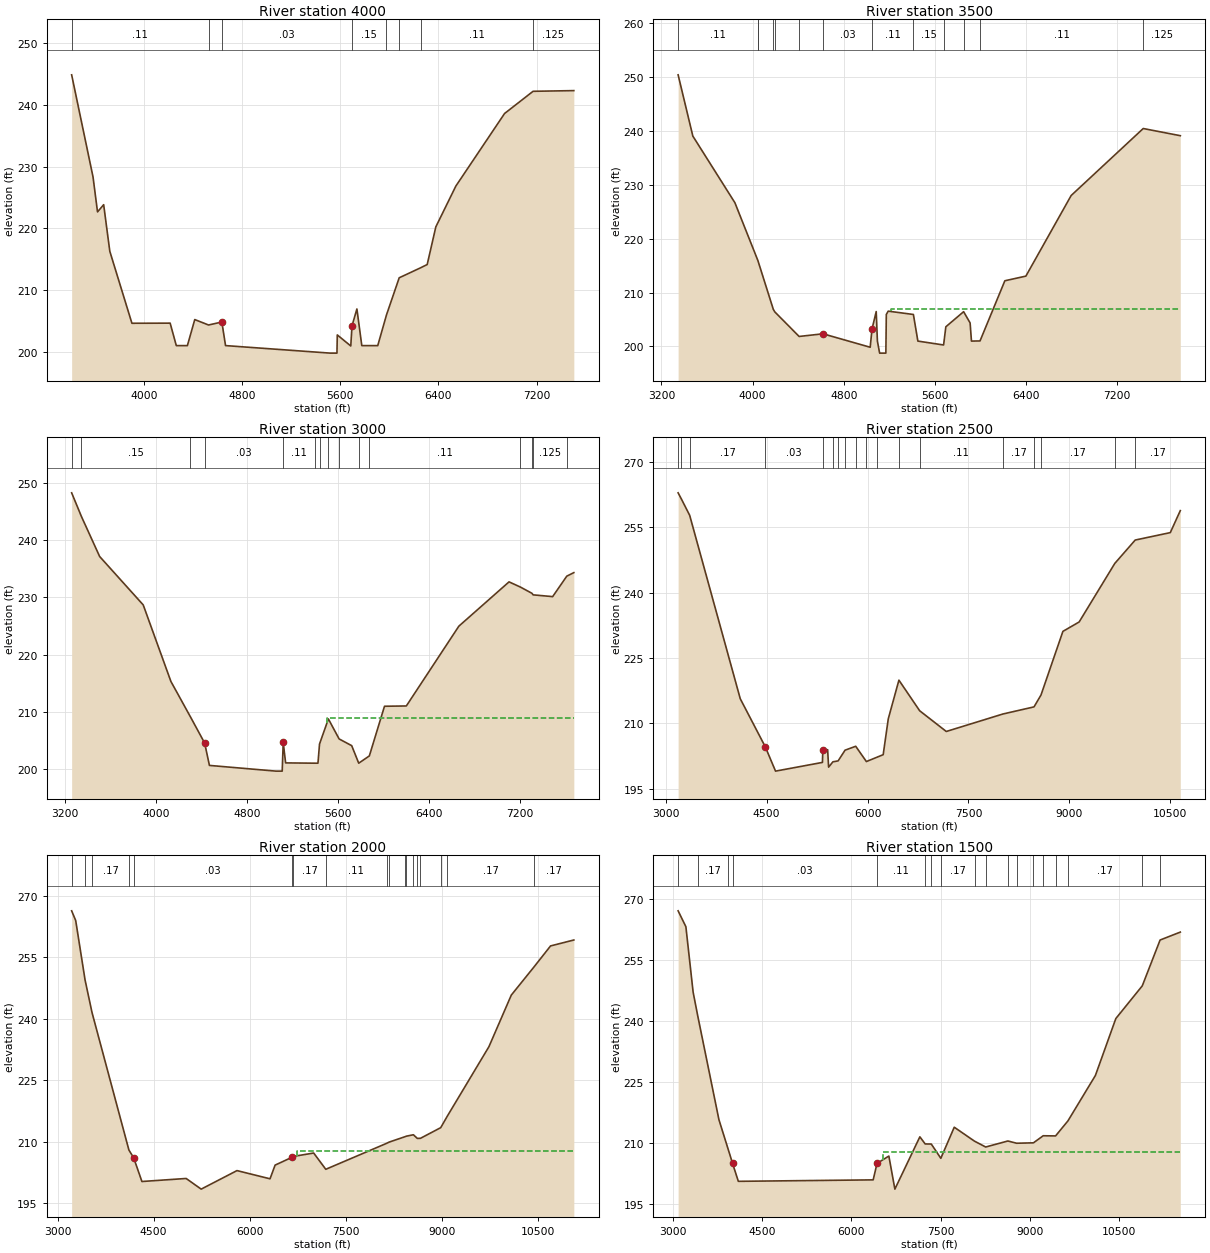
Type RM Length L Ch R = 1 ,4000    ,500,500,500
BEGIN DESCRIPTION:
EAST SANDY CREEK 8.0
END DESCRIPTION:
XS GIS Cut Line= 4
      3782707.94     10196489.98      3781122.22      10196637.9
      3780128.75     10196659.02      3779146.43     10197806.61
#Sta/Elev= 30
  3407.4  244.89  3581.9  228.33  3618.4  222.67  3668.6  223.84  3718.8  216.28
  3899.1  204.62    4211  204.64  4261.2     201  4351.6     201  4411.8  205.22
  4524.3  204.34  4632.8  204.82  4662.9     201  5517.1  199.78  5571.8  199.78
  5574.5  202.73  5684.5  200.94  5694.5  204.19  5734.5  206.94  5774.5     201
  5904.6     201  5975.8  205.97  6079.6  211.99    6254  213.61    6308  214.14
  6378.3  220.24  6541.8  226.86  6939.2  238.62  7171.9  242.22  7504.3  242.33
#Mann= 8 ,-1 , 0
  3407.4     .11       0  4524.3    .125       0  4632.8     .03       0
  5694.5     .15       0  5975.8     .11       0  6079.6    .125       0
    6254     .11       0  7171.9    .125       0
Bank Sta=4632.8,5694.5
XS Rating Curve= 0 ,0
Exp/Cntr=0.3,0.1

Type RM Length L Ch R = 1 ,3500    ,500,500,500
BEGIN DESCRIPTION:
EAST SANDY CREEK 7.0
END DESCRIPTION:
XS GIS Cut Line= 4
       3782417.8     10195069.37       3781157.9     10196140.54
      3780078.48     10196508.23      3779032.84      10197736.1
#Sta/Elev= 30
  3346.3  250.34  3475.5  238.99  3844.6  226.64  4047.8  215.85  4049.7   215.7
  4181.7  206.88  4194.8  206.41  4408.2  201.86  4617.7  202.35  5031.7  199.86
  5047.9  203.24  5084.6  206.47  5095.1     201  5114.6  198.77  5169.3  198.77
  5173.3  205.94  5190.2  206.55    5411  205.93  5450.2     201  5675.9  200.28
  5695.7  203.65  5851.8  206.45  5908.6  204.36  5920.5     201  5995.7  201.03
  6213.5  212.18    6398  213.04  6795.5  227.98  7427.8  240.39  7753.1  239.06
#Mann= 13 ,-1 , 0
  3346.3     .11       0  4047.8     .15       0  4049.7     .11       0
  4181.7     .15       0  4194.8     .11       0  4408.2     .15       0
  4617.7     .03       0  5047.9     .11       0    5411     .15       0
  5675.9     .11       0  5851.8     .15       0  5995.7     .11       0
  7427.8    .125       0
#XS Ineff= 2 , 0
       0                  5211.3       0  206.91
Permanent Ineff=
       F       F
Bank Sta=4617.7,5047.9
XS Rating Curve= 0 ,0
Exp/Cntr=0.3,0.1

Type RM Length L Ch R = 1 ,3000    ,500,500,500
BEGIN DESCRIPTION:
EAST SANDY CREEK 6.0
END DESCRIPTION:
XS GIS Cut Line= 4
      3782259.78     10194850.39      3780814.06      10195824.9
       3779998.9     10196344.86       3778924.7     10197669.72
#Sta/Elev= 30
  3256.5   248.3  3342.7  244.15  3502.7  237.16  3885.9  228.69  4129.3   215.3
  4301.5  209.09  4426.1  204.52  4468.1  200.61  5053.1  199.61    5108  199.61
  5116.9  204.62  5138.1  201.05  5394.1     201  5422.5     201  5436.2  204.35
  5514.1  208.74  5608.6  205.24    5719  204.07  5780.9     201  5874.2  202.27
  6007.6  210.96  6199.5  211.01  6661.4  224.97  7102.6  232.72  7202.9  231.81
  7303.3  230.73  7314.9  230.45  7486.2  230.14  7610.5  233.72  7672.5  234.34
#Mann= 15 ,-1 , 0
  3256.5     .17       0  3342.7     .15       0  4301.5     .11       0
  4426.1     .03       0  5116.9     .11       0  5394.1    .125       0
  5436.2     .11       0  5514.1    .125       0  5608.6     .11       0
  5780.9     .15       0  5874.2     .11       0  7202.9    .125       0
  7303.3     .11       0  7314.9    .125       0  7610.5     .11       0
#XS Ineff= 2 , 0
       0                  5501.9       0  208.92
Permanent Ineff=
       F       F
Bank Sta=4426.1,5116.9
XS Rating Curve= 0 ,0
Exp/Cntr=0.3,0.1

Type RM Length L Ch R = 1 ,2500    ,500,500,500
BEGIN DESCRIPTION:
EAST SANDY CREEK 5.0
END DESCRIPTION:
XS GIS Cut Line= 5
      3781972.13     10194129.81      3780634.78     10195359.54
      3779638.74     10196085.19       3778201.9     10197586.86
      3778876.25     10199826.66
#Sta/Elev= 30
  3183.2  262.94  3232.9  261.49  3354.9  257.78  4107.2  215.63  4479.2  204.59
  4631.6     199  5328.9     201  5335.1  203.94  5406.2  203.92  5420.9  199.92
  5484.7  201.14  5562.1  201.35  5665.2  203.81  5823.8  204.71  5982.3   201.2
  6140.8   202.2  6232.3  202.78    6308  211.02  6466.1   219.9  6774.7  212.87
  7170.6  208.11  8011.5  212.12  8474.8  213.76  8578.6  216.49  8904.4  231.11
  9145.9  233.27  9675.8  246.72  9979.5  252.09 10501.1   253.8 10649.8  258.85
#Mann= 18 ,-1 , 0
  3183.2     .17       0  3232.9     .11       0  3354.9     .17       0
  4479.2     .03       0  5335.1    .125       0  5484.7     .11       0
  5562.1    .125       0  5665.2    .125       0  5823.8    .125       0
  5982.3     .15       0  6140.8     .11       0  6466.1     .17       0
  6774.7     .11       0  8011.5     .17       0  8474.8     .11       0
  8578.6     .17       0  9675.8     .11       0  9979.5     .17       0
Bank Sta=4479.2,5335.1
XS Rating Curve= 0 ,0
Exp/Cntr=0.3,0.1

Type RM Length L Ch R = 1 ,2000    ,500,500,500
BEGIN DESCRIPTION:
EAST SANDY CREEK 4.0
END DESCRIPTION:
XS GIS Cut Line= 5
      3781887.86     10193792.49      3780483.14     10194884.59
      3779161.27     10195699.86      3778093.49     10197610.95
      3778767.84     10199826.67
#Sta/Elev= 30
  3220.7  266.32    3284  263.95  3430.3  249.44  3538.1  241.53  4114.4  207.94
  4188.8  206.04  4317.3  200.26  5007.5     201  5242.4   198.4  5801.1  202.92
  6316.7  200.92    6396  204.26  6659.7  206.17  6680.6  206.38  6998.2  207.21
  7186.9  203.24    8137  209.58  8172.6  209.86  8424.5   211.2  8443.9  211.32
  8554.1  211.67  8615.3  210.78  8664.3   210.8  8980.6   213.4    9078  216.06
  9733.1  233.16 10082.5  245.76 10435.7  252.61 10694.8  257.75 11058.3   259.2
#Mann= 18 ,-1 , 0
  3220.7     .17       0  3430.3     .11       0  3538.1     .17       0
  4114.4     .11       0  4188.8     .03       0  6659.7     .11       0
  6680.6     .17       0  7186.9     .11       0    8137     .17       0
  8172.6     .11       0  8424.5     .17       0  8443.9     .11       0
  8554.1     .17       0  8615.3     .11       0  8664.3     .17       0
  8980.6     .11       0    9078     .17       0 10435.7     .17       0
#XS Ineff= 2 , 0
       0                  6738.9       0  207.71
Permanent Ineff=
       F       F
Bank Sta=4188.8,6659.7
XS Rating Curve= 0 ,0
Exp/Cntr=0.3,0.1

Type RM Length L Ch R = 1 ,1500    ,508,508,508
BEGIN DESCRIPTION:
EAST SANDY CREEK 3.0
END DESCRIPTION:
XS GIS Cut Line= 5
      3781863.76     10193660.01      3780152.51     10194509.51
      3777924.85     10196237.76      3777985.08     10197598.91
      3778671.16      10199837.7
#Sta/Elev= 30
  3089.5  267.13    3220  263.22  3341.7   247.1  3420.6  241.16  3774.7  215.73
  3925.9  208.63 4003.55  204.96  4100.9  200.53  6365.6  200.89  6429.9  204.94
    6629  206.75  6729.9  198.61  7149.5  211.49    7239  209.73  7341.4  209.71
  7501.7   206.2  7727.1  213.85  8067.2  210.42  8255.2  208.98  8627.5  210.46
  8774.7  209.91  9057.3  210.01  9220.8  211.75  9428.8  211.71  9636.8  215.42
 10097.6  226.59 10440.8  240.61 10884.9  248.66   11184  259.94 11523.5  261.89
#Mann= 18 ,-1 , 0
  3089.5     .17       0  3420.6     .17       0  3925.9     .11       0
 4003.55     .03       0  6429.9     .11       0    7239     .17       0
  7341.4     .11       0  7501.7     .17       0  8067.2     .11       0
  8255.2     .17       0  8627.5     .11       0  8774.7     .17       0
  9057.3     .11       0  9220.8     .17       0  9428.8     .11       0
  9636.8     .17       0 10884.9     .11       0   11184     .17       0
#XS Ineff= 2 , 0
       0                  6523.1       0   207.8
Permanent Ineff=
       F       F
Bank Sta=4003.55,6429.9
XS Rating Curve= 0 ,0
Exp/Cntr=0.3,0.1

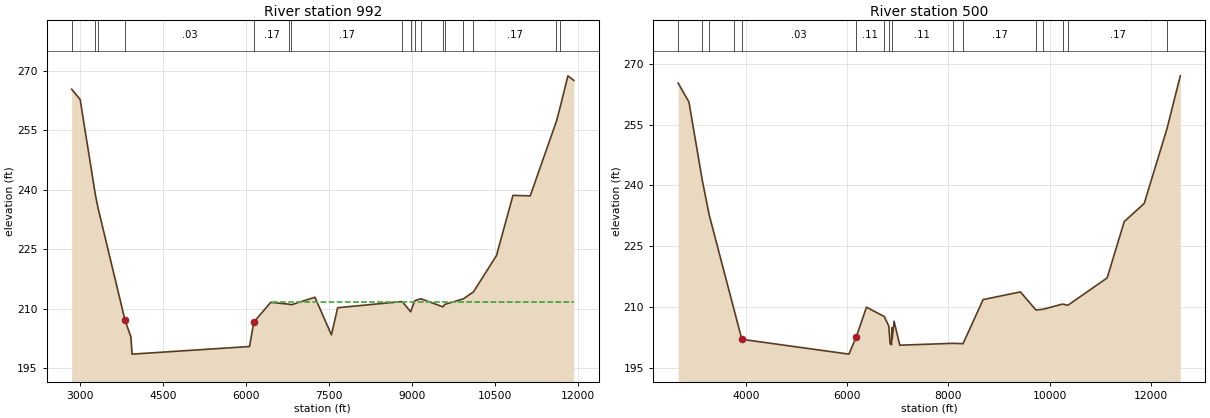
Type RM Length L Ch R = 1 ,992     ,492,492,492
BEGIN DESCRIPTION:
EAST SANDY CREEK 1.0
END DESCRIPTION:
XS GIS Cut Line= 5
      3781863.75     10193467.29      3779816.75     10194128.38
      3777503.26     10196177.53      3777864.62     10197586.86
      3778563.05     10199862.77
#Sta/Elev= 30
  2848.9  265.38  3002.2   262.8  3278.3  238.71  3324.6   235.5  3812.6  207.14
  3920.2  202.87  3941.3  198.54  6063.9  200.46  6141.7  206.61  6446.2   211.6
  6776.6  211.14  6818.5  210.98  7246.6  212.89  7544.4   203.4  7657.3  210.25
  8823.8   211.8  8976.6  209.22  9048.4     212  9157.3  212.52  9562.4  210.46
  9592.1  211.09  9929.4  212.49 10112.2  214.25 10527.9  223.41   10826  238.59
   11138  238.47 11612.6  257.34 11672.5  260.49 11818.8  268.75 11926.1   267.6
#Mann= 17 ,-1 , 0
  2848.9     .17       0  3278.3     .11       0  3324.6     .17       0
  3812.6     .03       0  6141.7     .17       0  6776.6     .11       0
  6818.5     .17       0  8823.8     .11       0  8976.6     .17       0
  9048.4     .11       0  9157.3     .17       0  9562.4     .11       0
  9592.1     .17       0  9929.4     .11       0 10112.2     .17       0
 11612.6     .11       0 11672.5     .17       0
#XS Ineff= 2 , 0
       0                  6488.8       0  211.71
Permanent Ineff=
       F       F
Bank Sta=3812.6,6141.7
XS Rating Curve= 0 ,0
Exp/Cntr=0.3,0.1

Type RM Length L Ch R = 1 ,500     ,0,0,0
BEGIN DESCRIPTION:
EAST SANDY CREEK 1.5
END DESCRIPTION:
XS GIS Cut Line= 4
      3781899.87     10193358.88      3779579.63     10193707.61
      3777069.62     10195912.53      3778454.87     10199923.74
#Sta/Elev= 30
  2653.7  265.24  2868.1  260.56  3131.4   241.3  3266.2  232.86  3755.9  209.58
  3913.9   202.1  6031.7  198.45 6176.26  202.68  6378.3  210.01  6729.6  207.73
  6821.1  205.31    6846     201  6874.5  200.78  6881.2  204.93  6887.6  202.22
  6923.9  206.55  7037.7  200.65  8080.6  201.11  8288.2  201.02  8685.5  211.89
  9423.4  213.78  9729.2  209.33  9869.7   209.5   10256  210.78 10361.4  210.49
 11138.1  217.22 11475.9  231.11 11870.7  235.57 12318.9  253.89 12584.6  267.02
#Mann= 16 ,-1 , 0
  2653.7     .17       0  3131.4     .11       0  3266.2     .17       0
  3755.9     .11       0  3913.9     .03       0 6176.26     .11       0
  6729.6     .11       0  6821.1     .17       0  6887.6     .11       0
  8080.6     .15       0  8288.2     .17       0  9729.2     .11       0
  9869.7     .17       0   10256     .11       0 10361.4     .17       0
 12318.9     .11       0
#XS Ineff= 2 , 0
       0                  6378.3       0  210.01
Permanent Ineff=
       F       F
Bank Sta=3913.9,6176.26
XS Rating Curve= 0 ,0
Exp/Cntr=0.3,0.1

Chan Stop Cuts=-1
Use User Specified Reach Order=0
Composite Channel Slope=5