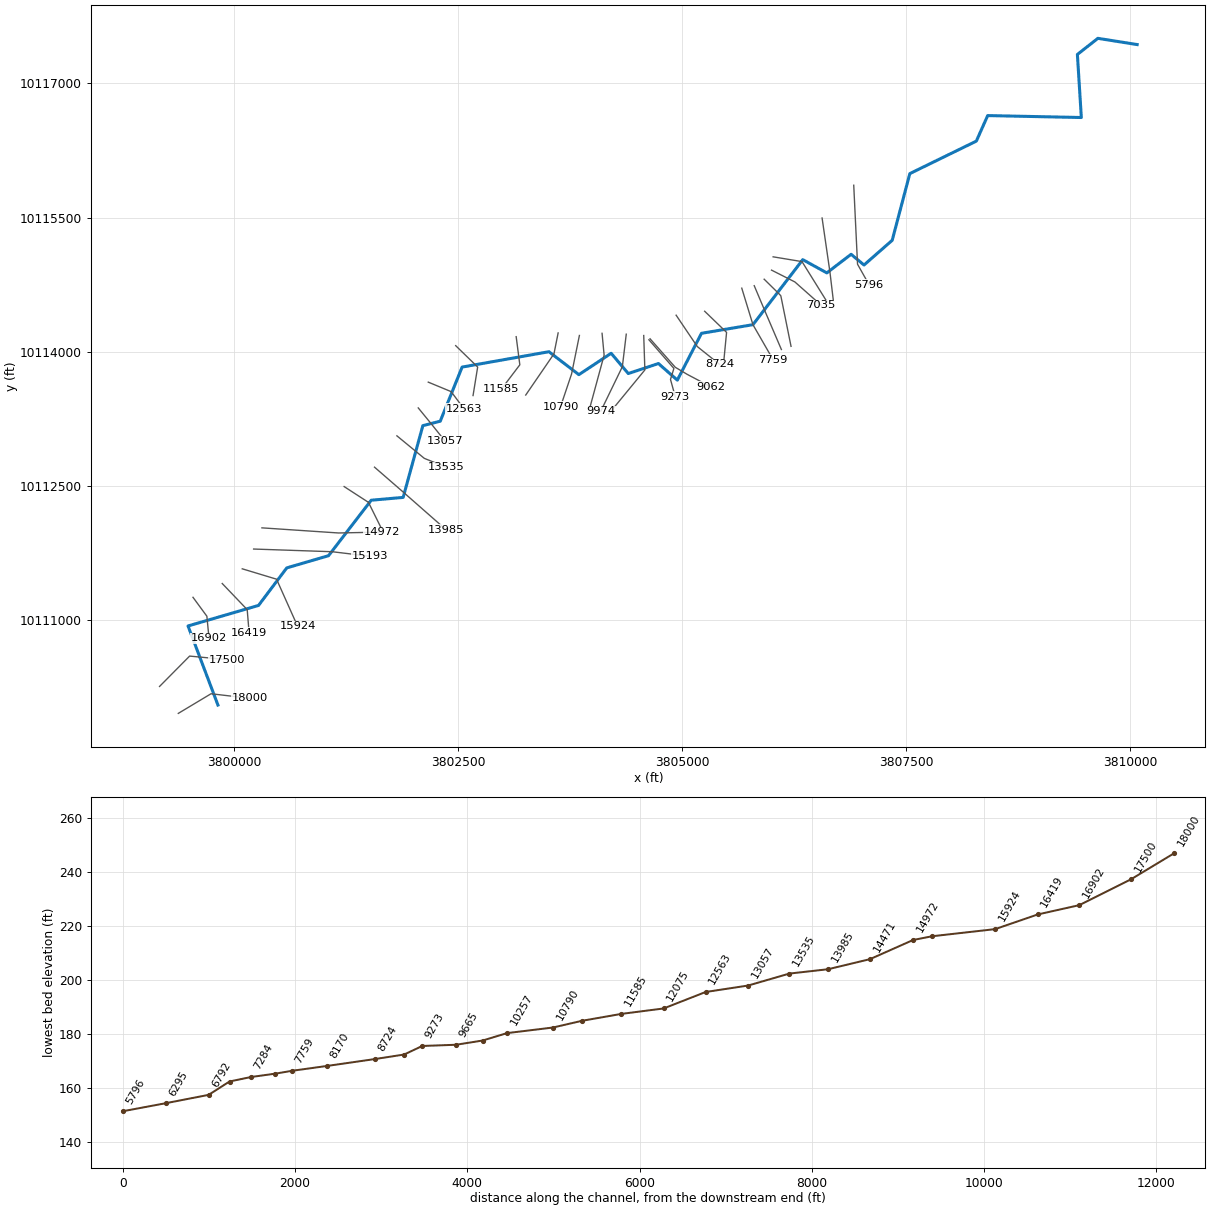
--- EGYPT CREEK.prj (project) ---

Proj Title=EGYPT CREEK Base Level Engineering
Current Plan=p01
Default Exp/Contr=0.3,0.1
English Units
Geom File=g01
Flow File=f01
Flow File=f02
Plan File=p01
Y Axis Title=Elevation
X Axis Title(PF)=Main Channel Distance
X Axis Title(XS)=Station
BEGIN DESCRIPTION:
EGYPT CREEK
END DESCRIPTION:
DSS Export Rating Curves= 0
DSS Export Rating Curve Sorted= 0
DSS Export Volume Flow Curves= 0
DXF OffsetX= 0
DXF OffsetY= 0
DXF ScaleX= 1
DXF ScaleY= 10

--- EGYPT CREEK.p01 (plan) ---

Plan Title=Multiple Run
Short Identifier=Multiple
Geom File=g01
Flow File=f01
Subcritical Flow
K Sum by GR= 0
Std Step Tol= 0.01
Critical Tol= 0.01
Num of Std Step Trials= 20
Max Error Tol= 0.3
Flow Tol Ratio= 0.001
Split Flow NTrial= 30
Split Flow Tol= 0.02
Split Flow Ratio= 0.02
Log Output Level= 0
Friction Slope Method= 1
Unsteady Friction Slope Method= 2
Unsteady Bridges Friction Slope Method= 1
Parabolic Critical Depth
Global Vel Dist=  1 , 1 , 1
Global Log Level= 0
CheckData=True
Encroach Param= -1, 0, 0, 0
BEGIN DESCRIPTION:
Multiple Run
END DESCRIPTION:

--- EGYPT CREEK.f01 (steady flow) ---

Flow Title=Multiple
Program Version=4.10
Number of Profiles= 7
Profile Names=10-year,25-year,50-year,1pct_min,100-year,1pct_plu,500-year
River Rch & RM=EGYPT CREEK,Reach-1         ,18000
     188     233     296     125     376    1136     624
River Rch & RM=EGYPT CREEK,Reach-1         ,16419
     616     831    1121     498    1504    4542    2798
River Rch & RM=EGYPT CREEK,Reach-1         ,9062
    1258    1757    2425    1099    3320   10026    6429
Boundary for River Rch & Prof#=EGYPT CREEK,Reach-1         , 1
Up Type= 0
Dn Type= 3
Dn Slope=0.005
Boundary for River Rch & Prof#=EGYPT CREEK,Reach-1         , 2
Up Type= 0
Dn Type= 3
Dn Slope=0.005
Boundary for River Rch & Prof#=EGYPT CREEK,Reach-1         , 3
Up Type= 0
Dn Type= 3
Dn Slope=0.005
Boundary for River Rch & Prof#=EGYPT CREEK,Reach-1         , 4
Up Type= 0
Dn Type= 3
Dn Slope=0.005
Boundary for River Rch & Prof#=EGYPT CREEK,Reach-1         , 5
Up Type= 0
Dn Type= 3
Dn Slope=0.005
Boundary for River Rch & Prof#=EGYPT CREEK,Reach-1         , 6
Up Type= 0
Dn Type= 3
Dn Slope=0.005
Boundary for River Rch & Prof#=EGYPT CREEK,Reach-1         , 7
Up Type= 0
Dn Type= 3
Dn Slope=0.005
DSS Import GetInterval= 0
DSS Import GetPeak= 0
DSS Import FillOption= 0

--- EGYPT CREEK.f02 (steady flow) ---

Flow Title=Orig_BLE_Flow
Program Version=4.10
Number of Profiles= 7
Profile Names=10-year,25-year,50-year,1pct_min,100-year,1pct_plu,500-year
River Rch & RM=EGYPT CREEK,Reach-1         ,18000
     188     228     257      96     289     873     363
River Rch & RM=EGYPT CREEK,Reach-1         ,16419
     616     815     975     383    1157    3495    1627
River Rch & RM=EGYPT CREEK,Reach-1         ,9062
    1258    1723    2109     846    2554    7712    3738
Boundary for River Rch & Prof#=EGYPT CREEK,Reach-1         , 1
Up Type= 0
Dn Type= 3
Dn Slope=0.005
Boundary for River Rch & Prof#=EGYPT CREEK,Reach-1         , 2
Up Type= 0
Dn Type= 3
Dn Slope=0.005
Boundary for River Rch & Prof#=EGYPT CREEK,Reach-1         , 3
Up Type= 0
Dn Type= 3
Dn Slope=0.005
Boundary for River Rch & Prof#=EGYPT CREEK,Reach-1         , 4
Up Type= 0
Dn Type= 3
Dn Slope=0.005
Boundary for River Rch & Prof#=EGYPT CREEK,Reach-1         , 5
Up Type= 0
Dn Type= 3
Dn Slope=0.005
Boundary for River Rch & Prof#=EGYPT CREEK,Reach-1         , 6
Up Type= 0
Dn Type= 3
Dn Slope=0.005
Boundary for River Rch & Prof#=EGYPT CREEK,Reach-1         , 7
Up Type= 0
Dn Type= 3
Dn Slope=0.005
DSS Import GetInterval= 0
DSS Import GetPeak= 0
DSS Import FillOption= 0

--- EGYPT CREEK.g01 (geometry) ---

Geom Title=Existing Conditions
Program Version=4.10

River Reach=EGYPT CREEK     ,Reach-1
Reach XY= 30
      3799819.85     10110053.37      3799485.92     10110936.87
      3800272.98      10111166.4      3800588.08     10111585.67
      3801054.75     10111722.12      3801531.31     10112341.92
      3801887.56     10112373.17      3802107.35     10113174.73
      3802301.62     10113224.73      3802545.89     10113829.42
      3803515.13     10114000.92      3803849.25     10113744.63
      3804209.66     10113983.52      3804400.64     10113757.13
      3804737.44     10113868.93      3804948.55     10113683.52
      3805218.23     10114206.84      3805792.57     10114302.99
      3806348.82     10115029.55      3806617.57     10114881.63
       3806888.4     10115089.44      3807032.67     10114969.65
      3807347.26     10115245.69      3807544.13     10115990.98
      3808286.58     10116353.74       3808413.4     10116639.16
      3809458.72     10116617.54      3809414.71     10117322.23
      3809643.87     10117502.18      3810082.09     10117432.52

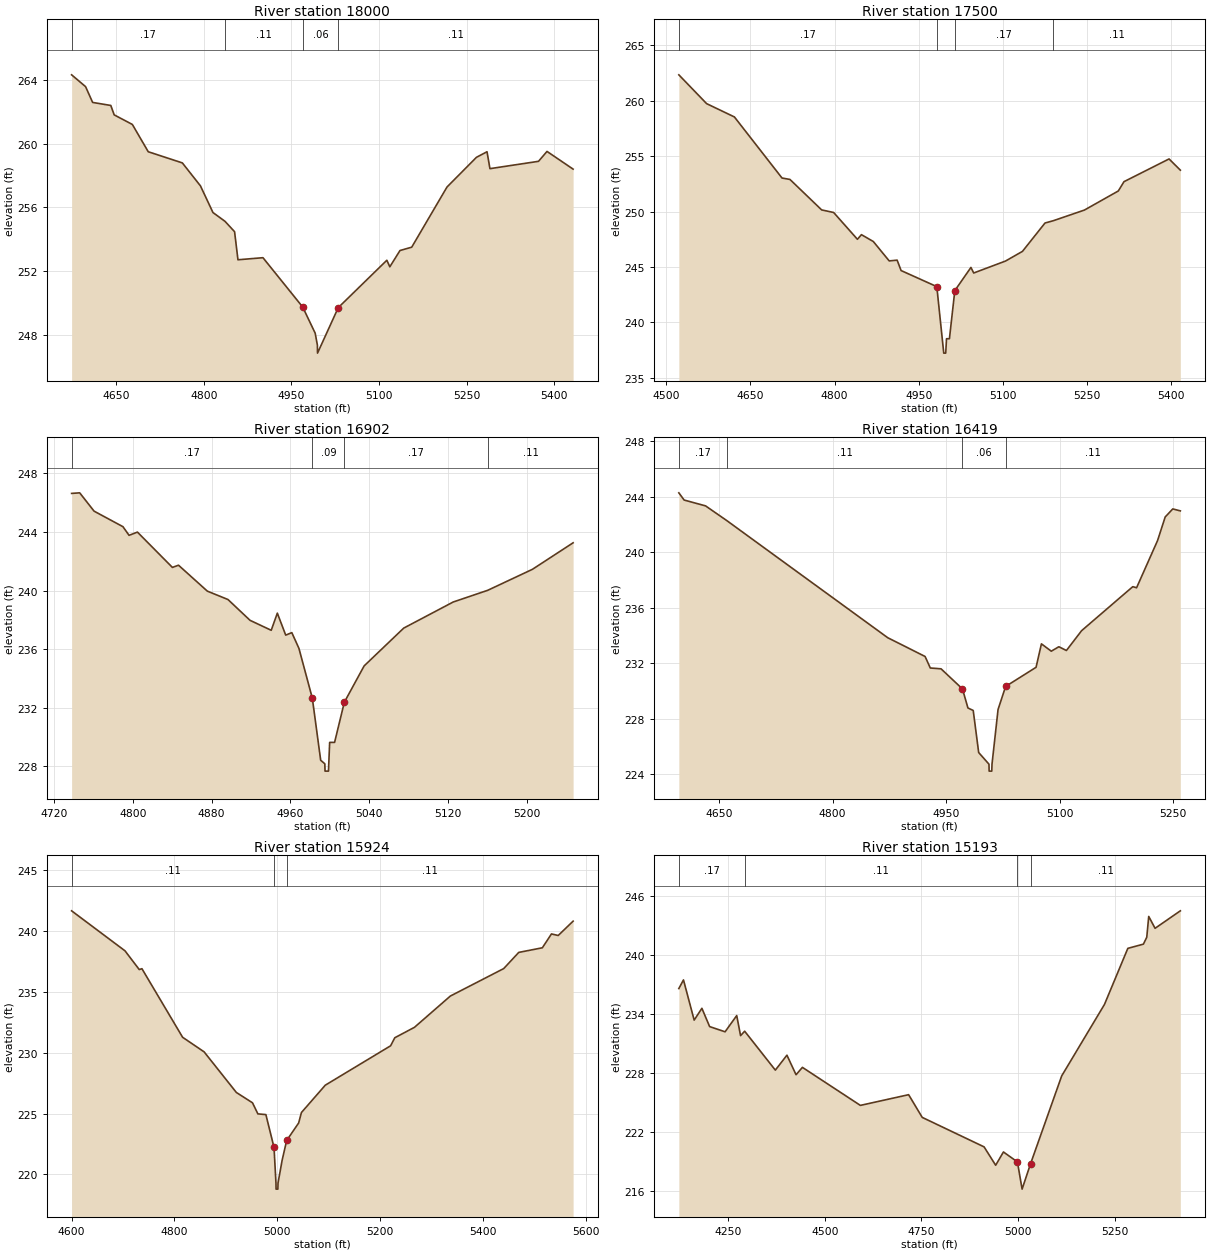
Type RM Length L Ch R = 1 ,18000   ,500,500,500
BEGIN DESCRIPTION:
EGYPT CREEK 34.0
END DESCRIPTION:
XS GIS Cut Line= 3
      3799377.34     10109960.34       3799742.8     10110179.61
      3800172.26     10110129.25
#Sta/Elev= 30
  4573.8  264.31  4597.7  263.57  4609.8  262.58  4640.9  262.39  4646.7   261.8
  4677.8   261.2    4705  259.49  4763.4  258.79  4794.4  257.35  4815.8  255.68
  4836.4  255.13  4852.8  254.48  4858.6  252.72  4901.4  252.85  4969.4  249.76
  4990.8  248.12  4994.6  247.37  4994.8  246.87  5030.3  249.72  5113.5  252.69
  5118.6  252.28    5136   253.3  5156.1  253.51  5216.5  257.28  5266.9  259.14
    5285  259.49    5290  258.43  5373.2  258.89  5387.7  259.51  5432.4   258.4
#Mann= 4 ,-1 , 0
  4573.8     .17       0  4836.4     .11       0  4969.4     .06       0
  5030.3     .11       0
Bank Sta=4969.4,5030.3
XS Rating Curve= 0 ,0
Exp/Cntr=0.3,0.1

Type RM Length L Ch R = 1 ,17500   ,598,598,598
BEGIN DESCRIPTION:
EGYPT CREEK 33.0
END DESCRIPTION:
XS GIS Cut Line= 3
      3799167.84     10110261.06      3799503.72     10110600.47
      3799917.85     10110561.07
#Sta/Elev= 30
  4522.5  262.34    4572  259.74  4621.5  258.54  4706.3  253.03  4720.5   252.9
    4777  250.15  4798.3  249.92  4840.7   247.5  4847.8  247.92    4869   247.3
  4897.3  245.55  4911.4  245.62  4918.5  244.68  4982.1  243.23  4994.5  237.23
    4998  237.23  4999.4  238.53  5004.6  238.53  5014.2  242.87  5042.9  244.96
  5047.9  244.46  5104.6  245.54  5134.7  246.41  5174.9  248.97  5189.9  249.18
  5245.2  250.14  5305.5  251.86  5315.6   252.7  5395.9  254.75    5416  253.74
#Mann= 4 ,-1 , 0
  4522.5     .17       0  4982.1     .09       0  5014.2     .17       0
  5189.9     .11       0
Bank Sta=4982.1,5014.2
XS Rating Curve= 0 ,0
Exp/Cntr=0.3,0.1

Type RM Length L Ch R = 1 ,16902   ,483,483,483
BEGIN DESCRIPTION:
EGYPT CREEK 32.0
END DESCRIPTION:
XS GIS Cut Line= 3
      3799541.27     10111257.08      3799696.26     10111045.72
      3799720.14     10110799.98
#Sta/Elev= 30
  4737.9  246.63  4746.1  246.67  4760.7  245.42    4790  244.36  4796.2  243.77
  4804.7  243.99  4840.2  241.58  4846.4  241.73  4875.7  239.96  4896.6  239.39
    4919  237.97  4940.5  237.29  4946.7  238.46  4955.2  236.96  4961.4  237.13
  4968.6  236.06  4982.2  232.66  4990.7  228.42  4994.9  228.18  4995.1  227.68
  4998.6  227.68  4999.8  229.64  5004.8  229.64  5014.7  232.38  5034.8  234.86
    5075  237.44  5125.2  239.22  5160.3  240.02  5205.6  241.45  5246.9  243.26
#Mann= 4 ,-1 , 0
  4737.9     .17       0  4982.2     .09       0  5014.7     .17       0
  5160.3     .11       0
Bank Sta=4982.2,5014.7
XS Rating Curve= 0 ,0
Exp/Cntr=0.3,0.1

Type RM Length L Ch R = 1 ,16419   ,495,495,495
BEGIN DESCRIPTION:
EGYPT CREEK 31.0
END DESCRIPTION:
XS GIS Cut Line= 3
      3799867.88     10111411.05      3800146.41     10111119.52
      3800167.85     10110861.11
#Sta/Elev= 30
  4596.8  244.27  4603.8  243.75  4632.1  243.33  4659.9  242.28  4872.8  233.83
  4922.1  232.48    4929  231.65  4943.2  231.59  4971.5  230.14  4978.7  228.77
  4985.7  228.59  4992.9  225.56  5006.5  224.72  5006.7  224.22  5010.2  224.22
  5010.5  224.72  5018.5  228.66  5028.5  230.32  5068.7   231.7  5075.8  233.39
  5088.8  232.86  5098.8  233.18  5108.8  232.91  5128.9  234.34  5196.5  237.51
  5201.5  237.43  5229.2  240.83  5239.3  242.53  5249.3  243.11  5259.3  242.97
#Mann= 4 ,-1 , 0
  4596.8     .17       0  4659.9     .11       0  4971.5     .06       0
  5028.5     .11       0
Bank Sta=4971.5,5028.5
XS Rating Curve= 0 ,0
Exp/Cntr=0.3,0.1

Type RM Length L Ch R = 1 ,15924   ,731,731,731
BEGIN DESCRIPTION:
EGYPT CREEK 30.0
END DESCRIPTION:
XS GIS Cut Line= 3
      3800091.27     10111575.48      3800474.02     10111459.62
      3800708.68     10110934.58
#Sta/Elev= 30
  4600.1  241.67  4703.9  238.38  4731.6  236.84  4736.8  236.91  4815.9  231.27
  4857.7  230.07  4920.4  226.73  4951.8  225.88  4962.2  224.97  4977.8  224.91
  4993.6  222.21  4997.4  219.28  4997.6  218.78  5001.1  218.78  5001.4  219.28
  5009.4  221.16  5018.2  222.78  5041.5  224.22  5046.9  225.08  5093.3  227.33
  5220.3  230.57  5228.4  231.23  5266.7  232.09  5336.4  234.66  5440.2  236.92
  5469.4  238.25  5515.3  238.63    5533  239.77  5546.1  239.64  5575.1  240.82
#Mann= 3 , 0 , 0
  4600.1     .11       0  4993.6     .06       0  5018.2     .11       0
Bank Sta=4993.6,5018.2
XS Rating Curve= 0 ,0
Exp/Cntr=0.3,0.1

Type RM Length L Ch R = 1 ,15193   ,221,221,221
BEGIN DESCRIPTION:
EGYPT CREEK 29.0
END DESCRIPTION:
XS GIS Cut Line= 3
      3800218.18     10111796.39      3801095.37      10111766.4
      3801512.76     10111716.12
#Sta/Elev= 30
  4122.3  236.55  4134.3  237.43    4162  233.34    4182  234.54    4202  232.68
    4242  232.15  4272.1   233.8  4282.1  231.76  4292.7  232.21  4372.1  228.25
  4402.1  229.77  4425.7  227.78  4442.2  228.53  4592.2  224.66  4717.1  225.75
  4752.3  223.44  4912.4  220.44  4942.4  218.57  4962.5  219.92  4998.7  218.91
  5010.8  216.14  5032.7  218.72  5113.3  227.66  5224.1  234.94  5284.5  240.64
  5324.8  241.07  5333.5  241.77  5338.6  243.89    5355  242.68  5420.4  244.46
#Mann= 4 ,-1 , 0
  4122.3     .17       0  4292.7     .11       0  4998.7     .07       0
  5032.7     .11       0
Bank Sta=4998.7,5032.7
XS Rating Curve= 0 ,0
Exp/Cntr=0.3,0.1

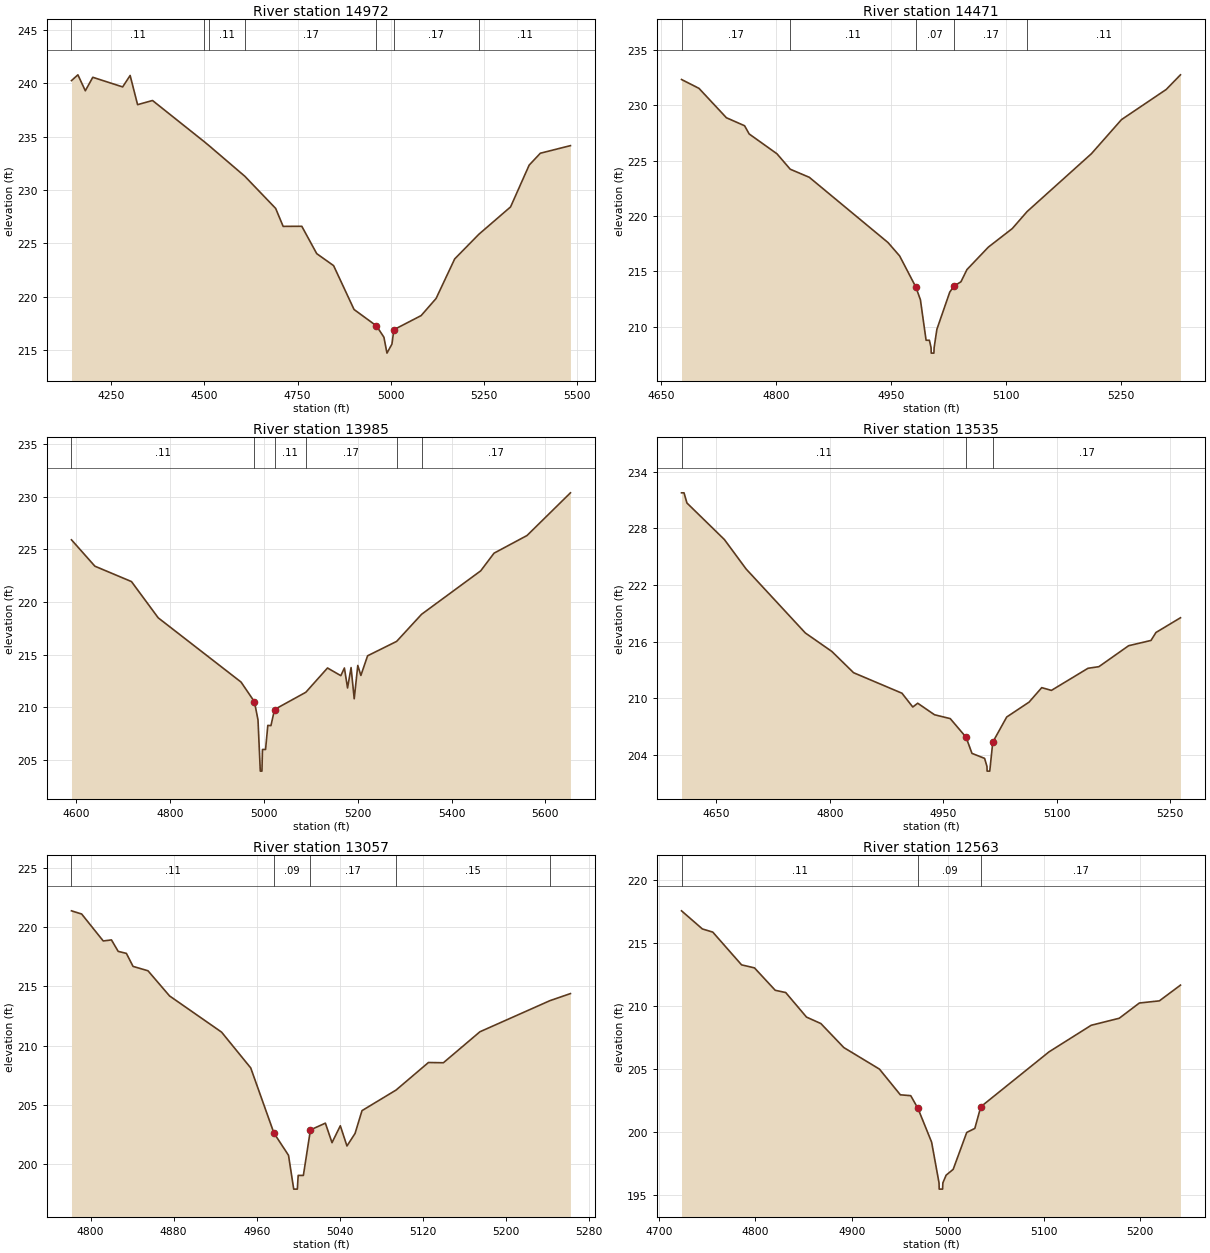
Type RM Length L Ch R = 1 ,14972   ,501,501,501
BEGIN DESCRIPTION:
EGYPT CREEK 28.0
END DESCRIPTION:
XS GIS Cut Line= 3
      3800310.74     10112033.09      3801165.93     10111975.86
      3801648.63     10111985.75
#Sta/Elev= 30
  4142.9  240.23  4160.1  240.77  4180.1  239.28  4200.1  240.54  4280.3  239.64
  4300.4  240.71  4320.4  237.98  4360.5  238.37    4499  234.53  4512.2  234.15
  4608.3  231.29  4691.2  228.28  4711.3   226.6  4761.4  226.61  4801.5  224.05
  4846.8  222.93  4901.7  218.83  4961.8   217.3  4981.9  216.24  4990.1  214.75
  5003.5   215.6  5008.6  216.94  5081.9  218.26    5122  219.86    5172  223.56
  5236.8  225.86    5322  228.42    5372  232.33    5402  233.44  5482.8  234.15
#Mann= 7 ,-1 , 0
  4142.9     .11       0    4499     .17       0  4512.2     .11       0
  4608.3     .17       0  4961.8     .09       0  5008.6     .17       0
  5236.8     .11       0
Bank Sta=4961.8,5008.6
XS Rating Curve= 0 ,0
Exp/Cntr=0.3,0.1

Type RM Length L Ch R = 1 ,14471   ,486,486,486
BEGIN DESCRIPTION:
EGYPT CREEK 27.0
END DESCRIPTION:
XS GIS Cut Line= 3
      3801228.74     10112494.14      3801500.06     10112317.96
      3801645.76     10112024.43
#Sta/Elev= 30
  4676.5  232.31  4699.3  231.51  4735.1  228.86  4758.8  228.14  4764.8   227.4
  4801.1  225.61  4818.4  224.22  4843.3  223.49    4946  217.61  4961.2   216.4
  4982.3   213.6  4988.3  212.45  4995.7   208.8    5000   208.8  5002.2  208.14
  5002.4  207.64  5005.9  207.64  5006.2  208.14  5009.8  209.79  5026.6  213.14
  5032.2  213.69  5041.2  214.07    5049  215.17    5077   217.2  5108.2  218.87
  5127.5   220.4  5211.5  225.62  5250.7  228.69  5309.1  231.41  5327.7  232.73
#Mann= 5 ,-1 , 0
  4676.5     .17       0  4818.4     .11       0  4982.3     .07       0
  5032.2     .17       0  5127.5     .11       0
Bank Sta=4982.3,5032.2
XS Rating Curve= 0 ,0
Exp/Cntr=0.3,0.1

Type RM Length L Ch R = 1 ,13985   ,450,450,450
BEGIN DESCRIPTION:
EGYPT CREEK 26.0
END DESCRIPTION:
XS GIS Cut Line= 3
      3801567.83     10112711.09      3801877.14     10112442.44
      3802367.89     10112011.04
#Sta/Elev= 30
  4590.3  225.91  4640.2   223.4  4718.1  221.94  4775.1  218.49  4951.6  212.38
  4980.1  210.51  4987.7  208.78  4992.6  203.91  4996.1  203.91  4997.2  205.97
  5003.8  205.97  5008.6  208.26  5015.3  208.24  5022.9  209.77  5089.6  211.41
  5135.8  213.72  5164.2  212.99  5171.8  213.72  5178.5  211.82    5186  213.76
  5192.7  210.79  5200.3  213.96  5206.9  213.01  5221.2  214.88  5283.1  216.25
  5336.3  218.83  5462.2  222.96  5490.6  224.64  5560.9  226.32  5653.4  230.38
#Mann= 6 ,-1 , 0
  4590.3     .11       0  4980.1     .07       0  5022.9     .11       0
  5089.6     .17       0  5283.1     .11       0  5336.3     .17       0
#XS Ineff= 2 , 0
       0                  5135.8       0  213.72
Permanent Ineff=
       F       F
Bank Sta=4980.1,5022.9
XS Rating Curve= 0 ,0
Exp/Cntr=0.3,0.1

Type RM Length L Ch R = 1 ,13535   ,478,478,478
BEGIN DESCRIPTION:
EGYPT CREEK 25.0
END DESCRIPTION:
XS GIS Cut Line= 3
      3801817.84     10113061.08       3802123.5     10112809.62
      3802367.87     10112711.06
#Sta/Elev= 30
  4604.2  231.76  4607.5  231.76  4611.4  230.68  4660.9  226.81  4689.6  223.69
  4767.8  216.92  4802.9  214.96  4831.6  212.71  4895.5  210.54  4909.8  209.08
  4916.3  209.48  4938.5  208.26  4959.3  207.85  4980.2  205.88    4988  204.17
  5004.7  203.64  5007.8  202.79    5008  202.29  5011.5  202.29  5015.5  205.36
  5033.9  208.02  5063.5   209.6  5080.2  211.13    5093  210.84  5141.3  213.18
  5155.7  213.35    5195  215.57  5224.6  216.13  5231.1  216.97  5263.5  218.53
#Mann= 3 , 0 , 0
  4604.2     .11       0  4980.2     .07       0  5015.5     .17       0
Bank Sta=4980.2,5015.5
XS Rating Curve= 0 ,0
Exp/Cntr=0.3,0.1

Type RM Length L Ch R = 1 ,13057   ,494,494,494
BEGIN DESCRIPTION:
EGYPT CREEK 24.0
END DESCRIPTION:
XS GIS Cut Line= 3
      3802056.14     10113373.01      3802194.33      10113203.9
      3802358.21     10112999.09
#Sta/Elev= 30
  4781.6   221.4  4791.4  221.13  4812.2  218.85  4820.1  218.94  4826.6  217.97
  4834.5   217.8  4840.9   216.7  4855.3  216.33  4876.1   214.2  4926.2  211.14
  4954.3  208.11  4976.6  202.61  4990.7  200.72  4995.7  197.86  4999.2  197.86
    5000  199.02    5005  199.02  5011.8  202.87  5026.2  203.44  5032.6  201.79
  5040.6  203.22    5047  201.51  5054.8  202.57  5061.5   204.5  5094.3  206.24
  5125.5  208.57  5139.9  208.55  5175.1  211.17  5242.5   213.8  5262.3   214.4
#Mann= 5 ,-1 , 0
  4781.6     .11       0  4976.6     .09       0  5011.8     .17       0
  5094.3     .15       0  5242.5     .17       0
Bank Sta=4976.6,5011.8
XS Rating Curve= 0 ,0
Exp/Cntr=0.3,0.1

Type RM Length L Ch R = 1 ,12563   ,488,488,488
BEGIN DESCRIPTION:
EGYPT CREEK 23.0
END DESCRIPTION:
XS GIS Cut Line= 3
      3802167.85     10113661.07       3802423.5     10113554.94
      3802567.85     10113361.08
#Sta/Elev= 30
  4723.2  217.56  4744.9  216.12  4755.7  215.87  4785.6  213.27    4799  213.03
  4820.6  211.25  4831.5  211.07  4853.1  209.12    4868  208.61  4891.9   206.7
  4928.9  204.99  4950.6  202.95  4961.4  202.88  4968.9  201.87  4983.1  199.19
  4990.8  195.96    4991  195.46  4994.5  195.46  4994.8  195.96  4998.2  196.57
  5005.5  197.03  5019.6  199.96    5028  200.28  5034.2     202  5105.1  206.36
  5148.9  208.47  5178.1  209.03    5199  210.24  5219.8  210.41  5241.7  211.66
#Mann= 3 , 0 , 0
  4723.2     .11       0  4968.9     .09       0  5034.2     .17       0
Bank Sta=4968.9,5034.2
XS Rating Curve= 0 ,0
Exp/Cntr=0.3,0.1

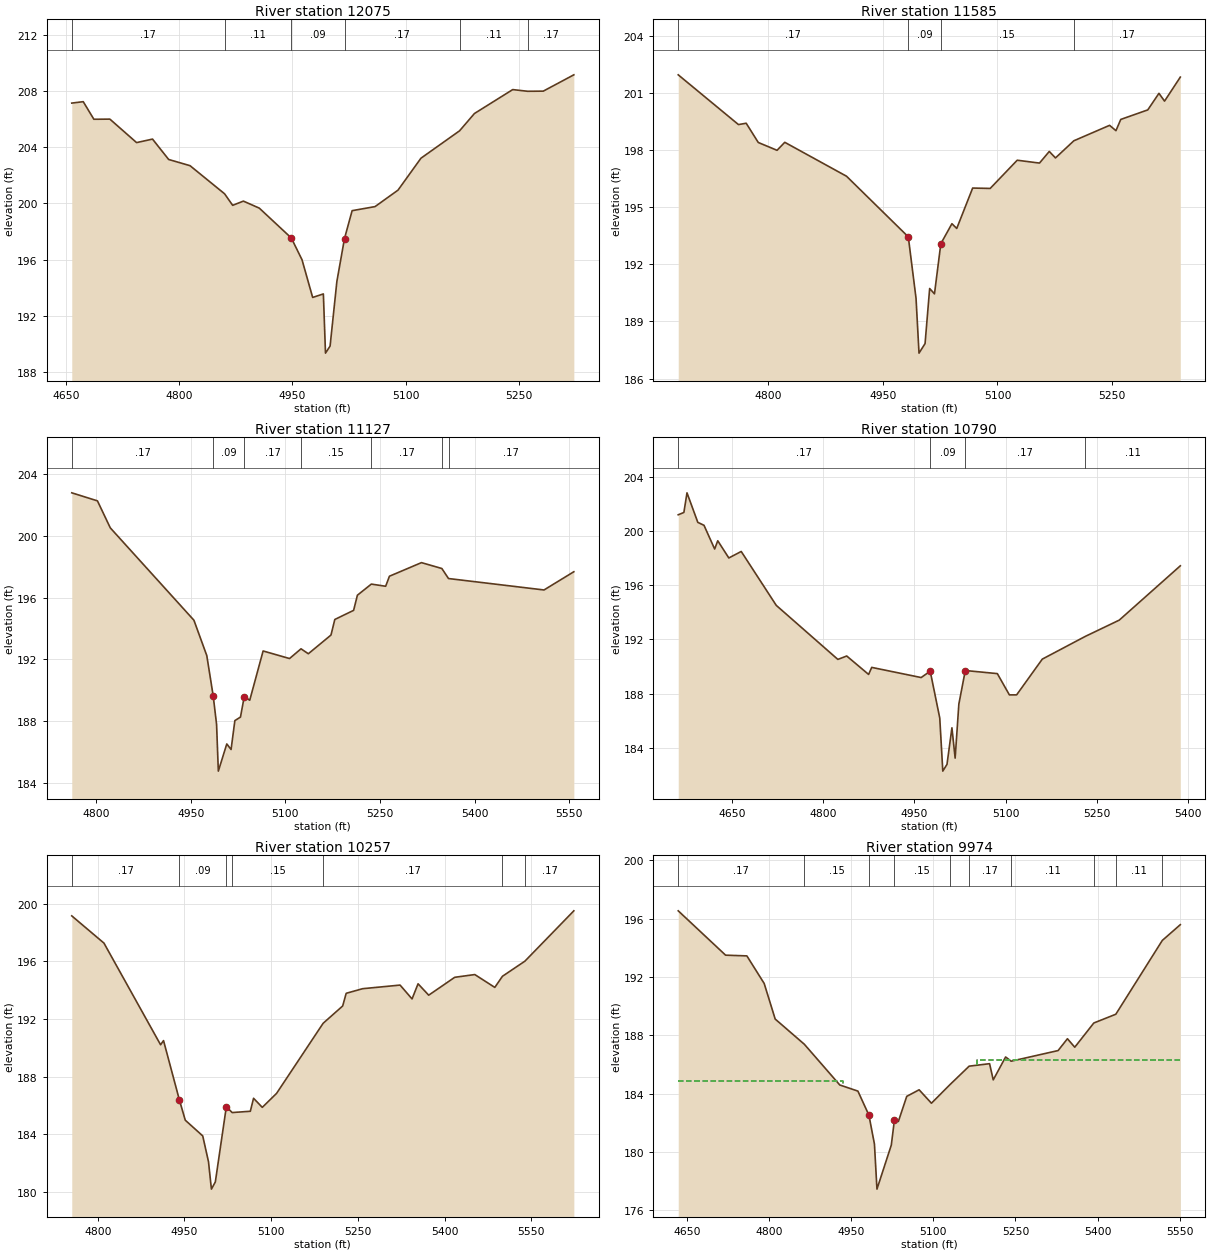
Type RM Length L Ch R = 1 ,12075   ,490,490,490
BEGIN DESCRIPTION:
EGYPT CREEK 22.0
END DESCRIPTION:
XS GIS Cut Line= 3
        3802474.     10114068.64      3802719.33     10113829.94
      3802667.85     10113511.07
#Sta/Elev= 30
  4657.7  207.13  4672.9  207.23    4687  205.98  4708.2  205.99  4743.6  204.32
  4764.7  204.57  4786.1  203.12  4814.4  202.68  4860.2  200.68  4870.9  199.86
  4885.1  200.16  4906.2  199.66  4948.6  197.54  4962.8  195.99  4976.9  193.31
  4991.1  193.56  4993.9  189.35    5000  189.85    5009  194.45  5019.1   197.5
  5029.2  199.48  5059.6  199.77    5090  200.94  5120.4  203.21  5171.6  205.16
  5191.3  206.39    5242  208.09  5261.8  207.97  5282.5  207.98    5323  209.14
#Mann= 6 ,-1 , 0
  4657.7     .17       0  4860.2     .11       0  4948.6     .09       0
  5019.1     .17       0  5171.6     .11       0  5261.8     .17       0
Bank Sta=4948.6,5019.1
XS Rating Curve= 0 ,0
Exp/Cntr=0.3,0.1

Type RM Length L Ch R = 1 ,11585   ,458,458,458
BEGIN DESCRIPTION:
EGYPT CREEK 21.0
END DESCRIPTION:
XS GIS Cut Line= 3
      3803149.28     10114169.13      3803190.14     10113854.68
      3802985.39     10113584.62
#Sta/Elev= 30
  4682.9  201.94  4761.6  199.33  4771.7   199.4  4787.5  198.39    4812  197.98
  4822.1   198.4  4902.8  196.62  4983.5  193.44  4993.6  190.22  4997.5  187.34
  5005.4  187.84  5011.4  190.73  5017.7  190.45    5026  193.08  5040.5  194.13
  5046.8  193.88  5067.6     196  5090.5  195.98  5125.8  197.46  5154.9  197.31
  5167.7  197.92  5175.8  197.58  5199.8  198.48  5246.5  199.29  5254.8  199.01
  5261.1   199.6  5296.4   200.1    5311  200.97  5318.3  200.56  5338.9  201.82
#Mann= 4 ,-1 , 0
  4682.9     .17       0  4983.5     .09       0    5026     .15       0
  5199.8     .17       0
Bank Sta=4983.5,5026
XS Rating Curve= 0 ,0
Exp/Cntr=0.3,0.1

Type RM Length L Ch R = 1 ,11127   ,337,337,337
BEGIN DESCRIPTION:
EGYPT CREEK 20.0
END DESCRIPTION:
XS GIS Cut Line= 3
      3803617.84     10114211.03      3803571.12     10113977.05
      3803256.11     10113517.08
#Sta/Elev= 30
  4761.4  202.79  4802.1  202.27  4822.5  200.52  4955.1  194.54  4975.5  192.25
  4985.7  189.63    4991   187.8  4993.8  184.77  5007.2  186.53    5014  186.17
    5020  188.04  5028.9  188.27  5034.9   189.6  5043.6  189.36  5064.8  192.55
  5106.7  192.06  5124.9  192.69  5136.5  192.37  5172.4  193.58  5178.5  194.59
  5208.3  195.18  5214.3  196.16  5236.4  196.88  5259.1  196.74  5265.1  197.39
  5315.9  198.27  5348.2  197.89  5358.8  197.24  5510.2   196.5  5557.5  197.68
#Mann= 7 ,-1 , 0
  4761.4     .17       0  4985.7     .09       0  5034.9     .17       0
  5124.9     .15       0  5236.4     .17       0  5348.2     .15       0
  5358.8     .17       0
Bank Sta=4985.7,5034.9
XS Rating Curve= 0 ,0
Exp/Cntr=0.3,0.1

Type RM Length L Ch R = 1 ,10790   ,533,533,533
BEGIN DESCRIPTION:
Mapping XS 4e243921
END DESCRIPTION:
XS GIS Cut Line= 3
      3803855.22      10114182.6        3803768.     10113752.96
      3803644.35     10113385.93
#Sta/Elev= 30
  4561.6  201.21  4570.9  201.38    4576  202.83  4593.8  200.65    4604  200.43
  4621.5  198.68  4626.6  199.29  4644.8  198.02  4665.2   198.5  4722.8  194.52
  4824.1  190.53  4838.7  190.78  4874.7  189.42  4879.8  189.94  4961.1  189.19
    4976  189.66  4991.7   186.2  4996.7  182.28  5003.6  182.78  5011.7  185.48
    5017  183.24  5023.1  187.23  5033.7  189.71  5086.4  189.48  5106.2  187.91
  5118.1  187.91  5160.3  190.55  5231.1  192.23  5286.9  193.43  5387.3  197.44
#Mann= 4 ,-1 , 0
  4561.6     .17       0    4976     .09       0  5033.7     .17       0
  5231.1     .11       0
Bank Sta=4976,5033.7
XS Rating Curve= 0 ,0
Exp/Cntr=0.3,0.1

Type RM Length L Ch R = 1 ,10257   ,283,283,283
BEGIN DESCRIPTION:
EGYPT CREEK 18.0
END DESCRIPTION:
XS GIS Cut Line= 3
       3804108.2     10114206.54      3804131.18     10113962.72
      3803967.86     10113361.09
#Sta/Elev= 30
  4755.1  199.16  4810.8  197.27  4908.7  190.22  4913.8  190.51  4941.4  186.37
  4951.4  184.99  4981.6   183.9  4991.6   182.1  4996.6  180.21  5003.4  180.71
  5022.4  185.92  5032.5  185.52  5063.9  185.61  5069.5  186.51  5084.6  185.88
  5109.3  186.85  5189.8  191.71  5223.6  192.91  5229.7  193.79  5258.2  194.11
  5322.9  194.36  5343.6   193.4    5354  194.45  5372.4  193.66  5417.4   194.9
  5452.1  195.09  5486.7   194.2  5499.9  194.97  5538.8  196.02  5623.4  199.51
#Mann= 7 ,-1 , 0
  4755.1     .17       0  4941.4     .09       0  5022.4     .17       0
  5032.5     .15       0  5189.8     .17       0  5499.9     .11       0
  5538.8     .17       0
Bank Sta=4941.4,5022.4
XS Rating Curve= 0 ,0
Exp/Cntr=0.3,0.1

Type RM Length L Ch R = 1 ,9974    ,309,309,309
BEGIN DESCRIPTION:
Mapping XS dcce27e6
END DESCRIPTION:
XS GIS Cut Line= 3
      3804378.23     10114196.92      3804334.66     10113833.52
      3804094.38     10113337.56
#Sta/Elev= 30
    4634  196.54  4720.5   193.5  4759.4  193.45    4791  191.56  4811.1  189.12
  4864.4  187.39  4929.1   184.6  4962.2  184.18  4982.3  182.53  4992.4  180.55
    4997  177.46  5023.2  180.48  5028.8  182.17  5036.1   182.1  5051.4  183.82
    5074  184.27  5096.5  183.35  5130.8  184.64  5165.4  185.89  5202.7  186.06
  5209.4  184.95    5232  186.52  5242.1  186.23  5327.9  186.96  5344.9  187.77
  5358.3  187.19  5393.1  188.85  5433.3  189.45  5518.2  194.51  5551.1  195.59
#Mann= 10 ,-1 , 0
    4634     .17       0  4864.4     .15       0  4982.3     .09       0
  5028.8     .15       0  5130.8     .11       0  5165.4     .17       0
  5242.1     .11       0  5393.1     .17       0  5433.3     .11       0
  5518.2     .17       0
#XS Ineff= 2 , 0
       0  4934.1  184.88  5180.5       0  186.31
Permanent Ineff=
       F       F
Bank Sta=4982.3,5028.8
XS Rating Curve= 0 ,0
Exp/Cntr=0.3,0.1

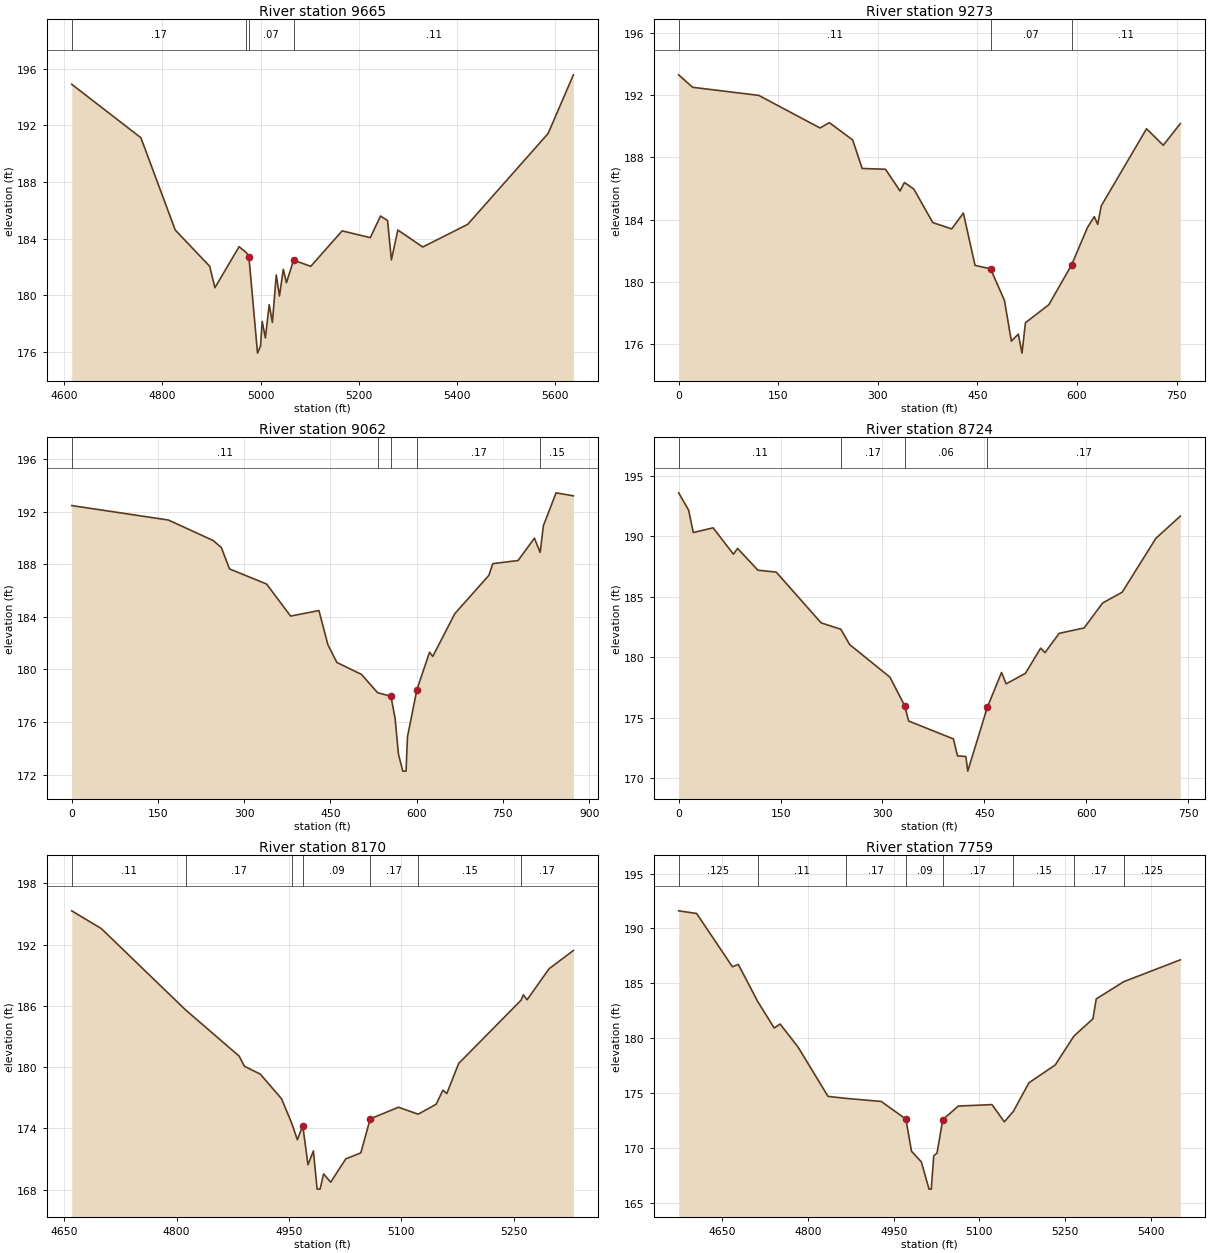
Type RM Length L Ch R = 1 ,9665    ,392,392,392
BEGIN DESCRIPTION:
EGYPT CREEK 17.0
END DESCRIPTION:
XS GIS Cut Line= 3
      3804573.36      10114181.9      3804586.05     10113797.41
      3804181.52     10113304.57
#Sta/Elev= 30
  4615.3  194.91  4756.2  191.13  4826.2   184.6  4896.3  182.04  4907.1  180.52
  4956.3  183.42  4971.4  182.99  4976.3  182.72  4993.9  175.89    5000  176.39
  5003.4  178.13  5009.9  176.97  5017.7  179.32  5024.2  178.07  5032.1  181.42
  5038.6  179.93  5046.4  181.82  5052.9  180.87  5067.3  182.47  5102.4  182.03
  5166.3  184.54  5223.7  184.06  5244.5  185.59  5258.9  185.27  5266.7  182.49
  5279.9   184.6  5330.6   183.4  5422.2     185  5586.1  191.43  5637.6  195.58
#Mann= 4 ,-1 , 0
  4615.3     .17       0  4971.4     .11       0  4976.3     .07       0
  5067.3     .11       0
#XS Ineff= 2 ,-1
  5166.3  5244.5  184.54  5244.5  5450.4  185.59
Permanent Ineff=
       F       F
Bank Sta=4976.3,5067.3
XS Rating Curve= 0 ,0
Exp/Cntr=0.3,0.1

Type RM Length L Ch R = 1 ,9273    ,211,211,211
BEGIN DESCRIPTION:
EGYPT CREEK 17.8
END DESCRIPTION:
XS GIS Cut Line= 4
      3804631.24      10114134.4       3804910.1      10113814.3
      3804872.12      10113690.6      3804926.38     10113496.38
#Sta/Elev= 30
       0   193.3      21   192.5   120.7  191.98   212.8  189.89     227  190.23
   262.1  189.12   276.4  187.29   311.5  187.24   333.4  185.85     340  186.39
   354.2  185.97   382.7  183.82   411.2  183.41   428.8  184.43   446.4  181.07
   469.8  180.85   490.7  178.82   501.1  176.21   511.6  176.66   517.1  175.44
   522.3  177.39   557.6  178.55   591.8   181.1   615.7   183.5     626   184.2
   631.1   183.7   636.5  184.89   704.7  189.84   729.9  188.78   755.6  190.17
#Mann= 3 , 0 , 0
       0     .11       0   469.8     .07       0   591.8     .11       0
Bank Sta=469.8,591.8
XS Rating Curve= 0 ,0
Exp/Cntr=0.3,0.1

Type RM Length L Ch R = 1 ,9062    ,338,338,338
BEGIN DESCRIPTION:
EGYPT CREEK 17.5
END DESCRIPTION:
XS GIS Cut Line= 4
      3804644.26     10114145.25      3804925.29     10113827.32
      3805058.35     10113748.28      3805317.85     10113611.07
#Sta/Elev= 30
       0  192.47   168.2  191.37     246  189.81   260.2  189.28   274.4  187.65
   338.9   186.5   380.7  184.06     430  184.48   445.6  181.88   461.2  180.53
     504  179.62     532  178.23   555.2  177.96   562.5  176.26   568.3  173.55
   575.9  172.26   581.5  172.26     584  174.88   600.4  178.47   622.4  181.31
     628  180.99   666.4  184.25   725.6  187.16   732.4  188.05   776.4  188.29
   804.8  189.99   814.8  188.91   820.4  190.94   842.5  193.44   872.6  193.21
#Mann= 5 ,-1 , 0
       0     .11       0     532     .17       0   555.2     .09       0
   600.4     .17       0   814.8     .15       0
Bank Sta=555.2,600.4
XS Rating Curve= 0 ,0
Exp/Cntr=0.3,0.1

Type RM Length L Ch R = 1 ,8724    ,554,554,554
BEGIN DESCRIPTION:
EGYPT CREEK 15.0
END DESCRIPTION:
XS GIS Cut Line= 3
      3804935.06     10114408.92      3805171.47     10114058.52
      3805417.85     10113861.07
#Sta/Elev= 30
       0  193.58    14.7  192.14    21.5   190.3    50.7  190.69    80.6  188.51
    86.7  188.99   116.6  187.19   143.6  187.03   209.6  182.84   238.7  182.31
   251.6  181.05     311  178.35   332.5  176.01   338.5  174.73   404.4  173.25
   410.4  171.85   422.7   171.8   425.5  170.59   454.3  175.86   475.2  178.74
   482.1   177.8   510.4  178.67   532.8  180.75   539.2  180.38     560  181.97
   596.8  182.42     624  184.48   652.8  185.37   702.4  189.82   738.4  191.66
#Mann= 4 ,-1 , 0
       0     .11       0   238.7     .17       0   332.5     .06       0
   454.3     .17       0
Bank Sta=332.5,454.3
XS Rating Curve= 0 ,0
Exp/Cntr=0.3,0.1

Type RM Length L Ch R = 1 ,8170    ,411,411,411
BEGIN DESCRIPTION:
EGYPT CREEK 14.0
END DESCRIPTION:
XS GIS Cut Line= 3
      3805253.84     10114452.93      3805498.23     10114216.84
      3805466.51     10113888.67
#Sta/Elev= 30
  4660.2   195.3  4699.7  193.56  4812.2  185.59  4883.6  181.07  4890.6  180.08
  4911.9   179.3  4940.2  176.89  4953.8  174.49  4961.3  172.88  4968.5  174.25
  4975.5  170.43  4982.7  171.78  4987.7  168.04  4991.6  168.04  4996.3  169.53
  5005.8  168.72  5025.9     171    5046  171.59  5058.5  174.92  5096.2  176.06
  5122.5  175.38  5146.5  176.35  5155.6  177.74  5160.7   177.4  5176.6  180.35
  5259.8  186.54  5262.9  187.07  5267.9  186.59  5297.2  189.62  5329.7  191.42
#Mann= 7 ,-1 , 0
  4660.2     .11       0  4812.2     .17       0  4953.8     .11       0
  4968.5     .09       0  5058.5     .17       0  5122.5     .15       0
  5259.8     .17       0
Bank Sta=4968.5,5058.5
XS Rating Curve= 0 ,0
Exp/Cntr=0.3,0.1

Type RM Length L Ch R = 1 ,7759    ,191,191,191
BEGIN DESCRIPTION:
EGYPT CREEK 13.0
END DESCRIPTION:
XS GIS Cut Line= 3
      3805667.86     10114711.05      3805792.57     10114302.99
      3806017.83     10113911.11
#Sta/Elev= 30
  4573.3  191.61  4604.7  191.37  4667.4  186.51  4677.8  186.72  4711.6  183.35
  4740.6  180.92    4751  181.28  4782.4  179.18  4834.9  174.68  4866.3   174.5
  4928.1  174.22  4971.3  172.61  4981.1  169.68  4998.4   168.7  5011.8  166.22
  5015.7  166.22  5020.1  169.26  5025.8  169.51  5035.9  172.56  5063.2   173.8
  5122.1  173.93  5143.7  172.36  5159.6  173.32  5186.8  175.92  5232.9  177.55
  5265.7  180.19  5298.9  181.76  5304.7  183.57  5352.6  185.14    5452  187.14
#Mann= 8 ,-1 , 0
  4573.3    .125       0  4711.6     .11       0  4866.3     .17       0
  4971.3     .09       0  5035.9     .17       0  5159.6     .15       0
  5265.7     .17       0  5352.6    .125       0
Bank Sta=4971.3,5035.9
XS Rating Curve= 0 ,0
Exp/Cntr=0.3,0.1

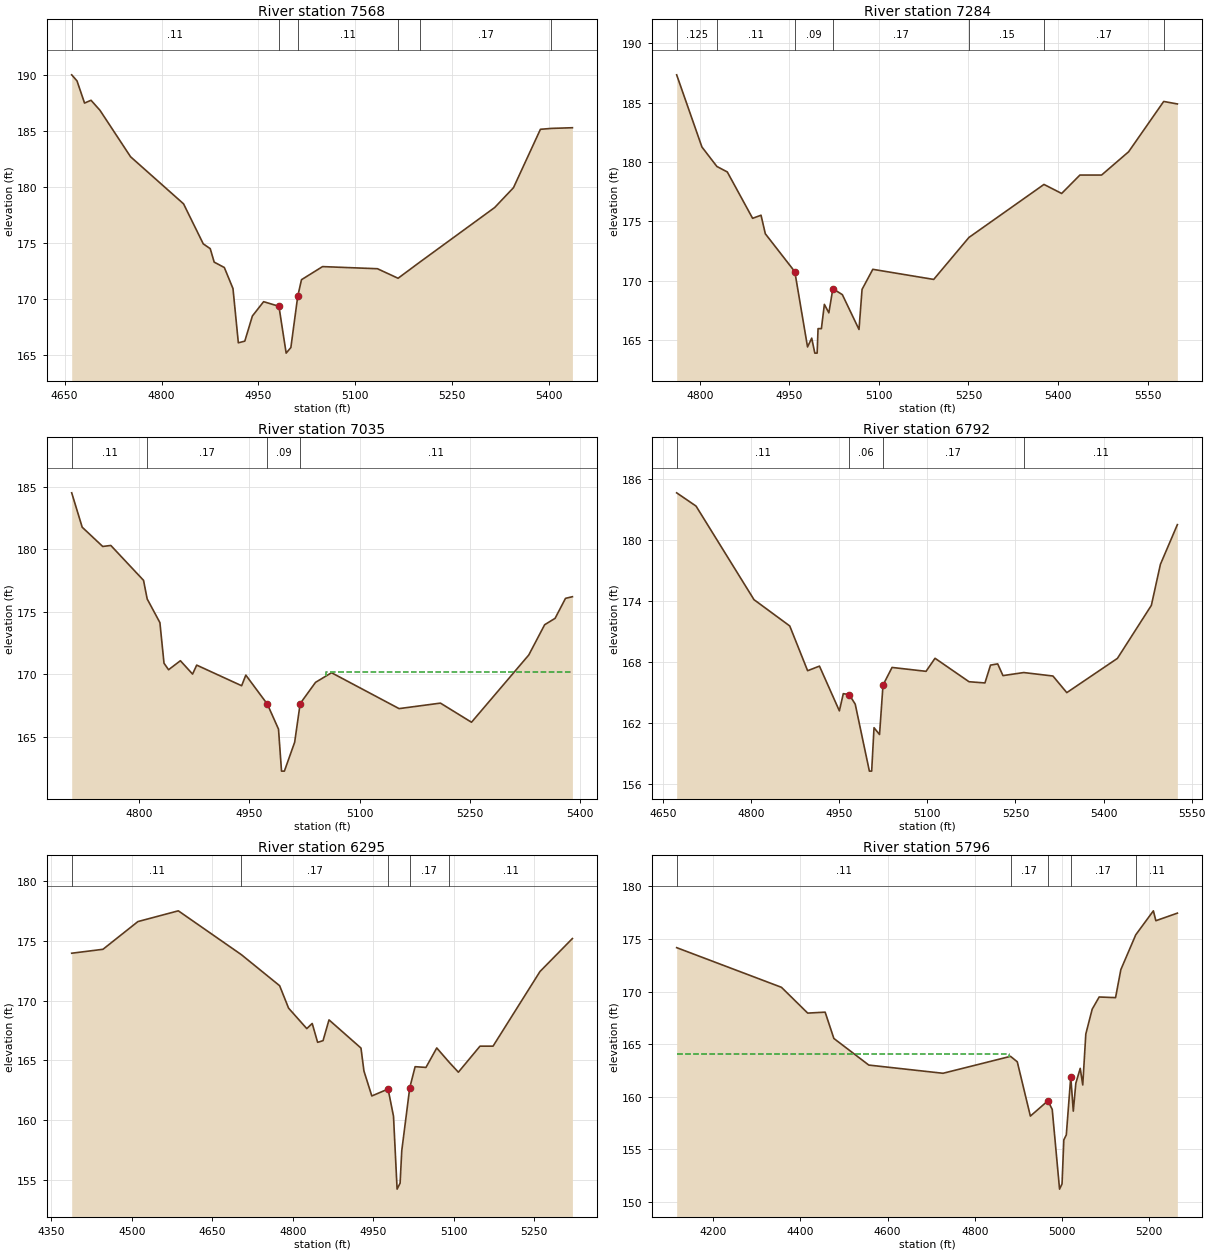
Type RM Length L Ch R = 1 ,7568    ,284,284,284
BEGIN DESCRIPTION:
Mapping XS e4f3612e
END DESCRIPTION:
XS GIS Cut Line= 3
      3805806.86     10114738.63      3805938.81     10114426.12
      3806110.18     10114025.57
#Sta/Elev= 30
    4661  190.01  4669.2  189.47  4680.9  187.49  4690.9  187.74  4704.7  186.85
  4752.1   182.7  4834.1   178.5  4864.6  174.93  4875.4   174.5  4881.5   173.3
  4897.2  172.82  4910.6  170.94  4918.9   166.1  4928.9  166.25  4940.6  168.49
    4958  169.77  4981.7  169.36  4992.9  165.18  5000.2  165.68  5010.8  170.24
  5016.6  171.73  5049.2   172.9  5134.2  172.71  5166.1  171.86  5199.3  173.28
  5315.6  178.17  5344.7  179.94  5386.4  185.15  5403.3  185.23  5435.9  185.29
#Mann= 6 ,-1 , 0
    4661     .11       0  4981.7     .07       0  5010.8     .11       0
  5166.1     .15       0  5199.3     .17       0  5403.3    .125       0
Bank Sta=4981.7,5010.8
XS Rating Curve= 0 ,0
Exp/Cntr=0.3,0.1

Type RM Length L Ch R = 1 ,7284    ,249,249,249
BEGIN DESCRIPTION:
EGYPT CREEK 12.0
END DESCRIPTION:
XS GIS Cut Line= 4
      3805917.89     10114811.04      3806087.88     10114643.61
      3806103.97     10114625.41      3806217.85     10114061.08
#Sta/Elev= 30
  4761.4  187.33  4803.7  181.26  4828.8  179.62  4846.2  179.16  4888.6  175.26
  4902.7  175.52  4909.9  173.96  4959.3  170.77  4980.6  164.44  4987.6  165.18
  4992.8  163.92  4996.7  163.92  4998.2  165.98  5003.8  165.98  5008.8  168.02
  5016.3  167.31    5023  169.34  5038.9  168.84  5066.8  165.91  5071.9  169.28
  5089.9  170.97  5191.9  170.12  5250.9  173.65  5376.6  178.11  5406.2  177.35
  5436.8   178.9  5473.1   178.9  5518.4  180.86  5577.1  185.09    5600  184.88
#Mann= 7 ,-1 , 0
  4761.4    .125       0  4828.8     .11       0  4959.3     .09       0
    5023     .17       0  5250.9     .15       0  5376.6     .17       0
  5577.1    .125       0
Bank Sta=4959.3,5023
XS Rating Curve= 0 ,0
Exp/Cntr=0.3,0.1

Type RM Length L Ch R = 1 ,7035    ,243,243,243
BEGIN DESCRIPTION:
Mapping XS affaeb7a
END DESCRIPTION:
XS GIS Cut Line= 3
      3806000.19      10114912.6      3806260.76     10114780.59
      3806552.28     10114521.97
#Sta/Elev= 30
  4707.9  184.52  4722.2  181.77  4750.1  180.23  4761.2  180.31  4805.7  177.52
  4810.7  176.03    4828  174.14  4833.6  170.89  4839.8  170.37  4855.9  171.09
  4872.5  170.02  4878.1  170.74  4939.3  169.09    4945  169.94  4974.3  167.62
  4989.5  165.62  4993.6  162.26  4997.5  162.26  5011.5  164.57    5019  167.66
  5039.9  169.36  5061.7  170.13  5153.7  167.26    5210   167.7  5252.3  166.17
  5330.3  171.55  5351.9  173.97  5366.1  174.48  5380.3  176.08  5389.7  176.21
#Mann= 4 ,-1 , 0
  4707.9     .11       0  4810.7     .17       0  4974.3     .09       0
    5019     .11       0
#XS Ineff= 2 , 0
       0    4945  169.94  5054.1       0  170.16
Permanent Ineff=
       F       T
Bank Sta=4974.3,5019
XS Rating Curve= 0 ,0
Exp/Cntr=0.3,0.1

Type RM Length L Ch R = 1 ,6792    ,497,497,497
BEGIN DESCRIPTION:
EGYPT CREEK 11.0
END DESCRIPTION:
XS GIS Cut Line= 3
      3806017.88     10115061.07      3806340.49     10115007.67
      3806617.84     10114561.09
#Sta/Elev= 30
    4673   184.6    4706   183.3  4804.7  174.12  4865.6  171.54    4896  167.15
  4916.2   167.6  4950.1  163.21  4956.8   164.9  4966.9   164.8  4977.1  163.87
  5001.2   157.3  5005.1   157.3  5009.1  161.56  5018.5  160.89  5024.4  165.74
  5039.8  167.47  5097.7  167.09    5113  168.37  5170.9  166.07    5198  165.95
  5207.5   167.7  5219.7  167.82  5228.7  166.67    5264  166.97  5313.8  166.63
  5337.4     165  5423.6  168.36  5481.4  173.56  5496.8  177.58  5525.7  181.48
#Mann= 4 ,-1 , 0
    4673     .11       0  4966.9     .06       0  5024.4     .17       0
    5264     .11       0
#XS Ineff= 2 , 0
       0                    5113       0  168.37
Permanent Ineff=
       F       T
Bank Sta=4966.9,5024.4
XS Rating Curve= 0 ,0
Exp/Cntr=0.3,0.1

Type RM Length L Ch R = 1 ,6295    ,499,499,499
BEGIN DESCRIPTION:
EGYPT CREEK 10.0
END DESCRIPTION:
XS GIS Cut Line= 3
       3806564.6     10115494.58      3806652.47     10114888.92
      3806690.47     10114570.08
#Sta/Elev= 30
    4388  173.96  4446.3  174.29  4511.4  176.61  4586.7  177.51  4704.2  173.84
  4775.5  171.24  4792.2  169.36  4826.1  167.65  4836.2  168.08  4846.3   166.5
  4856.4  166.64  4867.5  168.38  4927.1  166.02  4932.6   164.1  4947.3  162.01
  4977.6  162.59  4987.7  160.31  4994.4  154.21    5000  154.71  5003.1  157.43
    5018   162.7    5028  164.46  5048.2   164.4  5068.3  166.03  5090.9  164.86
  5108.6     164  5148.9  166.18  5173.2  166.18  5260.7  172.43  5321.1  175.19
#Mann= 5 ,-1 , 0
    4388     .11       0  4704.2     .17       0  4977.6     .09       0
    5018     .17       0  5090.9     .11       0
#XS Ineff= 2 , 0
       0  4867.5  168.38               0
Permanent Ineff=
       F       F
Bank Sta=4977.6,5018
XS Rating Curve= 0 ,0
Exp/Cntr=0.3,0.1

Type RM Length L Ch R = 1 ,5796    ,506,506,506
BEGIN DESCRIPTION:
EGYPT CREEK 9.0
END DESCRIPTION:
XS GIS Cut Line= 3
      3806917.85     10115861.09      3806960.25      10114978.6
      3807089.76     10114748.09
#Sta/Elev= 30
  4116.5  174.18  4356.8  170.41  4416.9  167.96  4456.9  168.05  4476.9  165.55
    4557  163.02  4727.2  162.24  4881.9  163.85  4897.4  163.33  4927.4  158.17
  4967.5  159.62  4977.5  158.81  4994.3  151.23    5000  151.73  5004.1  155.91
  5009.8  156.39    5020  161.91  5025.8  158.64  5031.6  161.29  5041.7  162.71
  5047.5  161.13  5054.5  165.97  5069.1  168.33  5085.1  169.49  5122.7  169.43
  5134.8  172.09    5169   175.4  5209.4  177.68  5215.1  176.74  5264.4  177.46
#Mann= 5 ,-1 , 0
  4116.5     .11       0  4881.9     .17       0  4967.5     .09       0
    5020     .17       0    5169     .11       0
#XS Ineff= 2 , 0
       0  4877.4  164.06               0
Permanent Ineff=
       T       F
Bank Sta=4967.5,5020
XS Rating Curve= 0 ,0
Exp/Cntr=0.3,0.1