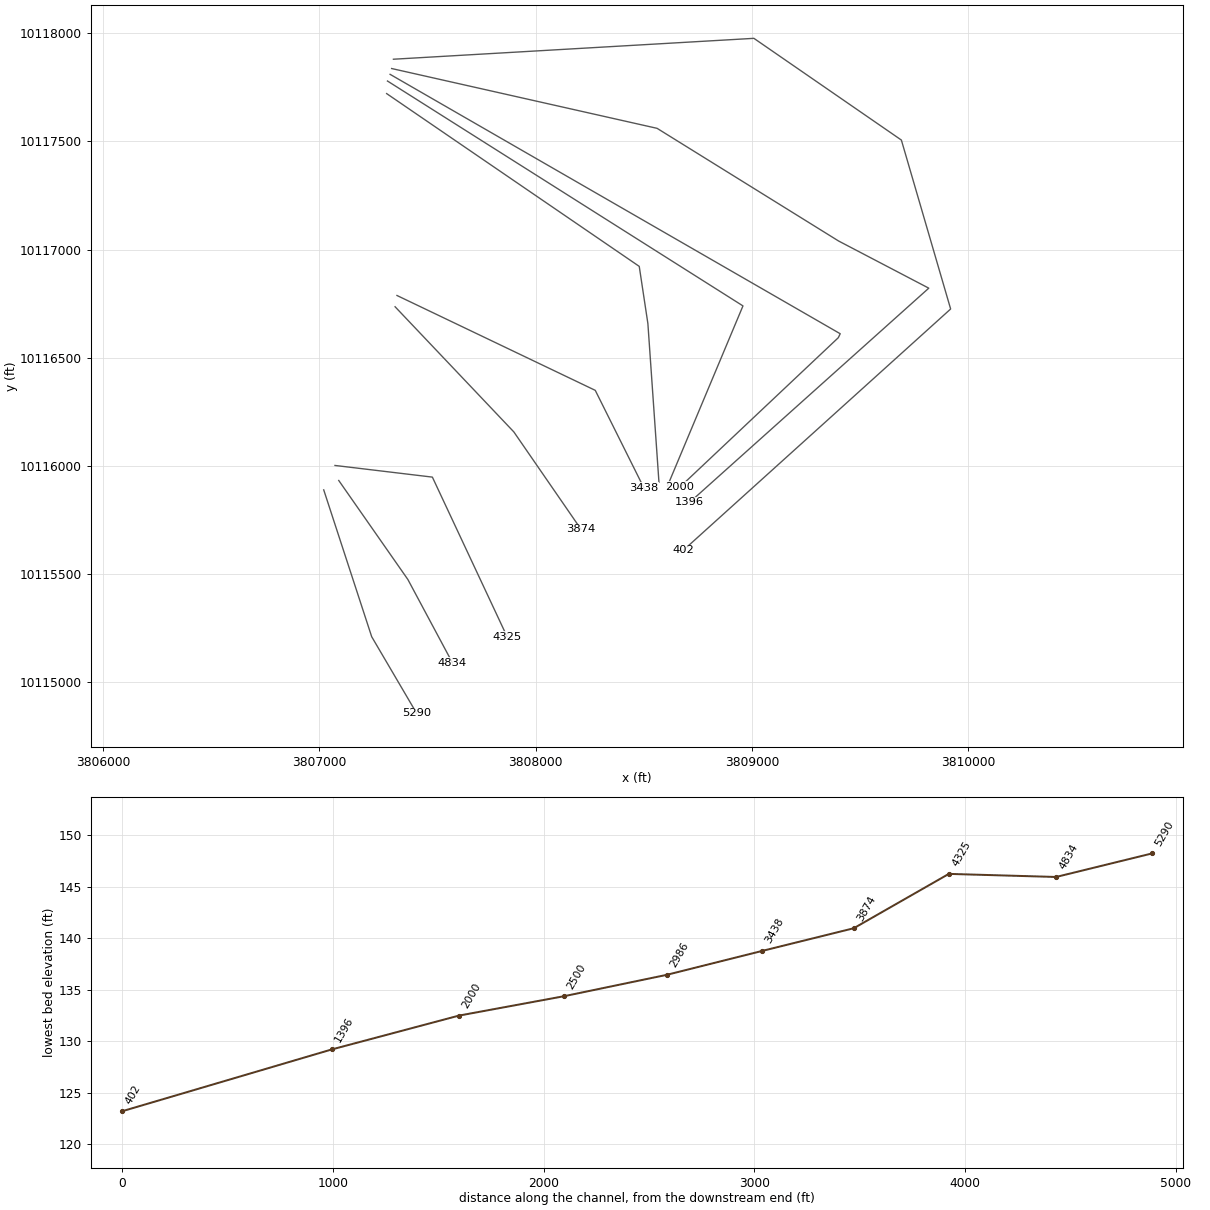
HEC-RAS study EGYPT CREEK.prj: EGYPT CREEK Base Level Engineering

--- EGYPT CREEK.g01 (geometry) --- (continued)

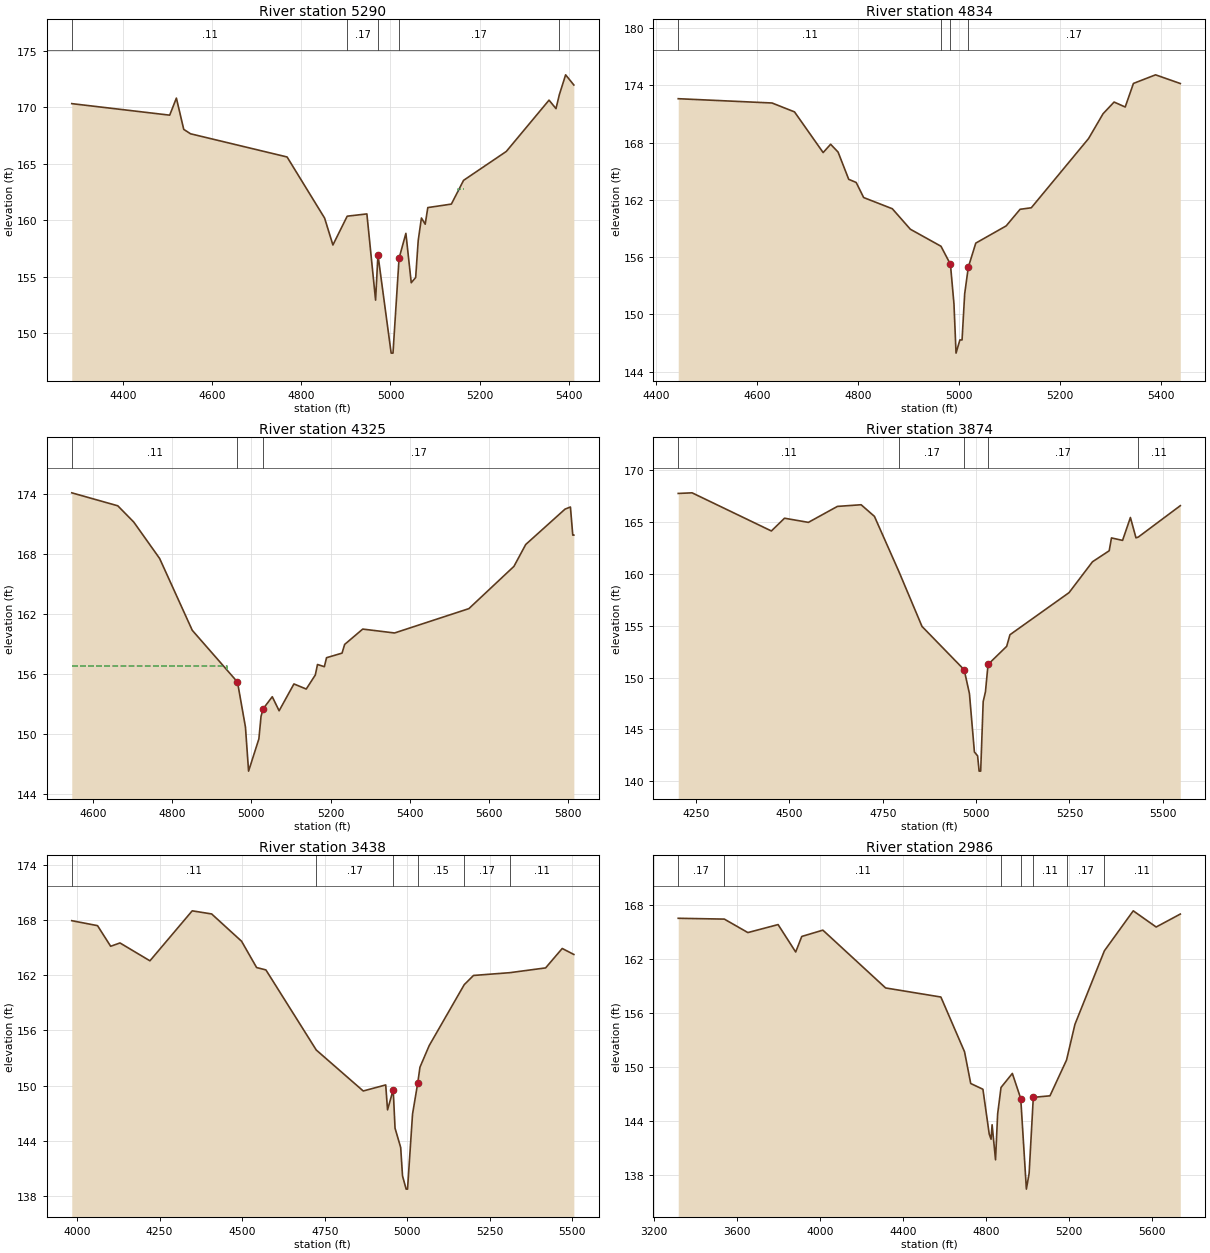
Type RM Length L Ch R = 1 ,5290    ,456,456,456
BEGIN DESCRIPTION:
EGYPT CREEK 8.0
END DESCRIPTION:
XS GIS Cut Line= 3
      3807020.32      10115889.6      3807242.05      10115210.8
      3807450.04     10114856.54
#Sta/Elev= 30
  4285.9  170.32  4505.3   169.3  4520.3  170.81  4536.8  168.04  4552.2  167.65
  4768.3   165.6  4852.4  160.19    4871  157.81    4903  160.36  4947.1  160.56
  4966.6  152.93  4971.9  156.95  5001.5  148.24  5005.6  148.24  5019.2  156.63
  5034.5  158.84  5046.5  154.47  5056.4  154.93  5062.1   158.2  5069.3   160.2
  5077.8  159.65  5083.6  161.12  5136.4  161.43  5163.7  163.53  5259.5  166.09
  5355.2  170.63  5370.8  169.88  5378.3  171.11  5392.4  172.87  5410.8  171.97
#Mann= 5 ,-1 , 0
  4285.9     .11       0    4903     .17       0  4971.9     .09       0
  5019.2     .17       0  5378.3     .11       0
#XS Ineff= 2 ,-1
  5150.4  5163.7  162.78  5163.7  5179.4  163.53
Permanent Ineff=
       F       F
Bank Sta=4971.9,5019.2
XS Rating Curve= 0 ,0
Exp/Cntr=0.3,0.1

Type RM Length L Ch R = 1 ,4834    ,509,509,509
BEGIN DESCRIPTION:
EGYPT CREEK 7.0
END DESCRIPTION:
XS GIS Cut Line= 3
       3807089.8     10115932.94      3807409.23     10115475.39
      3807614.93     10115090.98
#Sta/Elev= 30
    4444  172.59  4629.7  172.14  4674.2  171.21  4730.9  166.95  4745.7  167.82
  4760.5     167  4781.5  164.15  4796.3  163.82  4811.1  162.24  4867.8  161.07
  4903.6  158.92  4964.2  157.14  4982.9  155.25  4989.9  151.09    4994  145.95
  5001.6  147.33  5005.9  147.33  5011.1  152.16  5018.3  154.95  5033.1  157.47
  5093.2  159.27  5120.8  161.01    5143  161.17  5256.4  168.42    5285  171.01
  5306.9  172.24  5328.9  171.72  5345.2  174.19    5389  175.09    5438  174.18
#Mann= 4 ,-1 , 0
    4444     .11       0  4964.2     .17       0  4982.9     .09       0
  5018.3     .17       0
Bank Sta=4982.9,5018.3
XS Rating Curve= 0 ,0
Exp/Cntr=0.3,0.1

Type RM Length L Ch R = 1 ,4325    ,451,451,451
BEGIN DESCRIPTION:
EGYPT CREEK 6.0
END DESCRIPTION:
XS GIS Cut Line= 3
      3807072.43     10116002.42      3807522.52     10115948.53
      3807867.85     10115211.08
#Sta/Elev= 30
  4546.7  174.15  4662.9  172.85  4703.2  171.22  4768.5  167.57  4850.9  160.37
  4965.1  155.18  4985.2  150.67  4993.1  146.25  5019.1  149.48  5024.6  151.76
  5030.3  152.52  5052.9  153.71  5070.2   152.3  5107.6  154.99  5138.7  154.48
  5161.6  155.89  5167.1  156.94  5184.4  156.72  5189.9  157.62  5229.1  158.08
  5235.6  158.95  5281.3  160.49  5361.6   160.1  5549.3  162.54  5663.1  166.78
  5692.8  168.97  5792.2  172.52  5805.7  172.73  5811.6  169.91  5814.3  169.91
#Mann= 3 , 0 , 0
  4546.7     .11       0  4965.1     .06       0  5030.3     .17       0
#XS Ineff= 2 , 0
       0  4938.2  156.76               0
Permanent Ineff=
       F       F
Bank Sta=4965.1,5030.3
XS Rating Curve= 0 ,0
Exp/Cntr=0.3,0.1

Type RM Length L Ch R = 1 ,3874    ,436,436,436
BEGIN DESCRIPTION:
EGYPT CREEK 5.0
END DESCRIPTION:
XS GIS Cut Line= 3
      3807350.18     10116735.93      3807899.08     10116157.39
      3808209.56     10115707.28
#Sta/Elev= 30
  4202.5  167.76  4239.6  167.82  4451.9  164.14  4487.1  165.37    4551  164.97
  4628.7  166.51  4692.2  166.67  4727.8  165.55  4793.6   160.2  4855.2  154.93
  4968.1  150.75  4982.2  148.45  4995.5  142.82  5004.1  142.44  5008.1  140.97
  5012.3  140.97    5019  147.68  5025.1  148.63    5032  151.26  5081.9  153.01
  5090.7  154.13  5248.9  158.19  5311.7  161.17  5356.4  162.23  5362.5  163.47
  5392.2  163.23  5413.2  165.44  5428.1  163.48  5434.2  163.55  5546.8  166.58
#Mann= 5 ,-1 , 0
  4202.5     .11       0  4793.6     .17       0  4968.1     .09       0
    5032     .17       0  5434.2     .11       0
Bank Sta=4968.1,5032
XS Rating Curve= 0 ,0
Exp/Cntr=0.3,0.1

Type RM Length L Ch R = 1 ,3438    ,452,452,452
BEGIN DESCRIPTION:
EGYPT CREEK 4.0
END DESCRIPTION:
XS GIS Cut Line= 3
      3807358.85     10116788.02      3808275.38     10116349.57
      3808500.37     10115898.24
#Sta/Elev= 30
    3984  167.92    4062  167.38  4101.8  165.14    4130   165.5  4220.7  163.56
  4348.7  168.99  4407.6  168.65  4498.3  165.68  4543.7  162.83  4571.9  162.57
  4724.4  153.87  4866.6  149.42  4934.6  150.08  4940.2  147.37  4957.3  149.56
  4962.9  145.38    4980  143.28  4985.5   140.2  4996.5  138.76  5000.7  138.76
  5015.9  146.92  5031.8  150.33  5038.3     152  5066.3  154.35  5172.4  160.97
  5200.5  161.97  5310.1  162.27  5418.8  162.79  5469.1   164.9  5504.3  164.25
#Mann= 6 ,-1 , 0
    3984     .11       0  4724.4     .17       0  4957.3     .09       0
  5031.8     .15       0  5172.4     .17       0  5310.1     .11       0
Bank Sta=4957.3,5031.8
XS Rating Curve= 0 ,0
Exp/Cntr=0.3,0.1

Type RM Length L Ch R = 1 ,2986    ,486,486,486
BEGIN DESCRIPTION:
EGYPT CREEK 3.0
END DESCRIPTION:
XS GIS Cut Line= 4
      3807311.15     10117721.15      3808478.66     10116922.56
      3808518.61     10116658.17      3808569.75     10115925.15
#Sta/Elev= 30
  3318.1  166.57  3539.9  166.48  3653.3  164.98  3798.7  165.87  3883.5  162.82
  3912.7  164.55  4014.3  165.25  4316.3  158.82  4582.4  157.81  4696.2  151.72
    4726  148.19  4784.7  147.55    4815  142.57  4823.8  141.99  4828.9   143.6
  4845.4   139.7  4855.5  144.79  4871.8  147.75  4926.3  149.31  4966.7  146.52
  4993.9  136.44  5007.1   138.2  5027.2  146.65  5107.4  146.82  5187.2   150.8
  5227.6  154.77  5369.3  162.95  5508.3   167.4  5618.6   165.6  5734.8  167.04
#Mann= 7 ,-1 , 0
  3318.1     .17       0  3539.9     .11       0  4871.8     .17       0
  4966.7     .09       0  5027.2     .11       0  5187.2     .17       0
  5369.3     .11       0
#XS Ineff= 2 , 0
       0  4926.3  149.31               0
Permanent Ineff=
       T       F
Bank Sta=4966.7,5027.2
XS Rating Curve= 0 ,0
Exp/Cntr=0.3,0.1

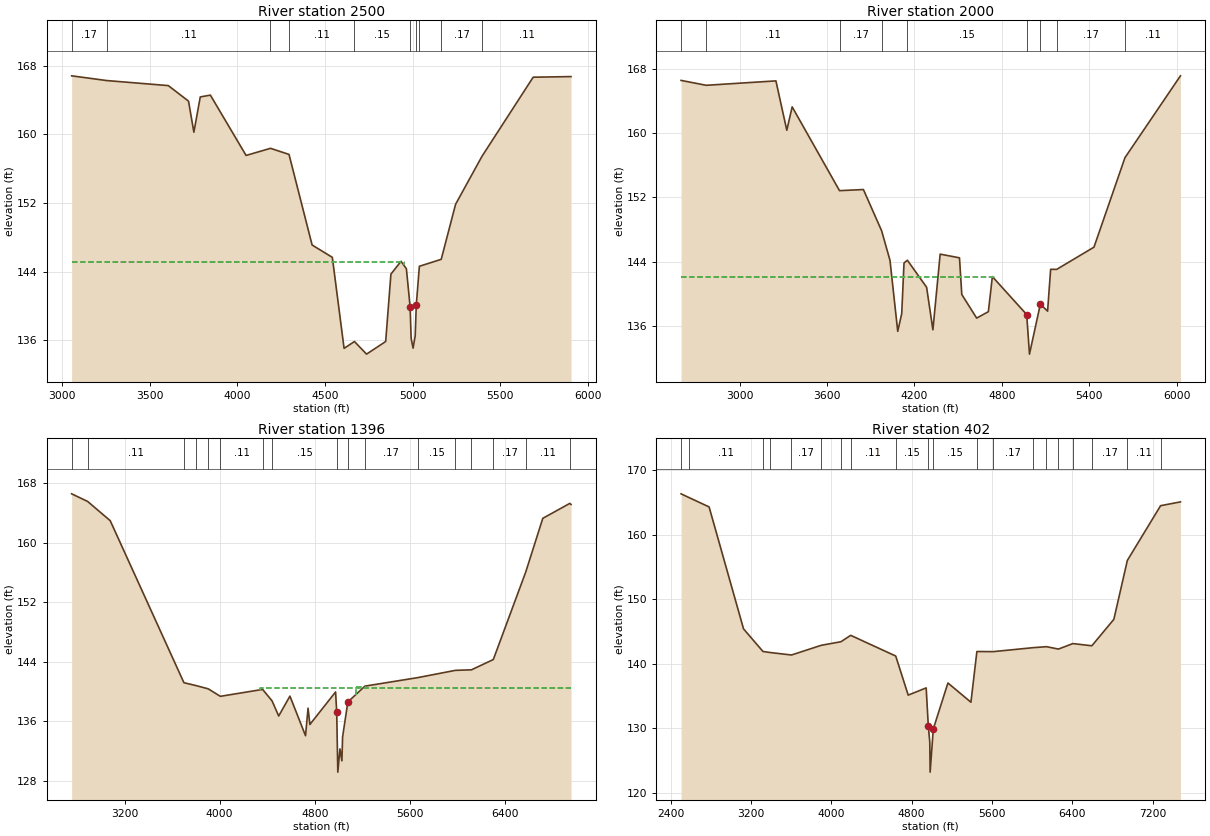
Type RM Length L Ch R = 1 ,2500    ,500,500,500
BEGIN DESCRIPTION:
EGYPT CREEK 4.5
END DESCRIPTION:
XS GIS Cut Line= 3
      3807315.02     10117779.26      3808958.06     10116739.88
      3808609.22     10115907.63
#Sta/Elev= 30
  3055.8  166.81  3255.5  166.26  3606.8  165.67  3722.1  163.86  3752.6  160.24
  3789.1  164.35  3846.7  164.56  4050.2  157.53  4189.3  158.36  4294.9  157.65
  4426.6  147.09  4541.8  145.65  4608.8  135.04  4667.9  135.84  4736.9  134.37
  4845.9  135.84  4875.8   143.7  4933.5  145.19    4964  144.32  4985.2  139.91
  4991.1   136.2  5002.1  135.07  5014.2   136.5  5020.4  140.11    5038  144.61
  5162.5  145.42  5244.5  151.84  5394.9  157.43  5686.7  166.65  5902.4  166.72
#Mann= 10 ,-1 , 0
  3055.8     .17       0  3255.5     .11       0  4189.3     .17       0
  4294.9     .11       0  4667.9     .15       0  4985.2     .09       0
  5020.4     .12       0    5038     .15       0  5162.5     .17       0
  5394.9     .11       0
#XS Ineff= 2 , 0
       0  4948.8  145.06               0
Permanent Ineff=
       T       F
Bank Sta=4985.2,5020.4
XS Rating Curve= 0 ,0
Exp/Cntr=0.3,0.1

Type RM Length L Ch R = 1 ,2000    ,604,604,604
BEGIN DESCRIPTION:
EGYPT CREEK 3.5
END DESCRIPTION:
XS GIS Cut Line= 4
      3807327.11     10117810.15      3809407.56     10116611.21
      3809398.62      10116592.8      3808666.99     10115902.87
#Sta/Elev= 30
  2598.8  166.59  2771.5  165.98  3249.8  166.53  3324.5  160.38  3361.4  163.29
  3686.3  152.85  3850.3  152.99  3975.3  147.85  4032.8  144.16  4085.9  135.32
  4113.2  137.53    4129  143.84  4152.1  144.18  4284.1  140.81  4327.2  135.51
  4377.1  144.94  4509.7  144.48  4525.5  139.91  4627.5  136.97  4707.9  137.77
  4735.3  142.14  4970.9  137.41    4990  132.48  5064.5   138.7  5114.3  137.84
  5135.3  143.05  5176.8  143.04  5432.7  145.81  5645.3  156.96  6026.1  167.16
#Mann= 9 ,-1 , 0
  2598.8     .17       0  2771.5     .11       0  3686.3     .17       0
  3975.3     .11       0  4152.1     .15       0  4970.9     .09       0
  5064.5     .15       0  5176.8     .17       0  5645.3     .11       0
#XS Ineff= 2 , 0
       0  4751.1  142.12               0
Permanent Ineff=
       T       F
Bank Sta=4970.9,5064.5
XS Rating Curve= 0 ,0
Exp/Cntr=0.3,0.1

Type RM Length L Ch R = 1 ,1396    ,994,994,994
BEGIN DESCRIPTION:
EGYPT CREEK 2.0
END DESCRIPTION:
XS GIS Cut Line= 5
      3807334.27     10117837.01      3808561.13     10117560.58
      3809399.86     10117039.94      3809816.89     10116821.82
      3808711.54     10115831.82
#Sta/Elev= 30
  2755.2  166.57  2889.6  165.55  3079.8  162.96  3699.5   141.2  3797.1  140.83
  3903.6  140.38  4005.6  139.37  4361.2   140.3  4440.5  138.76  4496.4  136.73
  4590.9   139.4    4722  134.08  4743.2  137.78  4758.6  135.59  4974.7  139.96
  4984.2  137.28  4993.4  129.19  5011.5  132.31  5027.9  130.71  5033.6   133.9
  5077.7  138.61  5221.5  140.74  5664.3  141.88  5982.4  142.86    6117  142.93
    6301  144.31  6573.6  156.06  6717.2  163.28  6944.9  165.29  6954.5  165.14
#Mann= 17 ,-1 , 0
  2755.2     .17       0  2889.6     .11       0  3699.5     .17       0
  3797.1     .11       0  3903.6     .17       0  4005.6     .11       0
  4361.2     .17       0  4440.5     .15       0  4984.2     .09       0
  5077.7     .15       0  5221.5     .17       0  5664.3     .15       0
  5982.4     .17       0    6117     .15       0    6301     .17       0
  6573.6     .11       0  6944.9     .17       0
#XS Ineff= 3 ,-1
  4338.2  4301.5  140.46  4974.7  4365.3  139.96  5144.4  5226.6  140.67
Permanent Ineff=
       T       T       T
Bank Sta=4984.2,5077.7
XS Rating Curve= 0 ,0
Exp/Cntr=0.3,0.1

Type RM Length L Ch R = 1 ,402     ,0,0,0
BEGIN DESCRIPTION:
EGYPT CREEK 1.0
END DESCRIPTION:
XS GIS Cut Line= 5
      3807342.46     10117880.01      3809008.58     10117976.55
      3809690.23     10117506.35      3809917.92      10116725.6
      3808682.14     10115610.03
#Sta/Elev= 30
    2503  166.34  2582.3  165.76  2782.3  164.31  3125.5   145.4  3318.8   141.9
  3387.6  141.74  3603.2  141.35    3899  142.85  4096.3  143.41  4192.7   144.4
  4641.6  141.19  4765.9  135.13    4945  136.25    4966   130.4  4980.9  127.81
  4984.4  123.19  5015.9  129.88  5161.7  137.01  5390.9  134.03  5450.2  141.89
    5611  141.87  6005.8  142.48  6143.3  142.64  6262.8  142.27  6406.4  143.12
  6595.5  142.78  6814.7  146.88  6949.1  156.01  7280.3   164.5  7478.1  165.09
#Mann= 20 ,-1 , 0
    2503     .17       0  2582.3     .11       0  3318.8     .17       0
  3387.6     .11       0  3603.2     .17       0    3899     .11       0
  4096.3     .17       0  4192.7     .11       0  4641.6     .15       0
    4966     .09       0  5015.9     .15       0  5450.2     .17       0
    5611     .17       0  6005.8     .15       0  6143.3     .15       0
  6262.8     .17       0  6406.4     .15       0  6595.5     .17       0
  6949.1     .11       0  7280.3     .17       0
Bank Sta=4966,5015.9
XS Rating Curve= 0 ,0
Exp/Cntr=0.3,0.1

Chan Stop Cuts=-1
Use User Specified Reach Order=0
Composite Channel Slope=5