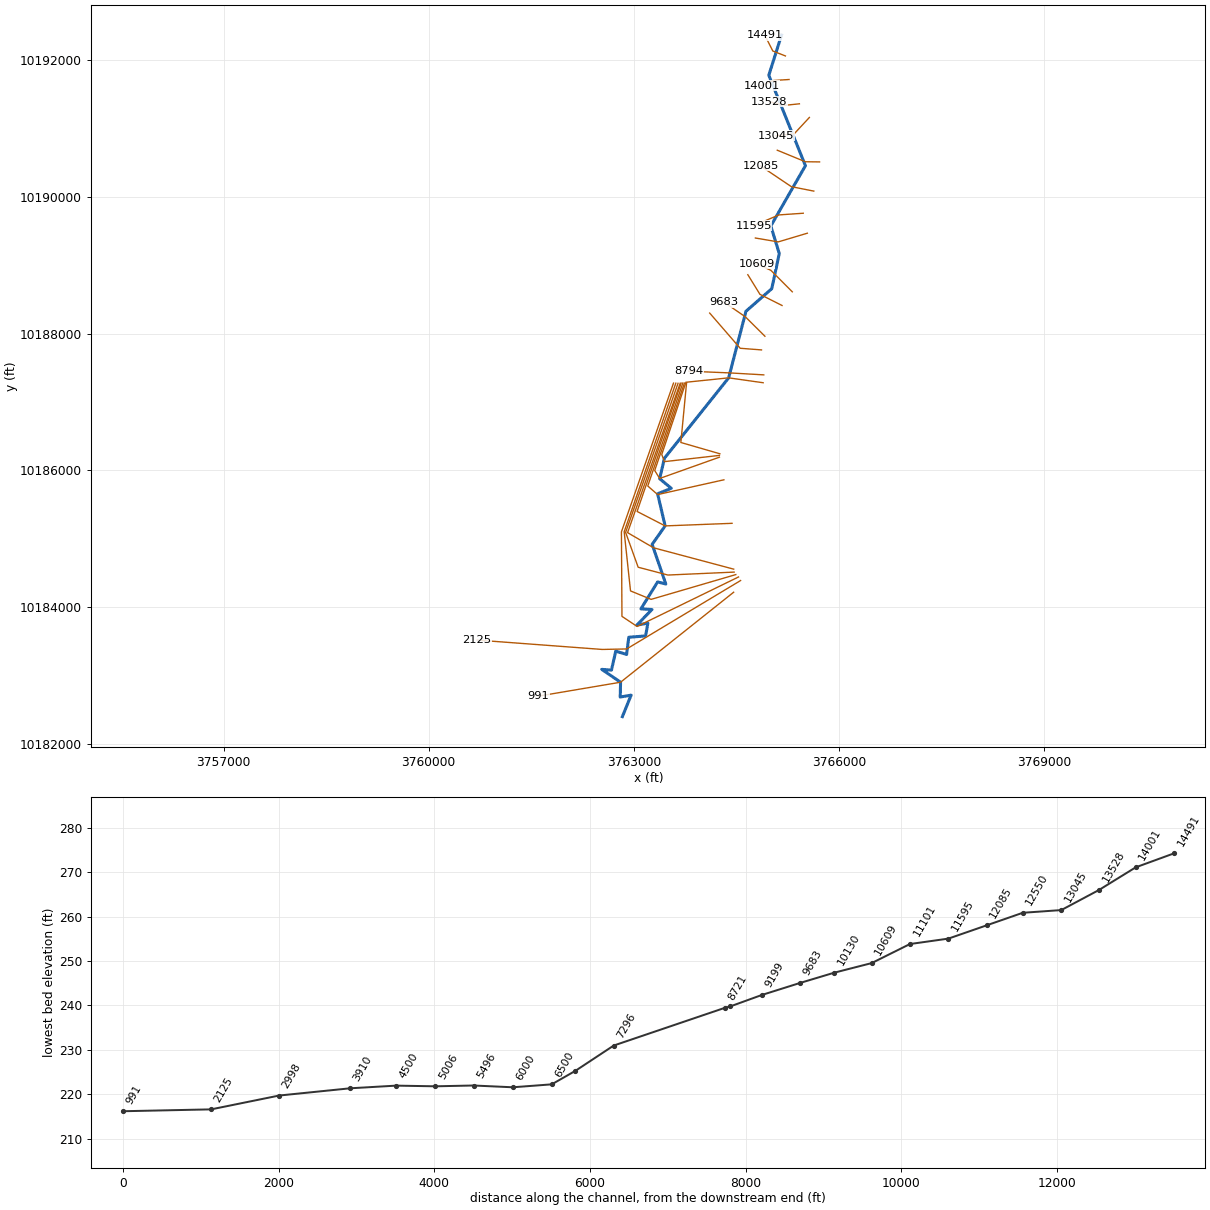
--- GREEN BRANCH.prj (project) ---

Proj Title=GREEN BRANCH Base Level Engineering
Current Plan=p01
Default Exp/Contr=0.3,0.1
English Units
Geom File=g01
Flow File=f01
Flow File=f02
Plan File=p01
Y Axis Title=Elevation
X Axis Title(PF)=Main Channel Distance
X Axis Title(XS)=Station
BEGIN DESCRIPTION:
GREEN BRANCH
END DESCRIPTION:
DSS Export Rating Curves= 0
DSS Export Rating Curve Sorted= 0
DSS Export Volume Flow Curves= 0
DXF OffsetX= 0
DXF OffsetY= 0
DXF ScaleX= 1
DXF ScaleY= 10

--- GREEN BRANCH.p01 (plan) ---

Plan Title=Multiple Run
Short Identifier=Multiple
Geom File=g01
Flow File=f01
Subcritical Flow
K Sum by GR= 0
Std Step Tol= 0.01
Critical Tol= 0.01
Num of Std Step Trials= 20
Max Error Tol= 0.3
Flow Tol Ratio= 0.001
Split Flow NTrial= 30
Split Flow Tol= 0.02
Split Flow Ratio= 0.02
Log Output Level= 0
Friction Slope Method= 1
Unsteady Friction Slope Method= 2
Unsteady Bridges Friction Slope Method= 1
Parabolic Critical Depth
Global Vel Dist=  1 , 1 , 1
Global Log Level= 0
CheckData=True
Encroach Param= -1, 0, 0, 0
BEGIN DESCRIPTION:
Multiple Run
END DESCRIPTION:

--- GREEN BRANCH.f01 (steady flow) ---

Flow Title=Multiple
Program Version=4.10
Number of Profiles= 7
Profile Names=10-year,25-year,50-year,1pct_min,100-year,1pct_plu,500-year
River Rch & RM=GREEN BRANCH,Reach-1         ,14491
     262     337     439     190     573    1730    1003
River Rch & RM=GREEN BRANCH,Reach-1         ,13045
     860    1188    1628     733    2215    6689    4240
River Rch & RM=GREEN BRANCH,Reach-1         ,6500
     815    1114    1513     676    2041    6164    3839
River Rch & RM=GREEN BRANCH,Reach-1         ,2125
    5405    7822   11045    5087   15363   46396   30769
River Rch & RM=GREEN BRANCH,Reach-1         ,991
    5405    7822   11045    5087   15363   46396   30769
Boundary for River Rch & Prof#=GREEN BRANCH,Reach-1         , 1
Up Type= 0
Dn Type= 3
Dn Slope=0.0015
Boundary for River Rch & Prof#=GREEN BRANCH,Reach-1         , 2
Up Type= 0
Dn Type= 3
Dn Slope=0.0015
Boundary for River Rch & Prof#=GREEN BRANCH,Reach-1         , 3
Up Type= 0
Dn Type= 3
Dn Slope=0.0015
Boundary for River Rch & Prof#=GREEN BRANCH,Reach-1         , 4
Up Type= 0
Dn Type= 3
Dn Slope=0.0015
Boundary for River Rch & Prof#=GREEN BRANCH,Reach-1         , 5
Up Type= 0
Dn Type= 3
Dn Slope=0.0015
Boundary for River Rch & Prof#=GREEN BRANCH,Reach-1         , 6
Up Type= 0
Dn Type= 3
Dn Slope=0.0015
Boundary for River Rch & Prof#=GREEN BRANCH,Reach-1         , 7
Up Type= 0
Dn Type= 3
Dn Slope=0.0015
DSS Import GetInterval= 0
DSS Import GetPeak= 0
DSS Import FillOption= 0

--- GREEN BRANCH.f02 (steady flow) ---

Flow Title=Orig_BLE_Flow
Program Version=4.10
Number of Profiles= 7
Profile Names=10-year,25-year,50-year,1pct_min,100-year,1pct_plu,500-year
River Rch & RM=GREEN BRANCH,Reach-1         ,14491
     262     330     382     146     441    1331     583
River Rch & RM=GREEN BRANCH,Reach-1         ,13045
     860    1165    1416     564    1704    5145    2465
River Rch & RM=GREEN BRANCH,Reach-1         ,6500
     815    1092    1316     520    1570    4741    2232
River Rch & RM=GREEN BRANCH,Reach-1         ,2125
    5405    7669    9604    3913   11818   35690   17889
River Rch & RM=GREEN BRANCH,Reach-1         ,991
    5405    7669    9604    3913   11818   35690   17889
Boundary for River Rch & Prof#=GREEN BRANCH,Reach-1         , 1
Up Type= 0
Dn Type= 3
Dn Slope=0.0015
Boundary for River Rch & Prof#=GREEN BRANCH,Reach-1         , 2
Up Type= 0
Dn Type= 3
Dn Slope=0.0015
Boundary for River Rch & Prof#=GREEN BRANCH,Reach-1         , 3
Up Type= 0
Dn Type= 3
Dn Slope=0.0015
Boundary for River Rch & Prof#=GREEN BRANCH,Reach-1         , 4
Up Type= 0
Dn Type= 3
Dn Slope=0.0015
Boundary for River Rch & Prof#=GREEN BRANCH,Reach-1         , 5
Up Type= 0
Dn Type= 3
Dn Slope=0.0015
Boundary for River Rch & Prof#=GREEN BRANCH,Reach-1         , 6
Up Type= 0
Dn Type= 3
Dn Slope=0.0015
Boundary for River Rch & Prof#=GREEN BRANCH,Reach-1         , 7
Up Type= 0
Dn Type= 3
Dn Slope=0.0015
DSS Import GetInterval= 0
DSS Import GetPeak= 0
DSS Import FillOption= 0

--- GREEN BRANCH.g01 (geometry) ---

Geom Title=Existing Conditions
Program Version=4.10

River Reach=GREEN BRANCH    ,Reach-1
Reach XY= 30
      3765160.95     10192366.48      3764974.66     10191778.78
      3765510.49     10190455.78      3765004.13      10189574.3
      3765127.74     10189170.48       3765018.2     10188656.81
      3764640.59     10188326.39       3764387.4     10187352.46
      3763448.23     10186176.84      3763378.23     10185876.84
      3763548.23     10185736.84      3763348.23     10185656.84
      3763458.23     10185186.84      3763268.23     10184916.84
      3763468.23     10184336.84      3763348.23     10184366.84
      3763103.88     10183973.38      3763265.76     10183963.92
      3763042.91     10183734.77      3763205.84     10183765.25
      3763172.21     10183577.09      3762926.24     10183558.17
       3762894.7     10183306.94      3762735.98     10183354.25
      3762672.91     10183076.74        3762531.      10183088.3
       3762806.4     10182900.15      3762801.15     10182683.61
      3762960.92     10182710.94      3762832.49     10182396.67

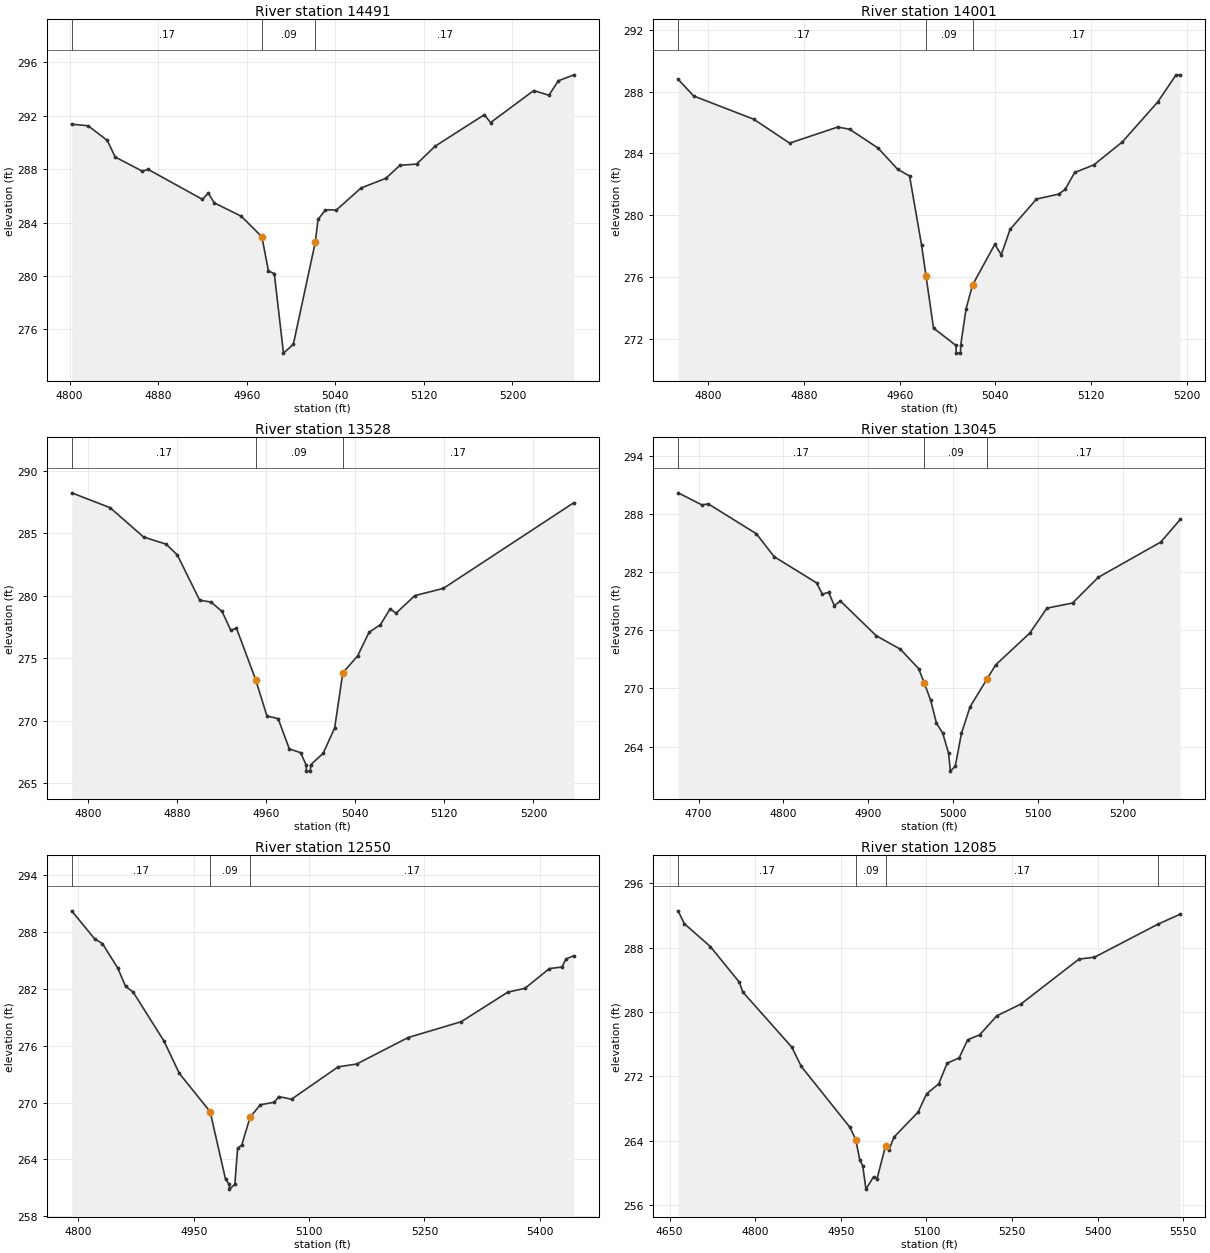
Type RM Length L Ch R = 1 ,14491   ,490,490,490
BEGIN DESCRIPTION:
GREEN BRANCH 21.0
END DESCRIPTION:
XS GIS Cut Line= 3
      3765217.82     10192061.09      3765033.36     10192133.33
      3764917.83     10192361.11
#Sta/Elev= 30
  4801.9  291.37  4816.8  291.25  4834.1  290.15  4841.2  288.91  4865.7  287.85
    4871  287.98  4919.9  285.74  4925.3   286.2  4930.7  285.47  4955.1  284.47
  4973.7  282.93  4979.6  280.37  4984.9  280.17  4993.2  274.21  5002.1  274.87
 5021.88  282.51  5024.4  284.23  5031.1  284.95    5041  284.94  5063.3  286.59
  5085.6  287.31  5098.4  288.29  5113.4  288.38  5130.1  289.72  5174.6  292.08
  5180.2  291.49  5219.2  293.89  5232.9  293.54  5241.4  294.62  5255.4  295.07
#Mann= 3 , 0 , 0
  4801.9     .17       0  4973.7     .09       0 5021.88     .17       0
Bank Sta=4973.7,5021.88
XS Rating Curve= 0 ,0
Exp/Cntr=0.3,0.1

Type RM Length L Ch R = 1 ,14001   ,473,473,473
BEGIN DESCRIPTION:
GREEN BRANCH 20.0
END DESCRIPTION:
XS GIS Cut Line= 3
      3765270.85     10191716.39      3765046.19     10191702.39
       3764866.3     10191628.44
#Sta/Elev= 30
  4774.9   288.8  4787.9  287.72    4838  286.22  4868.1  284.67  4908.2  285.71
  4918.2  285.57    4942  284.35  4958.3  282.98  4968.3  282.54  4978.3  278.08
    4982 276.089  4988.3   272.7    5007  271.58  5007.3  271.08  5010.8  271.08
    5011  271.58  5015.5  273.95  5020.9  275.49  5039.5  278.12  5044.9  277.45
  5052.3  279.09  5074.3  281.05  5092.8  281.37  5098.2  281.67  5106.3  282.77
  5122.2  283.26  5146.1  284.75  5175.5  287.32    5191  289.09  5194.5  289.09
#Mann= 3 , 0 , 0
  4774.9     .17       0    4982     .09       0  5020.9     .17       0
#XS Ineff= 2 , 0
       0                  5039.5       0  278.12
Permanent Ineff=
       F       F
Bank Sta=4982,5020.9
XS Rating Curve= 0 ,0
Exp/Cntr=0.3,0.1

Type RM Length L Ch R = 1 ,13528   ,483,483,483
BEGIN DESCRIPTION:
GREEN BRANCH 19.0
END DESCRIPTION:
XS GIS Cut Line= 3
      3765422.16     10191361.05      3765208.89       10191339.
      3764978.88     10191392.71
#Sta/Elev= 30
  4785.6  288.25  4820.1  287.06  4850.2  284.71  4870.4  284.14  4880.4  283.28
  4900.5  279.65  4910.6  279.51  4920.6  278.75  4928.4  277.25  4933.5  277.41
  4950.8  273.27  4960.8  270.39  4970.9  270.17  4980.9  267.75    4991  267.45
    4996  266.47  4996.3  265.97  4999.8  265.97    5000  266.47  5011.3   267.4
  5021.6  269.43  5028.9  273.84  5042.1  275.18  5052.4  277.08  5062.7   277.7
  5071.4  278.97  5076.6  278.61  5093.5  280.02  5119.1   280.6  5236.2  287.46
#Mann= 3 , 0 , 0
  4785.6     .17       0  4950.8     .09       0  5028.9     .17       0
Bank Sta=4950.8,5028.9
XS Rating Curve= 0 ,0
Exp/Cntr=0.3,0.1

Type RM Length L Ch R = 1 ,13045   ,495,495,495
BEGIN DESCRIPTION:
GREEN BRANCH 18.0
END DESCRIPTION:
XS GIS Cut Line= 3
      3765567.87     10191161.09      3765347.41     10190923.66
      3765081.84     10190893.24
#Sta/Elev= 30
    4676  290.18  4704.1  288.93  4711.5  289.04  4768.1  285.96  4789.1  283.59
    4839  280.89  4845.8  279.73  4853.2  279.91    4860  278.54  4867.1  279.02
  4909.3  275.43  4937.7  274.04  4959.2  272.04    4966  270.52  4973.4  268.76
  4980.2   266.4  4987.5   265.4  4994.4  263.32  4996.6  261.46  5002.3  261.96
  5009.6  265.35  5019.7  268.09  5039.8  270.98  5049.9  272.42  5090.1  275.71
  5110.3  278.28  5140.5  278.81  5170.7  281.46  5244.3   285.1  5267.3  287.44
#Mann= 3 , 0 , 0
    4676     .17       0    4966     .09       0  5039.8     .17       0
Bank Sta=4966,5039.8
XS Rating Curve= 0 ,0
Exp/Cntr=0.3,0.1

Type RM Length L Ch R = 1 ,12550   ,465,465,465
BEGIN DESCRIPTION:
GREEN BRANCH 17.0
END DESCRIPTION:
XS GIS Cut Line= 3
      3765717.86     10190511.07      3765509.27     10190513.33
      3765098.47     10190682.04
#Sta/Elev= 30
  4791.4  290.25  4821.4  287.28  4831.4  286.79  4851.4   284.2  4861.4  282.28
  4871.4  281.66  4911.4  276.49  4931.4  273.07  4971.4  269.03  4991.4   261.9
  4996.2  261.35  4996.5  260.85  5003.5  261.35  5007.1  265.15  5012.5  265.52
  5023.2  268.42  5036.5  269.76    5055  270.03  5060.4  270.63  5077.2  270.35
  5137.8  273.77  5161.7  274.06  5228.6  276.86  5297.8  278.54  5358.3  281.66
  5380.5  282.06  5412.3  284.15  5428.5  284.31    5434  285.17  5444.1  285.51
#Mann= 3 , 0 , 0
  4791.4     .17       0  4971.4     .09       0  5023.2     .17       0
Bank Sta=4971.4,5023.2
XS Rating Curve= 0 ,0
Exp/Cntr=0.3,0.1

Type RM Length L Ch R = 1 ,12085   ,490,490,490
BEGIN DESCRIPTION:
GREEN BRANCH 16.0
END DESCRIPTION:
XS GIS Cut Line= 3
      3765633.21     10190083.95      3765304.48     10190148.95
      3764852.51     10190453.15
#Sta/Elev= 30
  4664.9  292.56  4675.7  290.97  4721.3  288.13  4772.3  283.69  4778.2  282.49
    4864  275.65  4880.7  273.25    4966  265.69  4976.2  264.15  4983.2  261.64
  4988.3  260.93    4994  258.02  5007.4  259.56  5013.4  259.29  5028.4  263.41
  5034.4  262.91  5043.3  264.49  5085.4  267.58  5100.3  269.85  5121.4  271.08
  5136.3  273.65  5157.3  274.31  5172.3  276.56  5193.3  277.17  5223.3  279.53
  5265.3  280.98  5367.3  286.57  5394.3   286.8  5505.6   290.9  5544.8  292.15
#Mann= 4 ,-1 , 0
  4664.9     .17       0  4976.2     .09       0  5028.4     .17       0
  5505.6     .11       0
Bank Sta=4976.2,5028.4
XS Rating Curve= 0 ,0
Exp/Cntr=0.3,0.1

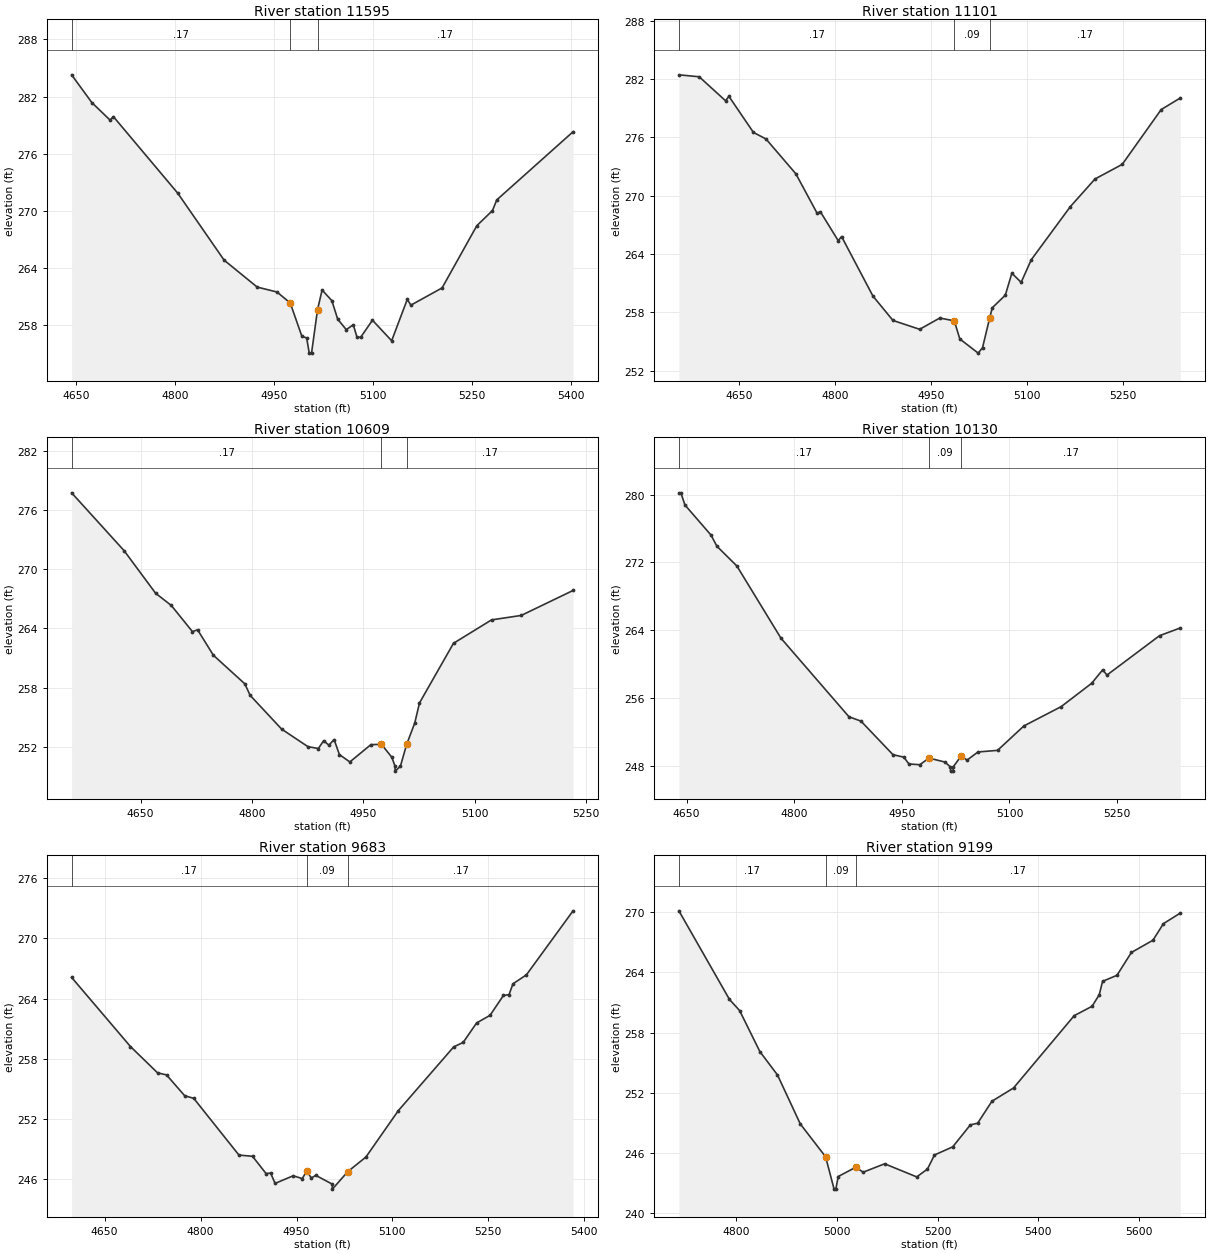
Type RM Length L Ch R = 1 ,11595   ,494,494,494
BEGIN DESCRIPTION:
GREEN BRANCH 15.0
END DESCRIPTION:
XS GIS Cut Line= 3
      3765478.41     10189760.26      3765123.05     10189735.76
       3764751.5     10189577.88
#Sta/Elev= 30
  4643.8  284.28  4674.4  281.37  4702.1  279.52  4707.1  279.89  4804.7  271.84
  4874.9  264.81    4925  261.98  4955.1  261.46  4975.1  260.31  4992.8   256.8
    5000  256.64  5003.9  255.04  5007.4  255.04  5016.5  259.62  5023.4  261.67
  5038.2  260.55    5047  258.61    5060  257.51  5070.7  258.02  5076.1  256.75
  5081.7  256.69  5099.7   258.5  5128.8  256.34  5152.5  260.69  5157.9  260.08
  5205.2  261.89  5257.9  268.43  5281.6  270.02  5288.1  271.14  5403.7   278.3
#Mann= 3 , 0 , 0
  4643.8     .17       0  4975.1     .09       0  5016.5     .17       0
Bank Sta=4975.1,5016.5
XS Rating Curve= 0 ,0
Exp/Cntr=0.3,0.1

Type RM Length L Ch R = 1 ,11101   ,492,492,492
BEGIN DESCRIPTION:
GREEN BRANCH 14.0
END DESCRIPTION:
XS GIS Cut Line= 3
      3765538.25     10189468.25      3765112.55     10189341.05
      3764778.35     10189397.88
#Sta/Elev= 30
  4555.7  282.44  4587.4  282.24  4628.6  279.77  4633.8  280.23  4672.1  276.52
  4691.8  275.84  4738.4  272.26  4771.5  268.22  4776.7  268.36  4804.6  265.38
  4809.8  265.81  4858.8  259.69  4890.1  257.18  4931.8  256.27  4963.2  257.43
  4985.9  257.14  4994.5  255.28  5023.2  253.82    5030  254.38 5041.18  257.44
  5045.3  258.49  5065.6  259.78  5075.8  262.04  5090.3   261.1  5106.2  263.43
  5167.1  268.88  5205.7  271.73  5248.2  273.23  5309.1  278.87    5339  280.06
#Mann= 3 , 0 , 0
  4555.7     .17       0  4985.9     .09       0 5041.18     .17       0
#XS Ineff= 2 , 0
       0                  5075.8       0  262.04
Permanent Ineff=
       F       F
Bank Sta=4985.9,5041.18
XS Rating Curve= 0 ,0
Exp/Cntr=0.3,0.1

Type RM Length L Ch R = 1 ,10609   ,479,479,479
BEGIN DESCRIPTION:
GREEN BRANCH 13.0
END DESCRIPTION:
XS GIS Cut Line= 3
      3765317.83     10188611.09      3765005.34     10188924.82
       3764794.6     10189023.02
#Sta/Elev= 30
  4557.2  277.72  4627.9  271.86  4670.3  267.55  4691.5  266.31  4719.8  263.67
  4726.9  263.84  4748.1  261.27  4790.5  258.37  4797.6  257.21    4840  253.79
  4875.4  252.01  4889.5  251.82  4896.6  252.61  4903.7  252.16  4910.7  252.73
  4917.8  251.21  4931.9  250.46  4960.2  252.21  4974.4  252.25  4988.5  250.93
  4992.7  250.03  4992.9  249.53    5000  250.03  5008.4  252.24  5019.3   254.4
  5025.7  256.44  5071.5  262.48  5122.7  264.85  5162.7   265.3  5232.5  267.83
#Mann= 3 , 0 , 0
  4557.2     .17       0  4974.4     .09       0  5008.4     .17       0
Bank Sta=4974.4,5008.4
XS Rating Curve= 0 ,0
Exp/Cntr=0.3,0.1

Type RM Length L Ch R = 1 ,10130   ,447,447,447
BEGIN DESCRIPTION:
GREEN BRANCH 12.0
END DESCRIPTION:
XS GIS Cut Line= 3
      3765167.86     10188411.07      3764845.63     10188573.37
      3764667.85     10188861.08
#Sta/Elev= 30
  4639.2  280.21    4642  280.21  4647.6  278.78    4684  275.22  4692.2  273.91
  4720.1  271.57  4781.4  263.07  4876.3  253.79    4893  253.28  4937.6  249.32
  4952.7  249.03  4959.9  248.22  4975.1  248.14  4987.8  248.92  5010.1  248.45
  5017.6  247.88  5017.9  247.38  5021.4  247.38  5021.6  247.88  5032.6  249.16
  5040.9  248.68  5056.1  249.64  5083.4  249.83  5120.1  252.71  5172.1  254.99
  5214.7  257.75    5230  259.34  5235.9  258.71  5309.2  263.36  5338.2  264.27
#Mann= 3 , 0 , 0
  4639.2     .17       0  4987.8     .09       0  5032.6     .17       0
Bank Sta=4987.8,5032.6
XS Rating Curve= 0 ,0
Exp/Cntr=0.3,0.1

Type RM Length L Ch R = 1 ,9683    ,484,484,484
BEGIN DESCRIPTION:
GREEN BRANCH 11.0
END DESCRIPTION:
XS GIS Cut Line= 3
      3764917.88     10187961.04      3764632.82     10188244.07
      3764317.84     10188461.08
#Sta/Elev= 30
  4598.3  266.11  4690.3  259.23  4732.7  256.61  4746.8   256.4  4775.1  254.33
  4789.3  254.07    4860  248.42  4881.2   248.3  4902.4  246.58  4909.5  246.63
  4916.5   245.6  4944.8  246.36    4959  246.08    4966  246.83  4973.1  246.14
  4980.2   246.4  5005.8  245.53  5006.1  245.03  5030.3  246.78  5058.5  248.22
  5109.3  252.85  5195.8  259.19  5210.7  259.64  5231.7  261.58  5252.6  262.33
  5273.6  264.31  5282.4   264.4  5288.5  265.47  5309.6  266.37  5382.5  272.74
#Mann= 3 , 0 , 0
  4598.3     .17       0    4966     .09       0  5030.3     .17       0
Bank Sta=4966,5030.3
XS Rating Curve= 0 ,0
Exp/Cntr=0.3,0.1

Type RM Length L Ch R = 1 ,9199    ,405,405,405
BEGIN DESCRIPTION:
GREEN BRANCH 10.0
END DESCRIPTION:
XS GIS Cut Line= 3
      3764867.89     10187761.07      3764555.91     10187785.09
      3764109.86     10188300.21
#Sta/Elev= 30
  4687.1  270.15  4787.4   261.3  4807.5  260.19  4847.6   256.1  4882.6  253.76
  4927.8  248.87    4978  245.59  4994.8  242.36  4998.3  242.36    5003  243.62
  5038.1  244.55  5052.4  244.05  5095.1  244.89  5158.7  243.58  5179.9  244.36
  5193.9  245.77    5230  246.58  5265.1  248.78  5279.4  248.94  5307.9  251.14
  5350.6  252.46  5470.9  259.68  5506.4  260.62  5520.6  261.77  5527.2  263.11
  5555.7  263.71  5584.3  265.99    5627  267.21  5647.9  268.87  5681.4  269.93
#Mann= 3 , 0 , 0
  4687.1     .17       0    4978     .09       0  5038.1     .17       0
Bank Sta=4978,5038.1
XS Rating Curve= 0 ,0
Exp/Cntr=0.3,0.1

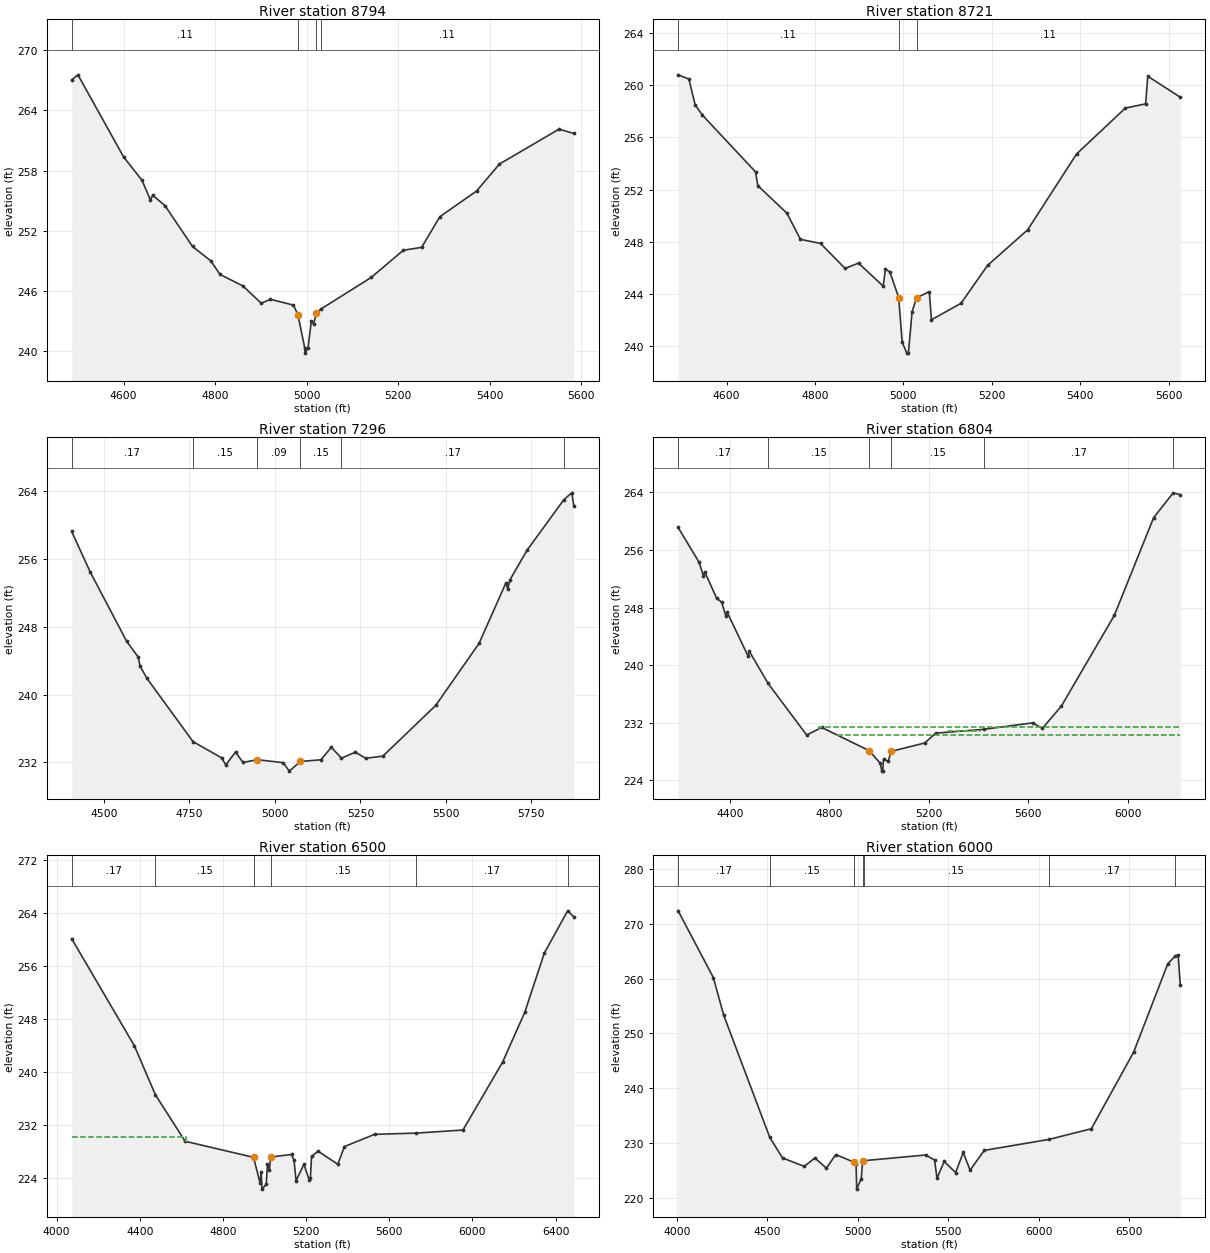
Type RM Length L Ch R = 1 ,8794    ,73,73,73
BEGIN DESCRIPTION:
GREEN BRANCH 9.0
END DESCRIPTION:
XS GIS Cut Line= 3
      3764901.51     10187396.02      3764388.95     10187425.47
      3763805.45     10187449.56
#Sta/Elev= 30
  4486.6  267.04  4500.3  267.55  4600.4  259.34  4640.5  257.02  4658.7  255.07
  4663.7  255.54  4690.6   254.5  4750.7  250.43  4790.8  248.99  4810.8  247.64
  4860.9  246.49  4900.9  244.77    4921  245.16  4971.1  244.58  4981.1  243.63
    4996  240.29  4996.3  239.79  5003.1  240.29  5010.4  243.01  5015.4  242.71
  5021.1  243.75  5031.1  244.18  5141.2  247.34  5211.3  250.05  5251.3  250.34
  5291.3   253.4  5371.4  255.96  5421.5  258.65  5551.6  262.13    5584   261.7
#Mann= 4 ,-1 , 0
  4486.6     .11       0  4981.1     .06       0  5021.1     .08       0
  5031.1     .11       0
Bank Sta=4981.1,5021.1
XS Rating Curve= 0 ,0
Exp/Cntr=0.3,0.1

Type RM Length L Ch R = 1 ,8721    ,1425,1425,1425
BEGIN DESCRIPTION:
GREEN BRANCH 8.0
END DESCRIPTION:
XS GIS Cut Line= 3
      3764891.94     10187280.83       3764387.4     10187352.46
      3763764.32     10187288.03
#Sta/Elev= 30
  4490.4  260.81  4514.7  260.49  4528.8  258.52    4545  257.73  4665.6  253.36
  4670.6  252.31  4736.5  250.19  4767.2  248.18  4812.5  247.87  4868.2  245.95
  4898.5  246.36  4954.3  244.59  4959.4  245.88  4969.2   245.7  4989.4  243.71
  4997.2  240.29  5007.8  239.45  5011.3  239.45  5019.7  242.64  5029.7  243.69
  5058.5  244.17  5063.5  242.01  5130.2  243.27  5190.6  246.19    5281  248.91
  5391.6  254.73  5502.2  258.26  5547.8  258.58  5552.9   260.7  5626.4  259.09
#Mann= 3 , 0 , 0
  4490.4     .11       0  4989.4     .06       0  5029.7     .11       0
#XS Ineff= 2 , 0
       0  4959.4  245.88               0
Permanent Ineff=
       F       F
Bank Sta=4989.4,5029.7
XS Rating Curve= 0 ,0
Exp/Cntr=0.3,0.1

Type RM Length L Ch R = 1 ,7296    ,492,492,492
BEGIN DESCRIPTION:
GREEN BRANCH 7.0
END DESCRIPTION:
XS GIS Cut Line= 3
      3764259.06     10186241.83      3763688.23     10186406.84
      3763771.43     10187276.98
#Sta/Elev= 30
  4405.8  259.28  4460.7  254.44  4566.8   246.3  4600.4  244.45  4605.6  243.39
  4625.7  241.95  4760.7  234.46  4844.3  232.55  4856.5  231.71  4884.9  233.24
  4906.7     232  4948.3  232.33  5024.3  231.98  5042.2  230.98  5074.6  232.12
  5134.8  232.32    5165   233.8  5194.6  232.51  5235.3  233.22  5265.4   232.5
  5315.7  232.75  5470.1  238.73  5596.9  246.06  5675.6  253.21  5680.6  252.47
  5687.3  253.57  5737.6  257.08  5845.1  263.04  5868.2  263.84  5874.1  262.31
#Mann= 6 ,-1 , 0
  4405.8     .17       0  4760.7     .15       0  4948.3     .09       0
  5074.6     .15       0  5194.6     .17       0  5845.1     .11       0
Bank Sta=4948.3,5074.6
XS Rating Curve= 0 ,0
Exp/Cntr=0.3,0.1

Type RM Length L Ch R = 1 ,6804    ,304,304,304
BEGIN DESCRIPTION:
GREEN BRANCH 6.0
END DESCRIPTION:
XS GIS Cut Line= 4
        3764252.     10186217.82      3763448.23     10186126.84
      3763408.75     10186231.55      3763757.96     10187275.07
#Sta/Elev= 30
  4191.1  259.13  4275.8  254.28  4293.2  252.38  4298.3  252.97  4346.2   249.3
  4366.4  248.75    4383  246.87    4388   247.4  4472.7  241.26  4477.7  241.93
  4553.5  237.46  4708.5   230.3  4768.9  231.36  4960.1  228.13  5004.9  226.38
  5010.8  225.29  5014.3  225.29  5017.9  226.96  5036.6  226.63  5048.1  228.03
  5183.9   229.2  5227.4  230.56  5422.4   231.1  5617.6  231.99  5657.5  231.25
  5733.6  234.32  5946.9  246.93  6104.8  260.48  6183.7  263.94  6212.3  263.68
#Mann= 6 ,-1 , 0
  4191.1     .17       0  4553.5     .15       0  4960.1     .09       0
  5048.1     .15       0  5422.4     .17       0  6183.7     .11       0
#XS Ineff= 4 ,-1
  4758.8  4668.3  231.39  4831.7  4758.8  230.37  5227.4  5278.6  230.56
  5278.6  5410.2  230.83
Permanent Ineff=
       F       F       F       F
Bank Sta=4960.1,5048.1
XS Rating Curve= 0 ,0
Exp/Cntr=0.3,0.1

Type RM Length L Ch R = 1 ,6500    ,500,500,500
BEGIN DESCRIPTION:
GREEN BRANCH 11.5
END DESCRIPTION:
XS GIS Cut Line= 4
      3764251.95     10186191.77      3763378.23     10185880.53
      3763305.89     10185997.18       3763739.9     10187275.97
#Sta/Elev= 30
  4072.5  260.14  4374.1  243.94  4475.3  236.52  4618.2  229.49  4947.3  227.06
  4978.7  223.18    4984  224.87  4987.9  222.25  5008.4  222.97  5014.2  225.98
  5023.7  225.19  5029.6  227.11  5130.1  227.49    5142  226.62  5151.9  223.53
  5189.5  225.99  5215.3  223.62  5220.9     224  5226.2   227.2  5257.6  227.99
  5352.6  226.01  5384.3  228.69  5529.6  230.54  5727.6  230.72  5954.5  231.19
  6144.6  241.43  6251.7     249  6345.9  257.97    6458  264.35  6487.7  263.44
#Mann= 6 ,-1 , 0
  4072.5     .17       0  4475.3     .15       0  4947.3     .09       0
  5029.6     .15       0  5727.6     .17       0    6458     .11       0
#XS Ineff= 2 , 0
       0  4624.7  230.17  5458.2       0  229.55
Permanent Ineff=
       F       F
Bank Sta=4947.3,5029.6
XS Rating Curve= 0 ,0
Exp/Cntr=0.3,0.1

Type RM Length L Ch R = 1 ,6000    ,504,504,504
BEGIN DESCRIPTION:
GREEN BRANCH 10.5
END DESCRIPTION:
XS GIS Cut Line= 4
      3764317.87     10185861.07      3763348.23     10185645.08
      3763204.32     10185770.62      3763716.95     10187276.49
#Sta/Elev= 30
  4006.6  272.38  4201.3   260.2  4258.6  253.32  4513.2  231.03  4583.5  227.28
  4703.3  225.75  4762.6  227.27  4826.2  225.41  4877.4   227.9  4979.9  226.49
  4990.1  226.15  4993.4  221.59  5018.6  223.52  5026.2  226.68  5032.8  226.78
  5374.4  227.82  5423.8   226.9  5437.2  223.58  5476.7  226.64    5540  224.62
  5582.3  228.28    5620  225.05  5698.5  228.66  6055.5  230.66  6290.1  232.61
  6524.2  246.61  6712.6  262.73  6751.3  264.05  6769.8  264.37  6781.7  258.76
#Mann= 7 ,-1 , 0
  4006.6     .17       0  4513.2     .15       0  4979.9     .09       0
  5026.2     .12       0  5032.8     .15       0  6055.5     .17       0
  6751.3     .11       0
#XS Ineff= 2 , 0
       0                  5582.3       0  228.28
Permanent Ineff=
       F       F
Bank Sta=4979.9,5026.2
XS Rating Curve= 0 ,0
Exp/Cntr=0.3,0.1

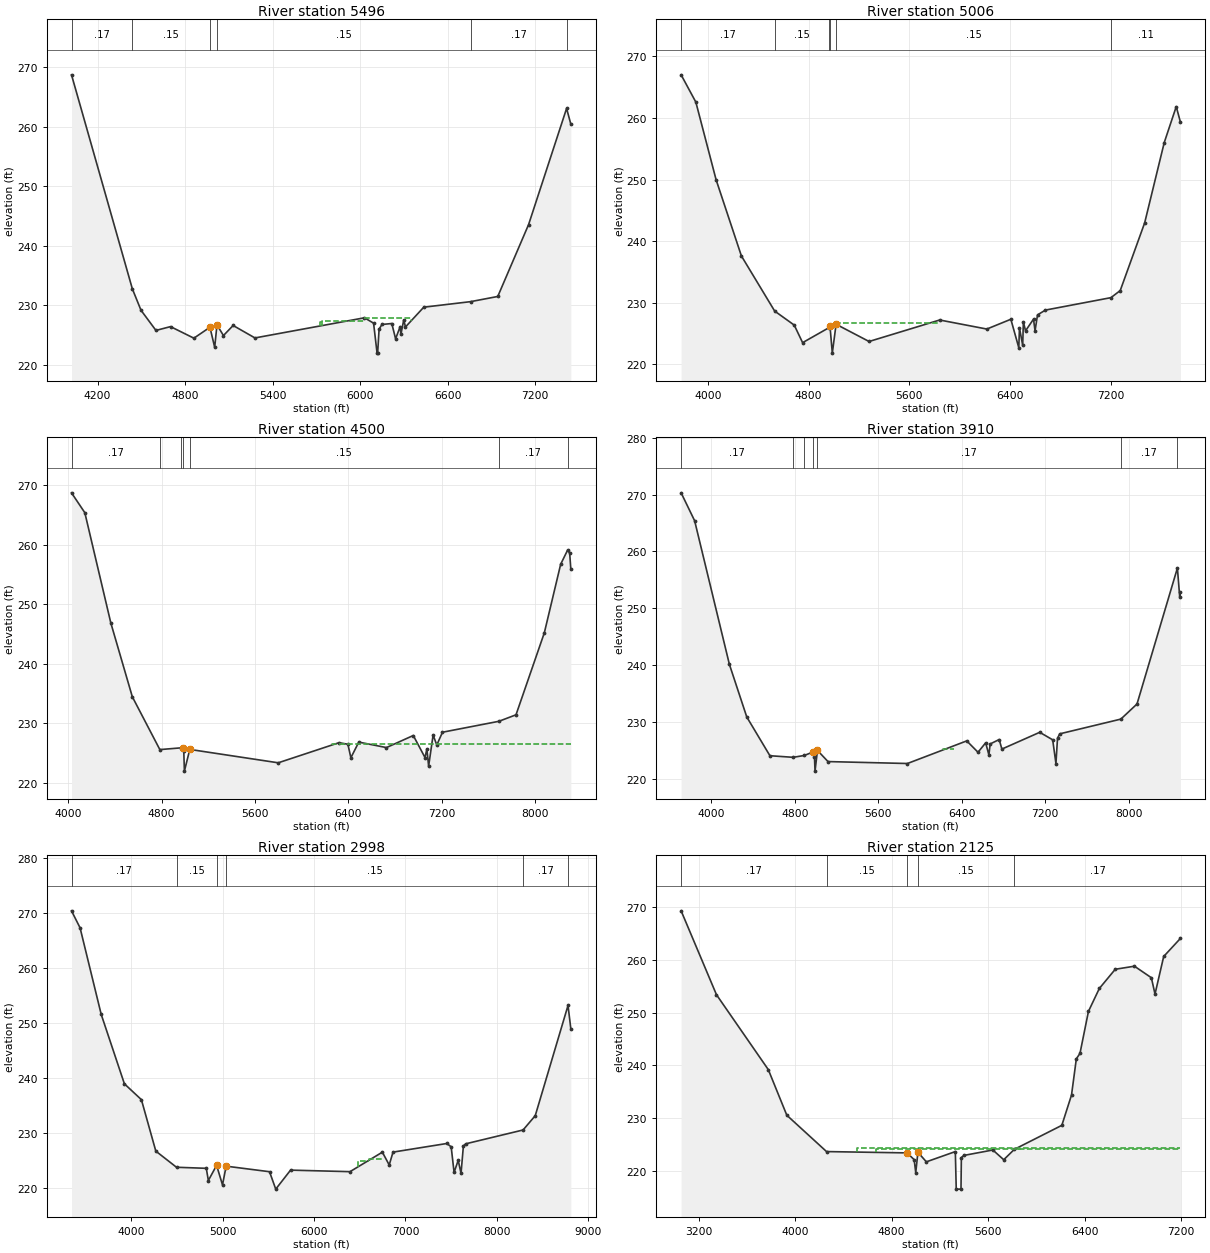
Type RM Length L Ch R = 1 ,5496    ,490,490,490
BEGIN DESCRIPTION:
GREEN BRANCH 4.0
END DESCRIPTION:
XS GIS Cut Line= 4
      3764436.61      10185224.5      3763458.23     10185186.84
      3763048.07     10185398.22      3763692.42     10187275.08
#Sta/Elev= 30
  4020.9   268.7  4438.2  232.78  4497.5  229.19  4600.1   225.8  4700.2  226.44
  4860.3   224.5  4970.4  226.33    5003  222.96  5018.7  226.74    5063  224.94
  5129.5  226.63  5279.1  224.54  6030.3  227.92  6092.8  227.02  6116.8  221.99
  6120.7  221.99  6130.5     226    6150   226.8  6217.8  226.96  6243.8  224.39
  6275.1  226.44  6280.3  225.14  6299.7  227.57  6311.6  226.38  6437.1   229.7
  6758.2  230.63  6944.6   231.5  7156.1  243.57  7416.7  263.06  7445.8  260.42
#Mann= 6 ,-1 , 0
  4020.9     .17       0  4438.2     .15       0  4970.4     .09       0
  5018.7     .15       0  6758.2     .17       0  7416.7     .11       0
#XS Ineff= 3 ,-1
    5723  5739.3  227.29  5739.3  6030.3  227.45  6030.3  6352.6  227.92
Permanent Ineff=
       F       F       F
Bank Sta=4970.4,5018.7
XS Rating Curve= 0 ,0
Exp/Cntr=0.3,0.1

Type RM Length L Ch R = 1 ,5006    ,506,506,506
BEGIN DESCRIPTION:
GREEN BRANCH 8.5
END DESCRIPTION:
XS GIS Cut Line= 4
      3764460.91     10184554.36      3763288.23     10184866.84
      3762908.75     10185088.32        3763678.     10187272.54
#Sta/Elev= 30
  3786.4  267.01  3903.4  262.58  4064.4  249.97  4265.6  237.59    4530  228.64
  4685.5  226.36    4752  223.51  4961.2  225.94  4969.3  226.26  4988.1  221.81
  5018.1   226.5  5280.2   223.7  5841.5  227.19  6216.2  225.72  6407.1  227.31
  6470.3  222.69  6475.6  225.93  6501.3  223.06  6506.6  226.91  6523.7  225.43
  6587.3  227.33  6599.4  225.43  6619.1  228.02  6681.7   228.8  7202.6  230.82
  7276.4  231.97  7470.6  242.96  7626.3  256.01  7721.7  261.85  7755.1  259.32
#Mann= 6 ,-1 , 0
  3786.4     .17       0    4530     .15       0  4961.2     .12       0
  4969.3     .09       0  5018.1     .15       0  7202.6     .11       0
#XS Ineff= 2 ,-1
  5023.8  5841.5  226.63  5841.5  6625.1  227.19
Permanent Ineff=
       F       F
Bank Sta=4969.3,5018.1
XS Rating Curve= 0 ,0
Exp/Cntr=0.3,0.1

Type RM Length L Ch R = 1 ,4500    ,590,590,590
BEGIN DESCRIPTION:
GREEN BRANCH 7.5
END DESCRIPTION:
XS GIS Cut Line= 5
      3764467.88     10184511.07      3763498.23     10184468.05
      3763063.72     10184582.19      3762880.11     10185092.23
      3763647.02     10187273.18
#Sta/Elev= 30
  4029.4  268.75  4143.4  265.41  4366.3  246.84  4549.9  234.46  4785.5  225.58
  4970.3  225.88  4980.4  225.81  4990.4  225.29  4995.7  221.96  5041.7  225.61
  5798.8  223.36  6318.7  226.74  6394.9  226.48  6420.5  224.21  6488.3  226.84
    6725  225.92  6954.7  227.95  7055.1  224.24  7071.3  225.71    7086  222.79
  7124.3  228.02  7156.1  226.36  7204.6   228.5  7687.9  230.34  7833.9  231.43
  8076.3  245.21  8216.2  256.74  8275.7  259.13  8293.2  258.62  8303.2  255.92
#Mann= 7 ,-1 , 0
  4029.4     .17       0  4785.5     .15       0  4970.3     .12       0
  4980.4     .09       0  5041.7     .15       0  7687.9     .17       0
  8275.7     .11       0
#XS Ineff= 2 , 0
       0                  6255.1       0  226.54
Permanent Ineff=
       F       F
Bank Sta=4980.4,5041.7
XS Rating Curve= 0 ,0
Exp/Cntr=0.3,0.1

Type RM Length L Ch R = 1 ,3910    ,912,912,912
BEGIN DESCRIPTION:
GREEN BRANCH 3.0
END DESCRIPTION:
XS GIS Cut Line= 5
      3764492.14      10184474.5      3763253.15     10184112.13
      3762951.74     10184235.84      3762859.08     10185100.93
      3763614.49     10187274.56
#Sta/Elev= 30
  3709.1  270.32  3838.6  265.41    4172  240.14  4338.7  230.88  4560.6  224.07
  4783.2  223.79  4888.9  224.11  4974.3  224.72  4987.9  223.82    4993  221.36
  5016.5     225  5117.5  223.04    5879   222.7  6447.9  226.68  6555.9  224.68
  6629.3  226.34  6660.4   224.2  6672.4  226.14    6759  226.92  6784.8  225.24
  7147.6  228.19    7272  226.87  7303.1   222.7  7318.2  227.14  7339.5  227.92
  7925.3  230.51  8080.4  233.17  8467.8  257.08    8490     252    8497   252.8
#Mann= 7 ,-1 , 0
  3709.1     .17       0  4783.2     .15       0  4888.9     .17       0
  4974.3     .09       0  5016.5     .17       0  7925.3     .17       0
  8467.8     .11       0
#XS Ineff= 3 ,-1
  6217.2    6323  225.31    6323  6447.9  225.79  6447.9  7561.7  226.68
Permanent Ineff=
       F       F       F
Bank Sta=4974.3,5016.5
XS Rating Curve= 0 ,0
Exp/Cntr=0.3,0.1

Type RM Length L Ch R = 1 ,2998    ,873,873,873
BEGIN DESCRIPTION:
GREEN BRANCH 2.0
END DESCRIPTION:
XS GIS Cut Line= 5
      3764532.04      10184439.9      3763048.17     10183715.85
      3762826.74     10183863.44      3762818.91     10185100.04
      3763580.62     10187275.82
#Sta/Elev= 30
  3348.9   270.4  3442.6   267.3  3673.8  251.53  3927.2   238.9    4113  236.02
  4270.7  226.65  4496.8  223.71  4822.5  223.52    4845   221.3  4935.1  224.06
  4999.7   220.5  5039.5  223.91  5513.8   222.9  5581.8  219.73  5743.8  223.19
  6393.8  222.91  6747.5  226.46  6822.2  224.13  6864.1  226.47  7452.5  228.04
  7499.8  227.43  7531.6  222.77  7576.6  224.98  7607.6   222.6  7633.3  227.59
  7658.7  227.98  8285.9   230.5  8418.8   233.1  8777.2  253.17    8808  248.92
#Mann= 6 ,-1 , 0
  3348.9     .17       0  4496.8     .15       0  4935.1     .09       0
  5039.5     .15       0  8285.9     .17       0  8777.2     .11       0
#XS Ineff= 3 ,-1
  6483.8    6605  224.89    6605  6747.5  225.24  6747.5  7987.1  226.46
Permanent Ineff=
       F       F       F
Bank Sta=4935.1,5039.5
XS Rating Curve= 0 ,0
Exp/Cntr=0.3,0.1

Type RM Length L Ch R = 1 ,2125    ,1134,1134,1134
BEGIN DESCRIPTION:
GREEN BRANCH 1.0
END DESCRIPTION:
XS GIS Cut Line= 4
      3764562.37     10184387.79      3762895.75     10183386.83
       3762538.3     10183379.59      3760707.65     10183516.67
#Sta/Elev= 30
  3055.9  269.24  3348.8  253.38  3778.2  239.22  3931.7  230.59  4260.8  223.72
  4928.6  223.47  4986.9  222.19    5000  219.73  5017.9  223.59  5087.9  221.78
    5328  223.72  5335.5  216.62  5374.9  216.62    5378  222.58  5398.1  222.99
  5638.8  224.02    5729  222.18  5817.1  224.14  6210.4  228.68  6290.6   234.4
  6330.7  241.26  6360.8  242.28    6431  250.23  6521.2  254.56  6653.1  258.19
    6812  258.77  6952.4  256.59  6982.5   253.5  7054.5  260.61  7193.3  264.03
#Mann= 5 ,-1 , 0
  3055.9     .17       0  4260.8     .15       0  4928.6     .09       0
  5017.9     .15       0  5817.1     .17       0
#XS Ineff= 3 ,-1
  4514.7  4192.7  224.32    4674  4514.7  224.17  5819.3  5879.4  224.18
Permanent Ineff=
       F       F       F
Bank Sta=4928.6,5017.9
XS Rating Curve= 0 ,0
Exp/Cntr=0.3,0.1

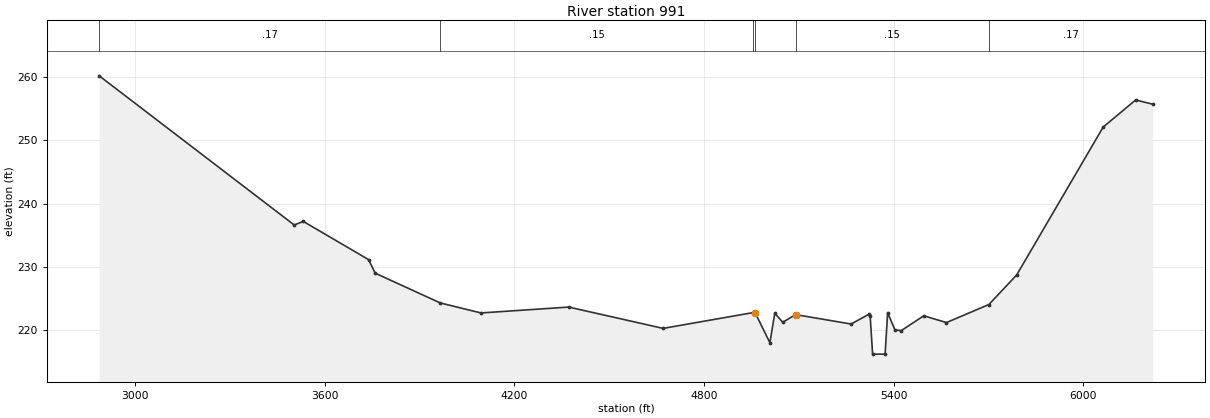
Type RM Length L Ch R = 1 ,991     ,0,0,0
BEGIN DESCRIPTION:
GREEN BRANCH 2.5
END DESCRIPTION:
XS GIS Cut Line= 3
      3764460.47      10184216.6       3762806.4     10182900.15
      3761603.23     10182696.39
#Sta/Elev= 30
    2886   260.2  3503.1  236.62    3532  237.18  3738.6  231.14  3759.4     229
  3965.5  224.29  4094.2  222.71  4371.9  223.64  4670.8  220.27  4955.9  222.77
  4962.3  222.71  5008.7     218  5024.1  222.68  5049.2  221.23  5089.8  222.45
  5265.6  220.96  5320.9  222.47    5326  222.22  5333.7   216.2  5373.3   216.2
  5381.3  222.76  5404.2  220.04  5424.5  219.92  5495.5  222.26  5567.5  221.19
  5701.6  224.04  5789.6  228.71  6063.5   252.1  6166.1  256.38  6220.3  255.71
#Mann= 6 ,-1 , 0
    2886     .17       0  3965.5     .15       0  4955.9     .12       0
  4962.3     .09       0  5089.8     .15       0  5701.6     .17       0
#XS Ineff= 2 , 0
       0  4962.3  222.71  5089.8       0  222.45
Permanent Ineff=
       F       F
Bank Sta=4962.3,5089.8
XS Rating Curve= 0 ,0
Exp/Cntr=0.3,0.1

Chan Stop Cuts=-1
Use User Specified Reach Order=0
Composite Channel Slope=5