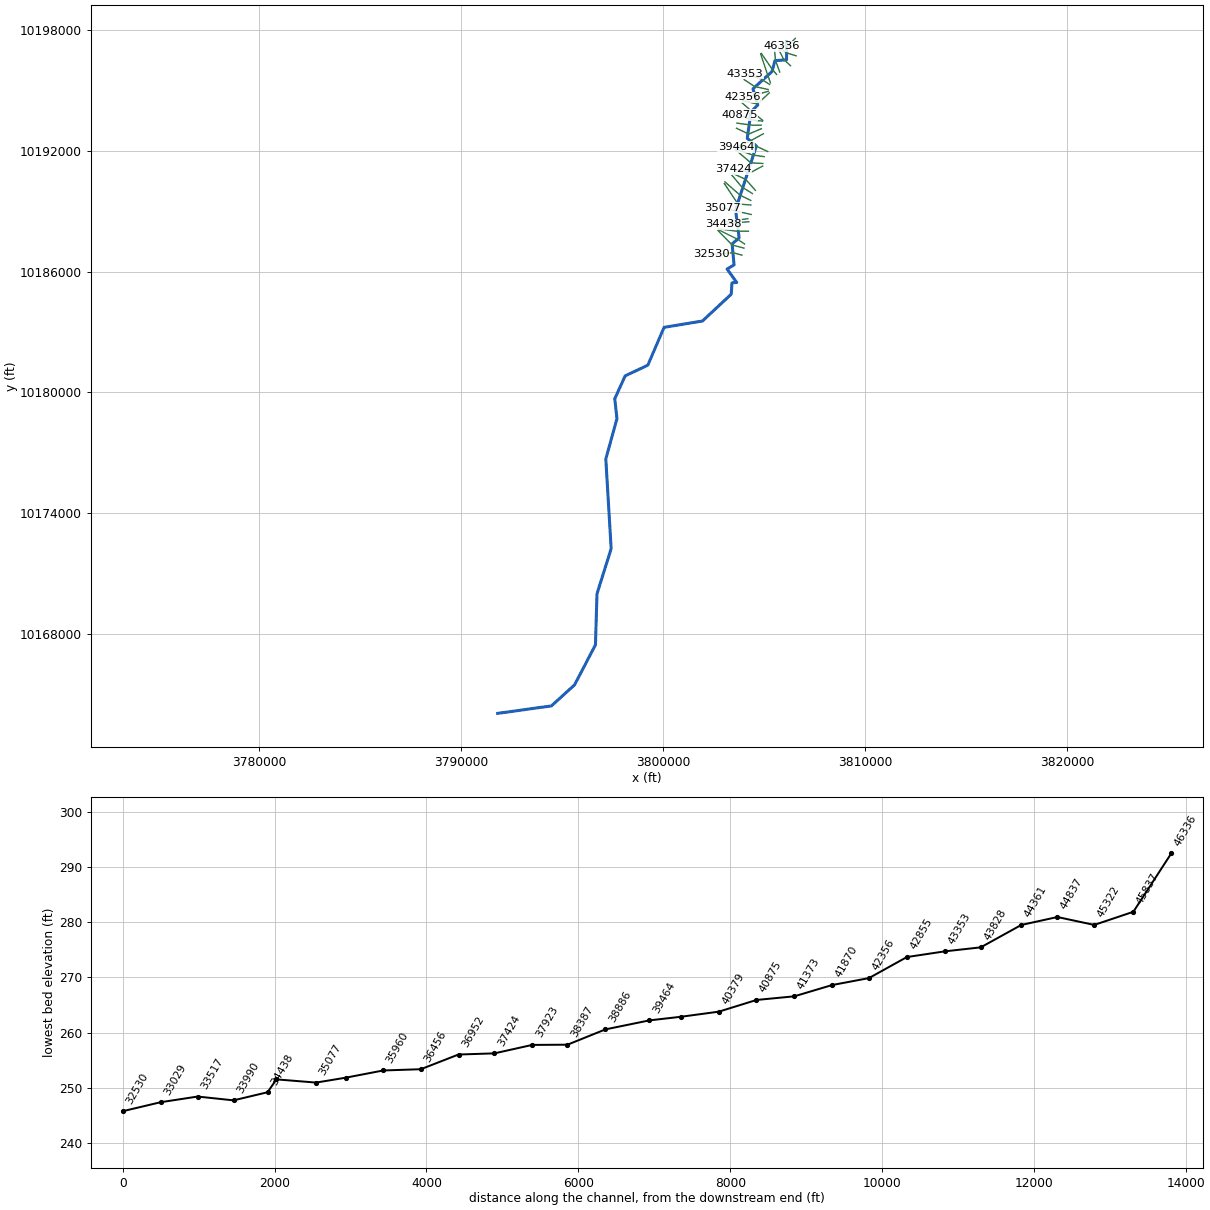
--- GUM BRANCH.prj (project) ---

Proj Title=GUM BRANCH Base Level Engineering
Current Plan=p01
Default Exp/Contr=0.3,0.1
English Units
Geom File=g01
Flow File=f01
Flow File=f02
Plan File=p01
Y Axis Title=Elevation
X Axis Title(PF)=Main Channel Distance
X Axis Title(XS)=Station
BEGIN DESCRIPTION:
GUM BRANCH
END DESCRIPTION:
DSS Export Rating Curves= 0
DSS Export Rating Curve Sorted= 0
DSS Export Volume Flow Curves= 0
DXF OffsetX= 0
DXF OffsetY= 0
DXF ScaleX= 1
DXF ScaleY= 10

--- GUM BRANCH.p01 (plan) ---

Plan Title=Multiple Run
Short Identifier=Multiple
Geom File=g01
Flow File=f01
Subcritical Flow
K Sum by GR= 0
Std Step Tol= 0.01
Critical Tol= 0.01
Num of Std Step Trials= 20
Max Error Tol= 0.3
Flow Tol Ratio= 0.001
Split Flow NTrial= 30
Split Flow Tol= 0.02
Split Flow Ratio= 0.02
Log Output Level= 0
Friction Slope Method= 1
Unsteady Friction Slope Method= 2
Unsteady Bridges Friction Slope Method= 1
Parabolic Critical Depth
Global Vel Dist=  1 , 1 , 1
Global Log Level= 0
CheckData=True
Encroach Param= -1, 0, 0, 0
BEGIN DESCRIPTION:
Multiple Run
END DESCRIPTION:

--- GUM BRANCH.f01 (steady flow) ---

Flow Title=Multiple
Program Version=4.10
Number of Profiles= 7
Profile Names=10-year,25-year,50-year,1pct_min,100-year,1pct_plu,500-year
River Rch & RM=GUM BRANCH,Reach-1         ,46336
     991    1388    1921     875    2643    7982    5167
River Rch & RM=GUM BRANCH,Reach-1         ,43353
    1269    1785    2474    1127    3402   10274    6651
River Rch & RM=GUM BRANCH,Reach-1         ,38886
    1478    2080    2883    1310    3957   11950    7714
River Rch & RM=GUM BRANCH,Reach-1         ,33517
    1579    2210    3051    1380    4167   12584    8044
River Rch & RM=GUM BRANCH,Reach-1         ,29126
    1849    2608    3621    1646    4971   15012    9701
River Rch & RM=GUM BRANCH,Reach-1         ,24319
    1676    2326    3191    1432    4326   13064    8232
River Rch & RM=GUM BRANCH,Reach-1         ,20852
    2083    2935    4070    1847    5577   16842   10841
River Rch & RM=GUM BRANCH,Reach-1         ,14576
    2135    3012    4180    1898    5732   17310   11156
River Rch & RM=GUM BRANCH,Reach-1         ,11820
    3909    5636    7937    3652   11028   33304   22031
River Rch & RM=GUM BRANCH,Reach-1         ,5000
    3709    5303    7426    3395   10253   30964   20232
Boundary for River Rch & Prof#=GUM BRANCH,Reach-1         , 1
Up Type= 0
Dn Type= 3
Dn Slope=0.005
Boundary for River Rch & Prof#=GUM BRANCH,Reach-1         , 2
Up Type= 0
Dn Type= 3
Dn Slope=0.005
Boundary for River Rch & Prof#=GUM BRANCH,Reach-1         , 3
Up Type= 0
Dn Type= 3
Dn Slope=0.005
Boundary for River Rch & Prof#=GUM BRANCH,Reach-1         , 4
Up Type= 0
Dn Type= 3
Dn Slope=0.005
Boundary for River Rch & Prof#=GUM BRANCH,Reach-1         , 5
Up Type= 0
Dn Type= 3
Dn Slope=0.005
Boundary for River Rch & Prof#=GUM BRANCH,Reach-1         , 6
Up Type= 0
Dn Type= 3
Dn Slope=0.005
Boundary for River Rch & Prof#=GUM BRANCH,Reach-1         , 7
Up Type= 0
Dn Type= 3
Dn Slope=0.005
DSS Import GetInterval= 0
DSS Import GetPeak= 0
DSS Import FillOption= 0

--- GUM BRANCH.f02 (steady flow) ---

Flow Title=Orig_BLE_Flow
Program Version=4.10
Number of Profiles= 7
Profile Names=10-year,25-year,50-year,1pct_min,100-year,1pct_plu,500-year
River Rch & RM=GUM BRANCH,Reach-1         ,46336
     991    1361    1670     673    2033    6138    3004
River Rch & RM=GUM BRANCH,Reach-1         ,43353
    1269    1750    2151     866    2617    7902    3867
River Rch & RM=GUM BRANCH,Reach-1         ,38886
    1478    2039    2507    1008    3044    9191    4485
River Rch & RM=GUM BRANCH,Reach-1         ,33517
    1579    2167    2653    1061    3205    9679    4677
River Rch & RM=GUM BRANCH,Reach-1         ,29126
    1849    2557    3149    1266    3824   11550    5640
River Rch & RM=GUM BRANCH,Reach-1         ,24319
    1676    2280    2775    1102    3328   10050    4786
River Rch & RM=GUM BRANCH,Reach-1         ,20852
    2083    2877    3539    1421    4290   12956    6303
River Rch & RM=GUM BRANCH,Reach-1         ,14576
    2135    2953    3635    1460    4409   13315    6486
River Rch & RM=GUM BRANCH,Reach-1         ,11820
    3909    5525    6902    2809    8483   25618   12809
River Rch & RM=GUM BRANCH,Reach-1         ,5000
    3709    5199    6457    2612    7887   23817   11763
Boundary for River Rch & Prof#=GUM BRANCH,Reach-1         , 1
Up Type= 0
Dn Type= 3
Dn Slope=0.005
Boundary for River Rch & Prof#=GUM BRANCH,Reach-1         , 2
Up Type= 0
Dn Type= 3
Dn Slope=0.005
Boundary for River Rch & Prof#=GUM BRANCH,Reach-1         , 3
Up Type= 0
Dn Type= 3
Dn Slope=0.005
Boundary for River Rch & Prof#=GUM BRANCH,Reach-1         , 4
Up Type= 0
Dn Type= 3
Dn Slope=0.005
Boundary for River Rch & Prof#=GUM BRANCH,Reach-1         , 5
Up Type= 0
Dn Type= 3
Dn Slope=0.005
Boundary for River Rch & Prof#=GUM BRANCH,Reach-1         , 6
Up Type= 0
Dn Type= 3
Dn Slope=0.005
Boundary for River Rch & Prof#=GUM BRANCH,Reach-1         , 7
Up Type= 0
Dn Type= 3
Dn Slope=0.005
DSS Import GetInterval= 0
DSS Import GetPeak= 0
DSS Import FillOption= 0

--- GUM BRANCH.g01 (geometry) ---

Geom Title=Existing Conditions
Program Version=4.10

River Reach=GUM BRANCH      ,Reach-1
Reach XY= 30
      3806128.23     10197381.84      3806124.14     10196503.67
      3805550.39     10196459.46      3805402.65      10195921.4
       3804459.4     10195063.47      3804696.27     10194258.21
      3804359.68      10193914.3      3804178.15     10192606.31
      3804628.03     10192225.75      3803598.85     10189060.69
      3803778.08     10187663.85      3803429.08      10187371.6
      3803526.07      10186326.8      3803179.69     10186122.81
      3803656.52     10185454.24       3803421.3     10185438.28
      3803384.83     10184874.53      3801961.97     10183543.63
      3800060.31     10183229.13      3799257.38     10181351.57
      3798135.41     10180823.06      3797619.81     10179685.16
       3797727.9     10178693.88      3797176.94     10176698.89
      3797441.74     10172246.86       3796739.9     10170009.46
      3796664.66     10167477.77      3795631.56     10165491.97
      3794485.83      10164447.4      3791825.98     10164076.55

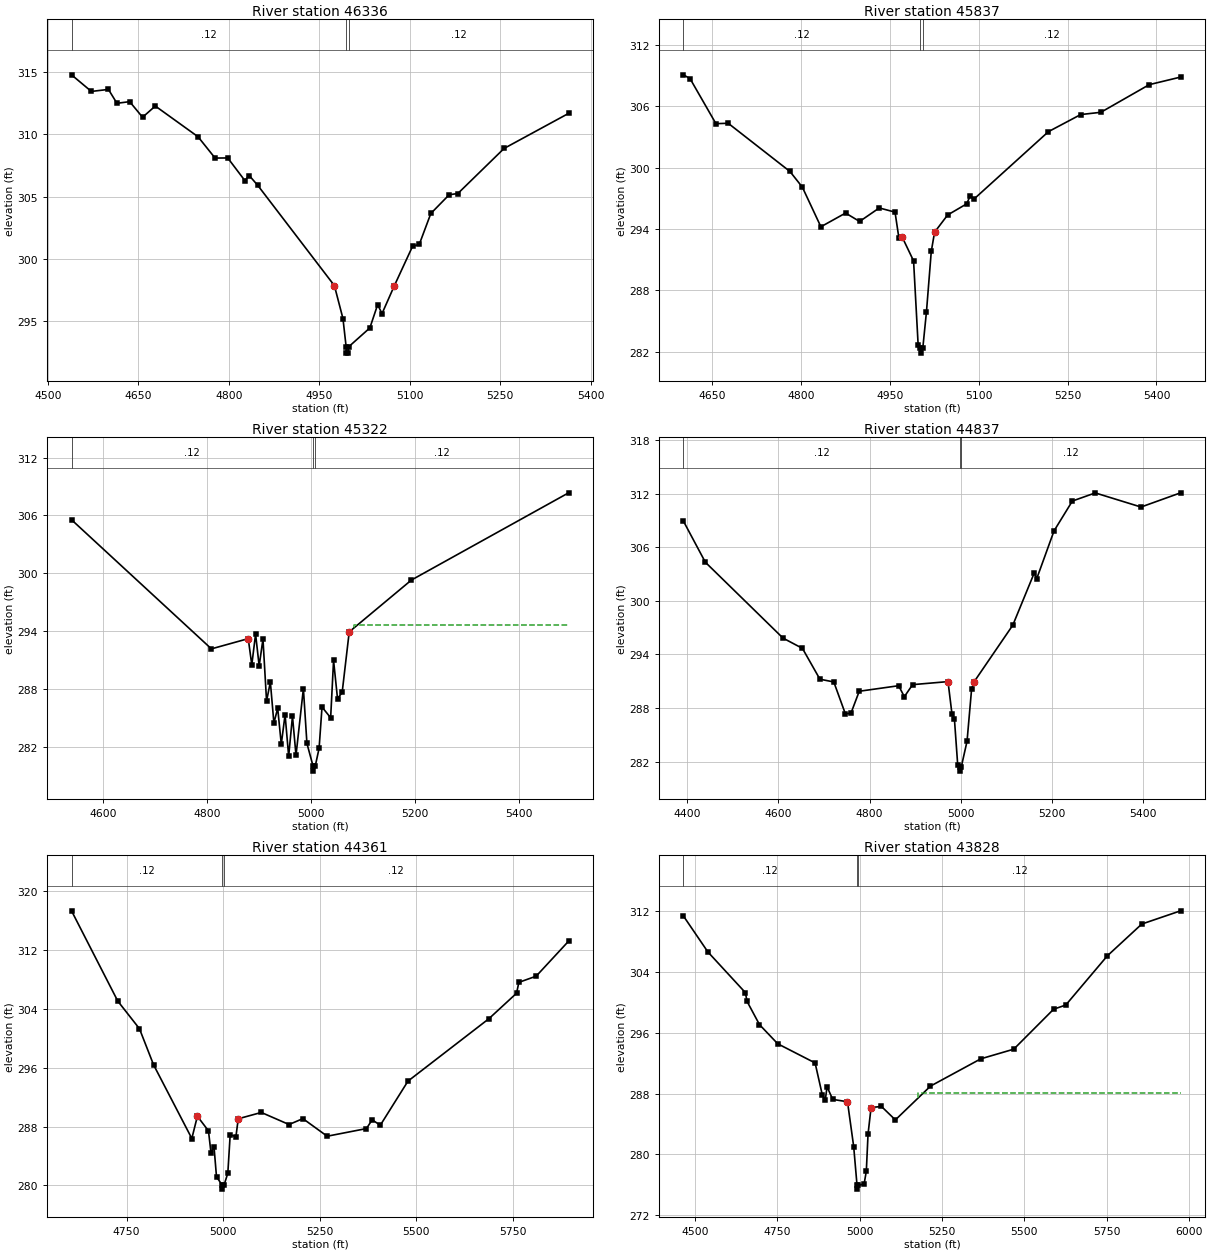
Type RM Length L Ch R = 1 ,46336   ,499,499,499
BEGIN DESCRIPTION:
GUM BRANCH 67.0
END DESCRIPTION:
XS GIS Cut Line= 3
      3806556.89     10197568.39      3806241.37     10197232.69
      3805882.01     10197178.65
#Sta/Elev= 30
  4539.3  314.75  4572.2  313.42  4600.5  313.58  4614.6  312.47  4635.7   312.6
  4657.1  311.35  4678.2  312.25    4749  309.79  4777.3  308.08  4798.3  308.09
  4826.6  306.28  4833.9  306.68  4848.1  305.89  4975.1  297.86  4989.3  295.22
  4994.6  292.95  4994.8  292.45  4998.3  292.45  4998.6  292.95  5033.9  294.47
  5046.8  296.33  5054.1  295.62  5074.3  297.83  5104.7  301.01  5115.8  301.16
    5135  303.64  5165.4  305.14  5179.8  305.24  5256.4  308.85  5363.4  311.66
#Mann= 3 ,-1 , 0
  4539.3     .12       0  4994.6     .07       0  4998.6     .12       0
Bank Sta=4975.1,5074.3
XS Rating Curve= 0 ,0
Exp/Cntr=0.3,0.1

Type RM Length L Ch R = 1 ,45837   ,515,515,515
BEGIN DESCRIPTION:
GUM BRANCH 66.0
END DESCRIPTION:
XS GIS Cut Line= 3
      3806600.17     10196701.84      3806218.17     10196815.66
        3805829.     10197022.44
#Sta/Elev= 30
  4601.4  309.06  4612.6  308.68  4656.2  304.29  4676.9  304.33  4781.2  299.62
  4802.1  298.09  4833.4  294.22  4875.1  295.56  4898.8  294.74    4932  296.06
  4958.6  295.65  4965.1  293.13  4970.3  293.26  4989.9  290.89  4997.6  282.71
  5001.5  282.38  5001.7  281.88  5005.5  282.38  5011.7  285.94  5019.8  291.82
  5025.4  293.69  5047.4  295.37  5079.6  296.46  5085.7  297.27  5091.4   296.9
  5217.6  303.51  5272.1  305.18  5306.1   305.4  5387.8   308.1  5440.7  308.84
#Mann= 3 ,-1 , 0
  4601.4     .12       0  5001.5     .07       0  5005.5     .12       0
#XS Ineff= 2 , 0
       0  4958.6  295.65               0
Permanent Ineff=
       F       F
Bank Sta=4970.3,5025.4
XS Rating Curve= 0 ,0
Exp/Cntr=0.3,0.1

Type RM Length L Ch R = 1 ,45322   ,485,485,485
BEGIN DESCRIPTION:
GUM BRANCH 65.0
END DESCRIPTION:
XS GIS Cut Line= 3
      3806317.82      10196211.1      3805981.52     10196526.12
      3805755.35     10196966.09
#Sta/Elev= 30
  4539.2  305.55  4808.1  292.17  4878.9  293.23  4885.7  290.51    4893   293.7
  4899.9   290.4  4907.2  293.19  4914.1  286.76  4921.4  288.74  4928.2  284.48
  4935.5  286.02  4942.4  282.29  4949.7  285.35  4956.6  281.04  4963.9  285.19
  4970.7  281.14  4984.9  288.05  4991.7  282.37  5003.6     280  5003.8   279.5
  5007.6     280  5015.1  281.87  5020.7  286.14  5037.3  285.03  5042.9  290.97
  5050.5  287.01  5059.4  287.65    5073  293.93  5192.5   299.3  5494.7  308.34
#Mann= 3 ,-1 , 0
  4539.2     .12       0  5003.6     .07       0  5007.6     .12       0
#XS Ineff= 2 , 0
       0    4893   293.7  5081.6       0  294.69
Permanent Ineff=
       F       F
Bank Sta=4878.9,5073
XS Rating Curve= 0 ,0
Exp/Cntr=0.3,0.1

Type RM Length L Ch R = 1 ,44837   ,476,476,476
BEGIN DESCRIPTION:
GUM BRANCH 64.0
END DESCRIPTION:
XS GIS Cut Line= 3
      3805785.67     10195895.95      3805577.42     10196467.18
      3805534.49     10196947.46
#Sta/Elev= 30
    4392   308.9    4440  304.31  4610.3  295.82  4652.9  294.67  4691.2  291.22
  4721.7  290.91    4747  287.35  4759.3  287.41  4777.5  289.87  4863.9  290.49
  4876.4  289.26  4894.5  290.61  4972.2  290.95  4980.8  287.35  4986.2  286.79
  4993.5  281.58  4997.4  281.43  4997.7  280.93  5001.4  281.43  5013.9  284.27
    5024  290.17  5029.8  290.96  5114.3  297.27  5161.6  303.15  5166.6  302.45
  5204.7  307.82  5244.9  311.16  5295.1  312.07  5395.5  310.49  5482.2  312.08
#Mann= 3 ,-1 , 0
    4392     .12       0  4997.4     .07       0  5001.4     .12       0
Bank Sta=4972.2,5029.8
XS Rating Curve= 0 ,0
Exp/Cntr=0.3,0.1

Type RM Length L Ch R = 1 ,44361   ,533,533,533
BEGIN DESCRIPTION:
GUM BRANCH 63.0
END DESCRIPTION:
XS GIS Cut Line= 3
      3805629.68     10195774.68      3805381.76     10196079.09
      3804876.78     10196817.42
#Sta/Elev= 30
  4607.4  317.31  4727.2  305.04  4783.3  301.29  4819.8  296.39  4918.9  286.37
  4933.3  289.39    4962  287.41  4968.5  284.44  4976.4  285.21  4982.8  281.17
    4998  279.99  4998.3  279.49    5002  279.99  5012.1  281.65  5018.2  286.86
  5033.1  286.63  5039.1  289.05  5098.8  289.91  5170.6  288.27  5206.5  289.07
  5269.4  286.68    5371  287.72  5385.9  288.91  5406.9  288.17  5478.6  294.17
  5687.9  302.64  5759.7  306.11  5765.7  307.59  5810.5  308.43  5894.5  313.19
#Mann= 3 ,-1 , 0
  4607.4     .12       0    4998     .07       0    5002     .12       0
Bank Sta=4933.3,5039.1
XS Rating Curve= 0 ,0
Exp/Cntr=0.3,0.1

Type RM Length L Ch R = 1 ,43828   ,475,475,475
BEGIN DESCRIPTION:
GUM BRANCH 62.0
END DESCRIPTION:
XS GIS Cut Line= 3
       3805326.4     10195363.09      3805149.66     10195868.38
      3804841.15     10196792.86
#Sta/Elev= 30
  4464.7  311.38    4539  306.65  4652.6  301.31  4657.9  300.14  4695.6  297.09
    4751  294.57  4864.5  292.05  4886.3  287.86  4895.5  287.17  4900.8  288.91
  4918.1  287.25  4962.9  286.94  4981.7  281.05  4991.9  275.94  4992.2  275.44
  4995.9  275.94  5013.4  276.12  5020.1   277.8  5025.3  282.67  5034.5  286.18
  5066.1  286.32  5108.3  284.55    5215     289  5367.8  292.59  5467.9  293.86
    5589  299.12  5625.9  299.67  5752.3  306.15  5856.8  310.33  5974.6  312.07
#Mann= 3 ,-1 , 0
  4464.7     .12       0  4991.9     .07       0  4995.9     .12       0
#XS Ineff= 2 , 0
       0  4900.8  288.91  5178.1       0  288.03
Permanent Ineff=
       F       F
Bank Sta=4962.9,5034.5
XS Rating Curve= 0 ,0
Exp/Cntr=0.3,0.1

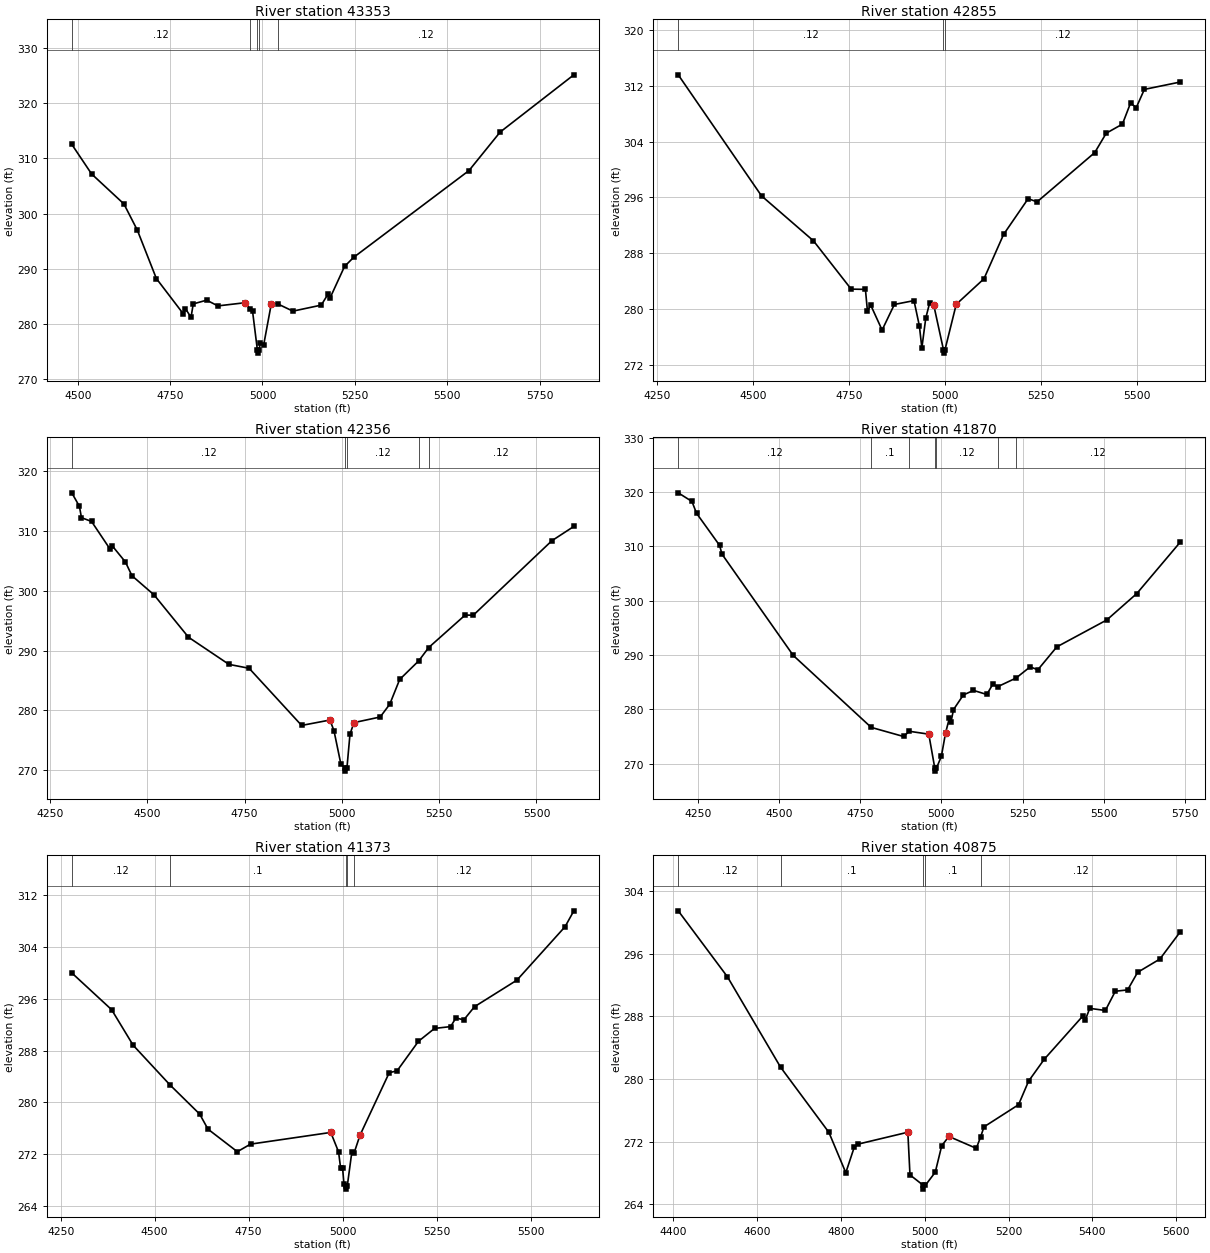
Type RM Length L Ch R = 1 ,43353   ,498,498,498
BEGIN DESCRIPTION:
GUM BRANCH 61.0
END DESCRIPTION:
XS GIS Cut Line= 3
      3805283.05     10195280.78      3804848.81     10195559.71
      3804048.29     10195822.33
#Sta/Elev= 30
  4483.9  312.55  4537.6  307.18    4625  301.75  4661.3     297  4712.8  288.23
  4785.5  281.85  4791.4  282.78  4806.6   281.2  4812.6  283.63  4848.9  284.31
  4879.3  283.27    4952  283.84  4966.1  282.74  4973.1   282.3  4986.3  275.21
  4986.5  274.71  4990.3  275.21  4994.2  276.51  5003.1  276.16  5023.9  283.67
  5043.2  283.57  5082.3  282.32  5158.9  283.41  5177.7  285.44    5183  284.73
    5222  290.42  5246.7  292.07  5558.8   307.8    5643  314.77  5842.5  325.15
#Mann= 5 ,-1 , 0
  4483.9     .12       0  4966.1      .1       0  4986.3     .07       0
  4990.3      .1       0  5043.2     .12       0
Bank Sta=4952,5023.9
XS Rating Curve= 0 ,0
Exp/Cntr=0.3,0.1

Type RM Length L Ch R = 1 ,42855   ,499,499,499
BEGIN DESCRIPTION:
GUM BRANCH 60.0
END DESCRIPTION:
XS GIS Cut Line= 3
      3805218.11     10195029.47       3804538.9     10195180.95
      3804026.62     10195519.06
#Sta/Elev= 30
  4304.1  313.59  4521.4  296.23  4656.9  289.78  4755.2  282.86  4792.4  282.82
  4797.6  279.73  4806.4  280.54  4835.9  276.99  4867.9  280.66  4919.1  281.21
  4933.1  277.59  4939.6  274.43  4949.8   278.7  4960.1  280.92  4970.3  280.65
  4995.9  274.18  4996.2  273.68    5000  274.18  5029.3  280.68  5101.6  284.34
  5152.8   290.7  5216.9  295.83  5240.1  295.37  5390.6  302.44  5420.6  305.22
  5462.8  306.52  5483.9  309.53    5499   308.9    5520   311.5  5613.8  312.56
#Mann= 3 ,-1 , 0
  4304.1     .12       0  4995.9     .07       0    5000     .12       0
Bank Sta=4970.3,5029.3
XS Rating Curve= 0 ,0
Exp/Cntr=0.3,0.1

Type RM Length L Ch R = 1 ,42356   ,486,486,486
BEGIN DESCRIPTION:
GUM BRANCH 59.0
END DESCRIPTION:
XS GIS Cut Line= 3
      3805226.74     10194942.82      3804558.18     10194756.25
      3803974.61      10194635.2
#Sta/Elev= 30
  4305.9  316.34  4325.5  314.09  4330.8  312.19  4356.7  311.56  4404.4  306.93
  4409.6  307.51  4443.8  304.79  4460.5   302.5  4517.3   299.3  4605.8  292.23
  4709.6   287.7  4761.6  287.04  4896.5   277.5  4969.2   278.4  4979.6  276.63
  4997.6  270.98  5008.3  270.37  5008.6  269.87  5012.9  270.37  5020.8  276.05
    5031  277.97  5098.4  278.91  5122.9  281.03  5148.5  285.18  5197.4  288.28
  5223.1  290.51  5316.9  295.94  5337.4  295.89  5539.5  308.34    5596  310.73
#Mann= 5 ,-1 , 0
  4305.9     .12       0  5008.3     .07       0  5012.9     .12       0
  5197.4      .1       0  5223.1     .12       0
Bank Sta=4969.2,5031
XS Rating Curve= 0 ,0
Exp/Cntr=0.3,0.1

Type RM Length L Ch R = 1 ,41870   ,497,497,497
BEGIN DESCRIPTION:
GUM BRANCH 58.0
END DESCRIPTION:
XS GIS Cut Line= 3
      3805267.83     10194861.06       3804674.3     10194309.86
      3803957.35      10194474.9
#Sta/Elev= 30
    4190  319.88  4232.2  318.29  4246.4  316.11  4317.3   310.2  4324.6  308.59
    4544  289.93    4784  276.67  4883.6  274.99  4901.4  275.95  4961.3  275.42
    4980  269.11  4980.3  268.61  4984.6  269.11    5000  271.32 5012.95  275.62
  5024.8   278.4    5030  277.75  5037.4  279.94  5067.7  282.64    5099  283.48
    5140  282.73  5158.4  284.62  5173.3  284.16  5230.1  285.76  5273.4  287.82
  5297.1  287.28  5355.5   291.5  5509.4  296.46  5601.8  301.33  5735.7  310.81
#Mann= 7 ,-1 , 0
    4190     .12       0    4784      .1       0  4901.4     .12       0
    4980     .07       0  4984.6     .12       0  5173.3      .1       0
  5230.1     .12       0
Bank Sta=4961.3,5012.95
XS Rating Curve= 0 ,0
Exp/Cntr=0.3,0.1

Type RM Length L Ch R = 1 ,41373   ,498,498,498
BEGIN DESCRIPTION:
GUM BRANCH 57.0
END DESCRIPTION:
XS GIS Cut Line= 3
      3804937.89     10193501.17      3804384.77     10193963.04
       3803921.7      10194368.2
#Sta/Elev= 30
  4279.4  300.02  4385.4  294.33  4442.7  288.83  4540.9  282.68  4619.7  278.18
  4641.8  275.85  4719.9  272.36    4755  273.53  4968.5  275.34  4989.3  272.33
  4994.7  269.84    5000  269.84  5003.6  267.33  5007.9  267.07  5008.2  266.57
  5012.5  267.07  5024.5  272.28  5030.2  272.09  5046.3  274.91  5124.1  284.58
    5145  284.87  5201.9  289.44  5244.7  291.43  5287.4  291.71  5301.5  293.05
  5322.5  292.75    5351  294.79  5463.9   298.9    5592  307.17  5615.3  309.62
#Mann= 5 ,-1 , 0
  4279.4     .12       0  4540.9      .1       0  5007.9     .07       0
  5012.5      .1       0  5030.2     .12       0
Bank Sta=4968.5,5046.3
XS Rating Curve= 0 ,0
Exp/Cntr=0.3,0.1

Type RM Length L Ch R = 1 ,40875   ,496,496,496
BEGIN DESCRIPTION:
GUM BRANCH 56.0
END DESCRIPTION:
XS GIS Cut Line= 3
      3804934.36     10193459.53      3804351.29     10193530.69
      3803788.55     10193765.08
#Sta/Elev= 30
  4412.6  301.52    4530  293.07  4656.6  281.51  4771.8  273.17  4812.1  268.01
  4832.2  271.27  4842.3  271.68    4960  273.19  4965.1  267.73  4996.5  266.41
  4996.9  265.91    5002  266.41  5025.4  268.08  5040.8  271.47  5057.9  272.65
  5123.2  271.13  5133.3  272.56  5141.6  273.88  5223.9  276.71  5247.8  279.72
  5285.4  282.54  5377.8   288.1  5383.2  287.59  5393.7  289.04  5430.9  288.77
  5454.7  291.23    5484   291.4  5507.8  293.65  5560.9  295.35  5609.6  298.84
#Mann= 5 ,-1 , 0
  4412.6     .12       0  4656.6      .1       0  4996.5     .07       0
    5002      .1       0  5133.3     .12       0
#XS Ineff= 2 , 0
       0                  5194.7       0  275.55
Permanent Ineff=
       F       F
Bank Sta=4960,5057.9
XS Rating Curve= 0 ,0
Exp/Cntr=0.3,0.1

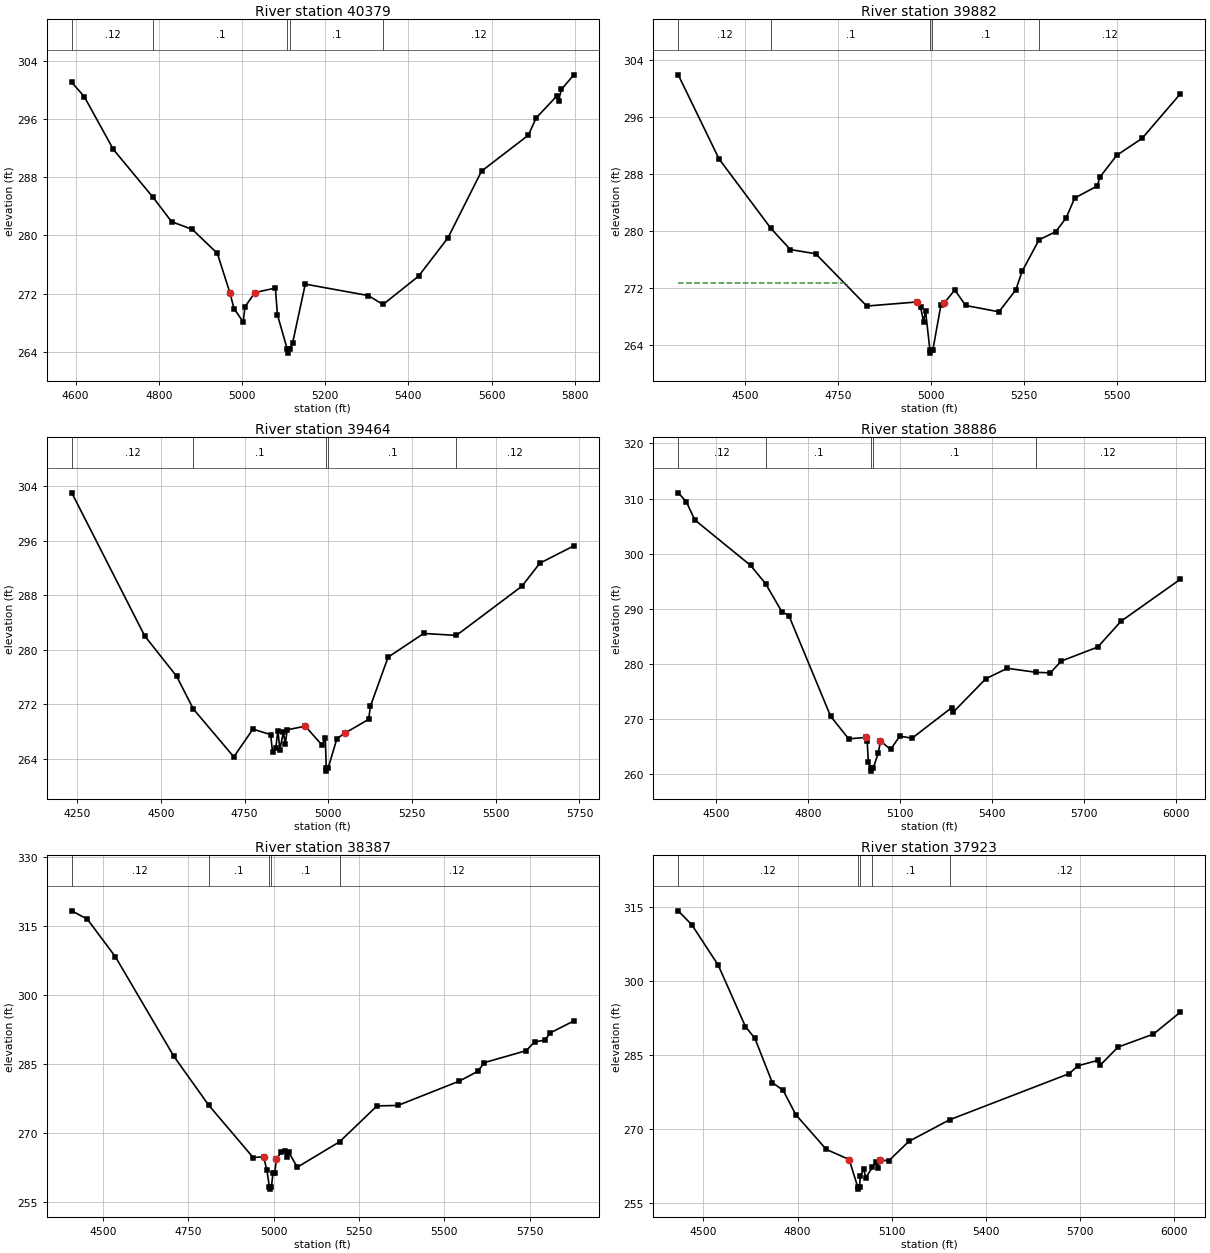
Type RM Length L Ch R = 1 ,40379   ,497,497,497
BEGIN DESCRIPTION:
GUM BRANCH 55.0
END DESCRIPTION:
XS GIS Cut Line= 3
      3804867.84     10193261.07      3804458.68     10193254.89
      3803667.88     10193361.07
#Sta/Elev= 30
  4590.8  301.07  4620.8  299.11  4690.8  291.84  4786.5  285.22  4830.8  281.89
  4880.8  280.82  4940.8  277.52 4970.88  272.12  4980.8  269.93  5002.9  268.08
  5007.4  270.18  5031.1  272.13  5080.3  272.75  5085.3  269.06  5109.1  264.29
  5109.5  263.79  5114.6  264.29  5121.9  265.24  5152.2  273.29  5303.5  271.72
  5339.2  270.49  5424.6  274.39  5495.2  279.66    5576  288.85  5688.6   293.8
  5707.1  296.16  5756.4  299.16  5761.5  298.57  5767.7  300.09  5797.9  302.11
#Mann= 5 ,-1 , 0
  4590.8     .12       0  4786.5      .1       0  5109.1     .07       0
  5114.6      .1       0  5339.2     .12       0
Bank Sta=4970.88,5031.1
XS Rating Curve= 0 ,0
Exp/Cntr=0.3,0.1

Type RM Length L Ch R = 1 ,39882   ,418,418,418
BEGIN DESCRIPTION:
GUM BRANCH 54.0
END DESCRIPTION:
XS GIS Cut Line= 3
      3804878.88     10193084.54      3804251.62     10192819.13
      3803646.16     10193108.84
#Sta/Elev= 30
  4318.9  301.94  4428.6  290.15  4568.7  280.37  4620.8  277.41  4689.2  276.82
  4826.6  269.48  4961.3  270.05  4971.5  269.38  4979.6   267.3    4985   268.8
  4996.6  263.37    4997  262.87  5002.1  263.37  5004.9  263.37  5026.3  269.59
  5035.6  269.93  5063.8  271.74  5092.9  269.56  5182.7  268.67    5228  271.74
  5245.1  274.35  5290.7  278.78  5335.8  279.92    5364  281.88  5386.7  284.64
  5447.6  286.34  5454.7  287.59    5500  290.64  5568.1  293.01  5671.2  299.27
#Mann= 5 ,-1 , 0
  4318.9     .12       0  4568.7      .1       0  4996.6     .07       0
  5002.1      .1       0  5290.7     .12       0
#XS Ineff= 2 , 0
       0  4773.8  272.65               0
Permanent Ineff=
       F       F
Bank Sta=4961.3,5035.6
XS Rating Curve= 0 ,0
Exp/Cntr=0.3,0.1

Type RM Length L Ch R = 1 ,39464   ,578,578,578
BEGIN DESCRIPTION:
GUM BRANCH 53.0
END DESCRIPTION:
XS GIS Cut Line= 3
      3804972.62     10192831.08      3804300.34     10192464.56
      3803625.35     10192178.27
#Sta/Elev= 30
  4234.3  303.04  4452.1  282.04  4547.3  276.13  4597.3  271.32  4718.1   264.3
    4775  268.37    4828  267.57  4833.7     265  4843.4  265.63  4849.8  268.16
  4855.5  265.38    4866  267.88  4871.7  266.23  4877.6  268.28  4931.5   268.8
  4980.9  266.06  4991.3  267.04    4994  262.71  4994.5  262.21    5000  262.71
  5025.8  266.98  5049.5  267.78  5120.5   269.8  5125.9  271.74  5178.7  278.93
  5285.1  282.41  5382.4  282.12  5578.4  289.35  5631.8  292.72  5733.2  295.26
#Mann= 5 ,-1 , 0
  4234.3     .12       0  4597.3      .1       0    4994     .07       0
    5000      .1       0  5382.4     .12       0
#XS Ineff= 2 , 0
       0                  5125.9       0  271.74
Permanent Ineff=
       F       F
Bank Sta=4931.5,5049.5
XS Rating Curve= 0 ,0
Exp/Cntr=0.3,0.1

Type RM Length L Ch R = 1 ,38886   ,499,499,499
BEGIN DESCRIPTION:
GUM BRANCH 52.0
END DESCRIPTION:
XS GIS Cut Line= 3
       3805191.3     10191952.59      3804626.85     10192219.31
      3803614.91     10192133.13
#Sta/Elev= 30
  4375.7  311.03  4401.6  309.45    4430  306.11  4611.8  297.88  4660.9  294.57
  4714.2  289.47    4737  288.79  4873.5  270.52  4932.5  266.43  4987.4  266.69
  4992.9  265.98  4996.7  262.17    5006  261.08  5006.5  260.58  5012.1  261.08
  5029.1  263.83  5036.2  266.06  5069.2  264.51  5099.4  266.92  5139.5  266.55
  5269.4  272.11  5274.4   271.3  5380.4  277.33  5450.6  279.22  5545.1  278.49
  5591.1  278.39  5626.8  280.53    5746  283.08    5822  287.75  6015.6  295.36
#Mann= 5 ,-1 , 0
  4375.7     .12       0  4660.9      .1       0    5006     .07       0
  5012.1      .1       0  5545.1     .12       0
#XS Ineff= 2 , 0
       0                  5269.4       0  272.11
Permanent Ineff=
       F       F
Bank Sta=4987.4,5036.2
XS Rating Curve= 0 ,0
Exp/Cntr=0.3,0.1

Type RM Length L Ch R = 1 ,38387   ,464,464,464
BEGIN DESCRIPTION:
GUM BRANCH 51.0
END DESCRIPTION:
XS GIS Cut Line= 3
      3805014.26     10191699.11      3804428.29     10191782.71
      3803601.97     10192084.19
#Sta/Elev= 30
  4408.1  318.29  4453.7  316.48  4535.8  308.32  4707.5  286.65  4809.3  276.07
  4939.8  264.67  4970.1  264.85  4980.2  261.86  4987.2  258.31  4987.7  257.81
  4993.4  258.31  4997.7  261.29  5002.9  261.29  5007.8  264.32  5021.8  265.79
  5032.4  266.03  5038.3   264.9  5043.7  265.89  5068.9  262.57  5192.9  268.09
  5302.7   275.9  5363.8  275.99  5543.4  281.27  5597.6  283.39  5617.5  285.31
  5739.7  287.89    5765  289.83  5795.5  290.19  5809.5  291.73  5879.6  294.36
#Mann= 5 ,-1 , 0
  4408.1     .12       0  4809.3      .1       0  4987.2     .07       0
  4993.4      .1       0  5192.9     .12       0
Bank Sta=4970.1,5007.8
XS Rating Curve= 0 ,0
Exp/Cntr=0.3,0.1

Type RM Length L Ch R = 1 ,37923   ,499,499,499
BEGIN DESCRIPTION:
GUM BRANCH 50.0
END DESCRIPTION:
XS GIS Cut Line= 4
      3804951.72     10191358.83      3804372.28     10191392.18
      3804344.91     10191401.04      3803591.93     10192045.22
#Sta/Elev= 30
  4419.6  314.28  4463.5  311.39  4547.1  303.24  4633.8  290.77  4663.9  288.39
  4719.3  279.41    4754  277.82  4794.1  272.91  4891.4  265.84  4964.4  263.78
  4991.3  258.27  4991.8  257.77  4997.5  258.27  4999.7  260.38  5011.3  261.94
  5016.5  260.02  5038.2  262.17  5048.3   263.2  5054.8     262  5062.5  263.66
  5090.7  263.54  5154.7  267.47  5284.3  271.85  5665.2  281.21  5693.7  282.82
  5757.4  283.92    5764  282.91  5821.1  286.61  5934.1  289.25  6019.7   293.7
#Mann= 5 ,-1 , 0
  4419.6     .12       0  4991.3     .07       0  4997.5     .12       0
  5038.2      .1       0  5284.3     .12       0
Bank Sta=4964.4,5062.5
XS Rating Curve= 0 ,0
Exp/Cntr=0.3,0.1

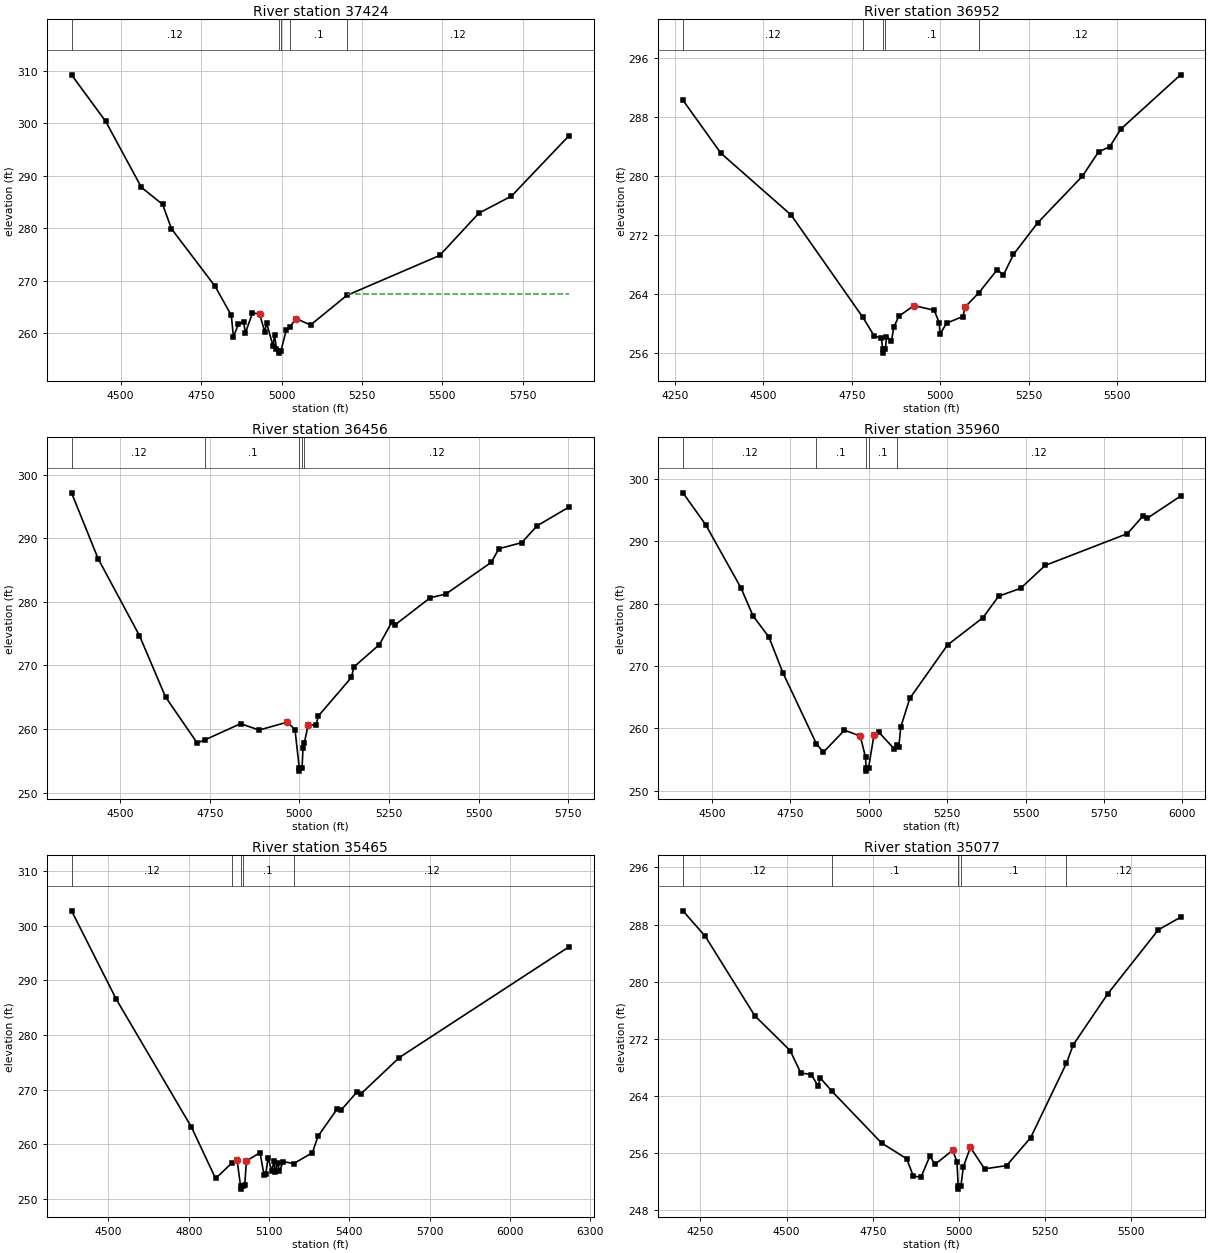
Type RM Length L Ch R = 1 ,37424   ,472,472,472
BEGIN DESCRIPTION:
GUM BRANCH 49.0
END DESCRIPTION:
XS GIS Cut Line= 4
      3804941.33     10191230.36      3804398.38     10190939.23
      3804362.66     10190931.12      3803481.18     10191080.77
#Sta/Elev= 30
  4347.3  309.21  4453.4  300.35  4564.6  287.78  4630.4  284.55    4658   279.9
  4793.8  268.94    4844  263.42  4850.5  259.36  4865.9  261.71  4882.1   262.2
  4887.8   260.1  4909.7  263.87  4931.7  263.72  4947.9   260.3  4953.6  262.01
  4973.3  257.67  4978.5  259.64  4984.4  257.02  4990.9  256.74  4991.4  256.24
  4998.5  256.74    5015  260.71  5025.6   261.2  5045.5  262.82  5090.2  261.59
  5203.1  267.23  5491.7  274.83  5613.5  282.88  5714.9  286.13  5894.1  297.65
#Mann= 5 ,-1 , 0
  4347.3     .12       0  4990.9     .07       0  4998.5     .12       0
  5025.6      .1       0  5203.1     .12       0
#XS Ineff= 2 , 0
       0                  5205.7       0  267.41
Permanent Ineff=
       F       F
Bank Sta=4931.7,5045.5
XS Rating Curve= 0 ,0
Exp/Cntr=0.3,0.1

Type RM Length L Ch R = 1 ,36952   ,496,496,496
BEGIN DESCRIPTION:
GUM BRANCH 48.0
END DESCRIPTION:
XS GIS Cut Line= 3
      3804583.69     10190025.51      3804102.14     10190569.89
       3803486.5     10190855.34
#Sta/Elev= 30
  4273.2  290.23  4380.4  283.06  4578.7  274.71  4781.3  260.87  4812.9   258.4
  4833.8  258.01  4837.5  256.53    4838  256.03  4845.1  256.53    4848  258.27
  4862.2  257.69  4868.9  259.57  4883.1  261.03  4925.8  262.46  4982.7  261.83
  4996.9  260.16  4999.5  258.62    5018  260.09  5063.8  260.98  5070.9   262.3
  5108.4  264.16  5160.9  267.31  5178.3  266.59  5206.8  269.38  5275.5  273.67
  5401.5  279.96  5446.9  283.24  5478.7  283.94  5510.1  286.33  5678.6  293.66
#Mann= 5 ,-1 , 0
  4273.2     .12       0  4781.3      .1       0  4837.5     .07       0
  4845.1      .1       0  5108.4     .12       0
Bank Sta=4925.8,5070.9
XS Rating Curve= 0 ,0
Exp/Cntr=0.3,0.1

Type RM Length L Ch R = 1 ,36456   ,496,496,496
BEGIN DESCRIPTION:
GUM BRANCH 47.0
END DESCRIPTION:
XS GIS Cut Line= 3
      3804434.38     10189865.78      3803896.68     10190205.27
      3803413.55     10190782.45
#Sta/Elev= 30
  4364.1  297.13  4438.2  286.78  4553.5  274.69  4626.5  265.02  4714.7   257.8
  4737.7  258.32  4835.9  260.83  4887.7  259.83  4966.5  261.08  4987.7  259.88
  4999.6  253.87  5000.1  253.37  5007.4  253.87    5010  256.98  5013.8  257.81
  5024.3  260.61  5046.4  260.66    5053  262.05  5145.3  268.11  5151.9  269.74
  5223.4  273.28  5258.6  276.87  5266.3  276.34  5365.2  280.64  5408.2   281.2
  5535.7  286.21  5556.5  288.34  5620.5   289.3  5663.2  291.94  5752.7  294.91
#Mann= 5 ,-1 , 0
  4364.1     .12       0  4737.7      .1       0  4999.6     .07       0
  5007.4      .1       0  5013.8     .12       0
Bank Sta=4966.5,5024.3
XS Rating Curve= 0 ,0
Exp/Cntr=0.3,0.1

Type RM Length L Ch R = 1 ,35960   ,495,495,495
BEGIN DESCRIPTION:
GUM BRANCH 46.0
END DESCRIPTION:
XS GIS Cut Line= 3
      3804351.02     10189525.51      3803820.02     10189788.83
      3803073.28     10190445.64
#Sta/Elev= 30
  4407.3  297.78  4479.7  292.67  4591.8  282.58  4631.1  278.02  4681.5  274.64
  4726.3   268.9    4833  257.52  4855.2  256.17  4922.5  259.71  4972.9  258.76
  4989.7  255.37  4991.4  253.64  4991.9  253.14  4999.2  253.64  5016.9     259
  5031.1  259.43  5081.4   256.7  5090.7  257.28  5095.6  256.95  5102.3  260.24
  5130.8   264.8  5251.3  273.38  5364.2  277.76  5414.4   281.2  5484.7  282.47
  5562.5  286.13  5825.3  291.24  5874.6  294.07  5888.8  293.72  5994.5  297.25
#Mann= 5 ,-1 , 0
  4407.3     .12       0    4833      .1       0  4991.4     .07       0
  4999.2      .1       0  5090.7     .12       0
Bank Sta=4972.9,5016.9
XS Rating Curve= 0 ,0
Exp/Cntr=0.3,0.1

Type RM Length L Ch R = 1 ,35465   ,388,388,388
BEGIN DESCRIPTION:
GUM BRANCH 45.0
END DESCRIPTION:
XS GIS Cut Line= 3
      3804354.51      10189299.8       3803718.3     10189348.85
      3803043.49     10190367.03
#Sta/Elev= 30
  4361.9  302.74  4529.1  286.56  4809.9  263.18  4900.2  253.78  4960.9   256.6
  4980.4  257.19  4993.7  252.33  4994.2  251.83  5001.8  252.33  5009.3  252.63
  5015.3  256.99  5066.4  258.49  5081.5  254.33  5087.5  254.51  5096.5  257.58
  5110.6  255.06  5117.6  256.89  5123.6  255.03  5132.6  256.69  5138.6  255.11
  5153.6  256.86  5192.1  256.51  5261.9  258.48    5283   261.5  5355.2  266.54
  5370.2  266.32  5427.4  269.54  5442.4  269.21  5586.8   275.9  6221.5  296.17
#Mann= 5 ,-1 , 0
  4361.9     .12       0  4960.9      .1       0  4993.7     .07       0
  5001.8      .1       0  5192.1     .12       0
Bank Sta=4980.4,5015.3
XS Rating Curve= 0 ,0
Exp/Cntr=0.3,0.1

Type RM Length L Ch R = 1 ,35077   ,522,522,522
BEGIN DESCRIPTION:
Mapping XS 69407815
END DESCRIPTION:
XS GIS Cut Line= 3
      3804371.24     10188828.94      3803598.72     10189002.54
      3802965.06     10189154.44
#Sta/Elev= 30
  4199.2  289.92  4264.2  286.33  4407.7  275.22  4510.3  270.35  4540.9  267.22
  4571.7  266.99  4591.8  265.33  4596.9  266.55  4631.5  264.65  4775.3  257.41
  4848.4   255.2    4867  252.81  4889.4  252.59  4915.4  255.57  4930.4  254.42
  4981.6  256.39    4994  254.81  4997.5  251.45    4998  250.95  5005.7  251.45
  5012.4  254.04    5033   256.8  5074.1  253.79  5137.9  254.24  5207.8  258.15
  5311.7  268.59  5331.2  271.15    5432  278.33    5578  287.25  5642.6  289.02
#Mann= 5 ,-1 , 0
  4199.2     .12       0  4631.5      .1       0  4997.5     .07       0
  5005.7      .1       0  5311.7     .12       0
Bank Sta=4981.6,5033
XS Rating Curve= 0 ,0
Exp/Cntr=0.3,0.1

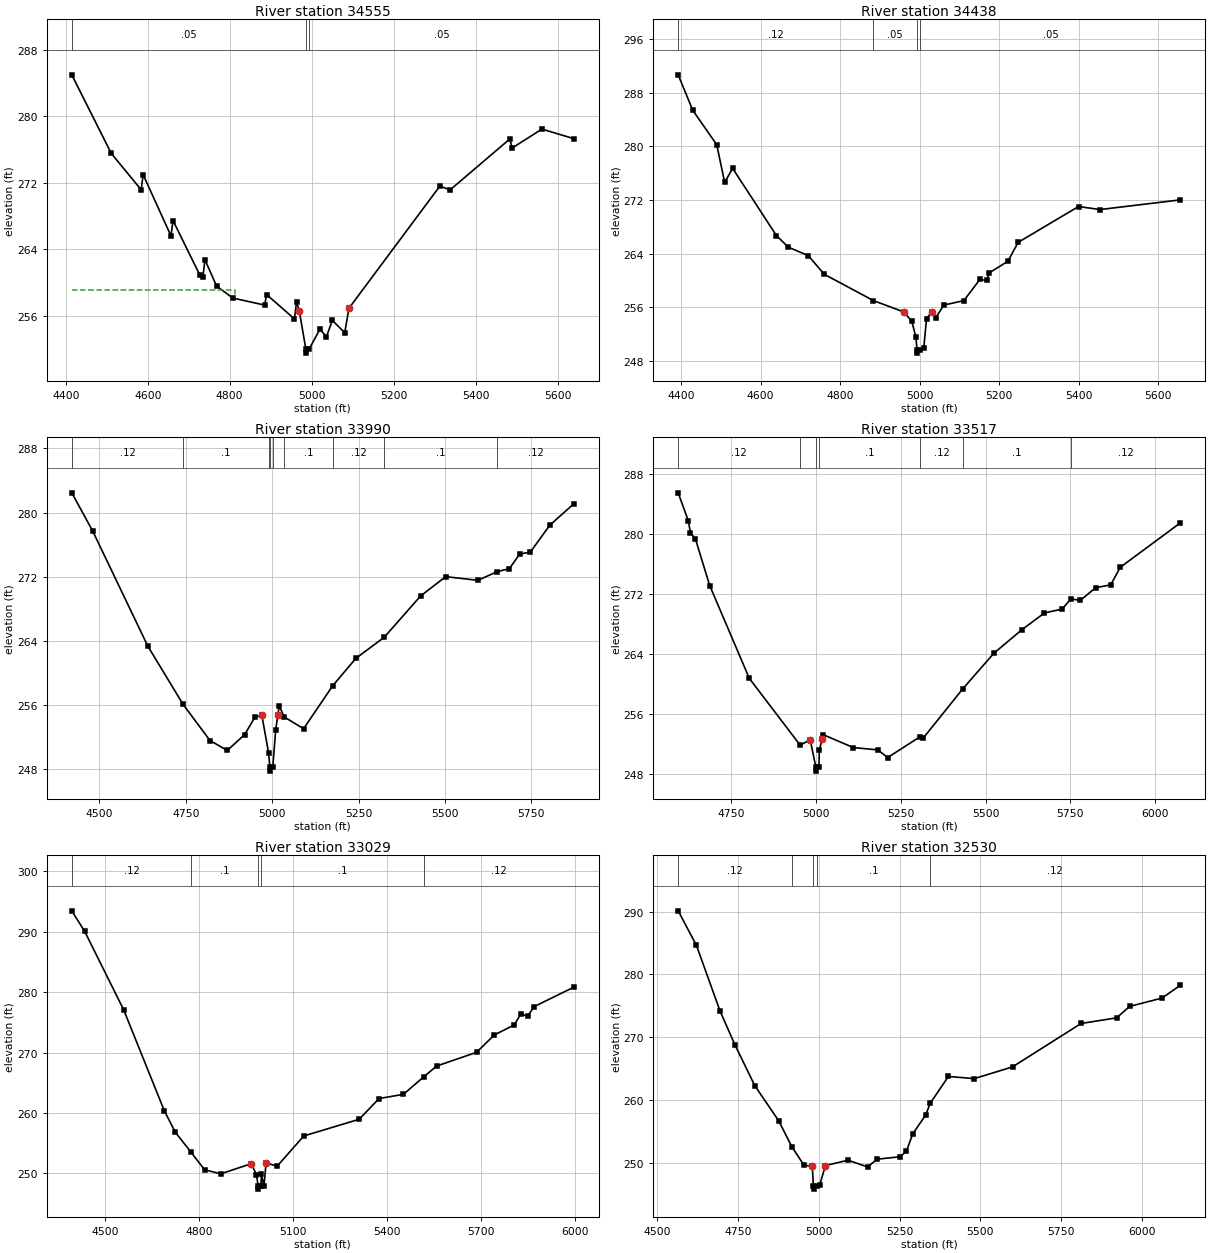
Type RM Length L Ch R = 1 ,34555   ,117,117,117
BEGIN DESCRIPTION:
GUM BRANCH 44.0
END DESCRIPTION:
XS GIS Cut Line= 3
      3804207.97     10188618.98       3803627.9     10188540.93
      3802993.67     10188455.96
#Sta/Elev= 30
  4414.7  284.96  4511.1  275.52  4583.9  271.16  4588.9  272.96  4656.7  265.62
  4661.8  267.45  4727.6  260.86  4734.6  260.64  4739.6  262.76    4768  259.59
  4807.4  258.15  4885.2   257.3  4890.3  258.56    4958  255.64  4963.1  257.71
  4969.8   256.6  4985.8  252.03  4986.3  251.53  4994.1  252.03  5020.2  254.41
    5036  253.49  5050.5  255.46  5080.8  253.98  5090.9  256.91  5312.8  271.59
  5337.9  271.14  5483.9  277.27  5488.9  276.16  5561.9  278.44  5639.9  277.29
#Mann= 3 ,-1 , 0
  4414.7     .05       0  4985.8     .03       0  4994.1     .05       0
#XS Ineff= 2 , 0
       0  4812.4  259.16               0
Permanent Ineff=
       F       F
Bank Sta=4969.8,5090.9
XS Rating Curve= 0 ,0
Exp/Cntr=0.3,0.1

Type RM Length L Ch R = 1 ,34438   ,448,448,448
BEGIN DESCRIPTION:
GUM BRANCH 43.0
END DESCRIPTION:
XS GIS Cut Line= 3
      3804254.62      10188467.5      3803648.26     10188428.59
      3802997.82     10188342.66
#Sta/Elev= 30
  4392.4  290.66  4429.2  285.37  4489.4  280.26  4509.4  274.64  4529.4  276.73
  4639.7  266.71  4669.7  264.98  4719.8  263.73  4759.9  260.95  4883.6  257.03
  4960.3  255.33  4980.4  253.94  4990.4  251.63  4993.6   249.7  4994.1   249.2
  5001.9   249.7  5010.5  249.98  5017.4   254.3  5030.7   255.4  5040.8  254.48
  5060.9  256.36  5111.4  257.02  5151.7  260.18  5169.4  260.02  5174.4  261.13
  5222.3  262.89  5247.9   265.7  5399.9  271.04  5454.3  270.59  5656.1  272.03
#Mann= 4 ,-1 , 0
  4392.4     .12       0  4883.6     .05       0  4993.6     .03       0
  5001.9     .05       0
Bank Sta=4960.3,5030.7
XS Rating Curve= 0 ,0
Exp/Cntr=0.3,0.1

Type RM Length L Ch R = 1 ,33990   ,473,473,473
BEGIN DESCRIPTION:
GUM BRANCH 42.0
END DESCRIPTION:
XS GIS Cut Line= 3
      3804237.86     10188003.19      3803657.98     10187998.75
      3802792.69     10188115.25
#Sta/Elev= 30
  4420.1  282.46  4480.1  277.74  4640.1  263.33  4741.9  256.08  4820.1  251.55
  4870.1  250.31  4920.1  252.28  4950.1  254.46  4970.1  254.69  4989.5  250.03
  4993.4  248.23  4993.9  247.73  5001.8  248.23  5010.2  252.89 5016.33  254.71
  5020.3  255.87  5034.9  254.49  5090.9  253.02  5175.1  258.38  5242.3  261.81
  5324.4  264.44  5429.3  269.58  5502.1     272  5595.5  271.54  5650.7  272.62
  5686.3  272.99  5716.5  274.83  5746.8  275.05  5803.3  278.42  5873.1   281.1
#Mann= 9 ,-1 , 0
  4420.1     .12       0  4741.9      .1       0  4989.5     .12       0
  4993.4     .07       0  5001.8     .12       0  5034.9      .1       0
  5175.1     .12       0  5324.4      .1       0  5650.7     .12       0
Bank Sta=4970.1,5016.33
XS Rating Curve= 0 ,0
Exp/Cntr=0.3,0.1

Type RM Length L Ch R = 1 ,33517   ,488,488,488
BEGIN DESCRIPTION:
GUM BRANCH 41.0
END DESCRIPTION:
XS GIS Cut Line= 3
      3804043.19     10187366.03      3803706.23     10187594.67
      3802746.15     10188076.49
#Sta/Elev= 30
  4592.8  285.52  4622.9  281.77    4629  280.18  4643.9  279.35  4685.9  273.15
  4802.6  260.79  4952.5  251.89  4982.3  252.59  4999.2  248.92  4999.7  248.42
  5007.8  248.92  5009.4   251.2 5017.19   252.7  5020.2  253.29  5109.5  251.56
  5182.1  251.25  5210.8  250.23  5307.4  253.03  5316.2  252.85  5431.9  259.36
  5524.1  264.13  5606.5  267.26  5673.5  269.51  5725.5  270.02  5751.2  271.37
  5779.6  271.19  5824.3  272.87    5869  273.25  5896.9  275.59  6074.2  281.51
#Mann= 7 ,-1 , 0
  4592.8     .12       0  4952.5      .1       0  4999.2     .07       0
  5007.8      .1       0  5307.4     .12       0  5431.9      .1       0
  5751.2     .12       0
Bank Sta=4982.3,5017.19
XS Rating Curve= 0 ,0
Exp/Cntr=0.3,0.1

Type RM Length L Ch R = 1 ,33029   ,499,499,499
BEGIN DESCRIPTION:
GUM BRANCH 40.0
END DESCRIPTION:
XS GIS Cut Line= 3
      3804017.85     10187161.07      3803431.82     10187314.58
       3802733.8     10188026.46
#Sta/Elev= 30
  4394.2  293.45  4435.5  290.04  4559.6   277.1  4689.5  260.37  4724.7   256.8
  4775.4  253.47    4818   250.6  4869.7  249.92  4967.2   251.6  4983.4   249.8
  4989.4  247.89  4989.9  247.39  4998.1  247.89  4999.5   249.9  5007.5  247.89
  5014.5  251.73  5049.9   251.2  5134.8  256.19  5311.5  258.95  5375.1  262.38
  5452.9  263.08  5518.5  266.01  5558.9  267.76  5686.2  270.03  5742.8   272.9
  5806.5  274.56  5827.7   276.4    5849     276  5870.1   277.6    5997  280.82
#Mann= 5 ,-1 , 0
  4394.2     .12       0  4775.4      .1       0  4989.4     .07       0
  4998.1      .1       0  5518.5     .12       0
Bank Sta=4967.2,5014.5
XS Rating Curve= 0 ,0
Exp/Cntr=0.3,0.1

Type RM Length L Ch R = 1 ,32530   ,482,482,482
BEGIN DESCRIPTION:
GUM BRANCH 39.0
END DESCRIPTION:
XS GIS Cut Line= 3
      3803917.89     10186811.06      3803498.26     10186928.29
       3802381.2     10186849.94
#Sta/Elev= 30
  4564.3  290.13  4620.8  284.63  4694.3  274.11  4740.8  268.69  4801.9  262.23
  4875.4  256.68  4916.7  252.49  4954.1  249.56  4979.7   249.4  4983.2  246.26
  4983.7  245.76  4993.5  246.26  5002.7  246.42  5020.5  249.52  5090.6  250.37
  5150.8   249.3  5180.8  250.53    5251  250.92  5271.1  251.78  5291.1  254.58
  5331.2  257.59  5344.8  259.43  5401.4  263.72  5481.6  263.38  5600.1  265.25
  5812.4  272.17  5922.7  273.07  5962.8  274.89    6063  276.22  6119.8  278.25
#Mann= 5 ,-1 , 0
  4564.3     .12       0  4916.7      .1       0  4983.2     .07       0
  4993.5      .1       0  5344.8     .12       0
Bank Sta=4979.7,5020.5
XS Rating Curve= 0 ,0
Exp/Cntr=0.3,0.1