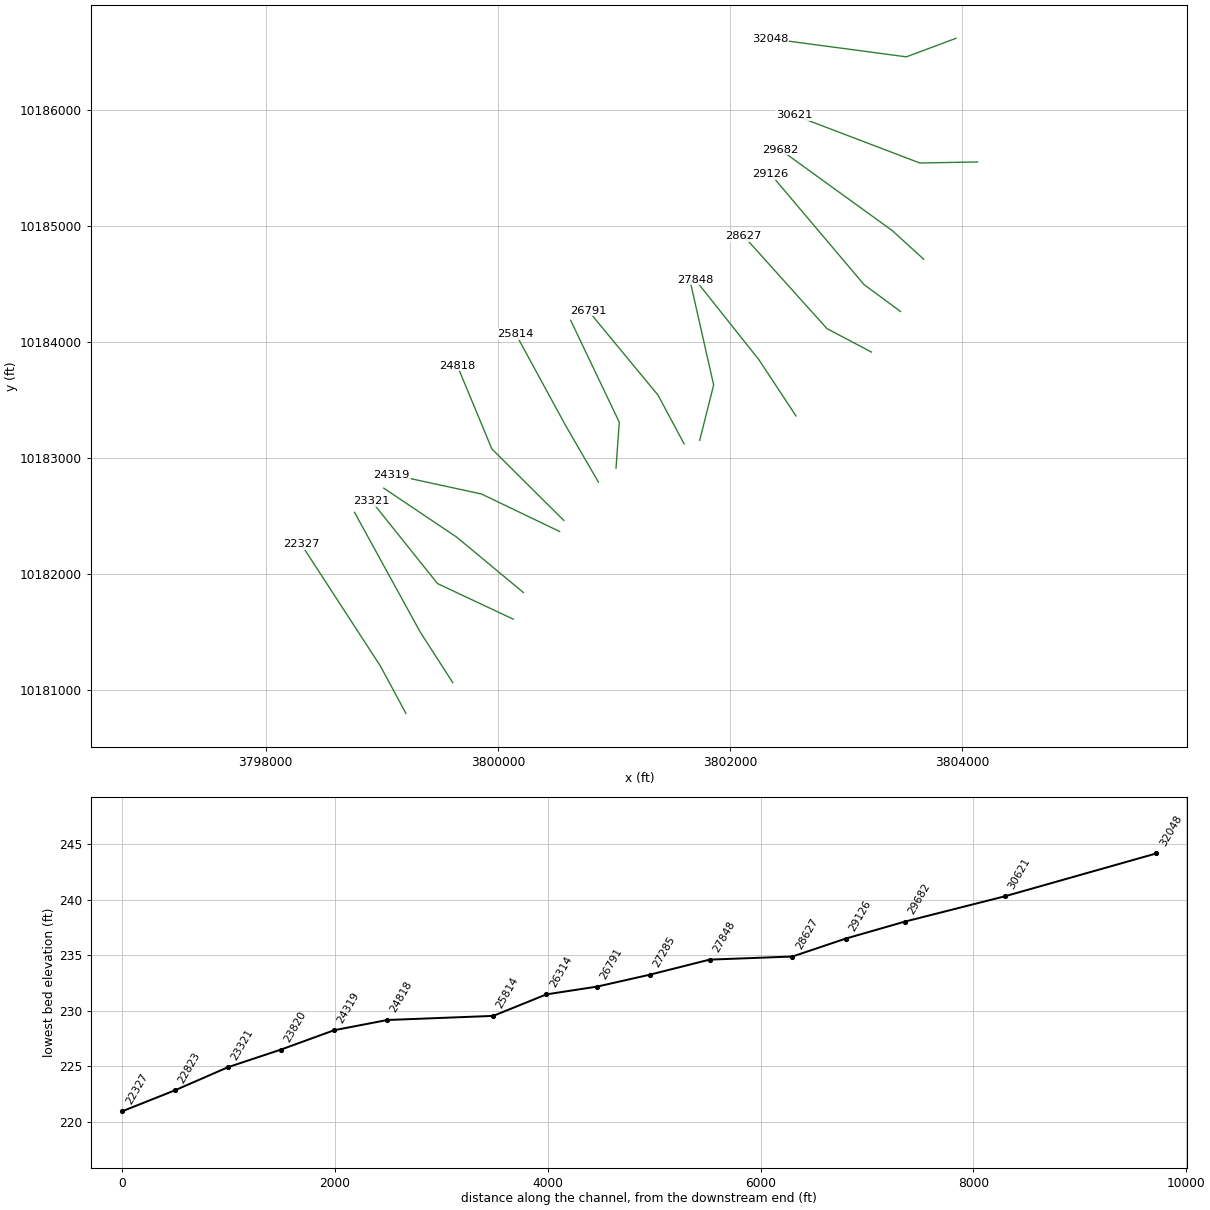
HEC-RAS study GUM BRANCH.prj: GUM BRANCH Base Level Engineering

--- GUM BRANCH.g01 (geometry) --- (continued)

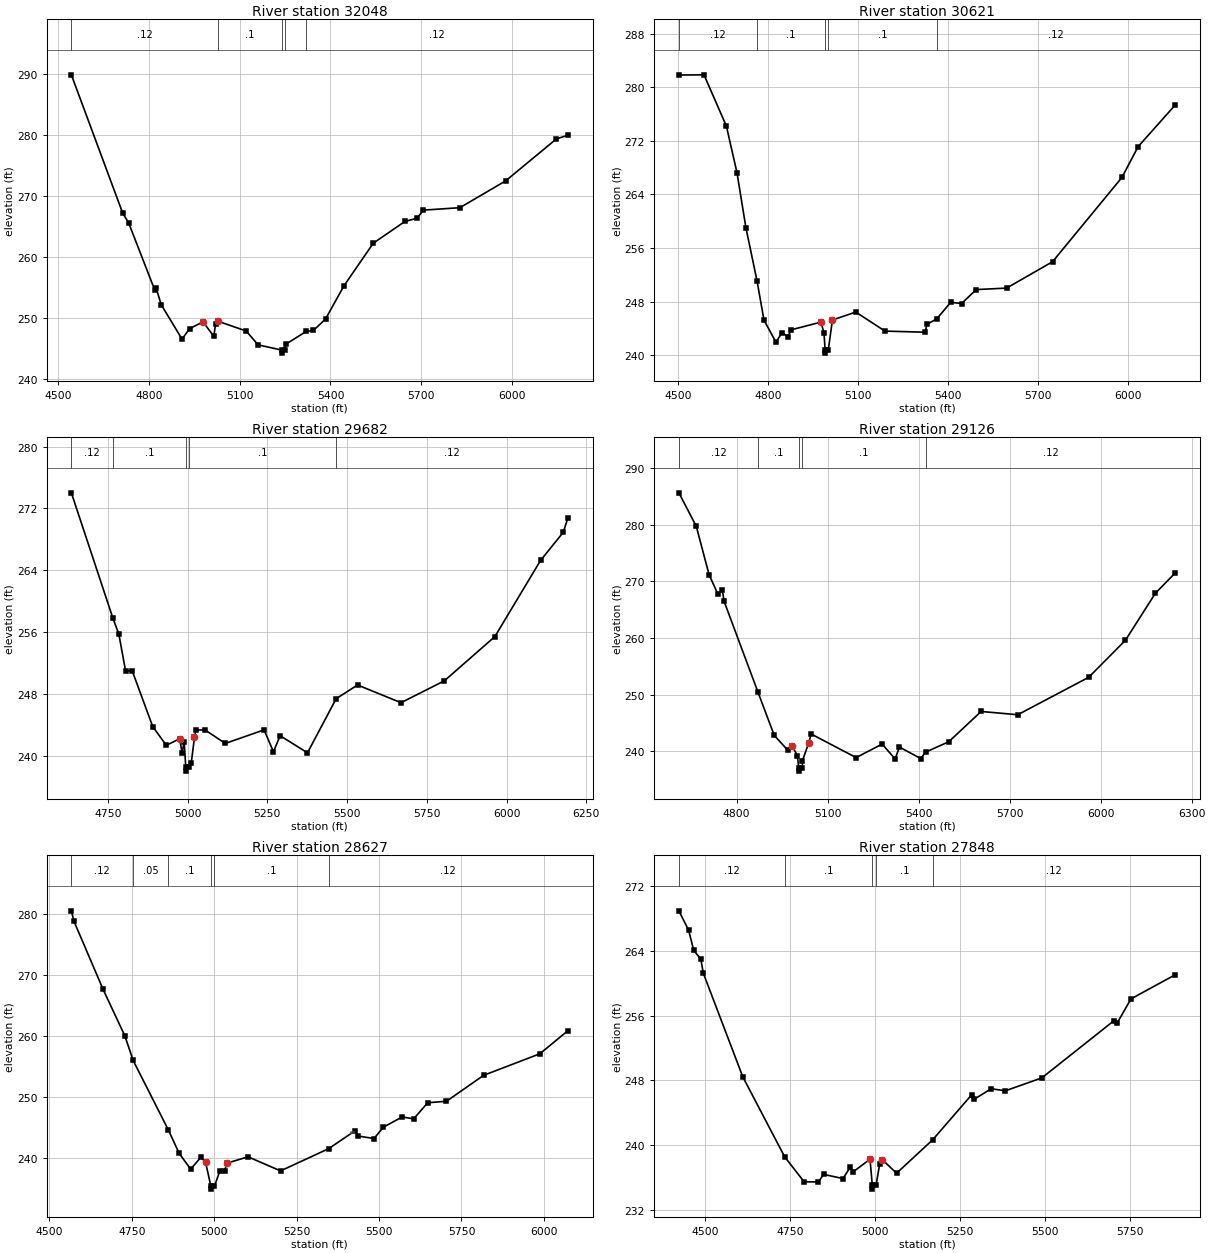
Type RM Length L Ch R = 1 ,32048   ,1427,1427,1427
BEGIN DESCRIPTION:
GUM BRANCH 38.0
END DESCRIPTION:
XS GIS Cut Line= 3
      3803945.83     10186613.83      3803518.21     10186454.33
       3802344.1     10186610.88
#Sta/Elev= 30
  4543.6  289.82  4713.2  267.15  4732.9  265.55  4818.5  254.61  4823.8  254.88
  4840.3  252.15  4909.4  246.47  4934.4   248.2    4979  249.31  5014.3  246.93
  5020.5  249.02  5029.9  249.38  5121.4  247.81  5160.6  245.54  5238.7  244.68
  5239.2  244.18    5249  244.68  5252.6  245.65  5319.6  247.73  5343.4   247.9
  5383.7  249.77  5444.3   255.2  5541.5  262.21    5646  265.77  5686.4  266.31
  5706.6  267.63  5827.6  268.03    5979  272.43  6146.7  279.31  6184.5  279.91
#Mann= 5 ,-1 , 0
  4543.6     .12       0  5029.9      .1       0  5238.7     .07       0
    5249      .1       0  5319.6     .12       0
Bank Sta=4979,5029.9
XS Rating Curve= 0 ,0
Exp/Cntr=0.3,0.1

Type RM Length L Ch R = 1 ,30621   ,939,939,939
BEGIN DESCRIPTION:
GUM BRANCH 37.0
END DESCRIPTION:
XS GIS Cut Line= 3
      3804131.65     10185548.96      3803634.34      10185539.9
      3802551.75     10185952.64
#Sta/Elev= 30
  4502.6  281.84  4586.4  281.87  4661.2  274.19  4696.4  267.25  4726.4  258.98
  4763.5  251.05  4786.4  245.24  4826.5  241.93  4846.5  243.39  4866.5  242.74
  4876.5  243.78  4976.5  244.94  4986.5  243.31  4990.5  240.81    4991  240.31
    5001  240.81  5014.8  245.26  5092.6  246.44    5190   243.6  5324.4  243.43
  5329.7   244.6  5363.4  245.45  5409.3   247.9  5445.7  247.72  5494.2   249.8
  5595.6  250.02    5749  253.96  5980.8  266.57  6034.3  271.14  6158.6  277.39
#Mann= 5 ,-1 , 0
  4502.6     .12       0  4763.5      .1       0  4990.5     .07       0
    5001      .1       0  5363.4     .12       0
#XS Ineff= 2 , 0
       0                  5409.3       0   247.9
Permanent Ineff=
       F       F
Bank Sta=4976.5,5014.8
XS Rating Curve= 0 ,0
Exp/Cntr=0.3,0.1

Type RM Length L Ch R = 1 ,29682   ,556,556,556
BEGIN DESCRIPTION:
GUM BRANCH 35.0
END DESCRIPTION:
XS GIS Cut Line= 3
      3803667.86     10184711.06      3803398.47      10184956.6
      3802432.57     10185655.27
#Sta/Elev= 30
  4635.5  274.02    4766  257.77  4784.3  255.77  4805.4     251  4826.4  250.99
  4890.6  243.79  4933.1  241.37    4975  242.21  4982.5   240.4  4989.2  241.84
  4994.2  238.53  4994.7  238.03  5005.1  238.53  5011.5  239.12 5021.51  242.39
  5025.4  243.31  5053.3  243.39  5118.3  241.61  5239.7  243.37  5269.1  240.53
    5290  242.61  5375.8   240.4  5465.8   247.4  5532.8  249.17    5669  246.88
  5805.1  249.71  5963.4  255.43  6106.8  265.29  6177.9  268.92  6192.1  270.76
#Mann= 5 ,-1 , 0
  4635.5     .12       0    4766      .1       0  4994.2     .07       0
  5005.1      .1       0  5465.8     .12       0
Bank Sta=4975,5021.51
XS Rating Curve= 0 ,0
Exp/Cntr=0.3,0.1

Type RM Length L Ch R = 1 ,29126   ,499,499,499
BEGIN DESCRIPTION:
GUM BRANCH 34.0
END DESCRIPTION:
XS GIS Cut Line= 3
      3803467.85     10184261.08      3803153.62     10184492.91
       3802348.9     10185444.59
#Sta/Elev= 30
  4609.5  285.66  4666.9  279.74  4708.9  271.22  4737.9  267.78  4752.5  268.52
  4758.7  266.47  4870.2  250.46  4923.7  242.83  4967.6  240.25  4982.3  241.02
    5000  239.26    5005     237  5005.5   236.5  5015.9     237    5017  238.37
  5037.8  241.51  5045.5  243.06    5194  238.89  5279.6  241.28  5322.4  238.65
  5336.7  240.75    5407  238.72  5422.7  239.85  5499.3  241.69  5605.9  247.04
  5726.7  246.46  5960.8  253.08  6081.6  259.61  6180.5  267.92  6246.3  271.54
#Mann= 5 ,-1 , 0
  4609.5     .12       0  4870.2      .1       0    5005     .07       0
  5015.9      .1       0  5422.7     .12       0
Bank Sta=4982.3,5037.8
XS Rating Curve= 0 ,0
Exp/Cntr=0.3,0.1

Type RM Length L Ch R = 1 ,28627   ,779,779,779
BEGIN DESCRIPTION:
GUM BRANCH 33.0
END DESCRIPTION:
XS GIS Cut Line= 3
      3803217.82     10183911.09      3802834.76     10184113.39
      3802117.85     10184911.07
#Sta/Elev= 30
  4566.8  280.54  4574.9   278.8    4663  267.66  4729.1  260.02  4754.2     256
  4861.2  244.57  4893.9  240.74  4928.7  238.17  4959.9  240.13  4973.9  239.27
  4989.9  235.39  4990.4  234.89  5000.9  235.39  5017.4  237.91  5031.6  237.89
  5038.4  239.15  5102.7  240.19  5201.3  237.88  5346.9  241.52  5427.8  244.48
  5435.3  243.61  5484.6  243.19    5513  245.04  5569.8  246.73    5605  246.42
  5647.6  249.06  5704.4   249.3  5817.2  253.56  5987.7  257.09  6072.5  260.87
#Mann= 6 ,-1 , 0
  4566.8     .12       0  4754.2     .05       0  4861.2      .1       0
  4989.9     .07       0  5000.9      .1       0  5346.9     .12       0
#XS Ineff= 2 ,-1
  5413.7  5427.8   244.2  5427.8    5513  244.48
Permanent Ineff=
       F       F
Bank Sta=4973.9,5038.4
XS Rating Curve= 0 ,0
Exp/Cntr=0.3,0.1

Type RM Length L Ch R = 1 ,27848   ,563,563,563
BEGIN DESCRIPTION:
GUM BRANCH 31.0
END DESCRIPTION:
XS GIS Cut Line= 3
      3802567.84     10183361.09      3802249.86     10183843.52
      3801699.65     10184535.67
#Sta/Elev= 30
  4422.2  268.91  4450.8  266.53  4465.9  264.04  4486.9  262.95    4494  261.24
  4610.4  248.45  4733.6   238.6  4791.1  235.51  4833.2   235.5  4848.3  236.43
  4905.5  235.91  4926.5   237.3  4935.6  236.75  4985.1  238.29  4991.7  235.11
  4992.2  234.61  5002.9  235.11  5013.6  237.72  5021.7  238.22  5063.3  236.57
  5169.6  240.69  5284.4  246.24  5290.8  245.66  5341.8  246.98  5383.7  246.73
    5491  248.32  5704.1  255.39  5712.1  255.03  5753.7  258.06  5884.2  261.04
#Mann= 5 ,-1 , 0
  4422.2     .12       0  4733.6      .1       0  4991.7     .07       0
  5002.9      .1       0  5169.6     .12       0
#XS Ineff= 2 , 0
       0                  5191.5       0  241.67
Permanent Ineff=
       F       F
Bank Sta=4985.1,5021.7
XS Rating Curve= 0 ,0
Exp/Cntr=0.3,0.1

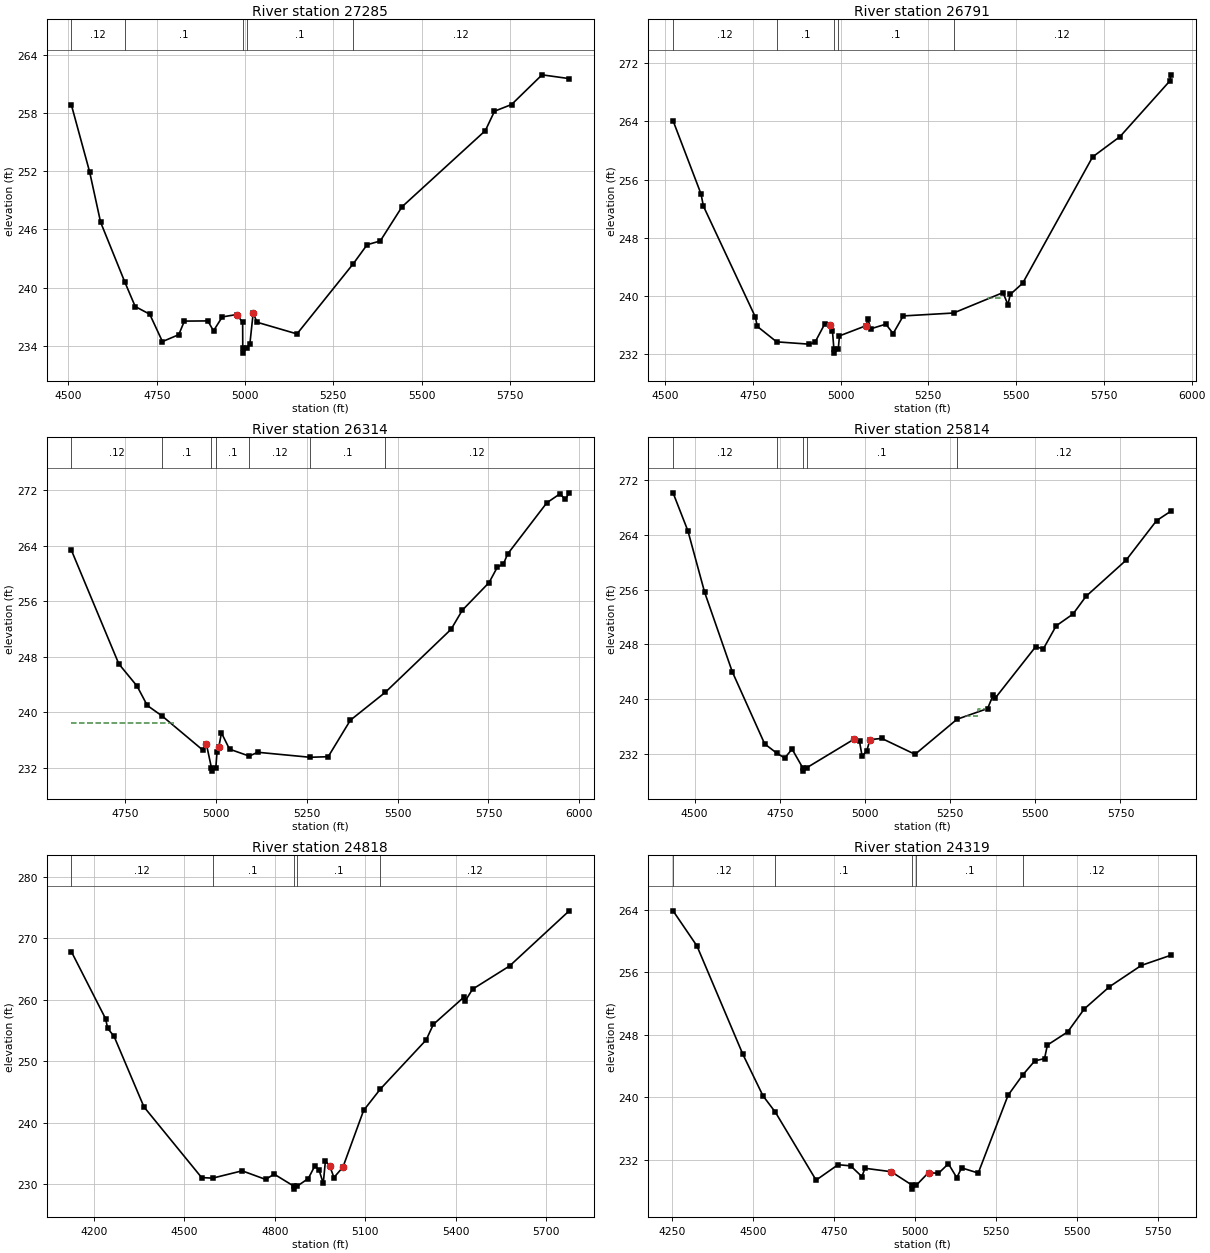
Type RM Length L Ch R = 1 ,27285   ,494,494,494
BEGIN DESCRIPTION:
GUM BRANCH 30.0
END DESCRIPTION:
XS GIS Cut Line= 3
      3801738.67     10183151.12      3801858.81      10183627.6
      3801656.22     10184522.66
#Sta/Elev= 30
  4508.6  258.81  4560.1  251.93  4591.1  246.75  4659.9  240.56  4689.2  238.05
  4730.3  237.26  4766.2  234.44  4812.4  235.15  4828.3  236.55  4894.6  236.57
  4910.8  235.55  4935.6  236.98  4976.7  237.23  4993.3  236.42  4993.6  233.75
  4994.1  233.25  5004.9  233.75  5013.8  234.23    5023  237.35  5034.3  236.43
  5147.1  235.23  5306.6  242.47  5345.6  244.42  5382.9  244.81  5444.4  248.33
  5680.3  256.18  5706.2  258.18  5754.5  258.87  5840.8  261.93  5917.7  261.54
#Mann= 5 ,-1 , 0
  4508.6     .12       0  4659.9      .1       0  4993.6     .07       0
  5004.9      .1       0  5306.6     .12       0
Bank Sta=4976.7,5023
XS Rating Curve= 0 ,0
Exp/Cntr=0.3,0.1

Type RM Length L Ch R = 1 ,26791   ,477,477,477
BEGIN DESCRIPTION:
GUM BRANCH 29.0
END DESCRIPTION:
XS GIS Cut Line= 3
      3801604.11     10183120.81      3801378.99     10183541.23
       3800779.7     10184266.34
#Sta/Elev= 30
  4523.1  264.11  4602.8  254.04  4609.5  252.38  4757.4  237.15    4763  235.85
  4818.1  233.73  4910.9  233.41  4927.2  233.66  4954.8  236.16    4971     236
  4977.1   235.2  4981.3  232.68  4981.8  232.18  4993.4  232.68  4997.1  234.55
  5071.8  235.93  5078.3  236.83  5086.1  235.52  5129.1  236.16  5149.9  234.87
  5178.6  237.29  5321.9  237.69  5462.6  240.49  5476.9  238.84  5483.4  240.24
  5518.7  241.78  5717.9  259.13  5796.1  261.93  5938.1  269.58  5940.7  270.41
#Mann= 5 ,-1 , 0
  4523.1     .12       0  4818.1      .1       0  4981.3     .07       0
  4993.4      .1       0  5321.9     .12       0
#XS Ineff= 2 ,-1
  5419.6  5462.6  239.76  5462.6  5497.8  240.49
Permanent Ineff=
       F       F
Bank Sta=4971,5071.8
XS Rating Curve= 0 ,0
Exp/Cntr=0.3,0.1

Type RM Length L Ch R = 1 ,26314   ,500,500,500
BEGIN DESCRIPTION:
GUM BRANCH 28.0
END DESCRIPTION:
XS GIS Cut Line= 3
      3801017.85      10182911.1      3801045.96      10183306.7
      3800627.56     10184184.16
#Sta/Elev= 30
  4603.4  263.34  4733.7  246.95  4783.8  243.75    4812  240.95  4853.6   239.4
  4964.3  234.53  4974.3  235.43  4988.3  231.98  4988.8  231.48  5000.5  231.98
  5003.6  234.21  5008.8  235.01  5015.9  236.99  5038.1  234.65  5092.3  233.65
  5115.6   234.2  5259.2  233.48  5309.4  233.56  5370.4  238.83  5466.4  242.85
  5647.4  251.95  5678.1  254.69  5751.7  258.68  5774.4   260.9  5791.4  261.38
  5802.6  262.79  5910.5  270.19  5946.5  271.48  5961.5  270.69  5972.1  271.63
#Mann= 7 ,-1 , 0
  4603.4     .12       0  4853.6      .1       0  4988.3     .07       0
  5000.5      .1       0  5092.3     .12       0  5259.2      .1       0
  5466.4     .12       0
#XS Ineff= 2 , 0
       0  4884.1  238.38  5377.5       0   239.1
Permanent Ineff=
       F       F
Bank Sta=4974.3,5008.8
XS Rating Curve= 0 ,0
Exp/Cntr=0.3,0.1

Type RM Length L Ch R = 1 ,25814   ,996,996,996
BEGIN DESCRIPTION:
GUM BRANCH 27.0
END DESCRIPTION:
XS GIS Cut Line= 3
      3800866.29     10182790.91      3800583.88     10183277.96
      3800154.71     10184066.54
#Sta/Elev= 30
    4437  270.11  4480.7  264.55  4529.7  255.61  4610.6  244.05  4705.9  233.51
  4740.6  232.19  4764.7  231.45  4786.3  232.75  4817.4  230.04  4817.9  229.54
  4829.6  230.04  4968.9  234.22  4984.2  233.86    4992  231.68  5005.7  232.53
  5014.9  234.13  5049.4  234.31  5147.2  231.99  5270.3   237.1    5360  238.66
  5376.1  240.57  5381.8  240.14  5501.5   247.7  5523.3  247.33  5561.3  250.72
  5610.7  252.44  5648.7  255.01  5766.3  260.28  5855.8  266.05  5897.8  267.43
#Mann= 5 ,-1 , 0
    4437     .12       0  4740.6      .1       0  4817.4     .07       0
  4829.6      .1       0  5270.3     .12       0
#XS Ineff= 2 ,-1
  5294.4  5332.4  237.52  5332.4  5354.3  238.65
Permanent Ineff=
       F       F
Bank Sta=4968.9,5014.9
XS Rating Curve= 0 ,0
Exp/Cntr=0.3,0.1

Type RM Length L Ch R = 1 ,24818   ,499,499,499
BEGIN DESCRIPTION:
GUM BRANCH 26.0
END DESCRIPTION:
XS GIS Cut Line= 3
      3800567.87     10182461.06       3799948.4     10183077.04
      3799650.99     10183793.57
#Sta/Elev= 30
  4126.4  267.82  4239.5  256.92  4246.6  255.34  4267.8  254.03  4366.8  242.55
  4557.8  231.05  4594.2  230.96  4692.1  232.15  4769.9  230.75  4798.2  231.61
  4862.7  229.67  4863.2  229.17    4875  229.67  4911.3   230.9  4932.5  232.91
  4946.7  232.33  4960.8  230.09  4967.9  233.72    4982  232.99  4996.2  231.06
    5026  232.75  5094.6  241.99  5150.3  245.48  5301.8  253.46  5325.6  255.99
  5426.5  260.41  5431.9  259.87  5455.8  261.73  5578.2   265.5  5775.8  274.48
#Mann= 5 ,-1 , 0
  4126.4     .12       0  4594.2      .1       0  4862.7     .07       0
    4875      .1       0  5150.3     .12       0
Bank Sta=4982,5026
XS Rating Curve= 0 ,0
Exp/Cntr=0.3,0.1

Type RM Length L Ch R = 1 ,24319   ,499,499,499
BEGIN DESCRIPTION:
GUM BRANCH 25.0
END DESCRIPTION:
XS GIS Cut Line= 3
      3800532.12     10182365.55      3799858.75     10182688.72
      3799086.77     10182856.02
#Sta/Elev= 30
  4253.1  263.89  4326.8   259.4  4468.6  245.52  4530.6  240.21  4569.2  238.09
  4694.7   229.4  4762.6  231.38  4801.3  231.23  4836.1  229.86  4845.7  230.92
  4926.7  230.48  4991.3  228.75  4991.8  228.25  5004.2  228.75  5041.8  230.37
  5072.5  230.27  5103.2   231.5    5129  229.72  5144.2  230.97  5195.3  230.31
  5287.4  240.27  5332.6  242.87  5369.8  244.67    5400  244.97  5408.8   246.7
  5471.6  248.39  5522.8  251.33  5600.4  254.17  5698.8   256.9  5789.9   258.2
#Mann= 5 ,-1 , 0
  4253.1     .12       0  4569.2      .1       0  4991.3     .07       0
  5004.2      .1       0  5332.6     .12       0
Bank Sta=4926.7,5041.8
XS Rating Curve= 0 ,0
Exp/Cntr=0.3,0.1

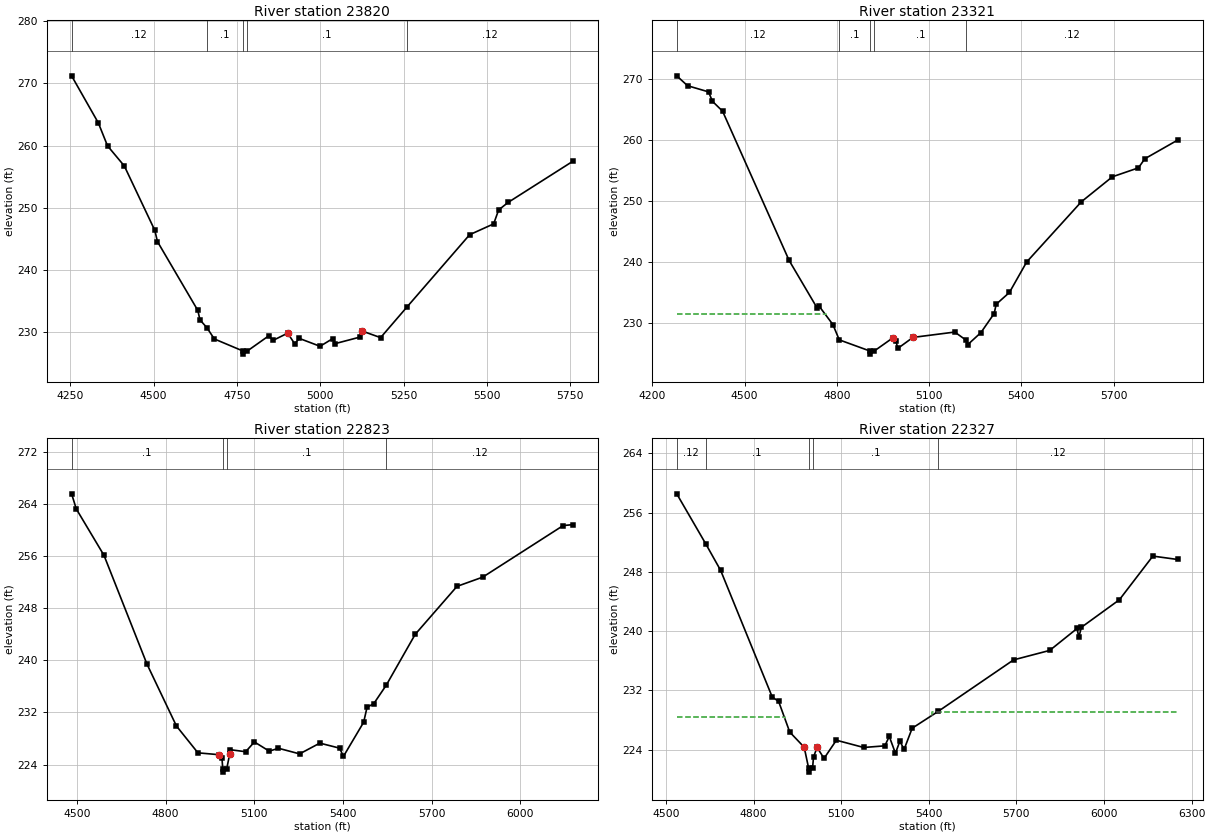
Type RM Length L Ch R = 1 ,23820   ,499,499,499
BEGIN DESCRIPTION:
GUM BRANCH 24.0
END DESCRIPTION:
XS GIS Cut Line= 3
      3800219.58      10181840.4      3799645.66     10182316.98
      3799017.34     10182738.83
#Sta/Elev= 30
    4254  271.21  4334.2  263.65  4361.8  259.96  4412.2  256.73  4503.7  246.38
  4511.5  244.59  4632.6  233.53  4639.1  232.01  4659.8  230.76  4682.1  228.95
  4768.1  227.01  4768.6  226.51    4781  227.01  4844.9  229.43  4859.2  228.74
  4902.2  229.88    4923  228.18  4937.3  229.03  4999.3  227.77  5036.9  228.99
  5045.5  228.21  5117.8  229.23  5123.9  230.25  5180.9  229.16  5260.5  234.11
    5448  245.69    5520  247.43    5535  249.67  5563.5  250.88  5756.8  257.46
#Mann= 5 ,-1 , 0
    4254     .12       0  4659.8      .1       0  4768.1     .07       0
    4781      .1       0  5260.5     .12       0
Bank Sta=4902.2,5123.9
XS Rating Curve= 0 ,0
Exp/Cntr=0.3,0.1

Type RM Length L Ch R = 1 ,23321   ,498,498,498
BEGIN DESCRIPTION:
GUM BRANCH 23.0
END DESCRIPTION:
XS GIS Cut Line= 3
      3800132.78     10181610.36      3799480.59     10181916.79
      3798913.13     10182626.02
#Sta/Elev= 30
  4279.4  270.56  4314.4  268.94  4382.8  267.93  4395.3  266.39  4428.4  264.76
  4644.8  240.28    4736  232.47  4741.5  232.84  4787.1  229.77  4807.8  227.26
  4908.1  225.42  4908.6  224.92  4921.2  225.42  4980.9  227.55    4992  227.11
  4997.9  225.85  5047.3  227.66  5183.4  228.54  5221.1  227.17    5225  226.45
  5268.3  228.45  5311.5  231.58  5317.9  233.09  5361.1  235.04  5417.1  240.03
  5594.8   249.9  5695.7     254  5780.5  255.47  5801.3  256.96  5908.3  260.03
#Mann= 5 ,-1 , 0
  4279.4     .12       0  4807.8      .1       0  4908.1     .07       0
  4921.2      .1       0  5221.1     .12       0
#XS Ineff= 2 , 0
       0  4764.3  231.48               0
Permanent Ineff=
       F       F
Bank Sta=4980.9,5047.3
XS Rating Curve= 0 ,0
Exp/Cntr=0.3,0.1

Type RM Length L Ch R = 1 ,22823   ,496,496,496
BEGIN DESCRIPTION:
GUM BRANCH 22.0
END DESCRIPTION:
XS GIS Cut Line= 3
      3799611.93      10181063.5      3799331.65     10181499.12
      3798765.59     10182530.49
#Sta/Elev= 30
    4482  265.54  4497.9  263.22  4591.6   256.1  4736.9  239.42  4836.6  229.92
  4909.3   225.8  4981.9  225.51  4990.4  225.07  4993.4  223.34  4993.9  222.84
  5006.6  223.34 5016.64  225.58  5018.8  226.28  5070.7  225.97  5100.3  227.47
  5150.5  226.06  5181.8   226.5  5253.2  225.64  5321.6  227.29  5388.4  226.52
  5401.5  225.26  5469.9   230.5  5481.3  232.79  5504.1  233.35  5546.3  236.18
  5644.3  243.99  5785.5  251.34  5872.7  252.76  6144.6  260.67  6176.5  260.81
#Mann= 4 ,-1 , 0
    4482      .1       0  4993.4     .07       0  5006.6      .1       0
  5546.3     .12       0
Bank Sta=4981.9,5016.64
XS Rating Curve= 0 ,0
Exp/Cntr=0.3,0.1

Type RM Length L Ch R = 1 ,22327   ,498,498,498
BEGIN DESCRIPTION:
GUM BRANCH 21.0
END DESCRIPTION:
XS GIS Cut Line= 3
      3799208.29     10180798.74      3798988.44     10181206.55
      3798305.83     10182256.58
#Sta/Elev= 30
  4536.7  258.54  4635.5  251.82    4687   248.2  4863.7   231.1  4885.6   230.5
  4923.7  226.36  4973.2  224.31  4988.5  221.45    4989  220.95  5001.7  221.45
  5005.1  222.99  5017.3  224.29  5041.1   222.8  5083.3  225.26  5176.9  224.28
  5249.3   224.5  5264.5  225.77  5285.6   223.5  5300.7  225.11  5315.5  224.04
  5342.9  226.88  5432.2  229.16  5690.2  236.11    5814  237.39  5907.6  240.35
  5913.6  239.19  5922.7  240.52  6052.5  244.23  6167.2  250.13  6252.4  249.67
#Mann= 5 ,-1 , 0
  4536.7     .12       0  4635.5      .1       0  4988.5     .07       0
  5001.7      .1       0  5432.2     .12       0
#XS Ineff= 2 , 0
       0  4907.5  228.46  5409.4       0  229.12
Permanent Ineff=
       F       F
Bank Sta=4973.2,5017.3
XS Rating Curve= 0 ,0
Exp/Cntr=0.3,0.1