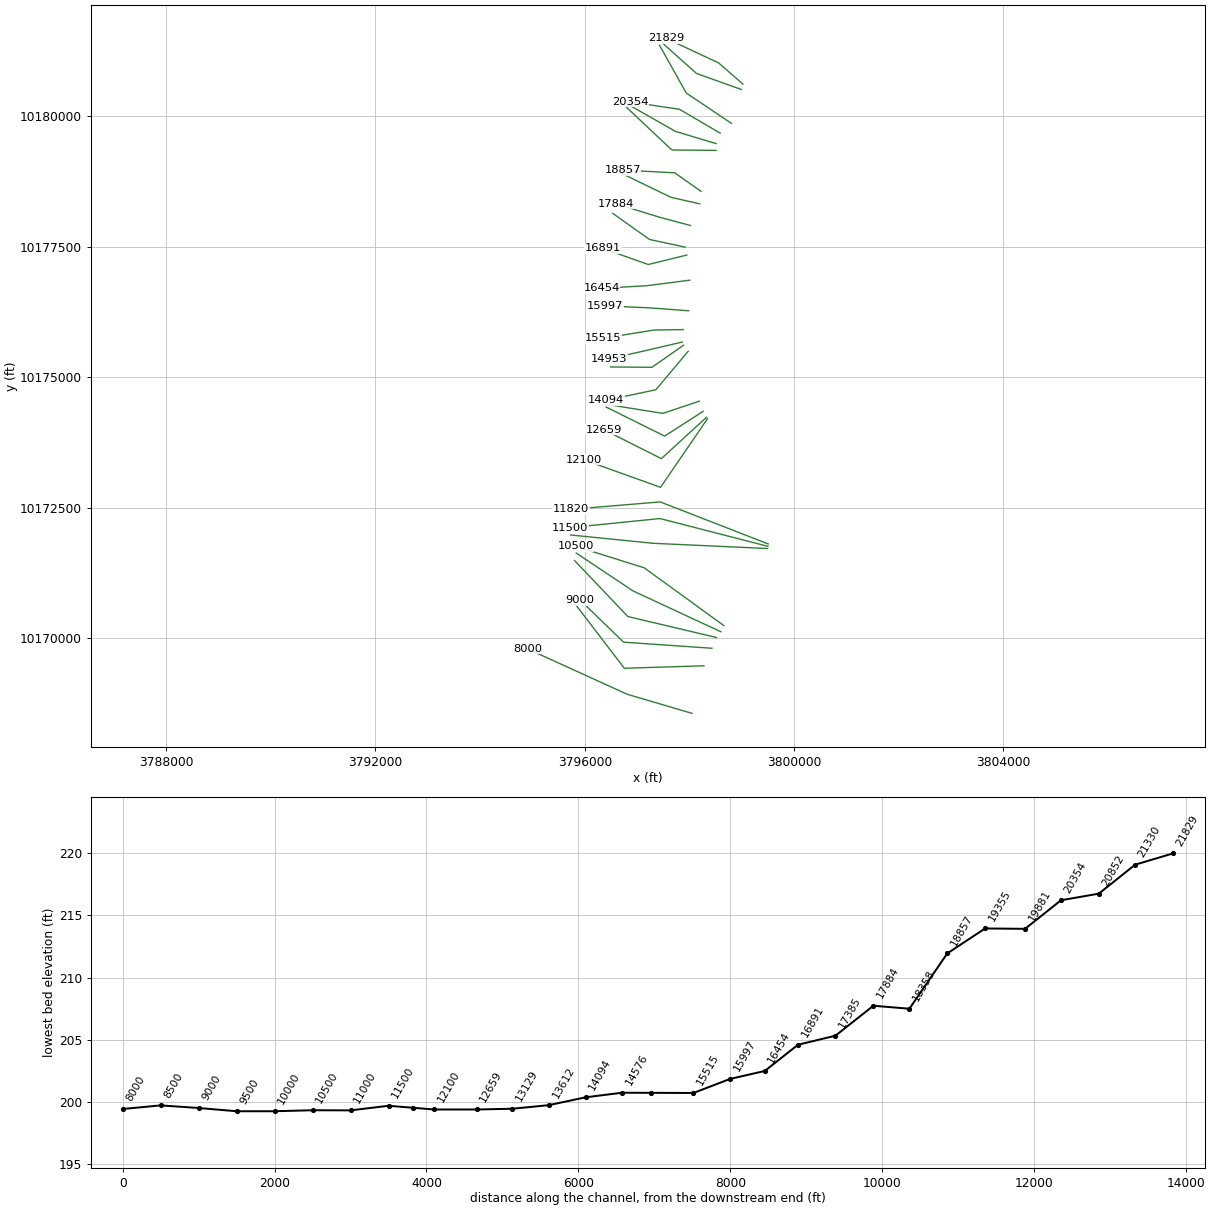
HEC-RAS study GUM BRANCH.prj: GUM BRANCH Base Level Engineering

--- GUM BRANCH.g01 (geometry) --- (continued)

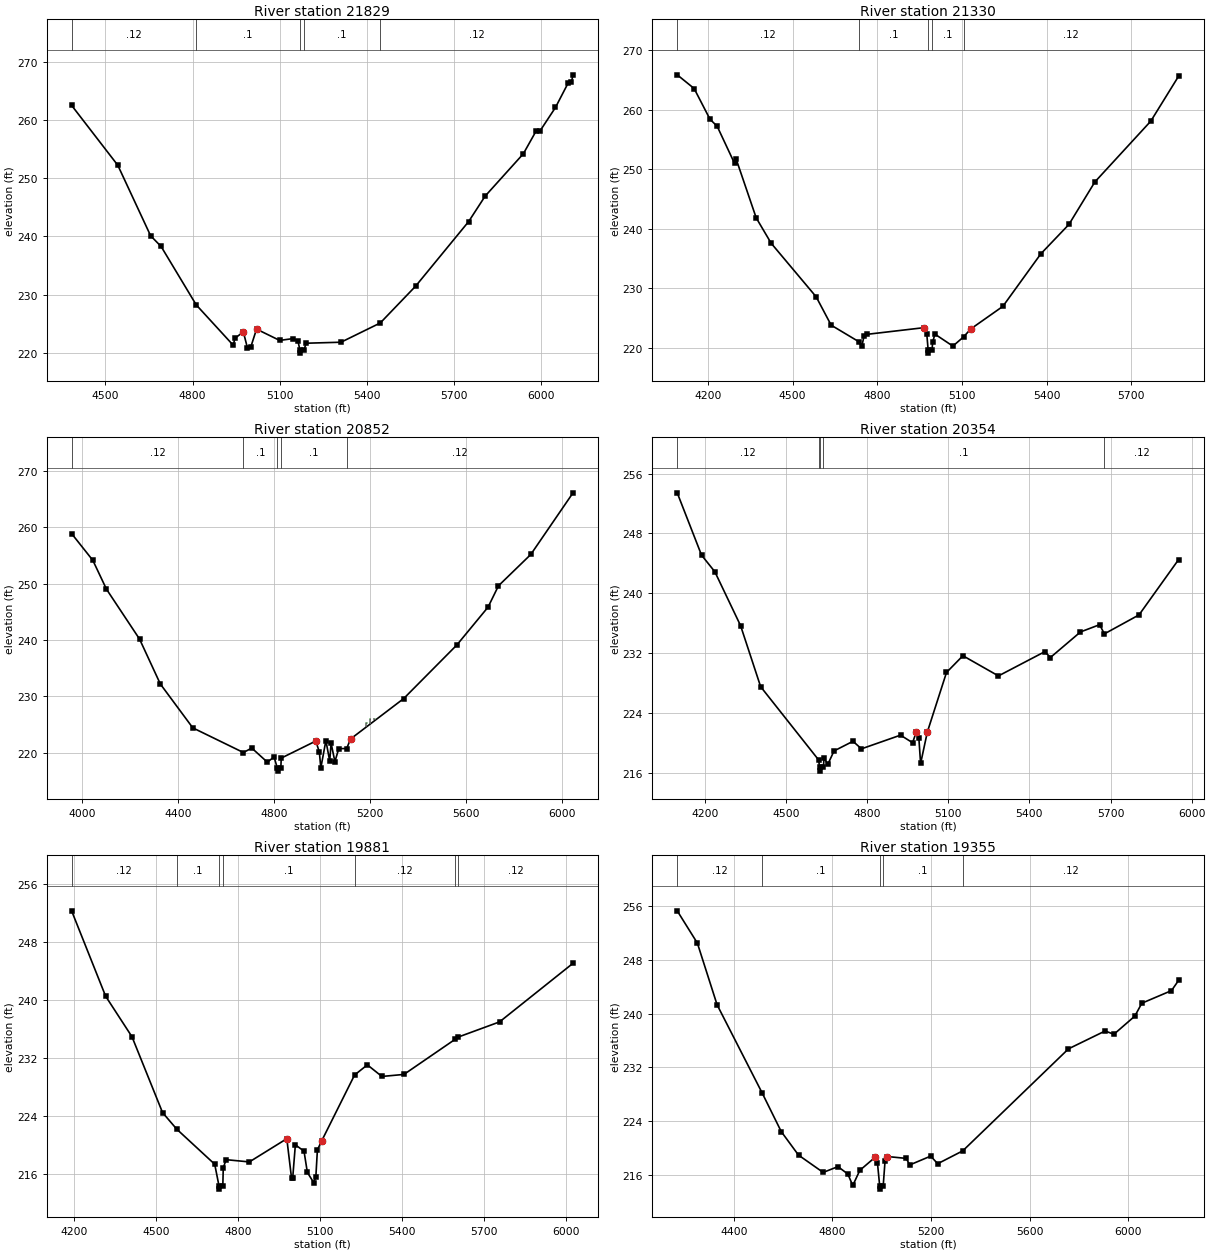
Type RM Length L Ch R = 1 ,21829   ,499,499,499
BEGIN DESCRIPTION:
GUM BRANCH 20.0
END DESCRIPTION:
XS GIS Cut Line= 3
      3799021.64     10180620.81      3798557.23     10181025.81
      3797553.15     10181496.19
#Sta/Elev= 30
  4383.8  262.48  4542.7  252.21  4655.6  240.12  4691.7  238.28  4812.6  228.26
  4939.5  221.36  4946.1  222.55  4974.6  223.64  4988.9  220.84    5000     221
    5020  224.11  5099.6  222.17  5145.2  222.48  5162.5  222.06  5169.4  220.49
  5169.9  219.99  5182.7  220.49  5190.9  221.69  5310.5  221.86  5445.6  225.16
  5567.2  231.47  5749.8  242.56  5806.5  246.92    5938  254.19  5982.1  258.11
  5994.7  258.05  6048.4  262.12  6092.6  266.37  6103.3  266.47  6108.8  267.72
#Mann= 5 ,-1 , 0
  4383.8     .12       0  4812.6      .1       0  5169.4     .07       0
  5182.7      .1       0  5445.6     .12       0
Bank Sta=4974.6,5020
XS Rating Curve= 0 ,0
Exp/Cntr=0.3,0.1

Type RM Length L Ch R = 1 ,21330   ,478,478,478
BEGIN DESCRIPTION:
GUM BRANCH 19.0
END DESCRIPTION:
XS GIS Cut Line= 3
       3798991.3     10180516.61      3798135.41     10180823.06
      3797489.53     10181402.04
#Sta/Elev= 30
  4090.9  265.84  4150.8  263.54    4207  258.38  4232.5  257.19    4294  250.96
  4299.3  251.74  4370.7  241.81  4423.8  237.54  4583.2  228.54  4636.3  223.78
  4735.4  220.97  4744.9  220.25  4753.1     222  4763.7  222.24  4965.5  223.36
  4975.1  222.31    4980  219.58  4980.5  219.08  4993.6  219.58    4996  220.95
    5004  222.27  5067.5  220.26  5105.3   221.8  5131.1  223.15  5244.7  226.94
  5379.3  235.77  5478.7   240.7  5570.6  247.84  5768.8  258.06  5867.4  265.62
#Mann= 5 ,-1 , 0
  4090.9     .12       0  4735.4      .1       0    4980     .07       0
  4993.6      .1       0  5105.3     .12       0
Bank Sta=4965.5,5131.1
XS Rating Curve= 0 ,0
Exp/Cntr=0.3,0.1

Type RM Length L Ch R = 1 ,20852   ,498,498,498
BEGIN DESCRIPTION:
GUM BRANCH 18.0
END DESCRIPTION:
XS GIS Cut Line= 3
      3798804.63     10179865.58      3797939.93     10180448.08
      3797428.78     10181362.97
#Sta/Elev= 30
  3957.4  258.86  4045.9  254.12  4102.8     249  4240.8  240.15  4327.3   232.2
  4462.7  224.42  4673.6  220.05  4708.6  220.84  4773.4  218.34  4801.5  219.26
  4815.5  217.25    4816  216.75  4829.6  217.25  4831.5  219.06  4975.4  222.08
  4990.4  220.13  4996.4   217.3  5017.6  222.17  5033.5  218.55  5039.3  221.69
  5055.2  218.43  5071.2  220.73  5104.3  220.76  5120.4  222.45  5341.9  229.61
  5563.5  239.11  5693.8  245.83  5737.2  249.61  5871.9  255.16    6048  266.09
#Mann= 5 ,-1 , 0
  3957.4     .12       0  4673.6      .1       0  4815.5     .07       0
  4829.6      .1       0  5104.3     .12       0
#XS Ineff= 2 ,-1
  5186.7  5201.5  225.34  5201.5  5223.2  225.92
Permanent Ineff=
       F       F
Bank Sta=4975.4,5120.4
XS Rating Curve= 0 ,0
Exp/Cntr=0.3,0.1

Type RM Length L Ch R = 1 ,20354   ,473,473,473
BEGIN DESCRIPTION:
GUM BRANCH 17.0
END DESCRIPTION:
XS GIS Cut Line= 3
      3798587.67     10179678.92      3797810.33     10180136.85
      3796868.93     10180277.89
#Sta/Elev= 30
  4097.8  253.43  4187.7   245.1  4236.9  242.88  4332.1  235.67  4406.3  227.51
  4620.6  217.72  4624.4  216.72  4624.9  216.22  4638.5  216.72  4640.6  217.98
  4654.7  217.13  4677.7  218.92  4747.8  220.21  4779.1   219.2  4923.5  221.03
  4968.1  220.02  4982.1  221.48  4991.3  220.65  4997.8  217.24  5022.7  221.45
  5093.5  229.41  5154.2  231.65  5285.6  228.95  5457.5   232.2  5477.7  231.41
    5589  234.83  5659.8   235.8  5677.3  234.57  5805.5  237.11  5951.9  244.51
#Mann= 5 ,-1 , 0
  4097.8     .12       0  4620.6      .1       0  4624.4     .07       0
  4638.5      .1       0  5677.3     .12       0
#XS Ineff= 2 , 0
       0  4470.7  224.14               0
Permanent Ineff=
       F       F
Bank Sta=4982.1,5022.7
XS Rating Curve= 0 ,0
Exp/Cntr=0.3,0.1

Type RM Length L Ch R = 1 ,19881   ,526,526,526
BEGIN DESCRIPTION:
GUM BRANCH 16.0
END DESCRIPTION:
XS GIS Cut Line= 3
      3798509.52     10179479.28      3797734.39     10179713.01
       3796842.8      10180221.5
#Sta/Elev= 30
  4190.4  252.28    4315  240.51  4411.5  234.92  4523.4  224.47  4575.5  222.18
  4714.4  217.35  4729.8  214.42  4730.3  213.92  4744.1  214.42  4745.7  216.86
  4756.2  217.98  4841.2  217.67  4978.4  220.87  4995.6  215.47    5000  215.47
  5009.7  220.03  5041.4  219.15  5053.6  216.23  5076.6  214.83  5084.6  215.55
  5090.4  219.33  5106.2  220.58  5226.5  229.65  5273.3  231.05  5326.6  229.45
  5407.3  229.73  5595.5  234.59  5606.7  234.89  5757.3  236.97  6026.4  245.05
#Mann= 7 ,-1 , 0
  4190.4     .12       0  4575.5      .1       0  4729.8     .07       0
  4744.1      .1       0  5226.5     .12       0  5595.5      .1       0
  5606.7     .12       0
Bank Sta=4978.4,5106.2
XS Rating Curve= 0 ,0
Exp/Cntr=0.3,0.1

Type RM Length L Ch R = 1 ,19355   ,498,498,498
BEGIN DESCRIPTION:
GUM BRANCH 15.0
END DESCRIPTION:
XS GIS Cut Line= 4
      3798509.54     10179349.08      3797680.48     10179356.87
      3797652.31     10179367.67      3796799.43     10180173.75
#Sta/Elev= 30
  4170.9  255.25  4252.6  250.46  4332.6   241.3  4516.2  228.15  4592.6  222.49
  4662.6     219  4762.6  216.43  4822.6  217.29  4862.6  216.19  4882.6  214.49
  4911.3  216.74  4972.6  218.66  4982.6  217.87  4991.7  214.45  4992.2  213.95
    5006  214.45  5013.5  218.15  5022.3  218.79  5099.4  218.51  5113.6  217.54
  5198.5  218.85  5226.9  217.72  5328.5  219.63  5757.2  234.77  5905.7  237.42
  5941.3  236.93  6026.2  239.63  6054.5  241.54  6174.7  243.41  6203.7  244.93
#Mann= 5 ,-1 , 0
  4170.9     .12       0  4516.2      .1       0  4991.7     .07       0
    5006      .1       0  5328.5     .12       0
Bank Sta=4972.6,5022.3
XS Rating Curve= 0 ,0
Exp/Cntr=0.3,0.1

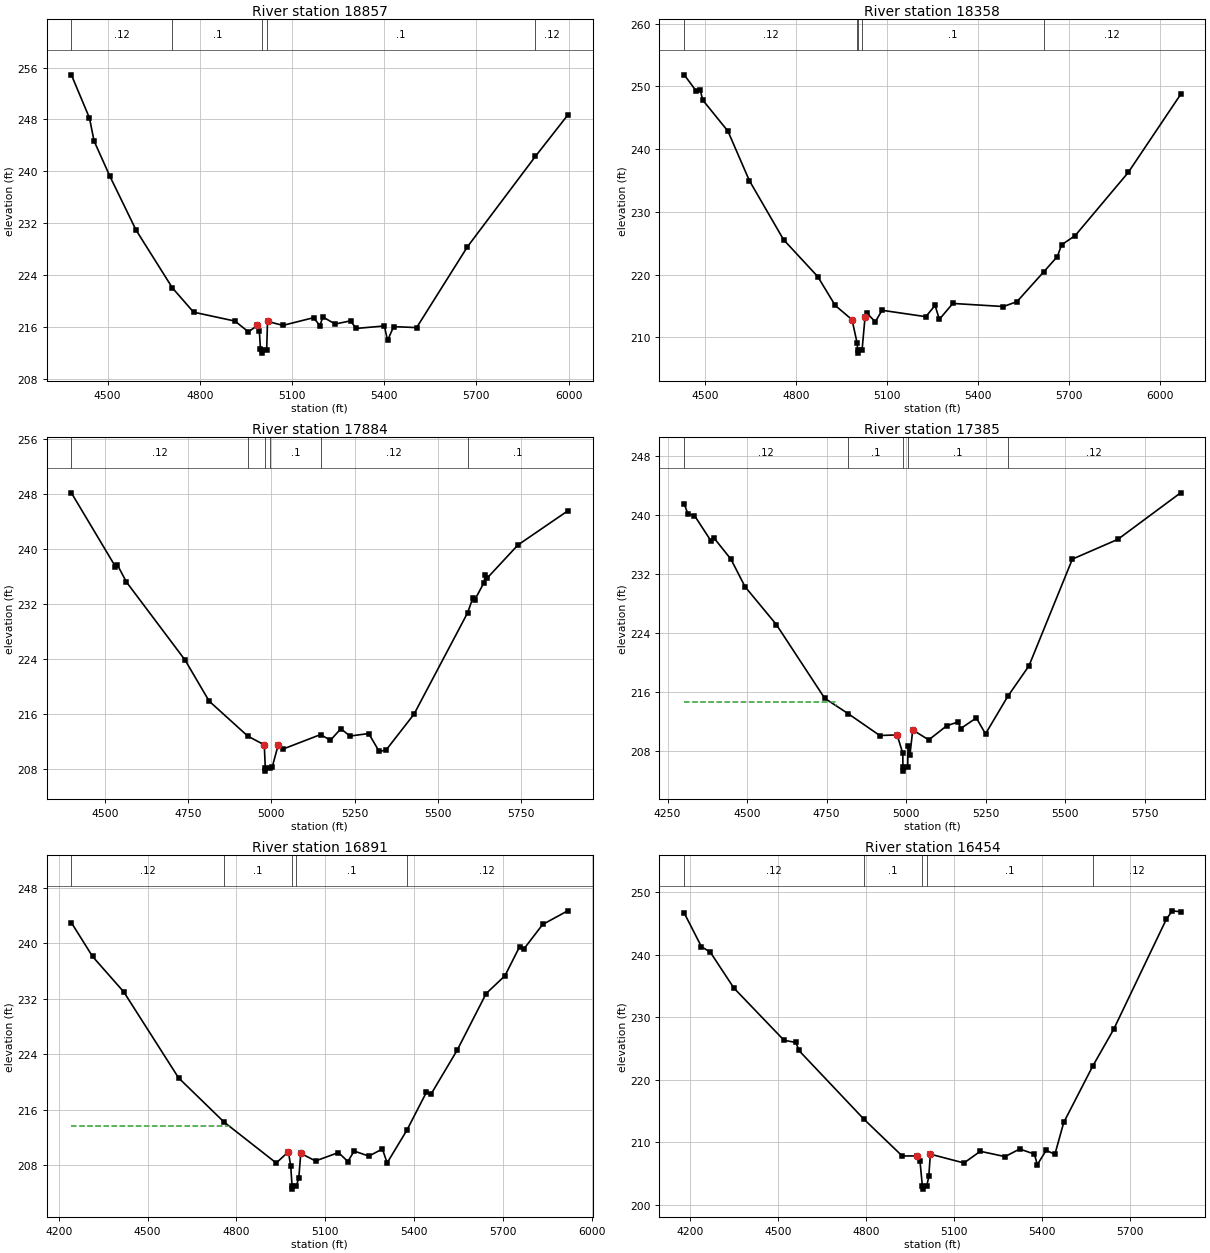
Type RM Length L Ch R = 1 ,18857   ,499,499,499
BEGIN DESCRIPTION:
GUM BRANCH 14.0
END DESCRIPTION:
XS GIS Cut Line= 3
      3798223.08     10178563.47      3797718.07     10178920.02
      3796722.09     10178971.43
#Sta/Elev= 30
  4381.8  254.88  4440.8  248.21  4455.6  244.69  4506.1  239.34  4592.3  230.93
  4710.6  222.01  4779.5  218.26  4914.6  216.88    4958  215.22  4987.5  216.22
  4993.7  215.39  4997.1  212.64    5003  212.44  5003.5  211.94  5017.5  212.44
  5020.2  216.84  5070.3  216.22  5170.4  217.41  5190.5  216.18  5200.5  217.51
  5240.5  216.43  5290.6  216.92  5308.5  215.75  5400.7  216.13  5410.8  213.89
  5430.8  216.03  5505.6  215.88  5671.1  228.36  5891.9  242.28  5997.3  248.66
#Mann= 5 ,-1 , 0
  4381.8     .12       0  4710.6      .1       0    5003     .07       0
  5017.5      .1       0  5891.9     .12       0
Bank Sta=4987.5,5020.2
XS Rating Curve= 0 ,0
Exp/Cntr=0.3,0.1

Type RM Length L Ch R = 1 ,18358   ,474,474,474
BEGIN DESCRIPTION:
GUM BRANCH 13.0
END DESCRIPTION:
XS GIS Cut Line= 3
      3798196.97     10178324.78      3797642.91     10178451.66
      3796682.59     10178919.23
#Sta/Elev= 30
  4431.6  251.86  4471.7  249.23  4484.6  249.41  4492.2  247.86  4575.6  242.88
  4646.1  235.01    4759  225.58  4871.8  219.69  4929.2   215.1  4984.7  212.82
  5001.6   209.1  5003.3  207.99  5003.8  207.49  5017.9  207.99  5027.6  213.21
  5033.2   213.9  5061.3  212.48  5083.8  214.32  5228.1   213.3  5258.6  215.11
  5272.6  212.87  5317.1  215.41  5483.9  214.92  5528.4  215.69  5617.7  220.49
  5661.8  222.89  5675.5  224.75  5720.6  226.23  5895.4  236.29  6068.1  248.73
#Mann= 5 ,-1 , 0
  4431.6     .12       0  5001.6      .1       0  5003.3     .07       0
  5017.9      .1       0  5617.7     .12       0
Bank Sta=4984.7,5027.6
XS Rating Curve= 0 ,0
Exp/Cntr=0.3,0.1

Type RM Length L Ch R = 1 ,17884   ,499,499,499
BEGIN DESCRIPTION:
GUM BRANCH 12.0
END DESCRIPTION:
XS GIS Cut Line= 3
      3798017.88     10177911.06      3797437.19     10178065.97
      3796586.77     10178329.11
#Sta/Elev= 30
    4399  248.17  4531.6  237.43  4536.8  237.74  4564.6   235.2  4740.6  223.87
    4813   217.9    4929  212.82  4978.6  211.55  4981.6  208.23  4982.1  207.73
  4996.4  208.23  5002.4  208.31  5020.2  211.49  5035.1  210.94  5147.7  213.04
  5177.3  212.22  5208.7  213.89    5236  212.83  5292.4  213.19  5323.8  210.59
  5344.7   210.8  5428.5  216.01  5589.2  230.71  5605.2  232.89  5610.5  232.57
  5637.8  235.04  5643.1  236.27  5648.3  235.78  5740.9   240.6  5890.2  245.54
#Mann= 6 ,-1 , 0
    4399     .12       0    4929      .1       0  4981.6     .07       0
  4996.4      .1       0  5147.7     .12       0  5589.2      .1       0
Bank Sta=4978.6,5020.2
XS Rating Curve= 0 ,0
Exp/Cntr=0.3,0.1

Type RM Length L Ch R = 1 ,17385   ,494,494,494
BEGIN DESCRIPTION:
GUM BRANCH 11.0
END DESCRIPTION:
XS GIS Cut Line= 3
      3797919.22     10177495.78      3797237.36     10177642.64
       3796534.7     10178142.47
#Sta/Elev= 30
  4302.5  241.46  4314.1  240.12  4334.6  239.91  4385.7  236.52  4394.9  236.93
  4449.3  233.99  4493.5  230.28  4592.1  225.14  4743.8  215.18  4818.2  213.08
  4916.9  210.14  4971.4  210.22  4989.3  207.72  4989.7  205.82  4990.2  205.32
  5004.7  205.82  5005.7  208.73  5011.9  207.57  5020.5  210.89  5070.9  209.55
  5127.5  211.46  5163.1  211.97  5171.2  211.08  5220.3  212.52  5249.2  210.36
  5319.5  215.46  5385.7  219.56  5522.2  234.01  5664.9  236.68  5862.3  242.98
#Mann= 5 ,-1 , 0
  4302.5     .12       0  4818.2      .1       0  4989.7     .07       0
  5004.7      .1       0  5319.5     .12       0
#XS Ineff= 2 , 0
       0  4779.2  214.72               0
Permanent Ineff=
       F       F
Bank Sta=4971.4,5020.5
XS Rating Curve= 0 ,0
Exp/Cntr=0.3,0.1

Type RM Length L Ch R = 1 ,16891   ,437,437,437
BEGIN DESCRIPTION:
GUM BRANCH 10.0
END DESCRIPTION:
XS GIS Cut Line= 3
      3797949.66     10177343.88      3797214.44     10177162.77
      3796348.01     10177469.75
#Sta/Elev= 30
  4242.8     243  4314.4  238.12  4419.7  233.02    4605  220.62  4758.4  214.26
  4934.7  208.36  4975.9  209.97  4983.6  207.94  4988.2  205.09  4988.7  204.59
  5003.2  205.09  5011.1  206.26  5017.6  209.74  5067.5  208.65  5144.9  209.86
  5176.7  208.57    5198  210.08  5247.6  209.35  5293.4  210.38  5309.3  208.37
  5376.1  213.09    5442  218.55  5458.5  218.34  5545.8  224.61  5643.8  232.78
  5707.2  235.34  5756.7  239.53  5770.8  239.18  5834.5  242.73  5919.2   244.7
#Mann= 5 ,-1 , 0
  4242.8     .12       0  4758.4      .1       0  4988.2     .07       0
  5003.2      .1       0  5376.1     .12       0
#XS Ineff= 2 , 0
       0  4781.3  213.67               0
Permanent Ineff=
       F       F
Bank Sta=4975.9,5017.6
XS Rating Curve= 0 ,0
Exp/Cntr=0.3,0.1

Type RM Length L Ch R = 1 ,16454   ,457,457,457
BEGIN DESCRIPTION:
GUM BRANCH 9.0
END DESCRIPTION:
XS GIS Cut Line= 3
        3798006.     10176862.09      3797191.52     10176757.22
      3796319.53     10176705.96
#Sta/Elev= 30
  4178.8   246.7  4237.4  241.32  4267.7  240.44  4348.3  234.69  4519.7  226.31
  4560.1  225.98  4570.2  224.69  4792.1  213.69    4923  207.79  4973.5   207.8
  4983.5  207.05  4991.8  202.98  4992.3  202.48  5006.9  202.98  5013.7  204.51
  5019.1  208.08  5133.9  206.67  5189.5  208.54  5274.1  207.69  5324.2  208.91
  5374.3  208.09  5384.3   206.4  5414.4  208.68  5444.4  208.07  5474.5  213.16
  5573.3  222.17  5644.8  228.06  5825.1  245.74  5845.1  247.06  5873.5  246.91
#Mann= 5 ,-1 , 0
  4178.8     .12       0  4792.1      .1       0  4991.8     .07       0
  5006.9      .1       0  5573.3     .12       0
Bank Sta=4973.5,5019.1
XS Rating Curve= 0 ,0
Exp/Cntr=0.3,0.1

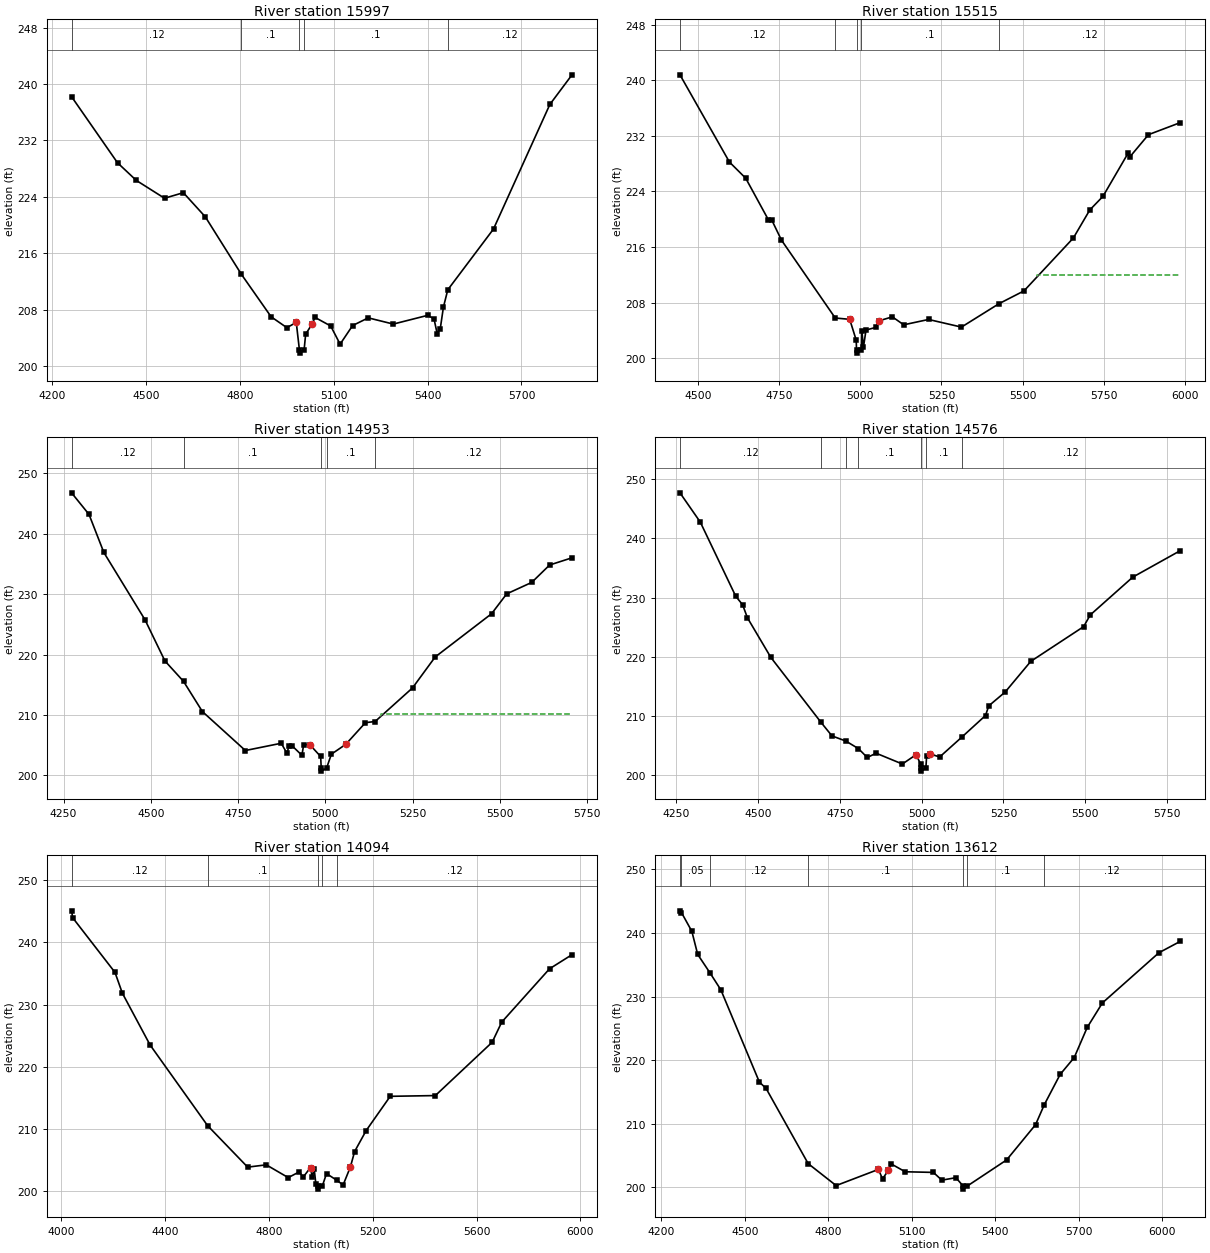
Type RM Length L Ch R = 1 ,15997   ,482,482,482
BEGIN DESCRIPTION:
GUM BRANCH 8.0
END DESCRIPTION:
XS GIS Cut Line= 3
      3797984.29     10176276.16      3797247.77     10176331.52
      3796387.11     10176371.65
#Sta/Elev= 30
  4261.4   238.2  4408.3  228.83  4468.4  226.33  4558.7   223.8  4618.8  224.59
    4689  221.17  4804.5  213.01  4899.6  206.99  4949.8  205.45  4979.9  206.19
  4989.9  202.34  4990.4  201.84  5005.1  202.34  5009.9  204.52    5030  205.93
    5040   206.9    5090  205.69  5120.1  203.11  5160.1  205.75  5210.1  206.84
  5290.2  205.96  5400.4   207.2  5420.4   206.7  5430.4  204.62  5440.4  205.31
  5450.4  208.35  5464.4  210.82  5610.6  219.44  5790.8   237.1  5861.6   241.3
#Mann= 5 ,-1 , 0
  4261.4     .12       0  4804.5      .1       0  4989.9     .07       0
  5005.1      .1       0  5464.4     .12       0
Bank Sta=4979.9,5030
XS Rating Curve= 0 ,0
Exp/Cntr=0.3,0.1

Type RM Length L Ch R = 1 ,15515   ,562,562,562
BEGIN DESCRIPTION:
GUM BRANCH 7.0
END DESCRIPTION:
XS GIS Cut Line= 3
      3797880.18     10175915.92      3797325.55     10175907.22
      3796352.61     10175751.02
#Sta/Elev= 30
  4445.3  240.81  4597.6  228.24  4647.7  225.91  4717.7   219.9  4727.7   219.9
  4757.7  216.99  4923.2  205.77  4967.7  205.58  4987.7  202.58  4988.7  201.21
  4989.2  200.71  5003.9  201.21    5005  203.97    5010  201.57  5017.9  204.04
  5048.3  204.42  5058.4  205.37  5098.9  205.94  5133.9  204.79  5210.4  205.56
  5311.6  204.46    5427  207.83  5504.1  209.68    5656   217.3  5706.6  221.34
  5747.1   223.3  5825.2  229.58  5830.3  229.01  5887.2  232.19  5985.4  233.93
#Mann= 5 ,-1 , 0
  4445.3     .12       0  4923.2      .1       0  4988.7     .07       0
  5003.9      .1       0    5427     .12       0
#XS Ineff= 2 , 0
       0                  5544.6       0  211.98
Permanent Ineff=
       F       F
Bank Sta=4967.7,5058.4
XS Rating Curve= 0 ,0
Exp/Cntr=0.3,0.1

Type RM Length L Ch R = 1 ,14953   ,377,377,377
BEGIN DESCRIPTION:
GUM BRANCH 6.0
END DESCRIPTION:
XS GIS Cut Line= 3
      3797862.76     10175677.19      3797154.72     10175511.39
       3796465.3     10175356.04
#Sta/Elev= 30
  4272.8  246.76  4322.8  243.19  4365.3  236.89  4483.3  225.75  4540.3  218.95
  4593.6  215.57  4647.6  210.58  4770.8  204.13  4873.5  205.33  4890.3  203.65
  4895.5  204.93  4904.3  204.93  4932.8  203.34  4937.9   205.1  4955.7  205.08
  4986.5  203.14  4988.2  201.22  4988.7  200.72  5003.5  201.22  5017.3  203.53
  5058.3  205.14  5114.9  208.74  5142.6  208.93  5249.8  214.49  5314.6   219.6
  5476.3  226.76  5519.5  230.04  5591.3  231.94  5642.6  234.82  5706.7  236.01
#Mann= 5 ,-1 , 0
  4272.8     .12       0  4593.6      .1       0  4988.2     .07       0
  5003.5      .1       0  5142.6     .12       0
#XS Ineff= 2 , 0
       0                  5158.2       0  210.14
Permanent Ineff=
       F       F
Bank Sta=4955.7,5058.3
XS Rating Curve= 0 ,0
Exp/Cntr=0.3,0.1

Type RM Length L Ch R = 1 ,14576   ,482,482,482
BEGIN DESCRIPTION:
GUM BRANCH 5.0
END DESCRIPTION:
XS GIS Cut Line= 3
      3797888.84     10175616.43      3797283.19     10175193.33
      3796492.12     10175199.77
#Sta/Elev= 30
  4261.2  247.66  4323.4  242.72  4431.8  230.21  4452.7  228.79  4467.5  226.58
    4539  219.91  4692.5  208.95  4725.9  206.67  4768.4   205.8  4806.9  204.52
  4833.8  203.03  4860.9  203.75  4941.1  201.93    4983   203.5  4997.6  201.85
  4997.7  201.23  4998.2  200.73    5013  201.23  5015.3  203.27  5025.3  203.63
  5055.3  203.12  5124.2  206.53  5195.3  210.11  5205.3  211.74  5255.3  214.06
  5333.7  219.24  5495.4   225.1  5515.4  227.06  5645.4  233.44  5791.1  237.92
#Mann= 7 ,-1 , 0
  4261.2     .12       0  4692.5      .1       0  4768.4     .12       0
  4806.9      .1       0  4997.7     .07       0    5013      .1       0
  5124.2     .12       0
Bank Sta=4983,5025.3
XS Rating Curve= 0 ,0
Exp/Cntr=0.3,0.1

Type RM Length L Ch R = 1 ,14094   ,482,482,482
BEGIN DESCRIPTION:
GUM BRANCH 4.0
END DESCRIPTION:
XS GIS Cut Line= 3
      3797975.69     10175499.29      3797359.58     10174763.47
      3796413.14     10174561.75
#Sta/Elev= 30
  4040.3  245.04  4044.6  243.93  4207.5  235.16  4235.9  231.82  4342.6  223.51
  4564.1  210.56  4718.6  203.89  4790.2  204.26  4874.8  202.21  4917.7  203.14
    4932  202.27  4960.6  203.83  4967.1   202.3  4974.9  203.53  4981.4  201.12
  4990.6  200.86  4991.1  200.36  5006.1  200.86  5022.2  202.85    5062  201.78
  5086.1  201.02  5114.2  203.92  5130.5   206.4  5174.9  209.76  5267.6  215.26
  5441.4  215.38  5660.2  223.94    5697  227.17  5881.1  235.73  5967.7     238
#Mann= 5 ,-1 , 0
  4040.3     .12       0  4564.1      .1       0  4990.6     .07       0
  5006.1      .1       0    5062     .12       0
Bank Sta=4960.6,5114.2
XS Rating Curve= 0 ,0
Exp/Cntr=0.3,0.1

Type RM Length L Ch R = 1 ,13612   ,483,483,483
BEGIN DESCRIPTION:
GUM BRANCH 3.0
END DESCRIPTION:
XS GIS Cut Line= 3
      3798188.33     10174544.39      3797493.61       10174310.
      3796440.99       10174479.
#Sta/Elev= 30
  4266.8  243.49  4272.2  243.22  4309.5  240.27  4330.6  236.63  4375.1  233.71
  4413.9  231.06  4552.3  216.57  4576.5  215.56  4727.8  203.74  4828.3  200.29
  4980.3  202.83  4995.1  201.35    5016  202.67  5026.1   203.7  5076.7  202.46
    5178  202.36  5208.4  201.14    5259  201.53  5284.8  200.23  5285.3  199.73
  5300.3  200.23  5441.3  204.32  5545.3  209.86  5576.7     213  5633.8  217.77
  5684.4  220.42  5731.1  225.16  5785.7  229.01  5988.9   236.9  6066.1   238.7
#Mann= 7 ,-1 , 0
  4266.8     .12       0  4272.2     .05       0  4375.1     .12       0
  4727.8      .1       0  5284.8     .07       0  5300.3      .1       0
  5576.7     .12       0
Bank Sta=4980.3,5016
XS Rating Curve= 0 ,0
Exp/Cntr=0.3,0.1

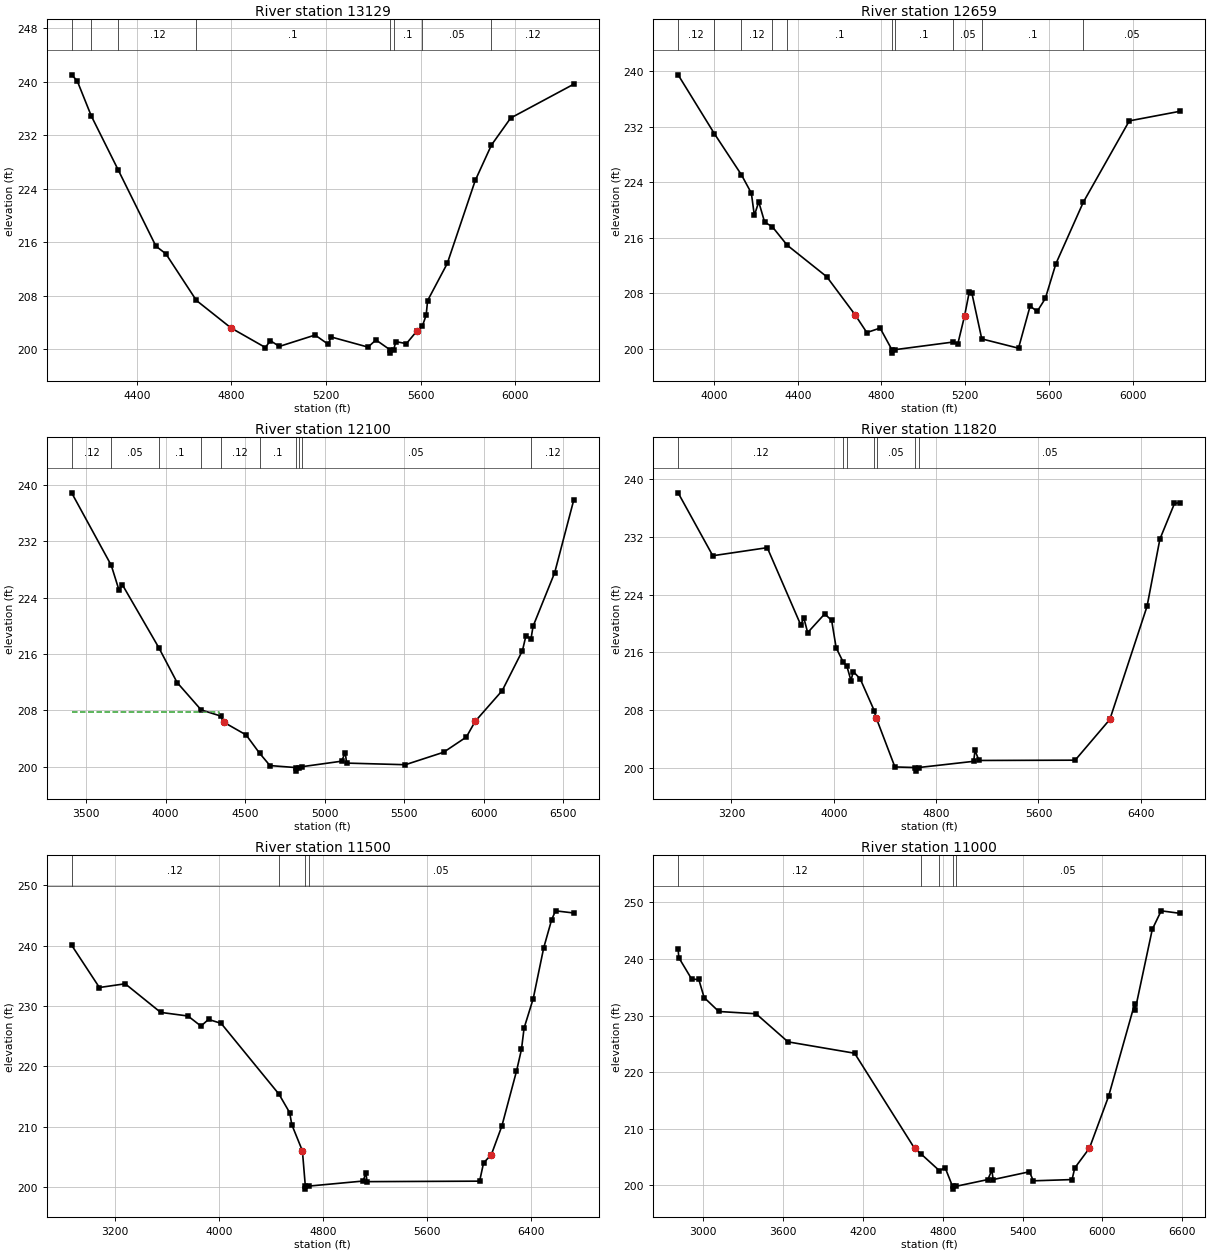
Type RM Length L Ch R = 1 ,13129   ,470,470,470
BEGIN DESCRIPTION:
GUM BRANCH 2.0
END DESCRIPTION:
XS GIS Cut Line= 3
      3798262.13     10174349.09      3797526.04     10173875.28
      3796408.86     10174431.52
#Sta/Elev= 30
  4124.6  241.01  4148.1  240.11  4207.6  234.87  4322.2  226.75  4480.9  215.42
  4523.1  214.27    4652  207.31  4798.5   203.2  4943.7  200.28  4964.9   201.3
  5002.7  200.44  5153.8  202.14  5210.2  200.75    5221  201.86  5377.7  200.34
  5411.3  201.41  5470.6  199.94  5471.1  199.44  5486.2  199.94  5495.2  201.16
    5540  200.86  5584.8  202.76  5606.9  203.42  5623.6  205.11  5629.6  207.28
  5712.9  212.84  5831.1  225.23  5899.4  230.51    5981  234.56    6248  239.62
#Mann= 8 ,-1 , 0
  4124.6     .12       0  4207.6     .05       0  4322.2     .12       0
    4652      .1       0  5470.6     .07       0  5486.2      .1       0
  5606.9     .05       0  5899.4     .12       0
Bank Sta=4798.5,5584.8
XS Rating Curve= 0 ,0
Exp/Cntr=0.3,0.1

Type RM Length L Ch R = 1 ,12659   ,559,559,559
BEGIN DESCRIPTION:
GUM BRANCH 1.0
END DESCRIPTION:
XS GIS Cut Line= 3
      3798327.24     10174236.24      3797463.67     10173443.44
      3796366.85     10173996.79
#Sta/Elev= 30
  3827.7  239.45  4001.2  230.97  4130.7  225.04  4177.9  222.41  4192.1   219.2
  4213.1  221.16  4241.4  218.23  4277.7  217.59  4349.2  214.92  4538.6  210.37
  4673.1  204.93  4729.8  202.34  4793.3  202.99  4849.6  199.88  4850.1  199.38
  4865.2  199.88  5143.4  200.98  5165.1  200.74  5196.9  204.71  5219.3  208.14
    5232  208.02  5279.3  201.43    5455  200.09  5510.5  206.16  5544.2  205.38
  5583.2  207.25  5633.7  212.25  5764.8  221.11  5984.6  232.82  6228.5  234.21
#Mann= 10 ,-1 , 0
  3827.7     .12       0  4001.2     .05       0  4130.7     .12       0
  4277.7     .05       0  4349.2      .1       0  4849.6     .07       0
  4865.2      .1       0  5143.4     .05       0  5279.3      .1       0
  5764.8     .05       0
#XS Ineff= 2 , 0
       0                  5219.3       0  208.14
Permanent Ineff=
       F       F
Bank Sta=4673.1,5196.9
XS Rating Curve= 0 ,0
Exp/Cntr=0.3,0.1

Type RM Length L Ch R = 1 ,12100   ,280,280,280
BEGIN DESCRIPTION:
GUM BRANCH 1.5
END DESCRIPTION:
XS GIS Cut Line= 3
      3798344.29     10174206.76      3797448.02     10172893.57
      3795974.53     10173423.84
#Sta/Elev= 30
  3410.1   238.9  3659.1   228.6  3707.6  225.09  3728.8  225.85  3957.3  216.93
  4072.9  211.96    4224  208.07  4346.2  207.21    4369  206.29  4506.5  204.52
  4590.6  201.94  4656.2  200.17  4821.8  199.88  4822.3  199.38  4837.5  199.88
  4854.8     200  5106.5  200.79  5129.3  202.01  5138.3  200.52  5507.2  200.29
  5747.6  202.06  5890.5  204.22  5946.1  206.45  6116.1  210.82    6243  216.49
  6264.9   218.6  6296.7  218.16  6309.8  219.95  6445.6  227.56    6566  237.93
#Mann= 10 ,-1 , 0
  3410.1     .12       0  3659.1     .05       0  3957.3      .1       0
    4224     .05       0  4346.2     .12       0  4590.6      .1       0
  4821.8     .03       0  4837.5      .1       0  4854.8     .05       0
  6296.7     .12       0
#XS Ineff= 2 , 0
       0  4333.1  207.71               0
Permanent Ineff=
       F       F
Bank Sta=4369,5946.1
XS Rating Curve= 0 ,0
Exp/Cntr=0.3,0.1

Type RM Length L Ch R = 1 ,11820   ,320,320,320
BEGIN DESCRIPTION:
GUM BRANCH 23.75
END DESCRIPTION:
XS GIS Cut Line= 3
      3799507.02     10171808.14      3797441.74     10172614.18
      3795738.75     10172472.21
#Sta/Elev= 30
    2783  238.14  3054.1  229.41  3479.9  230.53  3741.4  219.82  3765.9  220.76
  3795.8  218.74  3928.9  221.34  3983.3  220.43  4018.5  216.63  4073.3  214.66
  4102.7  214.06  4134.7  212.07  4151.7  213.34    4206  212.34  4318.2  207.83
  4327.9  206.95    4334   206.8  4477.7   200.1  4638.4  200.02  4638.9  199.52
  4664.5  200.02  5093.4  200.88  5104.2   202.4  5134.4     201    5887  201.04
  6157.9  206.69  6448.9  222.39  6549.2  231.71  6663.5  236.67  6708.9  236.79
#Mann= 7 ,-1 , 0
    2783     .12       0  4073.3      .1       0  4102.7     .12       0
  4318.2      .1       0    4334     .05       0  4638.4     .03       0
  4664.5     .05       0
Bank Sta=4327.9,6157.9
XS Rating Curve= 0 ,0
Exp/Cntr=0.3,0.1

Type RM Length L Ch R = 1 ,11500   ,500,500,500
BEGIN DESCRIPTION:
GUM BRANCH 23.5
END DESCRIPTION:
XS GIS Cut Line= 3
       3799500.1       10171763.      3797437.61     10172295.38
      3795717.48      10172121.4
#Sta/Elev= 30
  2869.9  240.07  3083.1  233.07  3281.2  233.69  3553.9  228.95    3764  228.35
  3863.7  226.68  3921.5  227.79  4018.6  227.13  4463.3   215.4  4545.3  212.34
  4561.7  210.35  4643.1  206.02  4665.5  200.18    4666  199.68  4691.6  200.18
  5110.3  201.02  5130.4   202.4  5140.5  200.92  6004.9     201    6035  204.01
  6095.3  205.41  6175.7  210.12  6288.2  219.21  6326.5  222.83  6346.6  226.35
  6416.9  231.24  6497.4  239.65  6557.7  244.25    6588  245.77  6728.9  245.41
#Mann= 4 ,-1 , 0
  2869.9     .12       0  4463.3     .05       0  4665.5     .03       0
  4691.6     .05       0
Bank Sta=4643.1,6095.3
XS Rating Curve= 0 ,0
Exp/Cntr=0.3,0.1

Type RM Length L Ch R = 1 ,11000   ,500,500,500
BEGIN DESCRIPTION:
GUM BRANCH 22.5
END DESCRIPTION:
XS GIS Cut Line= 3
      3799493.14     10171721.34      3797306.52     10171821.06
      3795728.33     10171980.35
#Sta/Elev= 30
  2811.1  241.76  2816.4  240.24  2913.2  236.44  2966.6  236.38  3006.6  233.19
  3116.7  230.72    3397  230.32  3637.2  225.35  4137.8  223.34  4588.2  206.53
  4640.5  205.46  4774.9  202.58  4818.5  203.09  4873.9  199.81  4874.4  199.31
    4900  199.81  5139.4     201  5169.5  202.66  5179.6     201  5452.1  202.38
  5481.1  200.78  5772.6     201  5792.7  203.05  5903.2  206.56  6047.3  215.74
  6242.4  232.02  6247.4  231.07  6375.6  245.25  6442.5  248.52  6586.2  248.07
#Mann= 5 ,-1 , 0
  2811.1     .12       0  4640.5      .1       0  4774.9     .05       0
  4873.9     .03       0    4900     .05       0
Bank Sta=4588.2,5903.2
XS Rating Curve= 0 ,0
Exp/Cntr=0.3,0.1

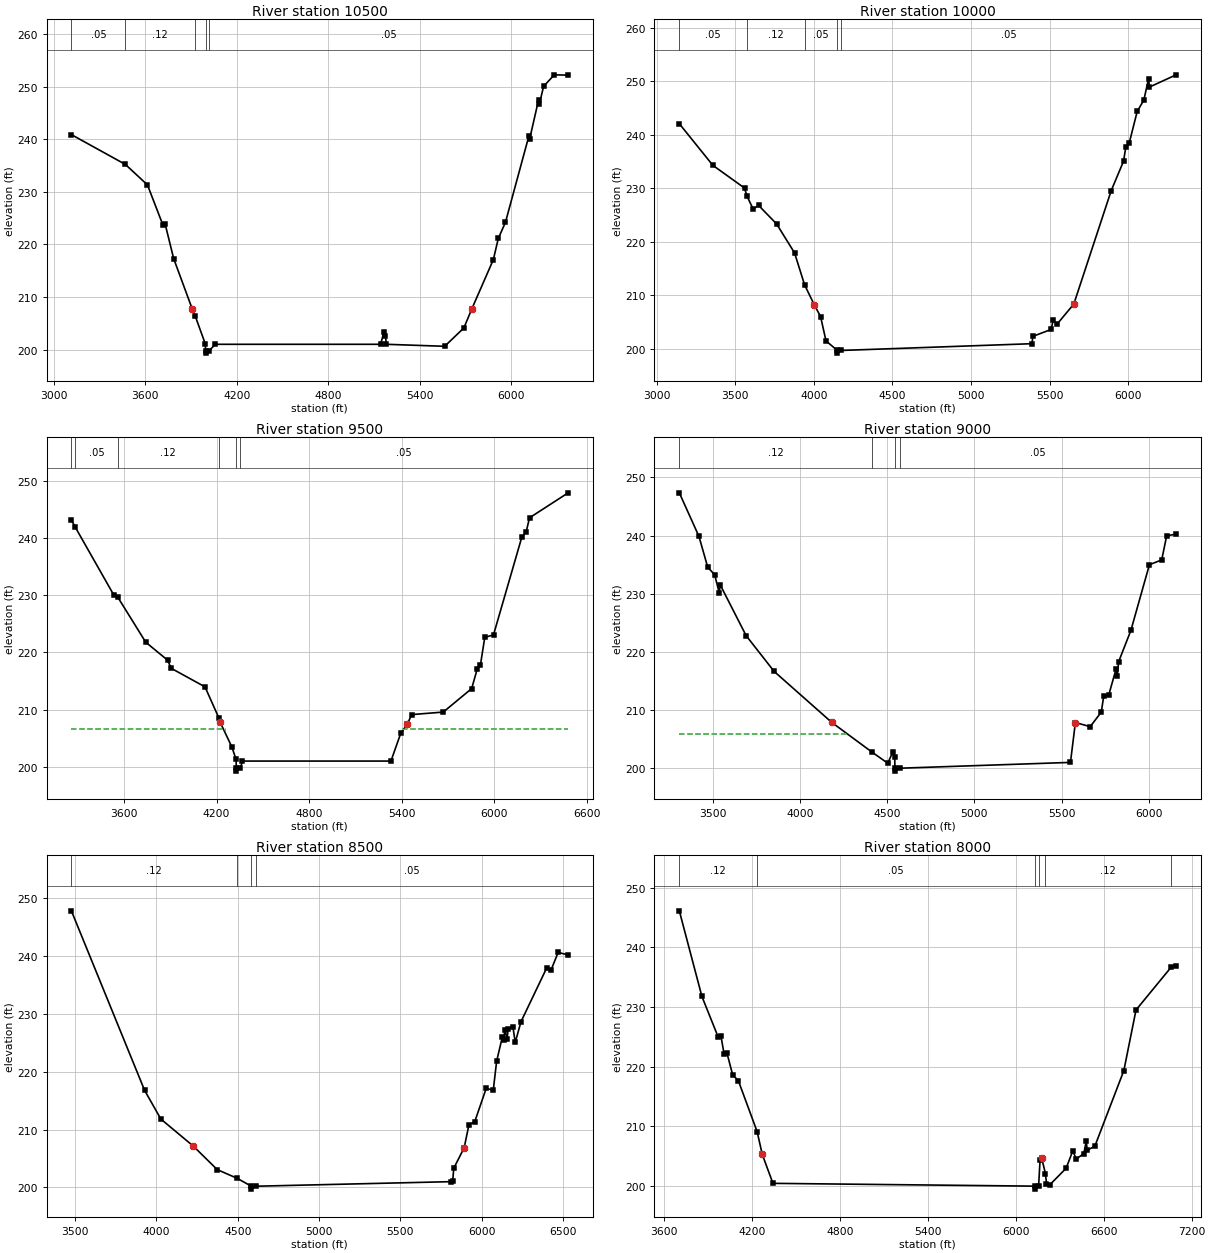
Type RM Length L Ch R = 1 ,10500   ,500,500,500
BEGIN DESCRIPTION:
GUM BRANCH 21.5
END DESCRIPTION:
XS GIS Cut Line= 3
      3798658.05     10170244.21      3797135.03     10171351.84
      3795825.98     10171763.33
#Sta/Elev= 30
  3116.8  240.92  3470.8  235.24  3615.4  231.34  3715.9  223.76  3730.6  223.97
    3787  217.33  3908.4  207.76  3928.1   206.4    3995  201.03  3995.7  199.82
  3996.2  199.32  4021.8  199.82    4059     201    5143     201  5164.8  203.27
  5175.2  202.67  5180.7     201  5563.1  200.62  5688.9  204.12  5741.3  207.77
    5882  217.12  5914.4  221.15  5961.4  224.23    6114  240.56  6119.2     240
  6178.8  247.58    6184  246.77  6211.2   250.1  6281.2   252.3  6372.2  252.24
#Mann= 5 ,-1 , 0
  3116.8     .05       0  3470.8     .12       0  3928.1     .05       0
  3995.7     .03       0  4021.8     .05       0
Bank Sta=3908.4,5741.3
XS Rating Curve= 0 ,0
Exp/Cntr=0.3,0.1

Type RM Length L Ch R = 1 ,10000   ,500,500,500
BEGIN DESCRIPTION:
GUM BRANCH 20.5
END DESCRIPTION:
XS GIS Cut Line= 3
       3798603.8     10170124.86      3796922.32      10170908.2
      3795836.83     10171633.13
#Sta/Elev= 30
    3145  242.06  3358.3  234.29  3559.7  230.05  3575.3  228.57  3614.9  226.11
  3649.3  226.81  3763.7  223.36  3878.1  217.95  3941.9  211.99  4003.5  208.26
  4043.7  206.06  4078.2  201.52  4150.5  199.74    4151  199.24  4176.7  199.74
  5388.2     201  5394.2  202.37  5510.4  203.66  5523.4  205.41  5546.5  204.59
  5654.7   208.4  5892.8  229.59  5970.9  235.05  5985.9  237.77    6007  238.43
    6058  244.36  6100.1  246.46  6130.1  250.43  6136.1   248.9  6305.3  251.18
#Mann= 5 ,-1 , 0
    3145     .05       0  3575.3     .12       0  3941.9     .05       0
  4150.5     .03       0  4176.7     .05       0
Bank Sta=4003.5,5654.7
XS Rating Curve= 0 ,0
Exp/Cntr=0.3,0.1

Type RM Length L Ch R = 1 ,9500    ,500,500,500
BEGIN DESCRIPTION:
GUM BRANCH 19.5
END DESCRIPTION:
XS GIS Cut Line= 3
      3798516.96     10170016.37      3796822.86     10170418.19
      3795804.29     10171492.07
#Sta/Elev= 30
  3258.9  243.16  3285.2  241.86  3535.5  229.97  3560.2  229.65    3741  221.79
  3884.9   218.6  3903.9  217.26  4125.3  213.98  4214.9  208.56  4224.1  207.76
  4299.3  203.48  4326.8   201.3  4328.4  199.74  4328.9  199.24  4354.7  199.74
  4367.9     201    5331     201  5394.6  205.86    5437  207.45  5465.4  209.13
  5670.4  209.57  5854.5  213.68  5889.7  217.03  5911.1  217.78  5939.4  222.63
  5996.1  223.08  6179.7  240.18    6208  241.11  6229.5  243.55  6480.1  247.92
#Mann= 6 ,-1 , 0
  3258.9     .12       0  3285.2     .05       0  3560.2     .12       0
  4214.9     .05       0  4328.4     .03       0  4354.7     .05       0
#XS Ineff= 2 , 0
       0    4252  206.64  5408.7       0   206.6
Permanent Ineff=
       F       F
Bank Sta=4224.1,5437
XS Rating Curve= 0 ,0
Exp/Cntr=0.3,0.1

Type RM Length L Ch R = 1 ,9000    ,500,500,500
BEGIN DESCRIPTION:
GUM BRANCH 18.5
END DESCRIPTION:
XS GIS Cut Line= 3
      3798430.19      10169810.2      3796741.99     10169926.55
      3795912.83     10170732.48
#Sta/Elev= 30
  3307.8  247.35  3420.4  239.86  3470.5  234.58  3510.6  233.25  3537.1   230.1
  3542.1  231.54    3691  222.79  3851.4  216.65  4182.2  207.87  4410.4  202.82
    4503  200.86    4533  202.85  4543.1  201.85  4544.1     200  4544.6   199.5
  4570.7     200  5550.6     201  5578.9  207.86  5663.7  207.14  5727.5  209.66
  5741.6  212.44  5769.9  212.56  5812.4  217.09  5819.3  215.89  5826.5  218.28
  5897.3  223.71  6003.3  234.99    6074  235.82  6102.3  239.97  6156.3  240.24
#Mann= 4 ,-1 , 0
  3307.8     .12       0  4410.4     .05       0  4544.1     .03       0
  4570.7     .05       0
#XS Ineff= 2 , 0
       0  4272.4  205.96               0
Permanent Ineff=
       F       F
Bank Sta=4182.2,5578.9
XS Rating Curve= 0 ,0
Exp/Cntr=0.3,0.1

Type RM Length L Ch R = 1 ,8500    ,500,500,500
BEGIN DESCRIPTION:
GUM BRANCH 17.5
END DESCRIPTION:
XS GIS Cut Line= 3
      3798278.23     10169473.83      3796755.46     10169426.76
      3795825.98     10170645.72
#Sta/Elev= 30
  3476.5  247.74  3927.1  216.75  4027.1   211.8  4227.2  207.12  4373.7  203.08
  4496.1  201.58  4584.1  200.21  4584.6  199.71  4610.7  200.21  5814.5     201
  5822.7   201.1    5829  203.31  5893.4  206.87  5922.5  210.84  5957.9  211.33
  6028.6  217.09  6072.2   216.8    6093   221.8  6128.3  226.01  6136.6  225.38
  6142.9  227.17  6157.4  225.64  6163.7  227.37  6192.8  227.74  6207.3  225.04
  6242.7   228.6  6400.6  237.87  6427.7  237.53  6471.3  240.56  6532.9  240.13
#Mann= 4 ,-1 , 0
  3476.5     .12       0  4496.1     .05       0  4584.1     .03       0
  4610.7     .05       0
Bank Sta=4227.2,5893.4
XS Rating Curve= 0 ,0
Exp/Cntr=0.3,0.1

Type RM Length L Ch R = 1 ,8000    ,759,759,759
BEGIN DESCRIPTION:
GUM BRANCH 16.5
END DESCRIPTION:
XS GIS Cut Line= 3
      3798050.41     10168562.37      3796808.01     10168929.84
      3794903.64     10169799.38
#Sta/Elev= 30
  3704.4  246.13  3858.4  231.77  3968.6     225  3988.6  225.11  4009.5  222.13
  4029.9  222.22  4068.4  218.59  4106.9  217.64  4235.7  209.04  4270.2  205.25
  4343.2  200.39    6129  199.92  6129.5  199.42  6155.6  199.92  6165.3  204.26
  6176.4  204.64  6202.3  202.02  6209.4  200.36  6231.4  200.13    6343  202.92
  6389.1  205.85  6412.1  204.46  6463.7  205.38  6481.2  207.49  6486.7  205.95
  6539.2  206.62  6737.1  219.32  6820.1  229.49  7058.4  236.63  7093.5   236.8
#Mann= 6 ,-1 , 0
  3704.4     .12       0  4235.7     .05       0    6129     .03       0
  6155.6     .05       0  6202.3     .12       0  7058.4     .05       0
#XS Ineff= 2 ,-1
  6389.1  6481.2  205.85  6481.2  6555.8  207.49
Permanent Ineff=
       F       F
Bank Sta=4270.2,6176.4
XS Rating Curve= 0 ,0
Exp/Cntr=0.3,0.1