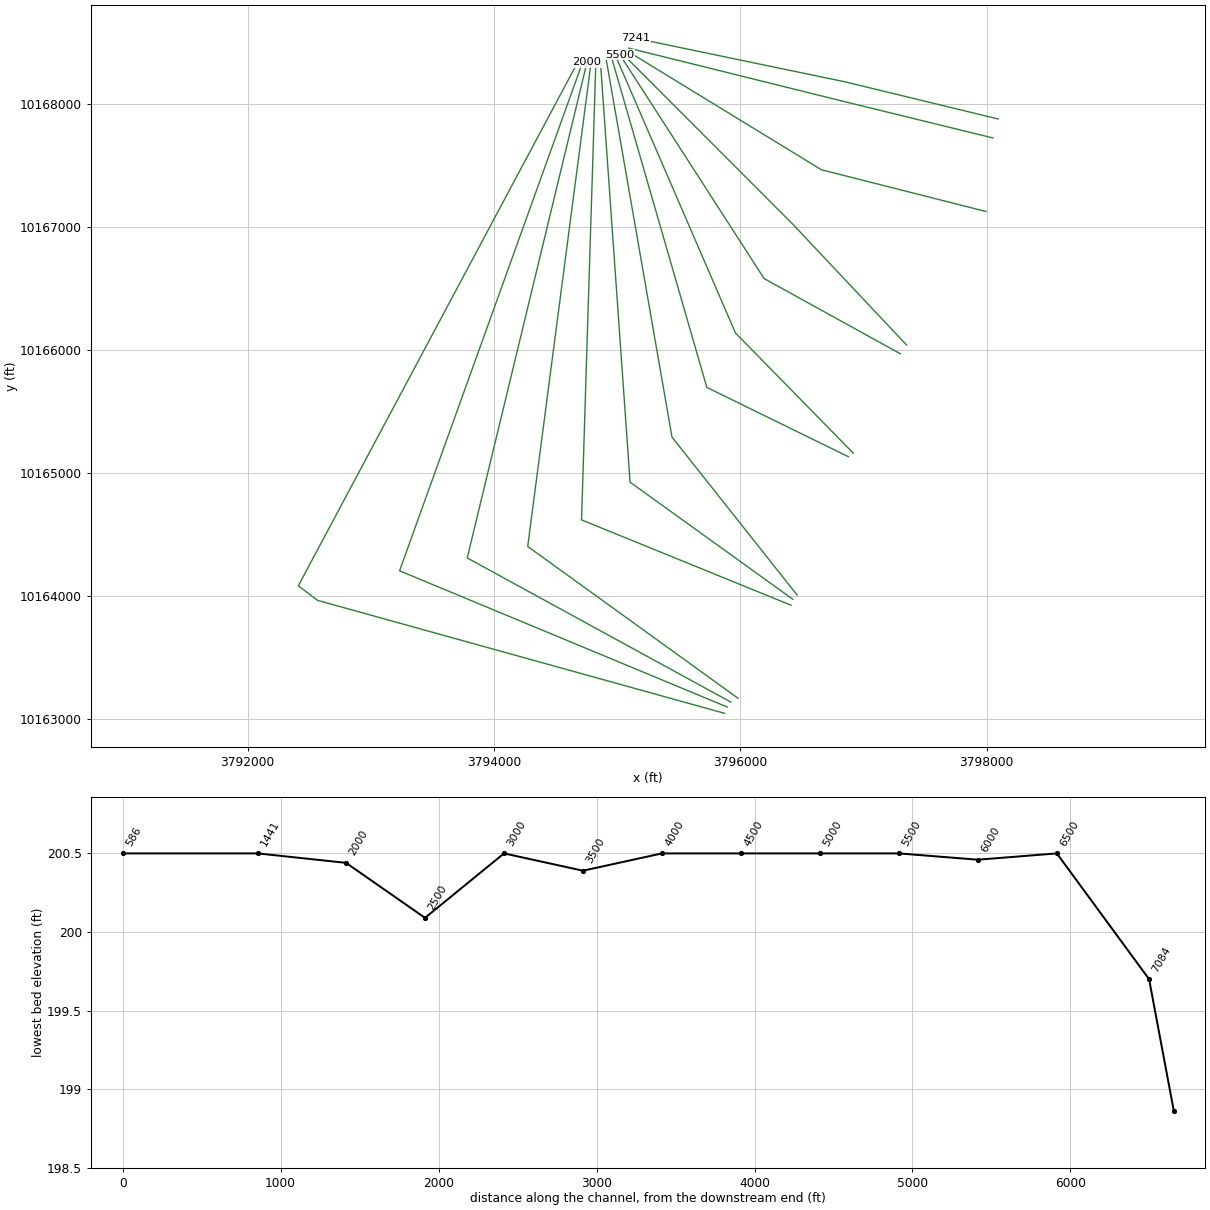
HEC-RAS study GUM BRANCH.prj: GUM BRANCH Base Level Engineering

--- GUM BRANCH.g01 (geometry) --- (continued)

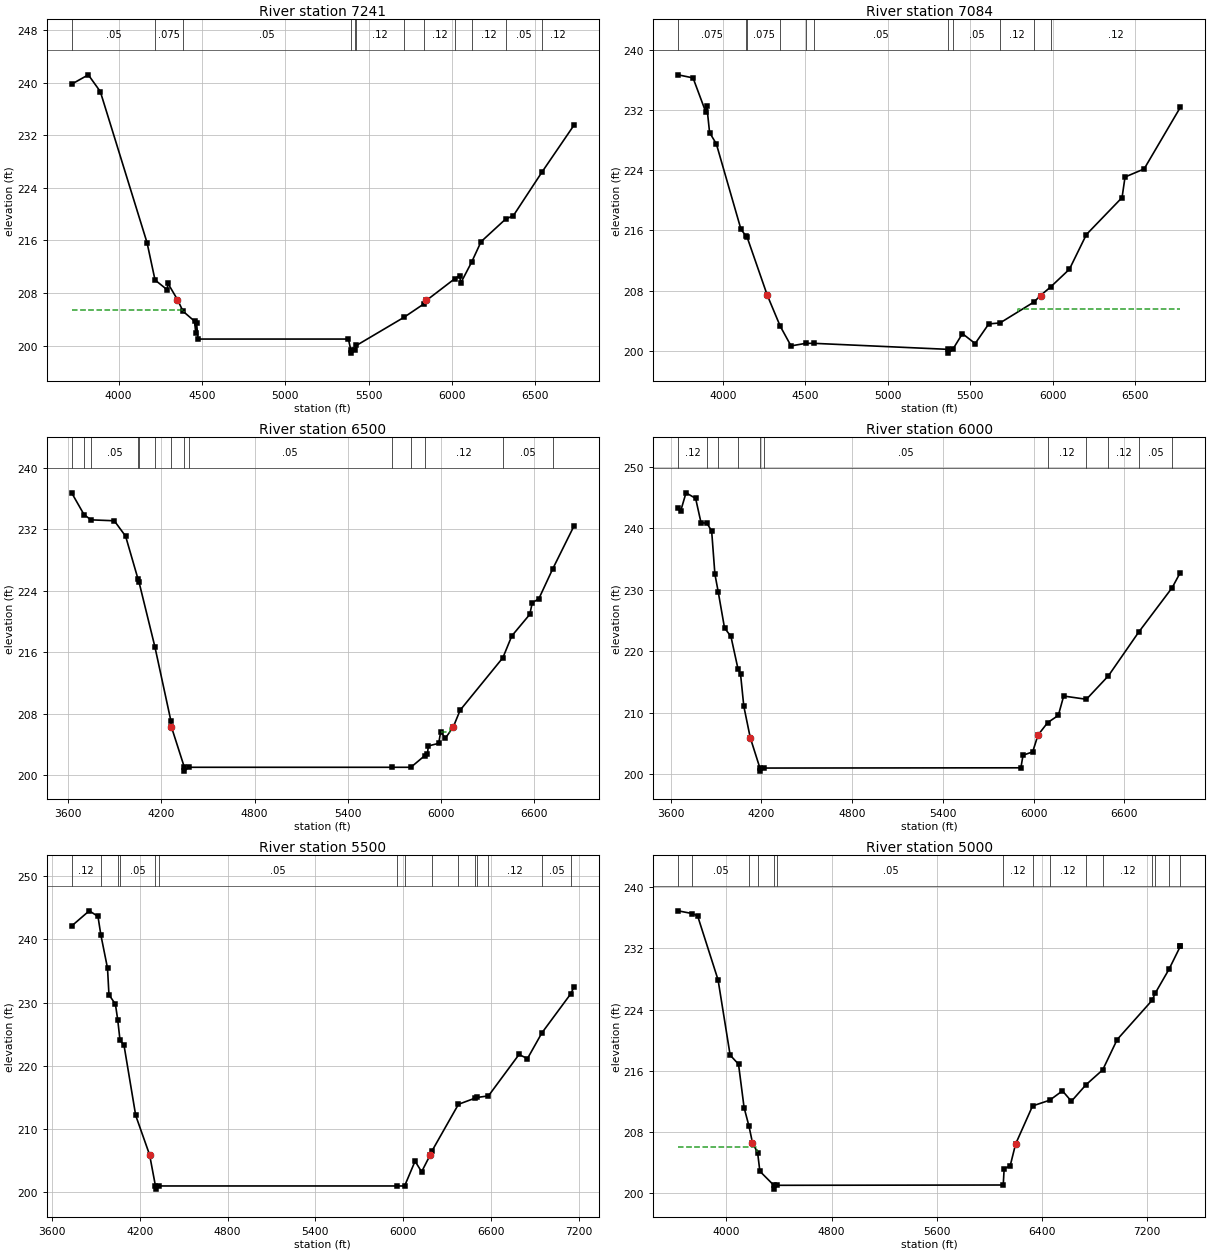
Type RM Length L Ch R = 1 ,7241    ,157,157,157
BEGIN DESCRIPTION:
GUM BRANCH 15.5
END DESCRIPTION:
XS GIS Cut Line= 3
      3798095.01     10167879.71      3796848.96     10168182.45
      3795152.59      10168535.9
#Sta/Elev= 30
  3717.7  239.76  3817.7  241.18  3889.7  238.64  4170.5  215.64  4218.3  209.98
  4290.6  208.51  4295.8  209.46  4352.8  207.01  4386.3  205.23  4455.7  203.71
  4462.8   201.9  4467.9  203.41  4476.3     201  5379.1     201  5393.7  199.36
  5394.2  198.86  5420.8  199.36  5426.9  200.02  5712.7   204.3  5833.8  206.37
  5847.5  206.87  6017.6  210.17  6047.7  210.66  6053.3   209.5  6119.2   212.7
  6175.8  215.81  6322.7  219.23  6369.9  219.77  6541.2  226.38  6732.8  233.49
#Mann= 12 ,-1 , 0
  3717.7     .05       0  4218.3    .075       0  4386.3     .05       0
  5393.7     .03       0  5420.8     .05       0  5426.9     .12       0
  5712.7     .05       0  5833.8     .12       0  6017.6     .05       0
  6119.2     .12       0  6322.7     .05       0  6541.2     .12       0
#XS Ineff= 2 , 0
       0    4394  205.41               0
Permanent Ineff=
       F       F
Bank Sta=4352.8,5847.5
XS Rating Curve= 0 ,0
Exp/Cntr=0.3,0.1

Type RM Length L Ch R = 1 ,7084    ,584,584,584
BEGIN DESCRIPTION:
GUM BRANCH 14.5
END DESCRIPTION:
XS GIS Cut Line= 3
      3798053.22     10167725.05      3796817.67      10168028.2
      3795094.76     10168456.31
#Sta/Elev= 30
  3727.8  236.66  3818.4  236.25  3896.4  231.67  3901.6  232.58  3918.7     229
  3959.9  227.48  4109.5  216.12  4142.1   215.2  4145.9  215.14  4268.8  207.39
  4347.2  203.29  4412.9  200.66  4502.7     201  4552.4     201  5367.5   200.2
    5368   199.7  5394.6   200.2  5453.2  202.29  5530.4  200.97    5613  203.58
  5681.4  203.71  5886.7  206.48  5927.2  207.35  5989.4  208.51  6102.3  210.84
  6205.4  215.45  6421.8  220.36  6439.9  223.09  6555.7  224.16  6775.3  232.34
#Mann= 11 ,-1 , 0
  3727.8    .075       0  4142.1     .12       0  4145.9    .075       0
  4347.2     .05       0  4502.7    .075       0  4552.4     .05       0
  5367.5     .05       0  5394.6     .05       0  5681.4     .12       0
  5886.7     .05       0  5989.4     .12       0
#XS Ineff= 2 , 0
       0                  5793.2       0  205.58
Permanent Ineff=
       F       F
Bank Sta=4268.8,5927.2
XS Rating Curve= 0 ,0
Exp/Cntr=0.3,0.1

Type RM Length L Ch R = 1 ,6500    ,500,500,500
BEGIN DESCRIPTION:
GUM BRANCH 13.5
END DESCRIPTION:
XS GIS Cut Line= 3
      3797994.73     10167127.32      3796658.89     10167466.79
      3795075.52     10168437.05
#Sta/Elev= 30
  3621.7  236.75  3701.6  233.91  3746.5  233.23  3896.4  233.11  3969.3   231.1
  4048.4  225.58    4055  225.18  4157.8  216.71  4260.6  207.09  4264.8  206.24
  4347.8     201  4348.3   200.5    4375     201  5685.6     201  5807.1     201
  5896.3  202.51  5913.7   202.7  5919.6  203.78  5986.4  204.12  5998.9   205.6
  6029.8   204.8  6080.2  206.25  6124.5  208.44  6399.8  215.27  6457.3  218.11
  6573.3  220.92  6588.8  222.42  6631.4  222.95  6719.9   226.8    6857  232.39
#Mann= 14 ,-1 , 0
  3621.7     .05       0  3701.6     .12       0  3746.5     .05       0
  4048.4     .12       0    4055     .05       0  4157.8     .12       0
  4260.6     .05       0  4347.8     .03       0    4375     .05       0
  5685.6     .12       0  5807.1     .05       0  5896.3     .12       0
  6399.8     .05       0  6719.9     .12       0
#XS Ineff= 2 ,-1
  5998.9  6056.9   205.6  6056.9  6087.8  206.17
Permanent Ineff=
       F       F
Bank Sta=4264.8,6080.2
XS Rating Curve= 0 ,0
Exp/Cntr=0.3,0.1

Type RM Length L Ch R = 1 ,6000    ,500,500,500
BEGIN DESCRIPTION:
GUM BRANCH 12.5
END DESCRIPTION:
XS GIS Cut Line= 3
      3797350.98     10166040.57      3796426.31     10167024.18
      3795035.33     10168418.92
#Sta/Elev= 30
    3650  243.21  3666.6  242.76  3702.2  245.75  3765.7  244.85  3801.3   240.9
  3840.6  240.79  3871.7  239.55  3893.2  232.51  3915.1  229.64  3956.7  223.77
  3999.2  222.37  4045.3  217.16  4062.7  216.24  4084.1  211.04  4126.6  205.93
  4190.7  200.96  4191.2  200.46  4217.9  200.96  5915.9     201  5930.1  203.05
  5993.7  203.59  6029.1  206.33  6092.7  208.35  6163.4  209.53  6198.8  212.68
  6348.9  212.15  6494.3  215.96  6693.8  223.05  6916.1  230.32  6969.8  232.78
#Mann= 11 ,-1 , 0
    3650     .12       0  3840.6     .05       0  3915.1     .12       0
  4045.3     .05       0  4190.7     .03       0  4217.9     .05       0
  6092.7     .12       0  6348.9     .05       0  6494.3     .12       0
  6693.8     .05       0  6916.1     .12       0
Bank Sta=4126.6,6029.1
XS Rating Curve= 0 ,0
Exp/Cntr=0.3,0.1

Type RM Length L Ch R = 1 ,5500    ,500,500,500
BEGIN DESCRIPTION:
GUM BRANCH 11.5
END DESCRIPTION:
XS GIS Cut Line= 3
      3797300.89     10165969.47      3796193.73     10166581.57
      3795021.91     10168403.57
#Sta/Elev= 30
  3734.9  242.13  3855.1  244.53  3914.7  243.65  3934.7  240.69    3980  235.45
  3989.8  231.24  4033.8  229.78  4049.9  227.25  4065.4  224.04  4092.6  223.27
  4172.6  212.15  4267.5  205.93  4307.5     201    4308   200.5  4334.7     201
  5956.6     201    6010     201  6081.4  204.92  6126.1  203.24  6183.6  205.85
  6195.6  206.48  6377.8  213.92  6491.9   214.9  6504.1     215  6582.8  215.25
  6791.8   221.8  6849.3  221.15  6948.1  225.22  7145.6  231.41  7166.3  232.44
#Mann= 15 ,-1 , 0
  3734.9     .12       0  3934.7     .05       0  4049.9     .12       0
  4065.4     .05       0  4307.5     .03       0  4334.7     .05       0
  5956.6     .12       0    6010     .05       0  6195.6     .12       0
  6377.8     .05       0  6491.9     .12       0  6504.1     .05       0
  6582.8     .12       0  6948.1     .05       0  7145.6     .12       0
#XS Ineff= 2 , 0
       0                  6081.4       0  204.92
Permanent Ineff=
       F       F
Bank Sta=4267.5,6183.6
XS Rating Curve= 0 ,0
Exp/Cntr=0.3,0.1

Type RM Length L Ch R = 1 ,5000    ,500,500,500
BEGIN DESCRIPTION:
GUM BRANCH 10.5
END DESCRIPTION:
XS GIS Cut Line= 3
      3796917.82      10165161.1      3795961.14     10166138.95
      3794988.41     10168392.04
#Sta/Elev= 30
    3632  236.92    3740  236.56  3780.5  236.25  3936.1  227.88  4027.9  218.04
  4091.7  216.85  4134.1  211.17  4171.1  208.75  4197.7  206.59  4237.1  205.26
  4254.2  202.84  4360.7     201  4361.2   200.5  4388.1     201  6106.4  201.04
  6113.3  203.16  6159.3  203.55  6200.4  206.39  6329.7  211.39  6459.4  212.13
  6557.2  213.36  6625.2     212    6737  214.17  6863.6  216.11  6973.8  220.08
  7239.1   225.2  7263.6  226.15  7368.9   229.3    7454  232.27  7454.1  232.27
#Mann= 15 ,-1 , 0
    3632     .12       0    3740     .05       0  4171.1     .12       0
  4237.1     .05       0  4360.7     .03       0  4388.1     .05       0
  6106.4     .12       0  6329.7     .05       0  6459.4     .12       0
    6737     .05       0  6863.6     .12       0  7239.1     .05       0
  7263.6     .12       0  7368.9     .05       0    7454     .12       0
#XS Ineff= 2 , 0
       0  4233.1  206.05               0
Permanent Ineff=
       F       F
Bank Sta=4197.7,6200.4
XS Rating Curve= 0 ,0
Exp/Cntr=0.3,0.1

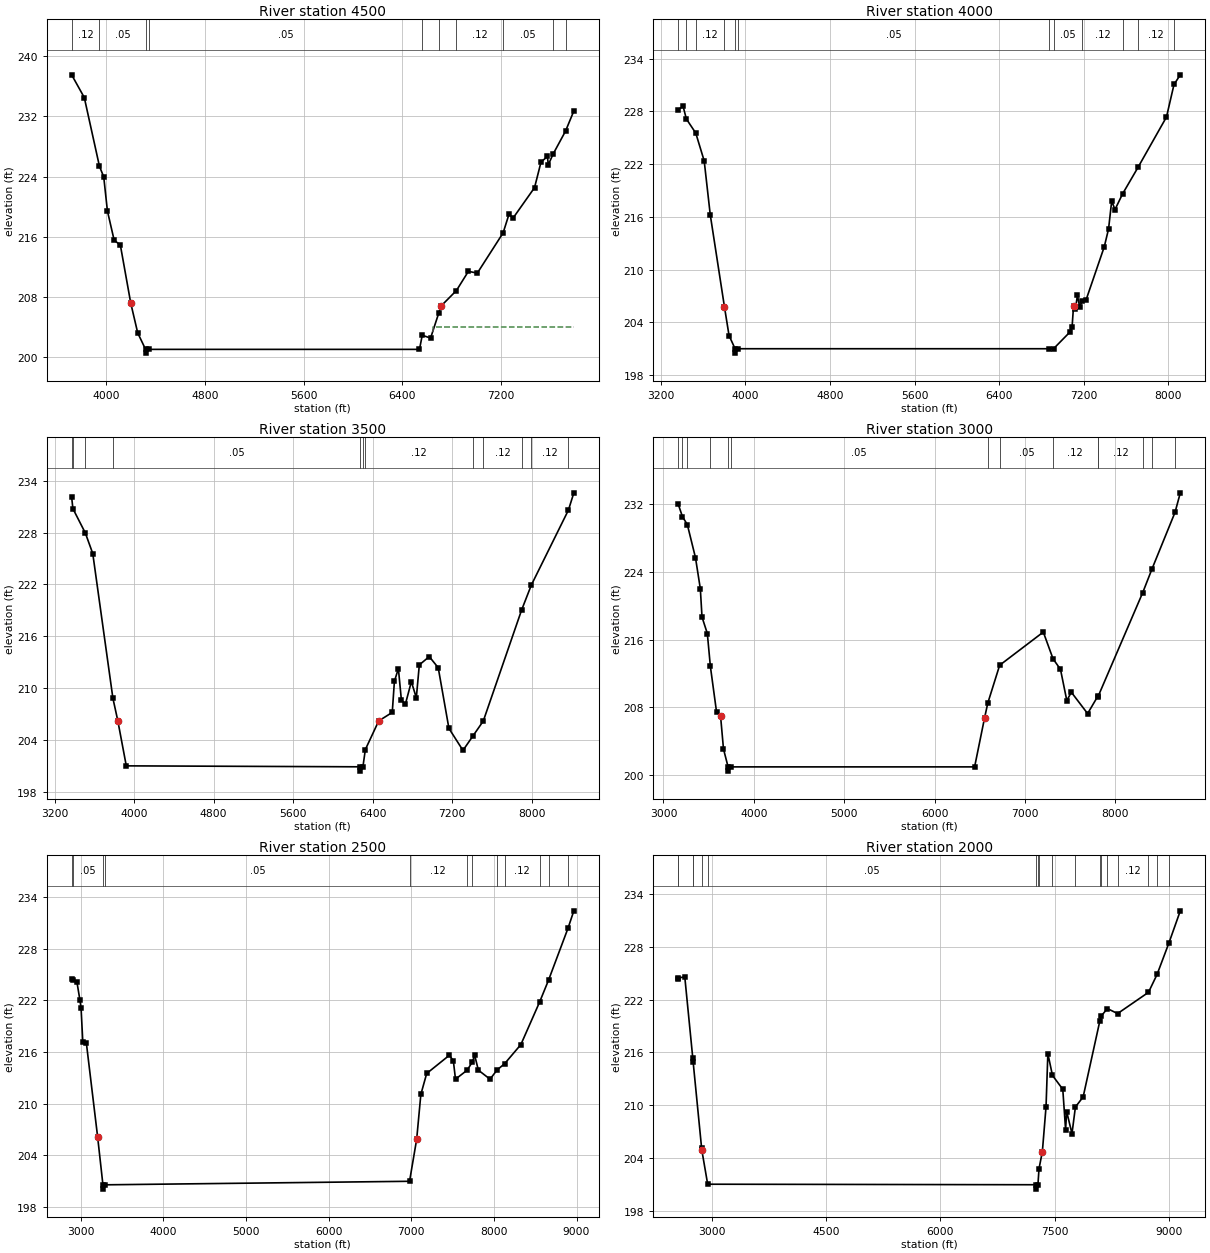
Type RM Length L Ch R = 1 ,4500    ,500,500,500
BEGIN DESCRIPTION:
GUM BRANCH 9.5
END DESCRIPTION:
XS GIS Cut Line= 3
      3796878.03     10165132.53      3795728.56     10165696.34
      3794955.98     10168376.72
#Sta/Elev= 30
  3719.7  237.53  3822.1  234.51  3945.3  225.34  3979.6  223.96  4009.5  219.42
    4064  215.53  4114.5  214.87  4198.8  207.14  4255.1  203.19  4318.7     201
  4319.2   200.5  4346.3     201  6538.5     201    6561  202.88  6628.4   202.5
  6695.8  205.88  6711.7  206.74    6838  208.83  6934.8  211.38  7007.4  211.15
  7216.3   216.5  7263.8  218.97  7297.5  218.48    7471  222.52  7523.4  225.92
  7575.5  226.67  7582.4  225.55  7620.9  226.97  7722.1  230.04  7789.5  232.72
#Mann= 10 ,-1 , 0
  3719.7     .12       0  3945.3     .05       0  4318.7     .03       0
  4346.3     .05       0    6561     .12       0  6695.8     .05       0
    6838     .12       0  7216.3     .05       0  7620.9     .12       0
  7722.1     .05       0
#XS Ineff= 2 , 0
       0                  6644.7       0  203.92
Permanent Ineff=
       F       F
Bank Sta=4198.8,6711.7
XS Rating Curve= 0 ,0
Exp/Cntr=0.3,0.1

Type RM Length L Ch R = 1 ,4000    ,500,500,500
BEGIN DESCRIPTION:
GUM BRANCH 8.5
END DESCRIPTION:
XS GIS Cut Line= 3
      3796461.36     10164007.54      3795445.84     10165291.61
       3794912.4     10168359.98
#Sta/Elev= 30
  3362.9  228.22  3410.4  228.57  3440.8  227.15  3529.9  225.54  3609.6  222.38
  3666.9  216.25  3801.1  205.78  3844.8   202.5  3901.8     201  3902.3   200.5
  3929.4     201  6874.3     201    6915     201  7070.1   202.9  7090.4  203.46
 7104.12  205.84  7122.6  205.54  7141.1  207.09  7161.4  205.79  7188.3  206.46
  7222.3  206.54  7394.9   212.6  7435.5  214.63  7465.2  217.81  7496.4  216.84
  7568.1  218.62  7715.2  221.66  7983.6  227.37  8054.7  231.07  8114.4  232.17
#Mann= 12 ,-1 , 0
  3362.9     .12       0  3440.8     .05       0  3529.9     .12       0
  3801.1     .05       0  3901.8     .03       0  3929.4     .05       0
  6874.3     .12       0    6915     .05       0  7188.3     .12       0
  7568.1     .05       0  7715.2     .12       0  8054.7     .05       0
Bank Sta=3801.1,7104.12
XS Rating Curve= 0 ,0
Exp/Cntr=0.3,0.1

Type RM Length L Ch R = 1 ,3500    ,500,500,500
BEGIN DESCRIPTION:
GUM BRANCH 7.5
END DESCRIPTION:
XS GIS Cut Line= 3
      3796426.66     10163972.79      3795105.38     10164925.43
      3794864.66     10168342.56
#Sta/Elev= 30
  3371.1   232.1  3383.7  230.78  3508.8  227.96  3583.6  225.58  3786.4  208.82
  3835.2  206.25  3921.1     201    6275  200.89  6275.5  200.39  6302.7  200.89
  6327.2  202.89  6461.6   206.2    6598  207.19  6619.6  210.79  6659.7  212.26
  6689.8  208.63  6729.9  208.13  6790.1  210.75  6840.2  208.88  6870.3  212.69
  6970.5  213.65  7060.7  212.36  7168.3  205.34  7309.6  202.79  7408.1  204.43
  7514.1  206.19  7899.5  219.03  7997.7  221.93  8371.4  230.62  8425.6  232.61
#Mann= 12 ,-1 , 0
  3371.1     .12       0  3383.7     .05       0  3508.8     .12       0
  3786.4     .05       0    6275     .03       0  6302.7     .05       0
  6327.2     .12       0  7408.1     .05       0  7514.1     .12       0
  7899.5     .05       0  7997.7     .12       0  8371.4     .05       0
#XS Ineff= 2 , 0
       0                  6659.7       0  212.26
Permanent Ineff=
       F       F
Bank Sta=3835.2,6461.6
XS Rating Curve= 0 ,0
Exp/Cntr=0.3,0.1

Type RM Length L Ch R = 1 ,3000    ,500,500,500
BEGIN DESCRIPTION:
GUM BRANCH 6.5
END DESCRIPTION:
XS GIS Cut Line= 3
      3796412.78     10163924.18       3794711.2     10164618.52
      3794827.36     10168336.41
#Sta/Elev= 30
  3162.2     232  3210.2  230.49  3264.1  229.56  3354.5  225.65    3408     222
  3426.6  218.66  3485.5  216.72    3519  212.86    3587  207.51    3632  206.98
  3664.4   203.1  3715.3     201  3715.8   200.5    3743     201  6443.3     201
  6553.3  206.76    6589  208.51  6720.5  212.98  7203.6  216.89  7311.2  213.74
  7393.7  212.49  7463.7  208.82  7513.8   209.8  7693.9  207.28  7803.5  209.27
  7811.6  209.34  8304.2  221.55  8406.4  224.33  8661.6  231.01  8719.7   233.3
#Mann= 14 ,-1 , 0
  3162.2     .12       0  3210.2     .05       0  3264.1     .12       0
    3519     .05       0  3715.3     .03       0    3743     .05       0
    6589     .12       0  6720.5     .05       0  7311.2     .12       0
  7803.5     .05       0  7811.6     .12       0  8304.2     .05       0
  8406.4     .12       0  8661.6     .05       0
Bank Sta=3632,6553.3
XS Rating Curve= 0 ,0
Exp/Cntr=0.3,0.1

Type RM Length L Ch R = 1 ,2500    ,500,500,500
BEGIN DESCRIPTION:
GUM BRANCH 5.5
END DESCRIPTION:
XS GIS Cut Line= 3
      3795982.24     10163167.22      3794274.17     10164402.44
      3794788.26     10168336.39
#Sta/Elev= 30
  2892.1  224.43  2905.7  224.33  2955.7  224.14  2991.3  222.08    3006  221.11
  3026.9  217.17  3070.3  217.03    3206  206.18  3270.5  200.59    3271  200.09
  3298.3  200.59  6979.9     201  7066.1  205.88  7116.5  211.08  7187.1  213.51
  7461.9  215.63  7509.8  214.97  7535.8  212.85  7675.9  213.89  7739.9  214.84
  7767.5  215.63  7812.3   213.9  7953.5  212.85  8038.8  213.92  8129.3  214.64
  8326.7  216.87  8555.3  221.85  8662.3  224.37  8897.9   230.4  8967.4  232.39
#Mann= 12 ,-1 , 0
  2892.1     .12       0  2905.7     .05       0  3270.5     .03       0
  3298.3     .05       0  6979.9     .12       0  7675.9     .05       0
  7739.9     .12       0  8038.8     .05       0  8129.3     .12       0
  8555.3     .05       0  8662.3     .12       0  8897.9     .05       0
Bank Sta=3206,7066.1
XS Rating Curve= 0 ,0
Exp/Cntr=0.3,0.1

Type RM Length L Ch R = 1 ,2000    ,559,559,559
BEGIN DESCRIPTION:
GUM BRANCH 4.5
END DESCRIPTION:
XS GIS Cut Line= 3
       3795923.5     10163136.23      3793782.99     10164308.94
      3794755.52     10168339.98
#Sta/Elev= 30
  2559.3  224.41  2564.1  224.49  2646.7  224.61  2752.1  215.32  2755.8  214.97
  2867.1  205.14  2869.5  204.92    2947     201  7251.4  200.94  7251.9  200.44
  7279.2  200.94  7293.2  202.76  7337.3  204.72  7385.4  209.82  7409.3  215.87
  7469.7  213.39  7605.1  211.81  7641.9  207.22  7656.2  209.27  7725.7  206.76
  7770.8  209.79  7872.2  210.94  8092.1  219.63  8107.2  220.13  8190.4     221
  8323.9  220.43  8729.2  222.85  8842.1  224.89  8996.9  228.46  9146.7  232.13
#Mann= 18 ,-1 , 0
  2559.3     .12       0  2564.1     .05       0  2752.1    .075       0
  2755.8     .05       0  2867.1    .075       0    2947     .05       0
  7251.4     .03       0  7279.2     .05       0  7293.2     .12       0
  7469.7     .05       0  7770.8     .12       0  8092.1     .05       0
  8107.2     .12       0  8190.4     .05       0  8323.9     .12       0
  8729.2     .05       0  8842.1     .12       0  8996.9     .05       0
Bank Sta=2869.5,7337.3
XS Rating Curve= 0 ,0
Exp/Cntr=0.3,0.1

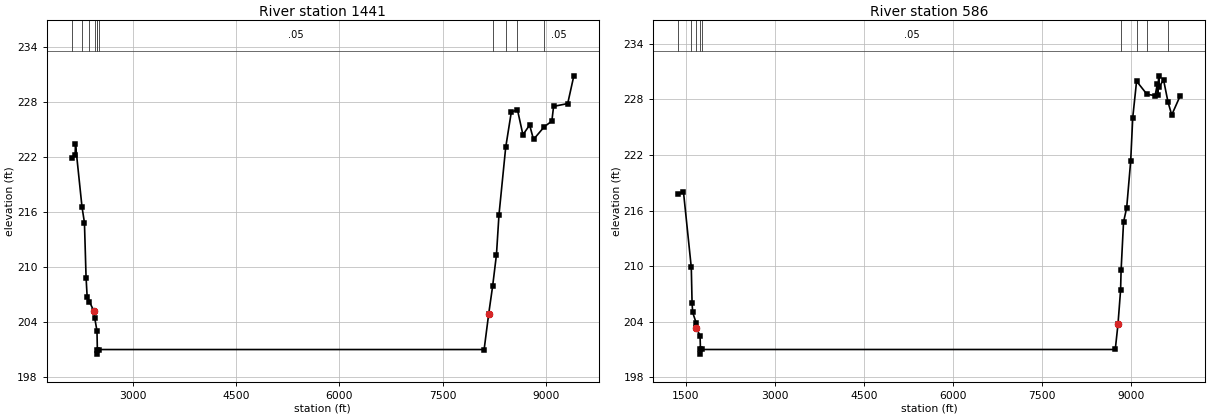
Type RM Length L Ch R = 1 ,1441    ,855,855,855
BEGIN DESCRIPTION:
GUM BRANCH 3.5
END DESCRIPTION:
XS GIS Cut Line= 3
      3795895.73     10163095.43      3793233.67     10164204.37
      3794721.22     10168344.86
#Sta/Elev= 30
  2116.2  221.86  2166.3  222.19  2171.7  223.36  2266.2  216.54  2301.7  214.82
  2325.5  208.81  2341.4  206.69  2374.8  206.21  2438.9  205.17  2451.3  204.41
  2483.5  203.03  2489.1     201  2489.6   200.5  2517.3     201  8098.5     201
  8165.3  204.92  8222.1  207.92  8277.5  211.35  8313.6  215.65  8411.2  223.01
  8492.6  226.86  8581.7  227.12  8661.1  224.39  8758.5  225.45  8814.7  223.88
  8970.4  225.26  9080.6  225.88    9106  227.48  9310.5  227.79  9399.6  230.81
#Mann= 11 ,-1 , 0
  2116.2     .05       0  2266.2    .075       0  2374.8     .05       0
  2451.3    .075       0  2483.5     .05       0  2489.1     .03       0
  2517.3     .05       0  8222.1     .12       0  8411.2     .05       0
  8581.7     .12       0  8970.4     .05       0
Bank Sta=2438.9,8165.3
XS Rating Curve= 0 ,0
Exp/Cntr=0.3,0.1

Type RM Length L Ch R = 1 ,586     ,0,0,0
BEGIN DESCRIPTION:
GUM BRANCH 2.5
END DESCRIPTION:
XS GIS Cut Line= 4
      3795874.23     10163044.44      3792567.83      10163963.7
      3792411.48     10164082.38      3794683.68     10168348.28
#Sta/Elev= 30
  1371.9  217.78  1461.6  218.05  1593.8  209.86    1607  206.02  1617.2     205
  1675.7  203.88  1680.7  203.36  1741.8  202.44  1748.4     201  1748.9   200.5
  1776.7     201  8737.4     201  8782.8   203.7  8827.1  207.41  8835.7  209.56
  8876.7  214.75  8930.1  216.32  8997.2  221.35    9032  226.05  9096.6  229.97
  9272.2  228.55  9408.8  228.42  9447.1  229.69  9452.8  228.46  9469.1  230.55
  9474.7  229.34  9551.3  230.11  9626.4  227.71  9689.2  226.33  9833.3  228.42
#Mann= 9 ,-1 , 0
  1371.9     .05       0  1593.8    .075       0  1675.7     .05       0
  1748.4     .03       0  1776.7     .05       0  8835.7     .12       0
  9096.6     .05       0  9272.2     .12       0  9626.4     .05       0
Bank Sta=1680.7,8782.8
XS Rating Curve= 0 ,0
Exp/Cntr=0.3,0.1

Chan Stop Cuts=-1
Use User Specified Reach Order=0
Composite Channel Slope=5