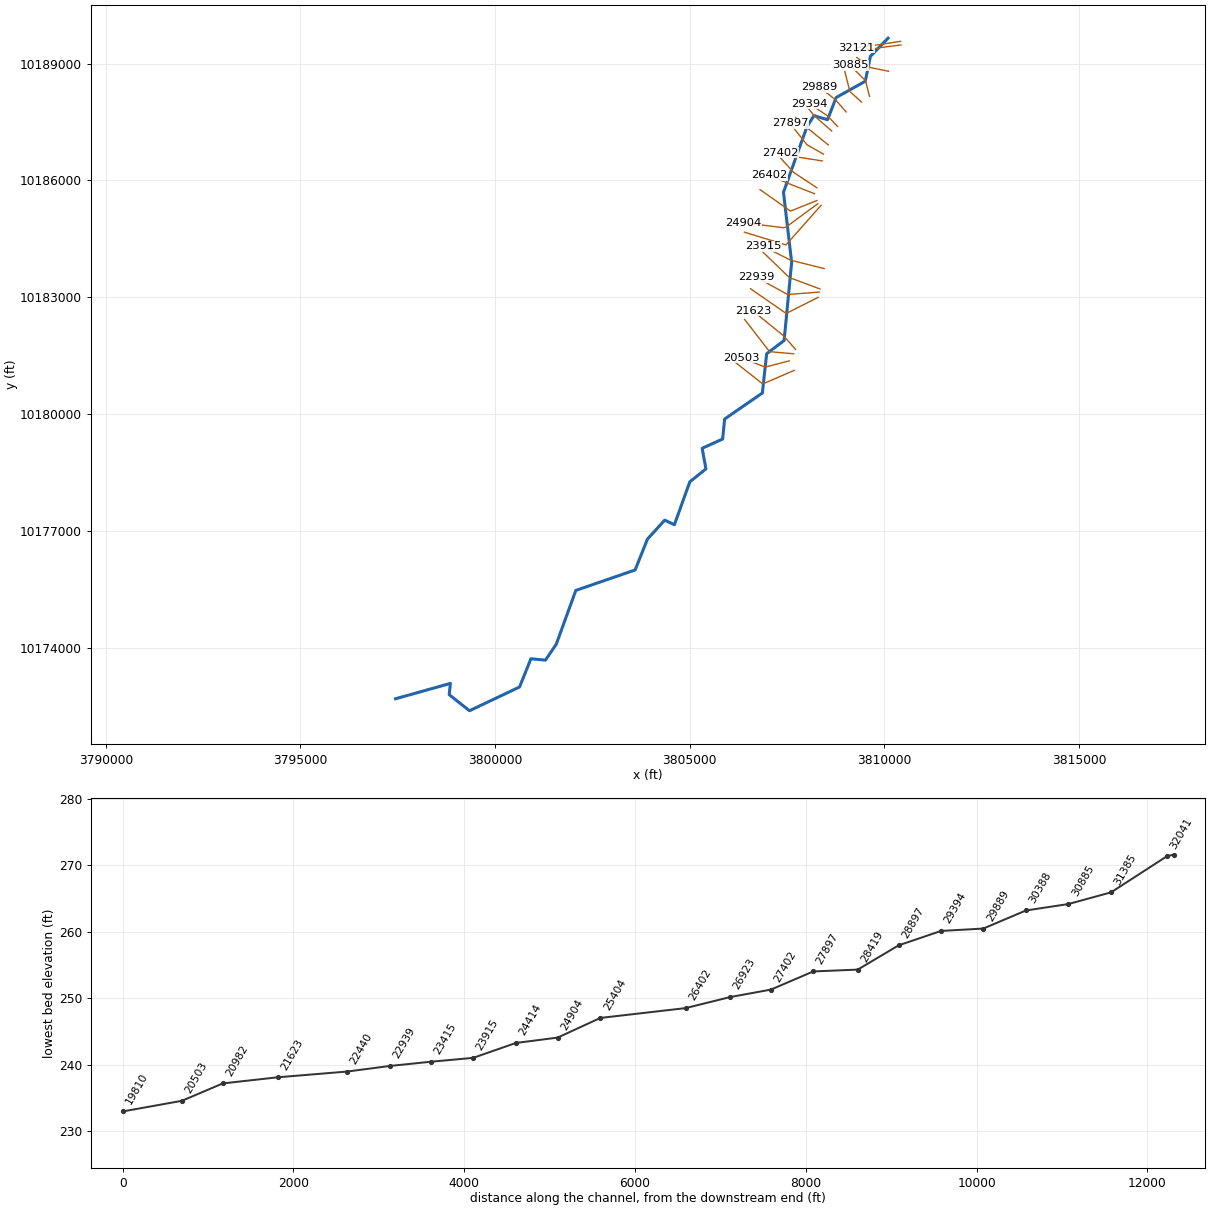
--- HOSTETTER CREEK.prj (project) ---

Proj Title=HOSTETTER CREEK Base Level Engineering
Current Plan=p01
Default Exp/Contr=0.3,0.1
English Units
Geom File=g01
Flow File=f01
Flow File=f02
Plan File=p01
Y Axis Title=Elevation
X Axis Title(PF)=Main Channel Distance
X Axis Title(XS)=Station
BEGIN DESCRIPTION:
HOSTETTER CREEK
END DESCRIPTION:
DSS Export Rating Curves= 0
DSS Export Rating Curve Sorted= 0
DSS Export Volume Flow Curves= 0
DXF OffsetX= 0
DXF OffsetY= 0
DXF ScaleX= 1
DXF ScaleY= 10

--- HOSTETTER CREEK.p01 (plan) ---

Plan Title=Multiple Run
Short Identifier=Multiple
Geom File=g01
Flow File=f01
Subcritical Flow
K Sum by GR= 0
Std Step Tol= 0.01
Critical Tol= 0.01
Num of Std Step Trials= 20
Max Error Tol= 0.3
Flow Tol Ratio= 0.001
Split Flow NTrial= 30
Split Flow Tol= 0.02
Split Flow Ratio= 0.02
Log Output Level= 0
Friction Slope Method= 1
Unsteady Friction Slope Method= 2
Unsteady Bridges Friction Slope Method= 1
Parabolic Critical Depth
Global Vel Dist=  1 , 1 , 1
Global Log Level= 0
CheckData=True
Encroach Param= -1, 0, 0, 0
BEGIN DESCRIPTION:
Multiple Run
END DESCRIPTION:

--- HOSTETTER CREEK.f01 (steady flow) ---

Flow Title=Multiple
Program Version=4.10
Number of Profiles= 7
Profile Names=10-year,25-year,50-year,1pct_min,100-year,1pct_plu,500-year
River Rch & RM=HOSTETTER CREEK,Reach-1         ,32121
     811    1112    1516     680    2053    6200    3889
River Rch & RM=HOSTETTER CREEK,Reach-1         ,31385
    1007    1380    1881     841    2540    7671    4792
River Rch & RM=HOSTETTER CREEK,Reach-1         ,23915
    1439    2015    2782    1260    3804   11488    7358
River Rch & RM=HOSTETTER CREEK,Reach-1         ,21623
    1806    2562    3571    1631    4926   14876    9701
River Rch & RM=HOSTETTER CREEK,Reach-1         ,18575
    2142    3061    4286    1966    5937   17929   11789
River Rch & RM=HOSTETTER CREEK,Reach-1         ,17145
    2112    3006    4198    1919    5795   17501   11438
River Rch & RM=HOSTETTER CREEK,Reach-1         ,14439
    2320    3309    4626    2118    6395   19313   12645
River Rch & RM=HOSTETTER CREEK,Reach-1         ,9921
    2400    3415    4767    2177    6573   19850   12941
River Rch & RM=HOSTETTER CREEK,Reach-1         ,6880
    2618    3746    5250    2406    7267   21946   14417
River Rch & RM=HOSTETTER CREEK,Reach-1         ,4911
    2645    3777    5288    2421    7310   22076   14463
Boundary for River Rch & Prof#=HOSTETTER CREEK,Reach-1         , 1
Up Type= 0
Dn Type= 3
Dn Slope=0.005
Boundary for River Rch & Prof#=HOSTETTER CREEK,Reach-1         , 2
Up Type= 0
Dn Type= 3
Dn Slope=0.005
Boundary for River Rch & Prof#=HOSTETTER CREEK,Reach-1         , 3
Up Type= 0
Dn Type= 3
Dn Slope=0.005
Boundary for River Rch & Prof#=HOSTETTER CREEK,Reach-1         , 4
Up Type= 0
Dn Type= 3
Dn Slope=0.005
Boundary for River Rch & Prof#=HOSTETTER CREEK,Reach-1         , 5
Up Type= 0
Dn Type= 3
Dn Slope=0.005
Boundary for River Rch & Prof#=HOSTETTER CREEK,Reach-1         , 6
Up Type= 0
Dn Type= 3
Dn Slope=0.005
Boundary for River Rch & Prof#=HOSTETTER CREEK,Reach-1         , 7
Up Type= 0
Dn Type= 3
Dn Slope=0.005
DSS Import GetInterval= 0
DSS Import GetPeak= 0
DSS Import FillOption= 0

--- HOSTETTER CREEK.f02 (steady flow) ---

Flow Title=Orig_BLE_Flow
Program Version=4.10
Number of Profiles= 7
Profile Names=10-year,25-year,50-year,1pct_min,100-year,1pct_plu,500-year
River Rch & RM=HOSTETTER CREEK,Reach-1         ,32121
     811    1090    1318     523    1579    4767    2261
River Rch & RM=HOSTETTER CREEK,Reach-1         ,31385
    1007    1353    1636     647    1954    5901    2786
River Rch & RM=HOSTETTER CREEK,Reach-1         ,23915
    1439    1975    2419     969    2926    8836    4278
River Rch & RM=HOSTETTER CREEK,Reach-1         ,21623
    1806    2512    3105    1255    3789   11443    5640
River Rch & RM=HOSTETTER CREEK,Reach-1         ,18575
    2142    3001    3727    1512    4567   13791    6854
River Rch & RM=HOSTETTER CREEK,Reach-1         ,17145
    2112    2947    3650    1476    4458   13463    6650
River Rch & RM=HOSTETTER CREEK,Reach-1         ,14439
    2320    3244    4023    1629    4919   14855    7352
River Rch & RM=HOSTETTER CREEK,Reach-1         ,9921
    2400    3348    4145    1674    5056   15270    7524
River Rch & RM=HOSTETTER CREEK,Reach-1         ,6880
    2618    3673    4565    1851    5590   16881    8382
River Rch & RM=HOSTETTER CREEK,Reach-1         ,4911
    2645    3703    4598    1862    5623   16981    8409
Boundary for River Rch & Prof#=HOSTETTER CREEK,Reach-1         , 1
Up Type= 0
Dn Type= 3
Dn Slope=0.005
Boundary for River Rch & Prof#=HOSTETTER CREEK,Reach-1         , 2
Up Type= 0
Dn Type= 3
Dn Slope=0.005
Boundary for River Rch & Prof#=HOSTETTER CREEK,Reach-1         , 3
Up Type= 0
Dn Type= 3
Dn Slope=0.005
Boundary for River Rch & Prof#=HOSTETTER CREEK,Reach-1         , 4
Up Type= 0
Dn Type= 3
Dn Slope=0.005
Boundary for River Rch & Prof#=HOSTETTER CREEK,Reach-1         , 5
Up Type= 0
Dn Type= 3
Dn Slope=0.005
Boundary for River Rch & Prof#=HOSTETTER CREEK,Reach-1         , 6
Up Type= 0
Dn Type= 3
Dn Slope=0.005
Boundary for River Rch & Prof#=HOSTETTER CREEK,Reach-1         , 7
Up Type= 0
Dn Type= 3
Dn Slope=0.005
DSS Import GetInterval= 0
DSS Import GetPeak= 0
DSS Import FillOption= 0

--- HOSTETTER CREEK.g01 (geometry) ---

Geom Title=Existing Conditions
Program Version=4.10

River Reach=HOSTETTER CREEK ,Reach-1
Reach XY= 30
      3810094.82     10189654.17      3809641.27     10189188.51
      3809510.33     10188548.86      3808760.87     10188130.02
      3808540.61     10187560.38      3808190.44     10187665.68
      3808010.31     10187377.01      3807408.41     10185697.95
      3807618.51      10183896.7      3807424.83     10181889.96
      3806976.23     10181549.85      3806866.28     10180541.97
      3805896.88      10179873.1      3805845.57       10179360.
      3805319.64     10179121.77      3805416.76     10178592.17
      3805002.62     10178260.49      3804606.79     10177159.15
      3804357.57     10177276.43       3803914.1     10176788.98
      3803598.23     10175996.84        3802074.     10175471.59
      3801572.15     10174091.37       3801294.8     10173680.54
      3800920.45     10173716.07      3800629.12     10172991.08
      3799342.79     10172381.23      3798821.55     10172794.11
      3798852.71     10173083.64      3797443.41     10172688.63

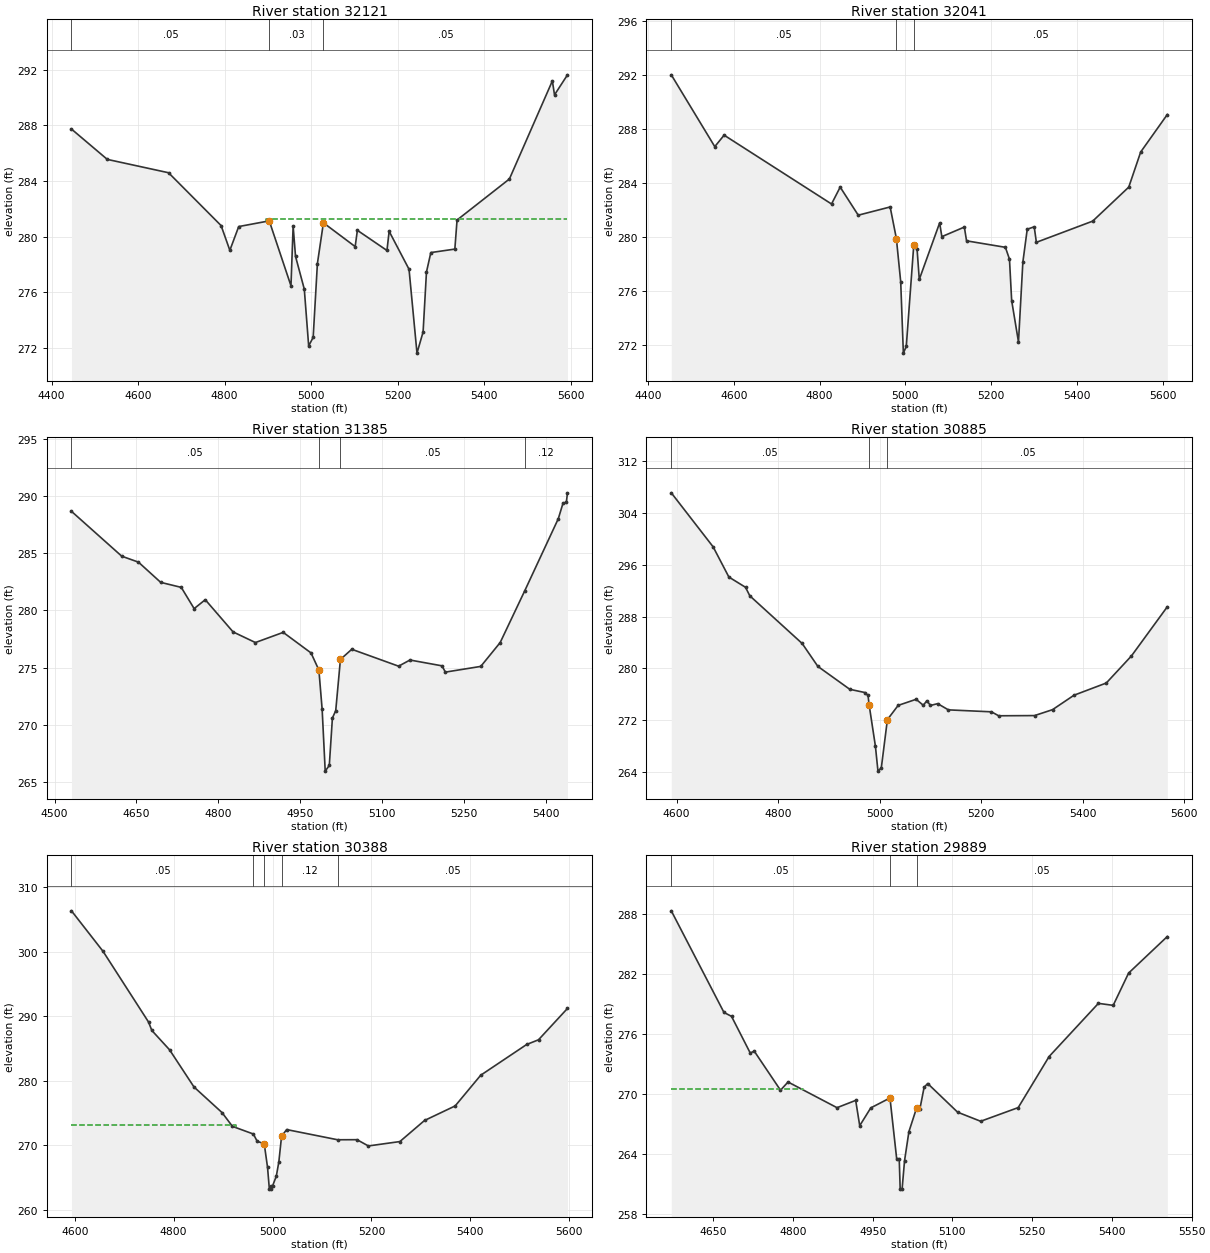
Type RM Length L Ch R = 1 ,32121   ,80,80,80
BEGIN DESCRIPTION:
HOSTETTER CREEK 58.0
END DESCRIPTION:
XS GIS Cut Line= 3
      3810419.63     10189574.69       3809872.3     10189489.64
      3809284.71     10189411.94
#Sta/Elev= 30
  4446.1  287.73  4528.9  285.55  4670.5  284.59    4792  280.79  4812.2  279.01
  4832.7  280.72  4903.3  281.13  4953.5  276.46  4958.5  280.75    4964  278.58
  4984.3  276.22  4994.4  272.14  5004.8  272.75  5014.6  278.06  5028.5  280.99
  5101.9  279.28    5107  280.45  5175.4     279  5180.4  280.38  5226.4  277.65
  5244.8  271.62  5258.9  273.14  5266.7  277.45  5276.8  278.85  5332.3   279.1
  5337.4  281.19  5458.4  284.14  5557.7  291.19  5562.7  290.19  5592.7  291.63
#Mann= 3 , 0 , 0
  4446.1     .05       0  4903.3     .03       0  5028.5     .05       0
#XS Ineff= 1 ,-1
  4895.6  4751.5  281.27
Permanent Ineff=
       T
Bank Sta=4903.3,5028.5
XS Rating Curve= 0 ,0
Exp/Cntr=0.3,0.1

Type RM Length L Ch R = 1 ,32041   ,656,656,656
BEGIN DESCRIPTION:
HOSTETTER CREEK 57.0
END DESCRIPTION:
XS GIS Cut Line= 3
      3810428.38     10189481.38      3809887.06      10189411.6
      3809286.82     10189299.08
#Sta/Elev= 30
  4454.2     292  4555.6  286.68  4577.4  287.53  4827.8  282.43    4848  283.68
  4890.1   281.6  4964.5  282.21    4979  279.87  4989.1  276.67  4995.3  271.38
  5002.1  271.88  5019.5  279.36  5027.3  279.07  5032.4  276.84  5079.9  281.03
    5085  280.01  5137.5  280.72  5142.6   279.7  5233.2  279.22  5242.7  278.34
  5247.8  275.27  5263.7  272.21  5273.9  278.12  5284.1  280.56  5300.4  280.74
  5305.4  279.59  5436.7  281.16  5520.8  283.68  5548.6  286.28  5610.7  289.06
#Mann= 3 ,-1 , 0
  4454.2     .05       0    4979     .03       0  5019.5     .05       0
Bank Sta=4979,5019.5
XS Rating Curve= 0 ,0
Exp/Cntr=0.3,0.1

Type RM Length L Ch R = 1 ,31385   ,500,500,500
BEGIN DESCRIPTION:
HOSTETTER CREEK 56.0
END DESCRIPTION:
XS GIS Cut Line= 3
      3810108.17     10188805.33      3809648.49     10188899.39
      3809292.43     10189158.23
#Sta/Elev= 30
  4530.8  288.68    4623  284.75  4653.6  284.23  4694.4  282.46  4732.1  282.02
  4755.7  280.16  4776.1  280.94  4827.1  278.12    4868  277.19    4919  278.08
    4970  276.28  4984.4  274.78  4990.4  271.33    4996  265.93  5003.5  266.43
  5009.2  270.58  5015.3  271.23  5023.9  275.71  5044.7   276.6  5130.5  275.12
  5151.4  275.66  5210.1  275.15  5216.3   274.6  5281.2   275.1  5316.8  277.19
  5361.9  281.73  5423.4  288.04  5431.9  289.38  5438.1  289.49  5440.2   290.3
#Mann= 4 ,-1 , 0
  4530.8     .05       0  4984.4     .03       0  5023.9     .05       0
  5361.9     .12       0
#XS Ineff= 2 , 0
       0    4919  278.08               0
Permanent Ineff=
       F       T
Bank Sta=4984.4,5023.9
XS Rating Curve= 0 ,0
Exp/Cntr=0.3,0.1

Type RM Length L Ch R = 1 ,30885   ,497,497,497
BEGIN DESCRIPTION:
HOSTETTER CREEK 55.0
END DESCRIPTION:
XS GIS Cut Line= 3
      3809617.86     10188161.04      3809517.43     10188559.17
      3809117.88     10188961.05
#Sta/Elev= 30
  4589.4  307.06  4671.9  298.73  4702.9  294.08  4735.7   292.5  4744.1  291.19
  4847.3  283.84  4878.2  280.31  4941.1  276.78    4971  276.28    4977  275.83
 4979.36   274.3  4991.6  268.01  4996.6  264.17  5003.2  264.67  5015.2  272.11
  5036.4   274.3  5071.8  275.24  5085.9  274.32    5093  275.02  5100.1  274.29
  5114.2  274.57  5135.4  273.61  5220.2  273.31  5234.4   272.7  5305.1  272.73
  5340.5  273.64  5382.9  275.87  5446.5  277.75    5496  281.92  5566.7   289.5
#Mann= 3 , 0 , 0
  4589.4     .05       0 4979.36     .03       0  5015.2     .05       0
Bank Sta=4979.36,5015.2
XS Rating Curve= 0 ,0
Exp/Cntr=0.3,0.1

Type RM Length L Ch R = 1 ,30388   ,499,499,499
BEGIN DESCRIPTION:
HOSTETTER CREEK 54.0
END DESCRIPTION:
XS GIS Cut Line= 3
      3809417.83     10188011.09      3809115.94     10188283.47
      3808967.85     10188861.09
#Sta/Elev= 30
  4593.4  306.38  4657.3  300.09  4749.2  289.13  4755.9  287.82  4791.8  284.81
  4841.1  279.05  4897.9  275.07  4918.8  272.94  4961.2  271.75  4968.9  270.62
  4983.1  270.25  4989.8   266.6  4993.5   263.2  4997.1   263.2  4997.4   263.7
    5000   263.7  5007.6  265.22  5012.7  267.44  5018.2  271.41  5028.5  272.44
  5131.5  270.86  5170.7  270.87  5193.7   269.9  5257.4  270.58  5307.2  273.85
  5369.2  276.11  5420.8  280.87  5513.7  285.64  5537.7  286.37  5596.3  291.24
#Mann= 5 ,-1 , 0
  4593.4     .05       0  4961.2     .12       0  4983.1     .07       0
  5018.2     .12       0  5131.5     .05       0
#XS Ineff= 2 , 0
       0  4926.3  273.09               0
Permanent Ineff=
       F       F
Bank Sta=4983.1,5018.2
XS Rating Curve= 0 ,0
Exp/Cntr=0.3,0.1

Type RM Length L Ch R = 1 ,29889   ,495,495,495
BEGIN DESCRIPTION:
HOSTETTER CREEK 53.0
END DESCRIPTION:
XS GIS Cut Line= 3
      3809017.82     10187761.11      3808734.96     10188083.25
      3808335.08     10188390.36
#Sta/Elev= 30
  4571.3  288.33  4670.4  278.16  4684.6  277.77  4719.8   274.1  4727.3  274.29
  4776.7  270.38  4790.9   271.2    4883  268.63  4918.1  269.36  4925.7  266.83
  4946.5  268.61  4982.6   269.6  4995.2  263.52    5000  263.52  5001.8  260.48
  5005.4  260.48    5010  263.32  5018.2  266.23  5032.7  268.61    5039  268.54
  5046.8  270.67  5053.5  271.05  5109.8  268.18  5153.2  267.27  5223.8  268.64
  5281.9  273.75  5374.6  279.07  5402.4  278.87  5431.4   282.1  5504.2  285.76
#Mann= 3 , 0 , 0
  4571.3     .05       0  4982.6     .05       0  5032.7     .05       0
#XS Ineff= 2 , 0
       0  4819.4  270.45  5053.5       0  271.05
Permanent Ineff=
       F       F
Bank Sta=4982.6,5032.7
XS Rating Curve= 0 ,0
Exp/Cntr=0.3,0.1

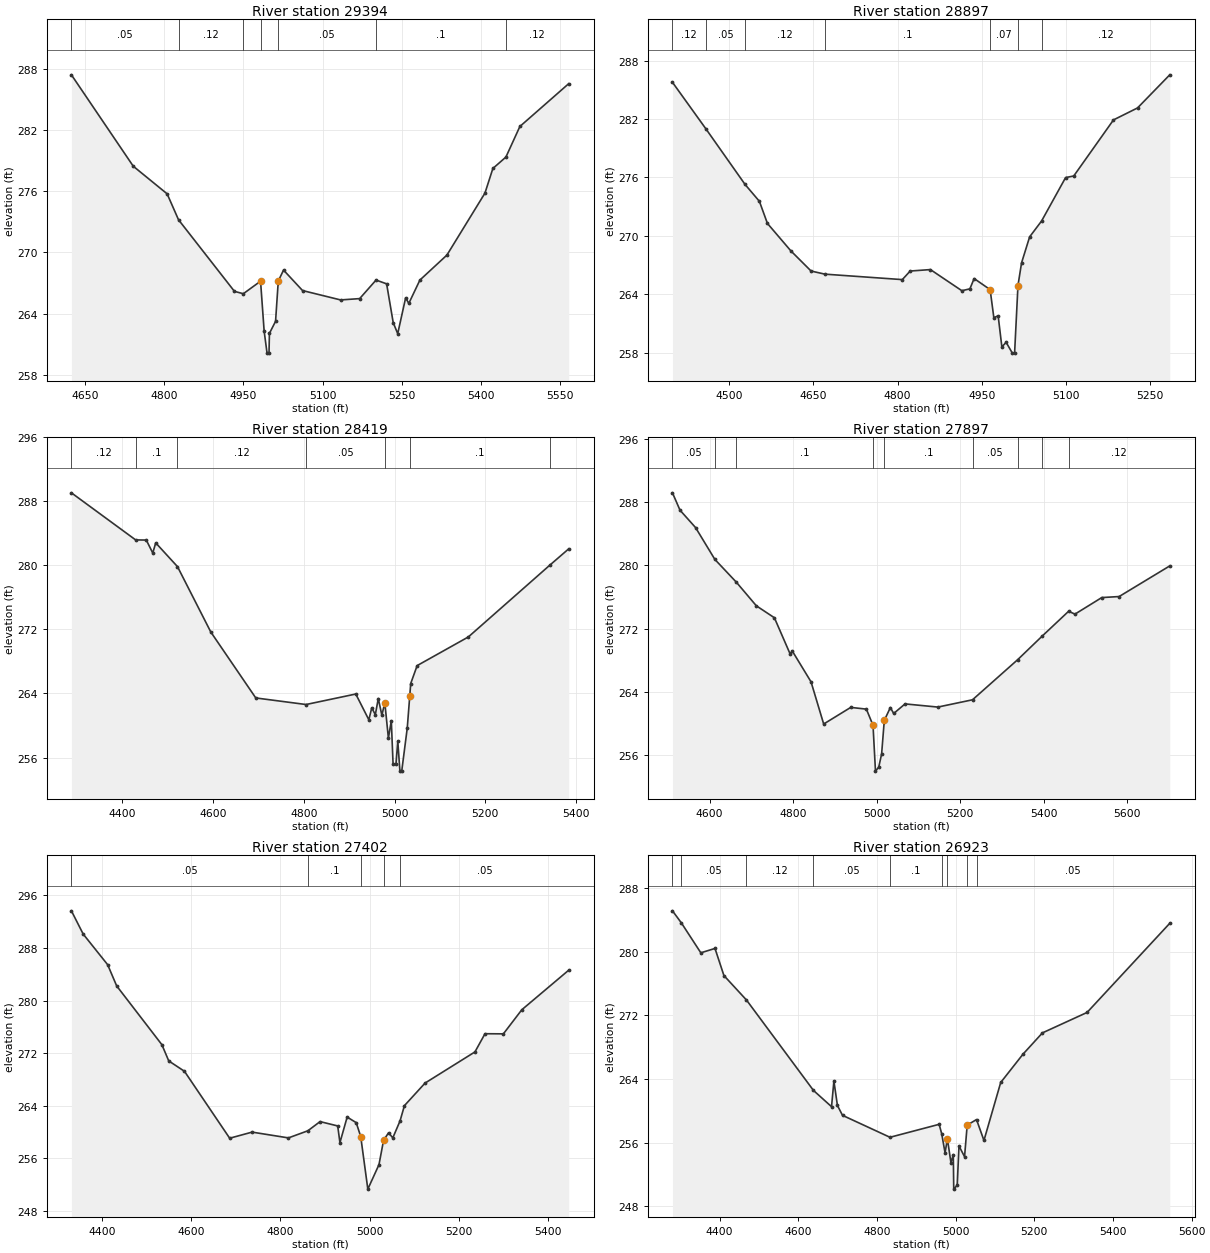
Type RM Length L Ch R = 1 ,29394   ,497,497,497
BEGIN DESCRIPTION:
HOSTETTER CREEK 52.0
END DESCRIPTION:
XS GIS Cut Line= 3
      3808798.13     10187385.44      3808542.13     10187659.88
      3808071.93     10187974.76
#Sta/Elev= 30
  4624.7  287.43  4741.8  278.46  4805.9  275.75  4827.4  273.21  4933.3  266.18
  4950.1  265.95  4982.7  267.18  4989.5  262.28    4995  260.12  4998.7  260.12
  4999.5  262.06  5011.1  263.24 5016.23  267.19  5026.2  268.27  5062.2  266.26
  5134.2  265.34  5170.3  265.47  5201.3  267.29  5221.3  266.92  5233.8  263.11
  5242.3  262.03  5257.3  265.55  5263.3     265  5284.3  267.29  5335.4  269.74
  5407.4  275.82  5422.4  278.24  5447.1  279.36  5473.5  282.36  5565.9  286.56
#Mann= 7 ,-1 , 0
  4624.7     .05       0  4827.4     .12       0  4950.1     .05       0
  4982.7     .05       0 5016.23     .05       0  5201.3      .1       0
  5447.1     .12       0
Bank Sta=4982.7,5016.23
XS Rating Curve= 0 ,0
Exp/Cntr=0.3,0.1

Type RM Length L Ch R = 1 ,28897   ,478,478,478
BEGIN DESCRIPTION:
HOSTETTER CREEK 51.0
END DESCRIPTION:
XS GIS Cut Line= 3
      3808647.23     10187272.27      3808193.11      10187666.4
      3808016.12     10187889.65
#Sta/Elev= 30
  4398.7  285.76  4458.3  280.98  4528.1  275.27  4553.6  273.54  4567.9  271.27
  4609.7  268.45  4645.7  266.38  4670.4  266.06  4808.3   265.5  4822.3  266.38
  4858.4  266.53  4914.4  264.36  4928.7  264.55  4936.3  265.61  4964.8  264.47
  4971.4  261.59  4979.1  261.78  4985.7  258.59  4993.3  259.06  5004.4  257.95
  5008.4  257.95  5014.4  264.89  5020.8  267.22  5035.2  269.89  5056.5  271.52
  5099.3  275.98  5113.8  276.14  5184.6   281.9  5227.5  283.13  5284.9  286.53
#Mann= 7 ,-1 , 0
  4398.7     .12       0  4458.3     .05       0  4528.1     .12       0
  4670.4      .1       0  4964.8     .07       0  5014.4      .1       0
  5056.5     .12       0
#XS Ineff= 2 , 0
       0  4858.4  266.53               0
Permanent Ineff=
       F       F
Bank Sta=4964.8,5014.4
XS Rating Curve= 0 ,0
Exp/Cntr=0.3,0.1

Type RM Length L Ch R = 1 ,28419   ,522,522,522
BEGIN DESCRIPTION:
HOSTETTER CREEK 50.0
END DESCRIPTION:
XS GIS Cut Line= 3
      3808561.08     10186912.12      3808007.71     10187360.93
      3807719.53     10187614.57
#Sta/Elev= 30
  4287.5  289.06  4429.1  283.18  4452.6  283.16  4466.9  281.54  4473.4  282.81
  4521.4  279.84  4594.8  271.68    4694  263.44  4804.8  262.62  4914.5  263.93
  4943.3  260.71  4949.7  262.21  4957.6  261.35  4964.1  263.37    4972  261.28
  4978.5  262.85  4986.4  258.42  4992.8   260.6  4996.7  255.22  5003.2  255.22
  5007.1  258.07  5011.8   254.3  5015.8   254.3    5028  259.69 5033.52  263.71
  5035.6  265.24  5049.8  267.48  5162.7  271.06  5341.8     280  5383.9  282.06
#Mann= 7 ,-1 , 0
  4287.5     .12       0  4429.1      .1       0  4521.4     .12       0
  4804.8     .05       0  4978.5     .05       0 5033.52      .1       0
  5341.8     .12       0
Bank Sta=4978.5,5033.52
XS Rating Curve= 0 ,0
Exp/Cntr=0.3,0.1

Type RM Length L Ch R = 1 ,27897   ,495,495,495
BEGIN DESCRIPTION:
HOSTETTER CREEK 49.0
END DESCRIPTION:
XS GIS Cut Line= 3
      3808435.87     10186675.68      3808011.49     10186918.23
       3807574.5     10187467.25
#Sta/Elev= 30
  4511.2  289.17  4529.2  286.98  4566.5  284.78  4612.7  280.76    4664  277.89
    4712   274.9  4755.2  273.39  4792.6  268.85  4798.4  269.16  4842.9   265.3
  4873.2  259.97    4938  262.07  4975.4  261.85  4991.3  259.81  4997.2  254.02
    5005  254.52  5011.9  256.19  5018.3  260.42  5032.8  262.05  5040.8   261.3
    5068  262.51  5146.5  262.11  5229.5  263.03  5337.7   268.1    5396  271.06
  5459.6  274.21  5474.8  273.85  5538.9  275.94  5580.5  276.07  5701.7  279.94
#Mann= 9 ,-1 , 0
  4511.2     .05       0  4612.7     .12       0    4664      .1       0
  4991.3     .07       0  5018.3      .1       0  5229.5     .05       0
  5337.7      .1       0    5396     .05       0  5459.6     .12       0
Bank Sta=4991.3,5018.3
XS Rating Curve= 0 ,0
Exp/Cntr=0.3,0.1

Type RM Length L Ch R = 1 ,27402   ,479,479,479
BEGIN DESCRIPTION:
HOSTETTER CREEK 48.0
END DESCRIPTION:
XS GIS Cut Line= 3
      3808408.04      10186501.8      3807748.02      10186606.7
      3807316.18     10186717.39
#Sta/Elev= 30
  4331.7  293.66    4358  290.13  4412.9  285.46  4433.1  282.23  4534.4  273.28
  4549.8  270.81    4585  269.23  4686.3  259.04  4736.5  259.97  4817.9  259.09
  4861.4  260.17  4888.8  261.57  4928.3  260.91  4933.3  258.37  4949.5  262.26
  4969.8  261.41  4979.9  259.29  4995.8  251.29  5020.8  255.02  5031.1  258.73
  5042.2  259.86  5051.8   259.1    5068  261.68  5077.8     264  5124.1  267.44
  5235.8  272.18  5258.3  274.95  5299.5  274.93  5340.8   278.6  5445.8  284.62
#Mann= 5 ,-1 , 0
  4331.7     .05       0  4861.4      .1       0  4979.9     .07       0
  5031.1      .1       0    5068     .05       0
#XS Ineff= 2 , 0
       0  4949.5  262.26               0
Permanent Ineff=
       F       F
Bank Sta=4979.9,5031.1
XS Rating Curve= 0 ,0
Exp/Cntr=0.3,0.1

Type RM Length L Ch R = 1 ,26923   ,521,521,521
BEGIN DESCRIPTION:
HOSTETTER CREEK 47.0
END DESCRIPTION:
XS GIS Cut Line= 3
      3808267.89     10185811.05      3807668.28     10186209.64
      3807302.56     10186612.76
#Sta/Elev= 30
    4280  285.16  4302.8  283.63  4352.1  279.88  4388.1  280.43  4410.8  277.02
  4468.2  273.94  4638.5  262.57  4684.4  260.53  4690.4  263.75  4699.4  260.68
  4712.3  259.44    4833  256.68    4958  258.31  4964.5  257.12    4973  254.73
    4979  256.48    4988  253.49    4994   254.5  4995.1  250.16    5004  250.66
  5008.4  255.59  5022.6  254.24  5029.3  258.21    5053  258.91  5071.9  256.28
  5114.5  263.57  5171.3  267.14  5220.6  269.81  5334.1  272.38  5544.3  283.59
#Mann= 9 ,-1 , 0
    4280     .12       0  4302.8     .05       0  4468.2     .12       0
  4638.5     .05       0    4833      .1       0  4964.5     .07       0
    4979     .07       0  5029.3      .1       0    5053     .05       0
#XS Ineff= 2 , 0
       0  4690.4  263.75               0
Permanent Ineff=
       F       F
Bank Sta=4979,5029.3
XS Rating Curve= 0 ,0
Exp/Cntr=0.3,0.1

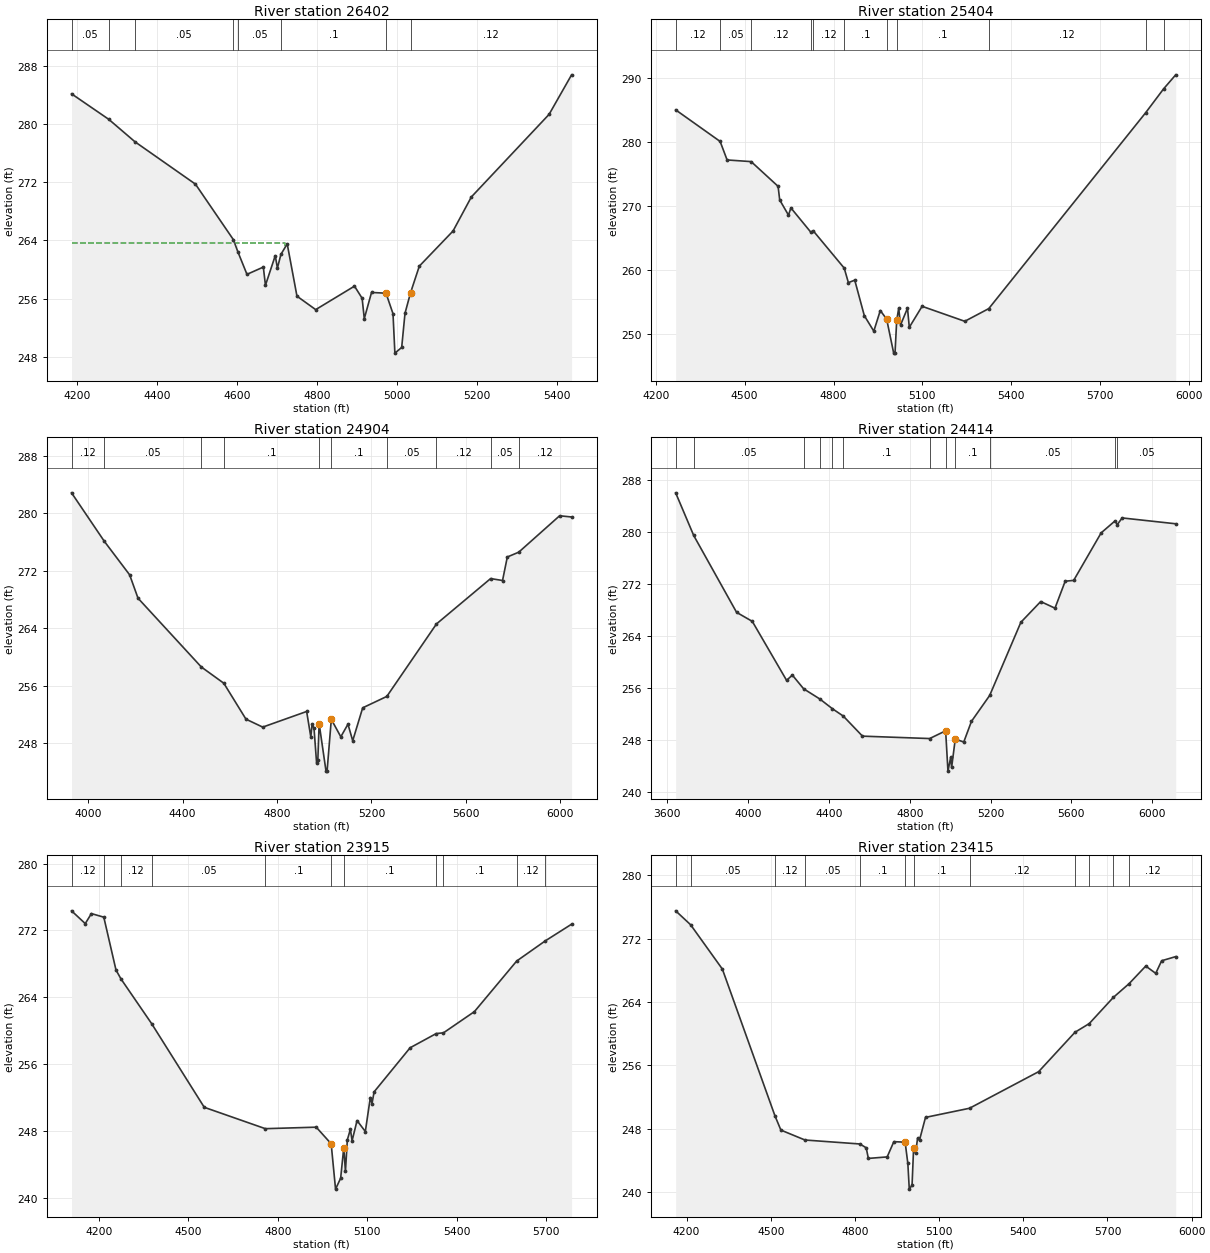
Type RM Length L Ch R = 1 ,26402   ,998,998,998
BEGIN DESCRIPTION:
HOSTETTER CREEK 46.0
END DESCRIPTION:
XS GIS Cut Line= 3
      3808206.36     10185660.29      3807447.67     10185956.89
      3807052.39     10186139.93
#Sta/Elev= 30
  4185.4  284.15  4278.5  280.64  4344.1  277.55  4495.2  271.73    4590   264.1
  4601.3  262.42    4624  259.33  4664.9  260.33  4670.2  257.83  4694.7   261.9
  4700.1  260.19  4708.9  262.08  4724.6  263.52    4749  256.33  4795.8  254.48
  4892.8  257.71  4911.9  256.04  4917.3  253.24  4935.4  256.84  4971.6  256.74
  4989.1  253.92  4993.8   248.5  5010.8  249.28  5019.1  253.98  5032.9  256.79
  5054.9  260.46  5139.2  265.29    5185  269.97  5379.4  281.33  5435.6  286.76
#Mann= 8 ,-1 , 0
  4185.4     .05       0  4278.5     .12       0  4344.1     .05       0
    4590     .12       0  4601.3     .05       0  4708.9      .1       0
  4971.6     .07       0  5032.9     .12       0
#XS Ineff= 2 , 0
       0  4719.2  263.67               0
Permanent Ineff=
       F       F
Bank Sta=4971.6,5032.9
XS Rating Curve= 0 ,0
Exp/Cntr=0.3,0.1

Type RM Length L Ch R = 1 ,25404   ,500,500,500
BEGIN DESCRIPTION:
HOSTETTER CREEK 45.0
END DESCRIPTION:
XS GIS Cut Line= 3
        3808269.     10185486.42      3807588.65     10185214.16
      3806808.49      10185764.6
#Sta/Elev= 30
  4267.2     285  4417.3  280.07  4440.8  277.18    4522  276.92  4612.9  273.06
  4618.3  270.94  4647.9  268.57  4656.2  269.69  4723.7  265.88  4731.4  266.12
  4836.1  260.29  4850.1  258.03  4871.6  258.41  4903.9  252.87  4935.9  250.45
  4957.8  253.67  4979.3  252.33    5003  247.02  5007.5  247.02  5013.2  252.13
    5020  254.04  5026.1  251.41  5049.6  254.03  5055.7  251.05  5098.9  254.33
  5242.9  251.99  5323.9  253.97  5853.3  284.55  5913.9  288.28  5954.8  290.47
#Mann= 11 ,-1 , 0
  4267.2     .12       0  4417.3     .05       0    4522     .12       0
  4723.7     .05       0  4731.4     .12       0  4836.1      .1       0
  4979.3     .07       0  5013.2      .1       0  5323.9     .12       0
  5853.3     .05       0  5913.9     .12       0
Bank Sta=4979.3,5013.2
XS Rating Curve= 0 ,0
Exp/Cntr=0.3,0.1

Type RM Length L Ch R = 1 ,24904   ,490,490,490
BEGIN DESCRIPTION:
HOSTETTER CREEK 44.0
END DESCRIPTION:
XS GIS Cut Line= 4
      3808289.84     10185402.96       3807491.2     10184814.98
      3807417.54     10184786.27      3806377.51      10184916.1
#Sta/Elev= 30
  3929.2  282.88    4068  276.12  4175.4  271.44  4210.9  268.18    4479  258.59
  4574.4  256.32  4668.3  251.31  4739.3   250.2  4925.4  252.38  4943.1  248.82
  4948.4  250.62  4956.7  250.01  4967.5  245.23  4972.9  245.66  4978.3   250.7
  5007.5  244.06    5012  244.06  5029.9  251.28  5070.2  248.85  5100.5  250.61
  5120.6   248.3  5162.9  252.89  5265.1  254.48  5475.5  264.59    5705  270.92
  5755.5  270.65  5775.7  273.93  5824.1   274.6  5997.4  279.68  6048.1  279.51
#Mann= 10 ,-1 , 0
  3929.2     .12       0    4068     .05       0    4479     .12       0
  4574.4      .1       0  4978.3     .07       0  5029.9      .1       0
  5265.1     .05       0  5475.5     .12       0    5705     .05       0
  5824.1     .12       0
#XS Ineff= 2 , 0
       0  4925.4  252.38               0
Permanent Ineff=
       F       F
Bank Sta=4978.3,5029.9
XS Rating Curve= 0 ,0
Exp/Cntr=0.3,0.1

Type RM Length L Ch R = 1 ,24414   ,499,499,499
BEGIN DESCRIPTION:
HOSTETTER CREEK 43.0
END DESCRIPTION:
XS GIS Cut Line= 3
      3808373.27      10185361.2      3807472.04     10184344.68
      3806405.13     10184672.71
#Sta/Elev= 30
  3641.5  286.05  3730.8  279.49    3943  267.67  4020.8  266.28  4190.5  257.21
    4219  258.02  4274.9  255.91  4354.7  254.35  4417.5  252.84  4470.9  251.72
  4566.1  248.63  4898.6  248.26  4977.6  249.45  4989.1  243.25  5002.4  245.35
  5007.2  243.82  5025.3  248.19  5067.2  247.72  5105.3   250.9  5195.6  254.89
  5349.9  266.14  5448.1  269.33  5518.7  268.31  5569.3  272.46  5611.2  272.58
  5747.2  279.89  5816.6  281.75  5826.6  281.14    5851  282.19  6116.2  281.29
#Mann= 12 ,-1 , 0
  3641.5     .12       0  3730.8     .05       0  4274.9     .12       0
  4354.7     .05       0  4417.5     .12       0  4470.9      .1       0
  4898.6     .05       0  4977.6     .07       0  5025.3      .1       0
  5195.6     .05       0  5816.6     .12       0  5826.6     .05       0
Bank Sta=4977.6,5025.3
XS Rating Curve= 0 ,0
Exp/Cntr=0.3,0.1

Type RM Length L Ch R = 1 ,23915   ,500,500,500
BEGIN DESCRIPTION:
HOSTETTER CREEK 42.0
END DESCRIPTION:
XS GIS Cut Line= 3
      3808452.48     10183737.21      3807587.11     10183954.38
      3806887.38     10184310.19
#Sta/Elev= 30
  4107.8  274.34  4153.8  272.81  4174.4  274.01    4216  273.58  4256.9  267.25
  4273.7  266.18  4376.4  260.83  4552.9  250.81  4757.8  248.25  4928.5  248.43
  4978.6  246.44  4993.3  241.01  5010.4  242.32  5020.9  245.99  5026.5  243.14
  5032.8  246.91  5043.1  248.18  5048.8  246.81  5065.4  249.22  5093.2  247.91
  5109.9  251.98  5115.5  251.24  5122.6  252.66  5243.4  257.94  5330.9  259.64
  5355.3  259.73  5459.1  262.27  5600.9  268.33  5697.1  270.75    5785  272.74
#Mann= 11 ,-1 , 0
  4107.8     .12       0    4216     .05       0  4273.7     .12       0
  4376.4     .05       0  4757.8      .1       0  4978.6     .07       0
  5020.9      .1       0  5330.9     .05       0  5355.3      .1       0
  5600.9     .12       0  5697.1     .05       0
Bank Sta=4978.6,5020.9
XS Rating Curve= 0 ,0
Exp/Cntr=0.3,0.1

Type RM Length L Ch R = 1 ,23415   ,476,476,476
BEGIN DESCRIPTION:
HOSTETTER CREEK 41.0
END DESCRIPTION:
XS GIS Cut Line= 3
      3808343.66     10183214.45       3807558.2     10183508.52
      3806878.67     10184162.63
#Sta/Elev= 30
  4161.3  275.49  4214.7  273.73  4327.7  268.15  4515.1  249.66  4536.3  247.86
  4622.1  246.61  4817.8  246.11  4840.2  245.63    4848  244.29    4915  244.48
  4938.8   246.4    4979  246.34  4988.7  243.65  4993.8  240.42  5003.7  240.92
  5009.2  245.59  5016.1  244.92  5023.3  246.82  5030.3  246.61  5051.6  249.46
  5208.4  250.61  5454.7  255.22  5584.4  260.19  5635.1  261.28  5720.7  264.57
  5777.3  266.32  5836.5  268.53    5872  267.61  5893.1   269.2  5943.2  269.72
#Mann= 12 ,-1 , 0
  4161.3     .12       0  4214.7     .05       0  4515.1     .12       0
  4622.1     .05       0  4817.8      .1       0    4979     .07       0
  5009.2      .1       0  5208.4     .12       0  5584.4      .1       0
  5635.1     .12       0  5720.7      .1       0  5777.3     .12       0
#XS Ineff= 2 , 0
       0                  5051.6       0  249.46
Permanent Ineff=
       F       F
Bank Sta=4979,5009.2
XS Rating Curve= 0 ,0
Exp/Cntr=0.3,0.1

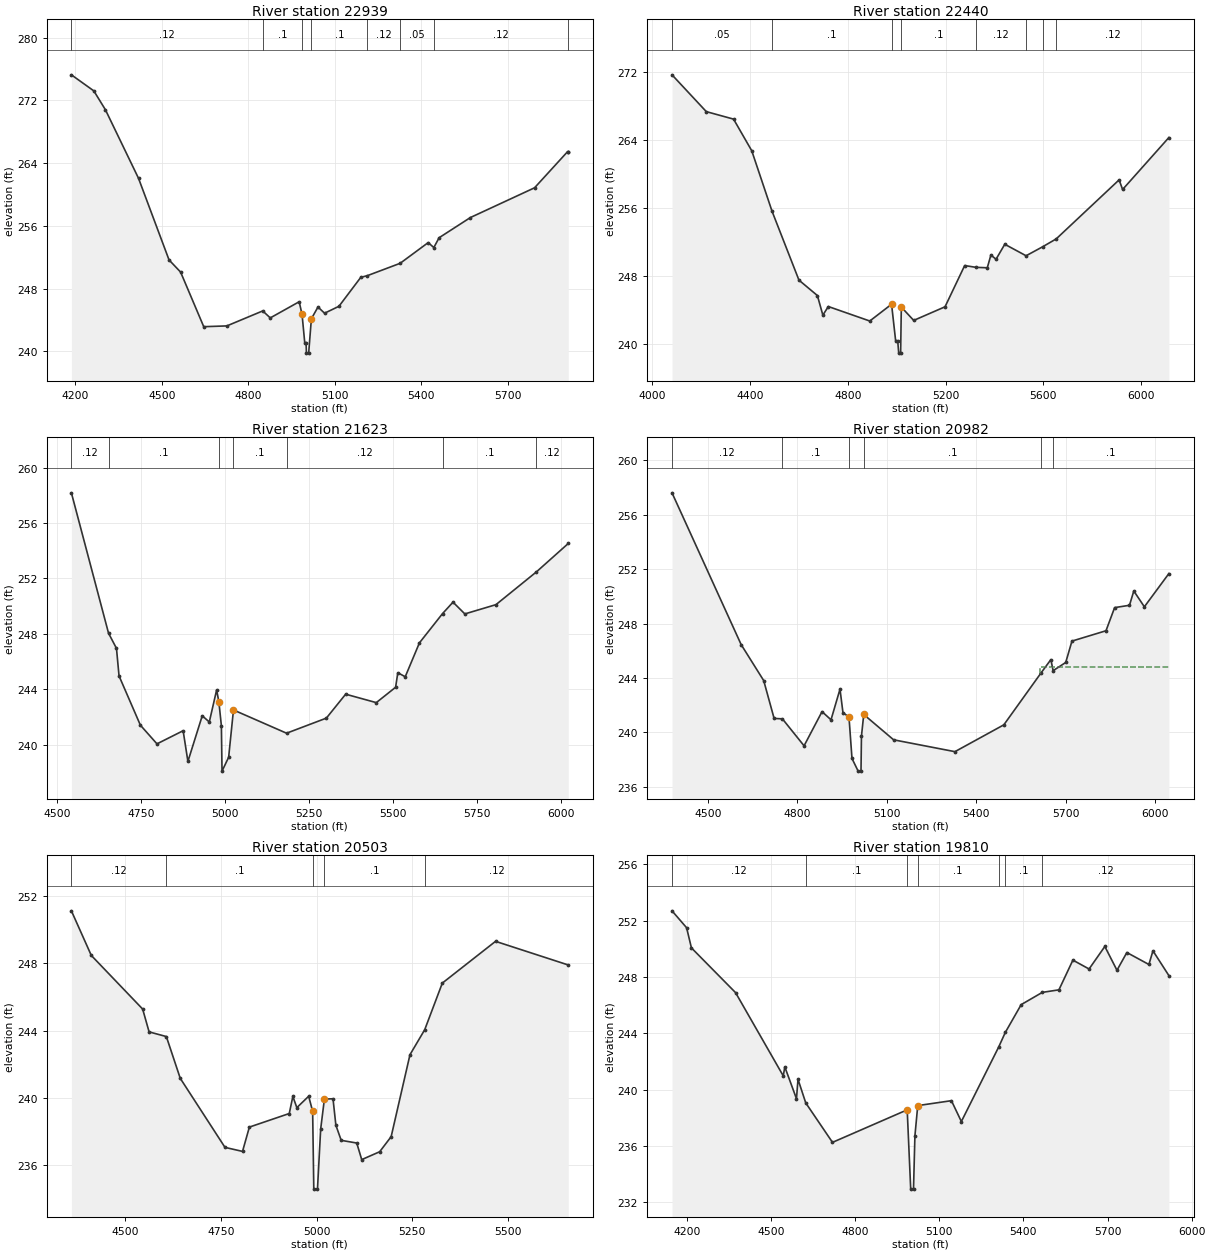
Type RM Length L Ch R = 1 ,22939   ,499,499,499
BEGIN DESCRIPTION:
HOSTETTER CREEK 40.0
END DESCRIPTION:
XS GIS Cut Line= 3
      3808325.52     10183133.79        3807514.     10183071.69
      3806717.89     10183511.05
#Sta/Elev= 30
  4186.1  275.27    4264  273.22  4304.1  270.82  4418.9  262.08  4524.8  251.67
  4564.9  250.12  4645.1  243.16  4725.3  243.26  4849.7  245.17  4875.8  244.28
  4976.1  246.34  4986.1  244.72  4995.6  241.04    5000  241.04  5001.3  239.79
    5009  239.79  5018.4  244.17  5041.3  245.67  5064.1  244.88    5114  245.76
  5189.7  249.45  5212.8  249.67  5326.2  251.24  5423.5  253.88  5443.1  253.25
  5461.3   254.5  5570.1  257.08  5792.5  260.87  5906.8  265.47  5909.3  265.47
#Mann= 8 ,-1 , 0
  4186.1     .12       0  4849.7      .1       0  4986.1     .07       0
  5018.4      .1       0  5212.8     .12       0  5326.2     .05       0
  5443.1     .12       0  5906.8     .05       0
Bank Sta=4986.1,5018.4
XS Rating Curve= 0 ,0
Exp/Cntr=0.3,0.1

Type RM Length L Ch R = 1 ,22440   ,817,817,817
BEGIN DESCRIPTION:
HOSTETTER CREEK 39.0
END DESCRIPTION:
XS GIS Cut Line= 3
      3808299.36     10182998.72      3807478.05     10182584.83
      3806562.11     10183219.95
#Sta/Elev= 30
  4080.3  271.62  4220.7   267.3  4332.3  266.42  4406.7  262.71  4489.8  255.61
    4600  247.52  4675.5  245.71  4697.9  243.41  4720.3  244.42    4890  242.72
  4979.2  244.69  4995.9   240.4  5004.3   240.4  5008.5  238.95  5016.3  238.95
  5019.1  244.36  5069.8  242.79  5198.1  244.39  5278.5  249.23  5325.2  249.02
  5371.1  248.97  5385.9  250.47  5406.9  249.97  5442.7  251.73  5529.9  250.38
  5597.4  251.43  5653.3  252.36  5910.8  259.29  5925.1  258.16  6114.6  264.26
#Mann= 8 ,-1 , 0
  4080.3     .05       0  4489.8      .1       0  4979.2     .07       0
  5019.1      .1       0  5325.2     .12       0  5529.9      .1       0
  5597.4     .05       0  5653.3     .12       0
Bank Sta=4979.2,5019.1
XS Rating Curve= 0 ,0
Exp/Cntr=0.3,0.1

Type RM Length L Ch R = 1 ,21623   ,641,641,641
BEGIN DESCRIPTION:
HOSTETTER CREEK 38.0
END DESCRIPTION:
XS GIS Cut Line= 3
      3807717.83      10181661.1      3807417.87     10182006.14
      3806623.58     10182650.05
#Sta/Elev= 30
  4542.8  258.19  4653.4  248.05  4677.1  246.95  4684.7  244.96  4748.3   241.4
  4797.7  240.05  4875.6     241  4889.8  238.78  4932.5  242.08  4953.5  241.63
  4975.3  243.94  4981.9  243.11  4989.5  241.36  4991.4  238.08  5011.1  239.08
  5025.5   242.5  5183.6  240.82  5302.1  241.91  5359.6  243.64  5450.8  243.03
  5508.3  244.14  5514.9  245.19    5537   244.9  5579.3  247.35    5648  249.46
  5679.3  250.29  5714.5  249.44  5807.2  250.11  5927.8  252.48  6022.5  254.53
#Mann= 7 ,-1 , 0
  4542.8     .12       0  4653.4      .1       0  4981.9     .07       0
  5025.5      .1       0  5183.6     .12       0    5648      .1       0
  5927.8     .12       0
Bank Sta=4981.9,5025.5
XS Rating Curve= 0 ,0
Exp/Cntr=0.3,0.1

Type RM Length L Ch R = 1 ,20982   ,479,479,479
BEGIN DESCRIPTION:
HOSTETTER CREEK 37.0
END DESCRIPTION:
XS GIS Cut Line= 3
      3807668.76     10181549.55      3807051.36     10181602.99
       3806411.8     10182430.17
#Sta/Elev= 30
  4380.3   257.6  4612.1  246.45  4687.6  243.81  4722.5  241.03  4750.3     241
  4822.9  239.02  4883.1  241.53  4913.2  240.93  4943.3  243.18  4953.3  241.45
  4973.4  241.14  4983.5  238.09  5004.1  237.16  5013.7  237.16  5015.2  239.72
  5022.9  241.32    5123  239.46  5328.5  238.59  5492.4  240.56  5617.4  244.38
    5650  245.35  5657.7  244.54  5699.8  245.14  5720.7  246.71  5834.8  247.47
  5863.7  249.17  5913.5  249.34    5928  250.39  5963.4  249.23  6045.6  251.67
#Mann= 6 ,-1 , 0
  4380.3     .12       0  4750.3      .1       0  4973.4     .07       0
  5022.9      .1       0  5617.4     .12       0  5657.7      .1       0
#XS Ineff= 2 , 0
       0                  5614.7       0  244.82
Permanent Ineff=
       F       F
Bank Sta=4973.4,5022.9
XS Rating Curve= 0 ,0
Exp/Cntr=0.3,0.1

Type RM Length L Ch R = 1 ,20503   ,693,693,693
BEGIN DESCRIPTION:
HOSTETTER CREEK 36.0
END DESCRIPTION:
XS GIS Cut Line= 3
      3807558.18     10181367.05      3806937.75     10181207.17
      3806324.55     10181444.16
#Sta/Elev= 30
  4359.3  251.14  4411.3  248.48  4545.5  245.28  4562.3  243.92  4607.4  243.64
  4643.7  241.15  4760.6  237.03  4806.4  236.79  4824.3  238.24  4928.5  239.05
  4937.9  240.07  4948.3   239.4  4979.2  240.08  4989.6  239.18  4992.6  234.54
  5002.2  234.54  5010.6  238.13  5020.3  239.91  5042.8  239.93  5050.3  238.35
  5064.2  237.45  5104.8  237.29  5117.8   236.3  5164.7  236.77  5194.7  237.67
  5243.9  242.56  5282.4  244.05  5328.4  246.83  5467.4  249.32  5657.4  247.91
#Mann= 5 ,-1 , 0
  4359.3     .12       0  4607.4      .1       0  4989.6     .07       0
  5020.3      .1       0  5282.4     .12       0
#XS Ineff= 2 , 0
       0                  5243.9       0  242.56
Permanent Ineff=
       F       F
Bank Sta=4989.6,5020.3
XS Rating Curve= 0 ,0
Exp/Cntr=0.3,0.1

Type RM Length L Ch R = 1 ,19810   ,561,561,561
BEGIN DESCRIPTION:
HOSTETTER CREEK 35.0
END DESCRIPTION:
XS GIS Cut Line= 4
      3807685.64     10181123.84      3806917.96     10180792.74
      3806851.77     10180793.83      3806168.32     10181331.29
#Sta/Elev= 30
  4147.1   252.7  4199.1   251.5  4216.3  250.07  4373.8  246.89  4543.8  240.98
  4549.3  241.62  4590.9  239.36  4596.3  240.74    4624  239.06  4719.3  236.26
  4985.7  238.57  4998.2  232.94  5008.2  232.94  5013.2  236.72  5023.3  238.87
  5143.4  239.22  5178.8  237.74  5311.9  243.03  5335.6  244.07  5392.1  246.04
  5467.5  246.91  5526.7  247.09  5576.5   249.2  5634.2  248.57  5690.4  250.17
  5733.7  248.48  5768.9  249.74  5847.5  248.89    5862  249.86  5918.8   248.1
#Mann= 7 ,-1 , 0
  4147.1     .12       0    4624      .1       0  4985.7     .07       0
  5023.3      .1       0  5311.9     .12       0  5335.6      .1       0
  5467.5     .12       0
#XS Ineff= 2 ,-1
  4549.3  4520.3  241.62  4596.3  4549.3  240.74
Permanent Ineff=
       F       F
Bank Sta=4985.7,5023.3
XS Rating Curve= 0 ,0
Exp/Cntr=0.3,0.1