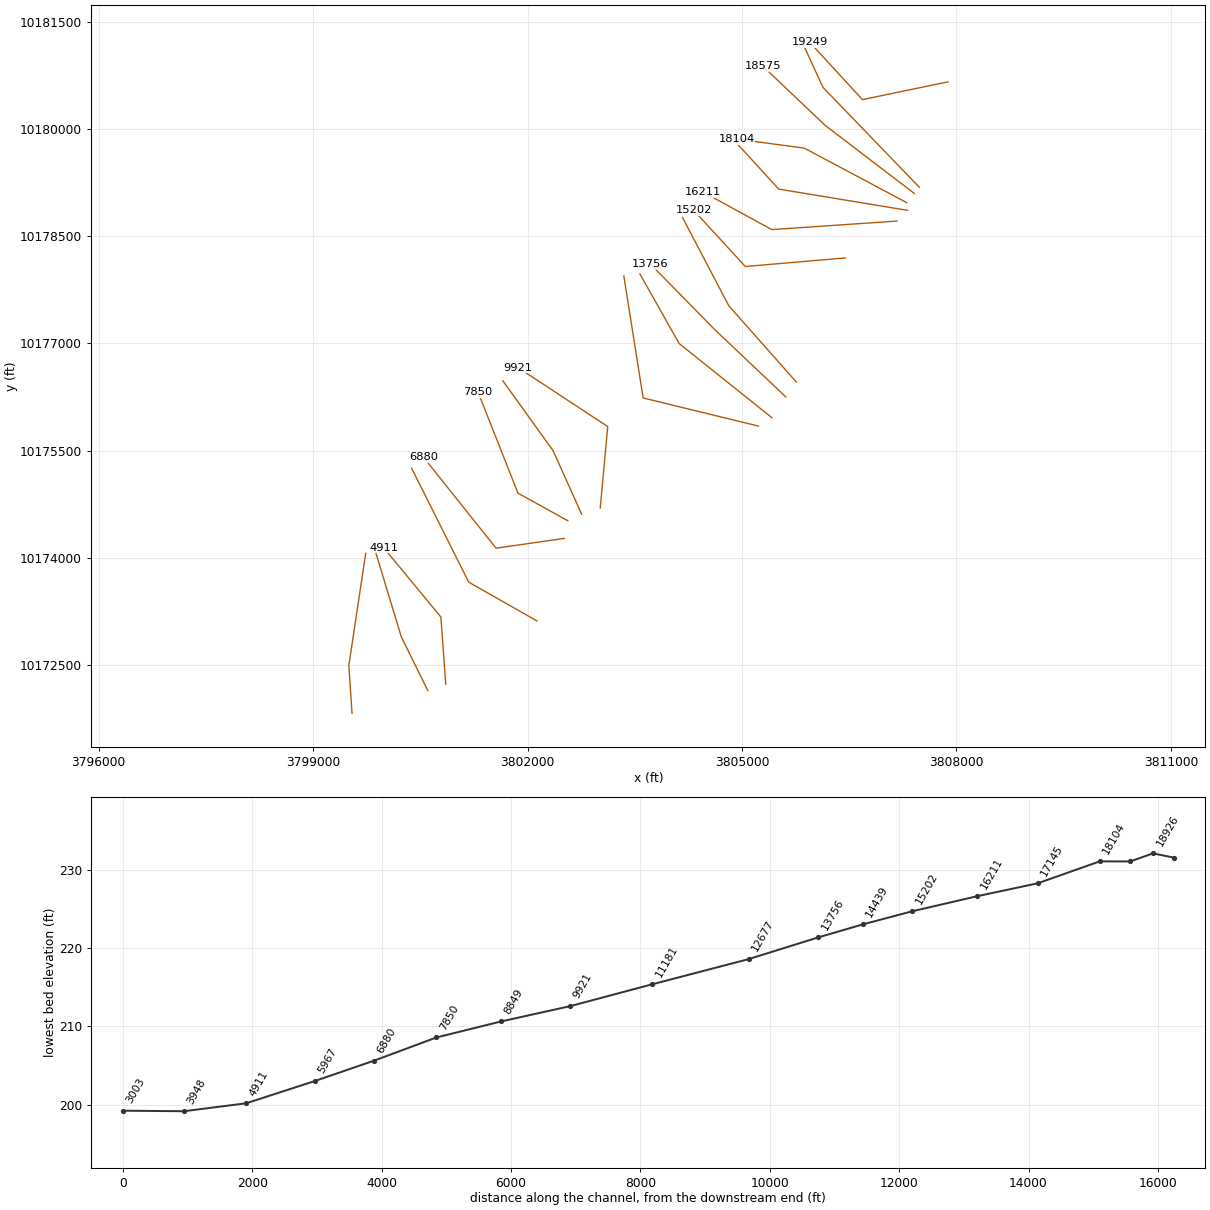
HEC-RAS study HOSTETTER CREEK.prj: HOSTETTER CREEK Base Level Engineering

--- HOSTETTER CREEK.g01 (geometry) --- (continued)

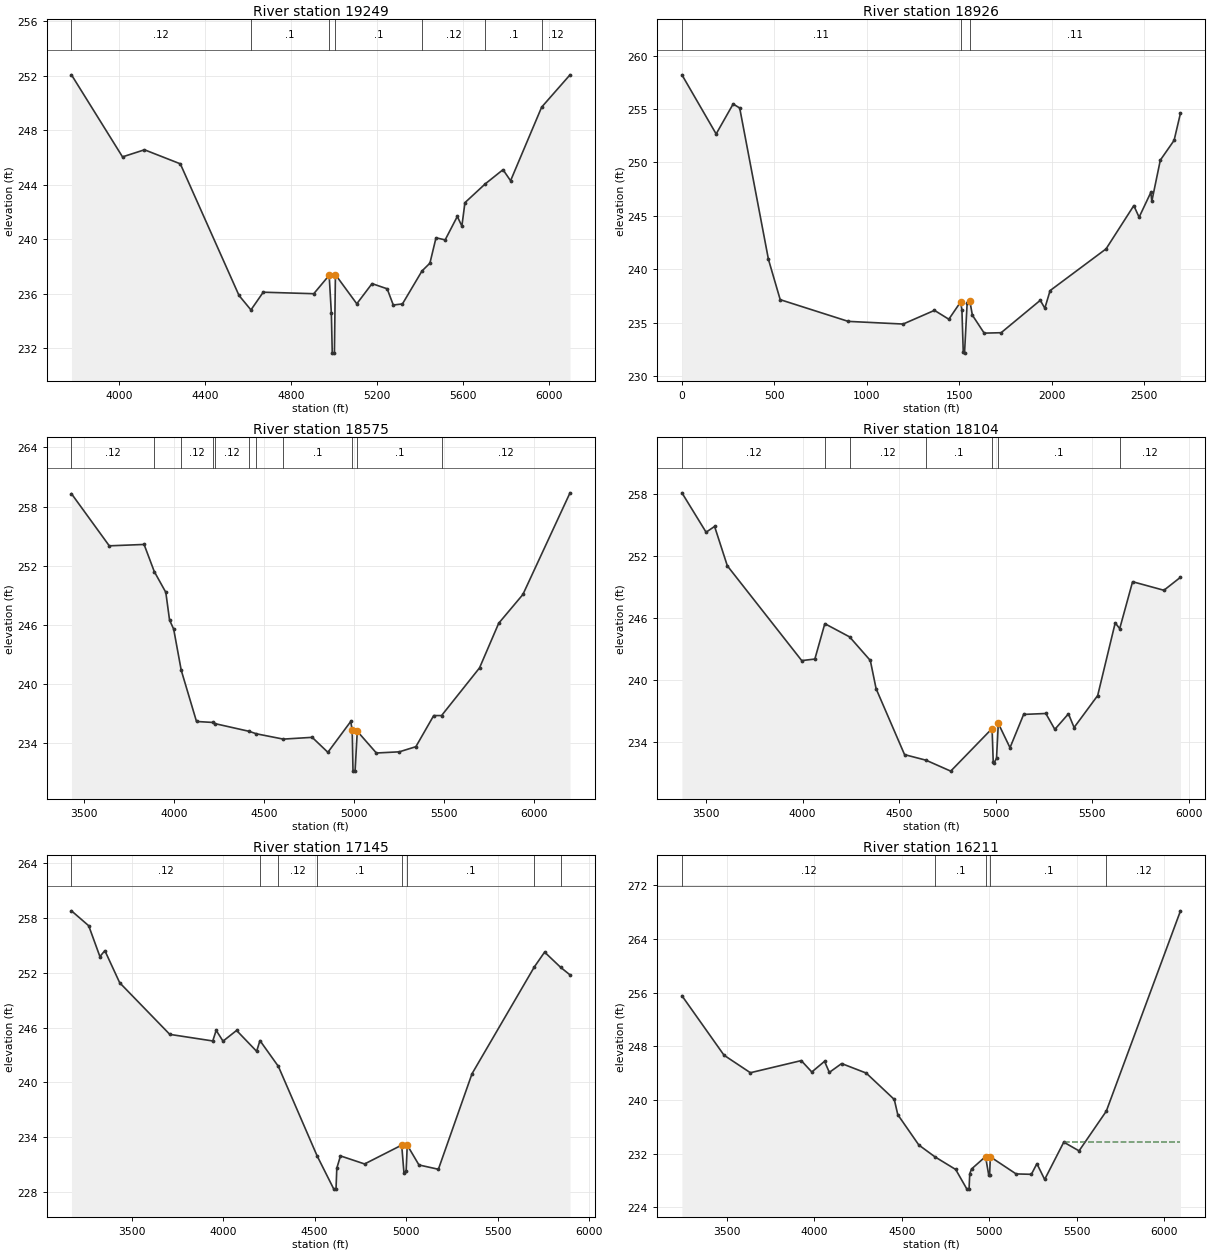
Type RM Length L Ch R = 1 ,19249   ,324,324,324
BEGIN DESCRIPTION:
HOSTETTER CREEK 38.5
END DESCRIPTION:
XS GIS Cut Line= 3
      3807880.09     10180658.57      3806684.86     10180410.03
      3805943.46     10181216.66
#Sta/Elev= 30
  3779.2  252.05  4016.4  246.03  4118.5  246.55  4284.9  245.52  4557.7  235.86
  4613.1   234.8  4670.1   236.1    4905  235.99  4976.5  237.34  4986.7  234.56
  4990.9  231.63  5000.9  231.63  5005.6  237.39  5104.9  235.25  5175.7  236.73
  5246.1  236.35  5274.4  235.16    5317  235.24  5407.9  237.66  5444.6  238.23
  5472.9  240.09  5515.5  239.94  5571.9  241.66  5593.2  240.95  5607.3  242.67
  5701.8  244.05  5784.3  245.09  5819.4  244.28  5963.8  249.68  6095.6  252.05
#Mann= 7 ,-1 , 0
  3779.2     .12       0  4613.1      .1       0  4976.5     .07       0
  5005.6      .1       0  5407.9     .12       0  5701.8      .1       0
  5963.8     .12       0
Bank Sta=4976.5,5005.6
XS Rating Curve= 0 ,0
Exp/Cntr=0.3,0.1

Type RM Length L Ch R = 1 ,18926   ,351,351,351
XS GIS Cut Line= 3
      3807481.86     10179183.39      3806133.79     10180580.55
      3805817.73     10181267.49
#Sta/Elev= 30
       0   258.2   185.1  252.67   276.9  255.47   312.4   255.1   468.1  240.93
   531.6  237.17   899.5  235.14  1196.4  234.89  1366.1  236.17  1443.8  235.34
  1507.6  236.96  1514.6   236.2  1521.8  232.25  1528.7  232.17  1542.9  236.89
    1557  237.07  1571.2  235.72    1635  234.04  1726.8  234.08  1938.4  237.11
  1963.1  236.37  1991.6  238.02  2294.3  241.92  2444.5  245.97    2473  244.88
  2536.4   247.2  2541.9  246.38  2587.8  250.22  2662.3  252.07  2696.9  254.62
#Mann= 3 , 0 , 0
       0     .11       0  1507.6     .07       0    1557     .11       0
Bank Sta=1507.6,1557
XS Rating Curve= 0 ,0
Exp/Cntr=0.3,0.1

Type RM Length L Ch R = 1 ,18575   ,471,471,471
BEGIN DESCRIPTION:
HOSTETTER CREEK 33.0
END DESCRIPTION:
XS GIS Cut Line= 3
      3807409.59     10179098.57      3806162.21      10180050.8
      3805293.22     10180876.48
#Sta/Elev= 30
  3430.7   259.3  3640.6  254.01  3833.9  254.15  3890.4   251.4  3954.5  249.29
  3975.3  246.47  3998.1  245.56  4040.1  241.38  4124.9  236.18  4217.3  236.08
  4230.2  235.95  4417.1  235.18  4457.2  234.93  4606.7  234.39  4767.1  234.57
  4854.3  233.05  4981.2  236.18  4989.4   235.3  4993.8  231.14  5005.3  231.14
  5017.5  235.19  5123.5  232.98  5250.9   233.1  5342.8  233.62  5441.9  236.78
  5485.5  236.78  5696.3  241.62  5802.7  246.15    5937  249.07  6198.7  259.39
#Mann= 11 ,-1 , 0
  3430.7     .12       0  3890.4     .05       0  4040.1     .12       0
  4217.3     .05       0  4230.2     .12       0  4417.1      .1       0
  4457.2     .12       0  4606.7      .1       0  4989.4     .07       0
  5017.5      .1       0  5485.5     .12       0
Bank Sta=4989.4,5017.5
XS Rating Curve= 0 ,0
Exp/Cntr=0.3,0.1

Type RM Length L Ch R = 1 ,18104   ,959,959,959
BEGIN DESCRIPTION:
HOSTETTER CREEK 32.0
END DESCRIPTION:
XS GIS Cut Line= 3
       3807305.4     10178968.37      3805871.23       10179732.
      3804922.79     10179858.24
#Sta/Elev= 30
  3375.2  258.14  3500.3  254.32  3544.3  254.88  3610.3  251.06  3995.5  241.87
  4063.5  242.02  4115.1  245.45  4243.3  244.17  4350.7  241.88  4380.7  239.14
    4528  232.75    4639  232.21  4767.1  231.15  4981.2  235.28  4987.1  232.07
  4992.8  231.98  5004.2   232.4  5013.5  235.78    5074  233.42  5144.6  236.65
  5259.5  236.74  5306.1   235.2  5376.7  236.71  5405.9  235.38    5528  238.48
  5618.8  245.53  5642.1  244.97  5708.8  249.52    5871  248.69  5956.8  249.95
#Mann= 7 ,-1 , 0
  3375.2     .12       0  4115.1     .05       0  4243.3     .12       0
    4639      .1       0  4981.2     .07       0  5013.5      .1       0
  5642.1     .12       0
Bank Sta=4981.2,5013.5
XS Rating Curve= 0 ,0
Exp/Cntr=0.3,0.1

Type RM Length L Ch R = 1 ,17145   ,934,934,934
BEGIN DESCRIPTION:
HOSTETTER CREEK 30.0
END DESCRIPTION:
XS GIS Cut Line= 3
      3807317.85     10178861.07      3805513.89     10179158.42
      3804909.61     10179819.03
#Sta/Elev= 30
  3171.7  258.75  3265.9  257.12  3327.1  253.75  3354.1   254.4  3435.2  250.89
  3708.8  245.25  3943.6  244.53  3962.2  245.69  3999.7  244.51  4073.7  245.68
  4183.2   243.4  4201.4  244.57  4302.1  241.75  4513.5  231.98  4604.9  228.34
  4616.9  228.34  4621.3  230.63  4641.3  231.97    4773  231.09  4975.7  233.15
  4988.2   230.1    5000  230.28    5006  233.15  5070.1  230.98  5176.2  230.51
  5359.9  240.95  5700.3  252.62  5756.5  254.24  5844.3  252.57  5895.3  251.75
#Mann= 8 ,-1 , 0
  3171.7     .12       0  4201.4     .05       0  4302.1     .12       0
  4513.5      .1       0  4975.7     .07       0    5006      .1       0
  5700.3     .12       0  5844.3      .1       0
Bank Sta=4975.7,5006
XS Rating Curve= 0 ,0
Exp/Cntr=0.3,0.1

Type RM Length L Ch R = 1 ,16211   ,1009,1009,1009
BEGIN DESCRIPTION:
HOSTETTER CREEK 29.0
END DESCRIPTION:
XS GIS Cut Line= 3
      3807167.83     10178711.07      3805416.76     10178592.17
      3804458.22     10179115.92
#Sta/Elev= 30
  3244.9  255.55  3485.4  246.67  3635.8  244.06  3926.4  245.87  3986.6  244.17
  4059.3  245.76  4086.8  244.11    4157  245.43  4297.3  244.01  4457.7  240.07
  4477.7   237.8    4598  233.27  4690.5   231.5  4808.5  229.62  4872.5  226.69
  4884.8  226.69  4888.7  228.98  4898.7  229.69  4978.9  231.55  4996.9  228.81
  5002.2  228.81  5006.3  231.51  5153.4  228.96  5240.6   228.9  5272.3  230.49
  5316.5  228.13  5425.7   233.7    5513   232.4  5668.5  238.32  6092.3  268.22
#Mann= 5 ,-1 , 0
  3244.9     .12       0  4690.5      .1       0  4978.9     .07       0
  5006.3      .1       0  5668.5     .12       0
#XS Ineff= 2 , 0
       0                  5431.8       0  233.72
Permanent Ineff=
       F       F
Bank Sta=4978.9,5006.3
XS Rating Curve= 0 ,0
Exp/Cntr=0.3,0.1

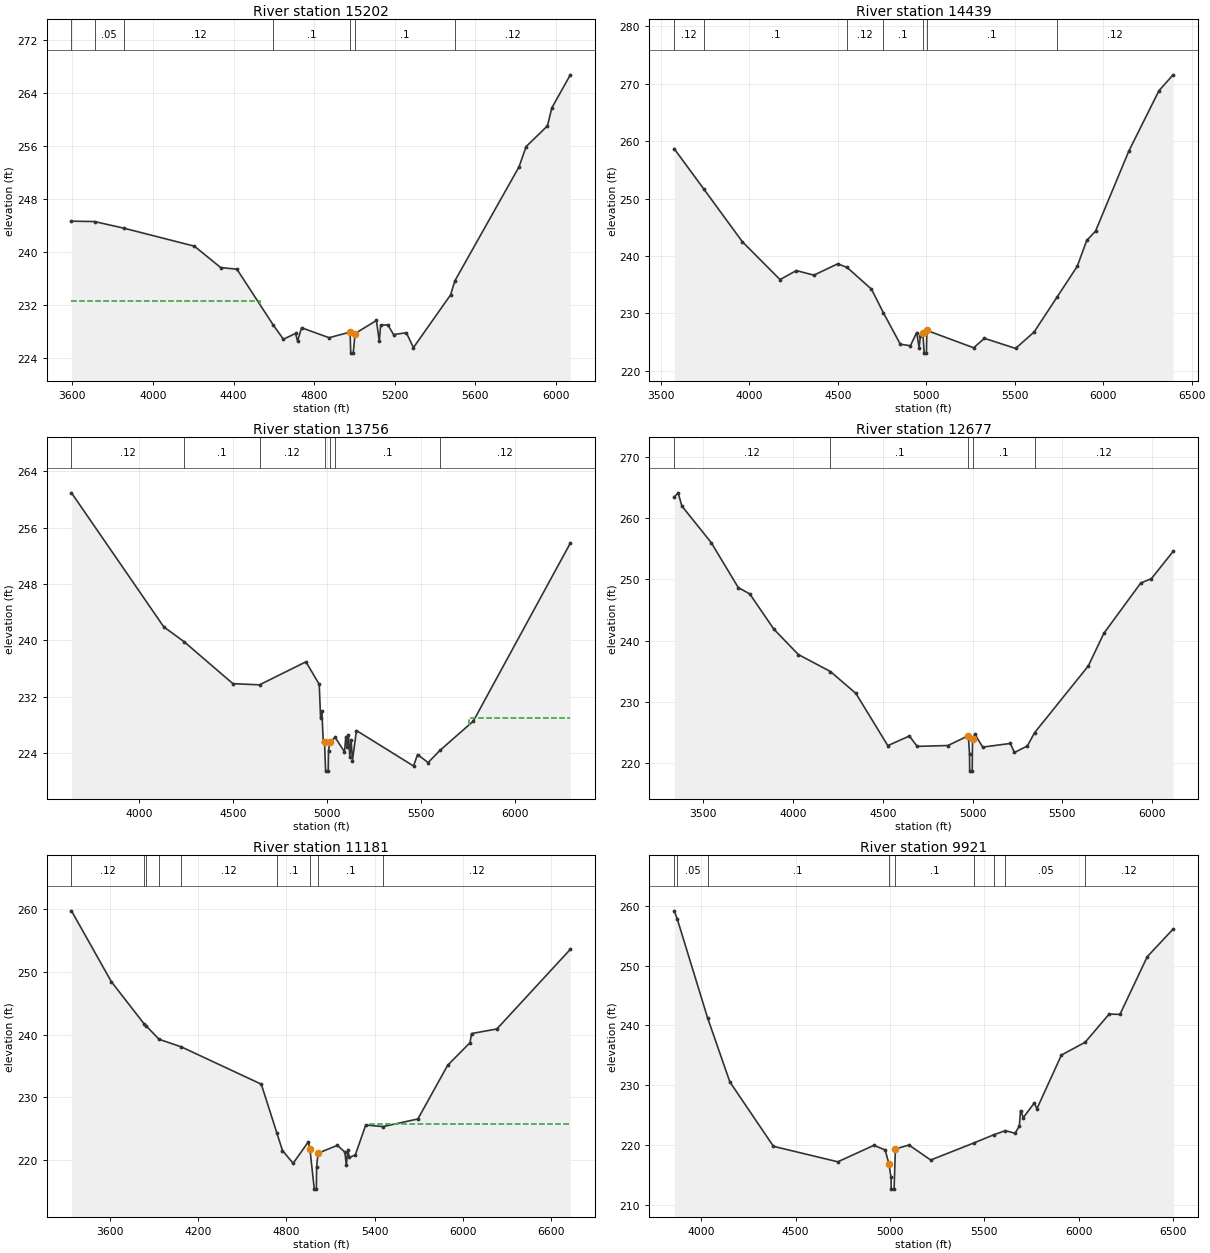
Type RM Length L Ch R = 1 ,15202   ,763,763,763
BEGIN DESCRIPTION:
HOSTETTER CREEK 27.0
END DESCRIPTION:
XS GIS Cut Line= 3
      3806446.03      10178195.8       3805046.6     10178075.41
      3804322.04      10178865.2
#Sta/Elev= 30
  3595.4  244.68  3709.8  244.62  3855.5  243.62  4205.8   240.9  4336.3  237.67
  4416.6  237.43  4596.4  229.03  4647.4  226.85  4707.7  227.72  4717.7  226.58
  4737.8  228.58  4874.4  227.08  4978.7  227.93  4981.7  224.75  4994.2  224.75
  5003.2  227.71  5109.3  229.68  5123.5  226.52  5130.2  228.97    5166  229.02
  5194.4  227.55  5257.9  227.83    5293  225.58  5477.4  233.55  5498.9  235.68
  5817.1  252.88  5852.3  255.94  5958.3  259.07  5979.9  261.78  6071.8  266.78
#Mann= 7 ,-1 , 0
  3595.4     .12       0  3709.8     .05       0  3855.5     .12       0
  4596.4      .1       0  4978.7     .07       0  5003.2      .1       0
  5498.9     .12       0
#XS Ineff= 2 , 0
       0  4528.8  232.63               0
Permanent Ineff=
       F       F
Bank Sta=4978.7,5003.2
XS Rating Curve= 0 ,0
Exp/Cntr=0.3,0.1

Type RM Length L Ch R = 1 ,14439   ,683,683,683
BEGIN DESCRIPTION:
HOSTETTER CREEK 26.0
END DESCRIPTION:
XS GIS Cut Line= 3
       3805760.3     10176459.65       3804815.7     10177525.65
      3804167.84     10178761.09
#Sta/Elev= 30
  3575.7  258.67  3741.8  251.69  3961.1  242.46  4173.6  235.88  4265.6  237.45
  4365.1  236.65  4499.5  238.63  4552.9  237.99  4690.5  234.21  4757.9  230.09
  4853.5  224.62  4910.4  224.36  4945.5  226.64  4959.8  224.05  4967.2  226.14
  4980.7  226.57  4988.4  223.07  5000.9  223.07  5003.3  227.03    5268     224
  5328.5  225.65    5505  223.89  5609.6  226.75  5739.3  232.84    5853  238.17
  5907.1  242.71  5956.9  244.33  6144.1  258.22    6315  268.78    6395  271.55
#Mann= 7 ,-1 , 0
  3575.7     .12       0  3741.8      .1       0  4552.9     .12       0
  4757.9      .1       0  4980.7     .07       0  5003.3      .1       0
  5739.3     .12       0
Bank Sta=4980.7,5003.3
XS Rating Curve= 0 ,0
Exp/Cntr=0.3,0.1

Type RM Length L Ch R = 1 ,13756   ,1079,1079,1079
BEGIN DESCRIPTION:
HOSTETTER CREEK 24.0
END DESCRIPTION:
XS GIS Cut Line= 3
      3805612.72     10176251.34      3804625.12     10177186.64
      3803717.83      10178111.1
#Sta/Elev= 30
  3639.8  260.96    4131  241.92  4240.1  239.79  4499.1  233.85  4640.8  233.68
  4887.9  236.95  4958.7  233.75  4965.9  228.97  4972.8  229.91  4980.1  225.61
    4987   225.5  4992.7  221.42  5006.5  221.42  5008.2   224.3  5015.4  225.61
  5043.6   226.2  5093.1  224.17  5100.2  226.29  5107.2  224.85  5114.4  226.54
  5121.4  223.48  5128.5  225.88  5135.5  222.92  5156.8  227.19  5460.8  222.15
  5482.1  223.77  5538.6  222.64  5601.5  224.37    5779  228.53  6295.3  253.81
#Mann= 7 ,-1 , 0
  3639.8     .12       0  4240.1      .1       0  4640.8     .12       0
    4987     .07       0  5015.4     .12       0  5043.6      .1       0
  5601.5     .12       0
#XS Ineff= 2 , 0
       0                  5757.9       0  228.93
Permanent Ineff=
       F       F
Bank Sta=4987,5015.4
XS Rating Curve= 0 ,0
Exp/Cntr=0.3,0.1

Type RM Length L Ch R = 1 ,12677   ,1496,1496,1496
BEGIN DESCRIPTION:
HOSTETTER CREEK 23.0
END DESCRIPTION:
XS GIS Cut Line= 3
      3805417.83     10175961.09      3804121.18     10176997.89
      3803572.83       10177970.
#Sta/Elev= 30
  3339.8  263.49  3361.4  264.17  3382.2  262.01  3545.5  256.03    3696  248.67
    3760  247.63  3894.5  241.85  4030.5  237.71  4209.4  234.92  4350.7  231.35
  4528.4   222.8  4648.5  224.38  4691.7  222.68    4863  222.82  4976.7  224.42
  4983.1  221.43  4984.1  218.63    4998  218.63    5000  223.91  5013.2  224.66
  5056.5  222.56  5210.3  223.16  5233.3  221.68  5304.9  222.75  5345.4  224.92
  5644.4  235.85    5731  241.19  5936.1  249.41  5995.4  250.13  6116.1  254.57
#Mann= 5 ,-1 , 0
  3339.8     .12       0  4209.4      .1       0  4976.7     .07       0
    5000      .1       0  5345.4     .12       0
Bank Sta=4976.7,5000
XS Rating Curve= 0 ,0
Exp/Cntr=0.3,0.1

Type RM Length L Ch R = 1 ,11181   ,1260,1260,1260
BEGIN DESCRIPTION:
HOSTETTER CREEK 21.0
END DESCRIPTION:
XS GIS Cut Line= 3
       3805230.8     10175843.36       3803617.6     10176236.45
      3803347.08     10177944.06
#Sta/Elev= 30
  3339.6   259.7  3610.2  248.43  3831.8  241.74  3844.9  241.44  3934.5  239.25
  4084.7  238.05  4629.2   232.1  4734.8  224.35  4773.3  221.53  4845.4   219.5
  4948.3  222.89  4959.9  221.75  4989.4  215.39  5003.6  215.39  5004.9  218.86
  5014.8  221.11  5146.4  222.36    5197  221.28  5207.2  219.17  5217.2  221.68
  5227.4  220.44  5267.9  220.83  5338.8  225.59  5457.5  225.35  5693.2  226.56
  5895.6  235.11  6047.5  238.71  6057.8  240.16  6229.8  240.89  6728.9  253.57
#Mann= 9 ,-1 , 0
  3339.6     .12       0  3831.8      .1       0  3844.9     .12       0
  3934.5      .1       0  4084.7     .12       0  4734.8      .1       0
  4959.9     .07       0  5014.8      .1       0  5457.5     .12       0
#XS Ineff= 2 , 0
       0                  5369.2       0  225.77
Permanent Ineff=
       F       F
Bank Sta=4959.9,5014.8
XS Rating Curve= 0 ,0
Exp/Cntr=0.3,0.1

Type RM Length L Ch R = 1 ,9921    ,1072,1072,1072
BEGIN DESCRIPTION:
HOSTETTER CREEK 19.0
END DESCRIPTION:
XS GIS Cut Line= 3
      3803017.22     10174697.51      3803121.82     10175836.52
      3801867.83     10176661.09
#Sta/Elev= 30
  3856.2  259.15  3872.8  257.73  4032.5   241.3    4151  230.54    4382  219.77
  4723.4  217.18  4914.2  219.93  4974.4  219.16  4994.5  216.82  5005.4  214.56
  5006.5  212.61  5021.7  212.61  5028.7  219.32  5100.5  219.99  5215.9  217.48
  5442.8  220.31  5550.3   221.7  5611.9  222.39    5663  221.95  5685.9  223.18
  5691.9  225.74    5707  224.58  5764.2  226.99  5779.3  226.08  5908.8  235.03
    6035  237.18  6161.9  241.89  6219.1  241.83  6363.7  251.47  6500.8   256.1
#Mann= 9 ,-1 , 0
  3856.2     .12       0  3872.8     .05       0  4032.5      .1       0
  4994.5     .07       0  5028.7      .1       0  5442.8     .05       0
  5550.3     .12       0  5611.9     .05       0    6035     .12       0
Bank Sta=4994.5,5028.7
XS Rating Curve= 0 ,0
Exp/Cntr=0.3,0.1

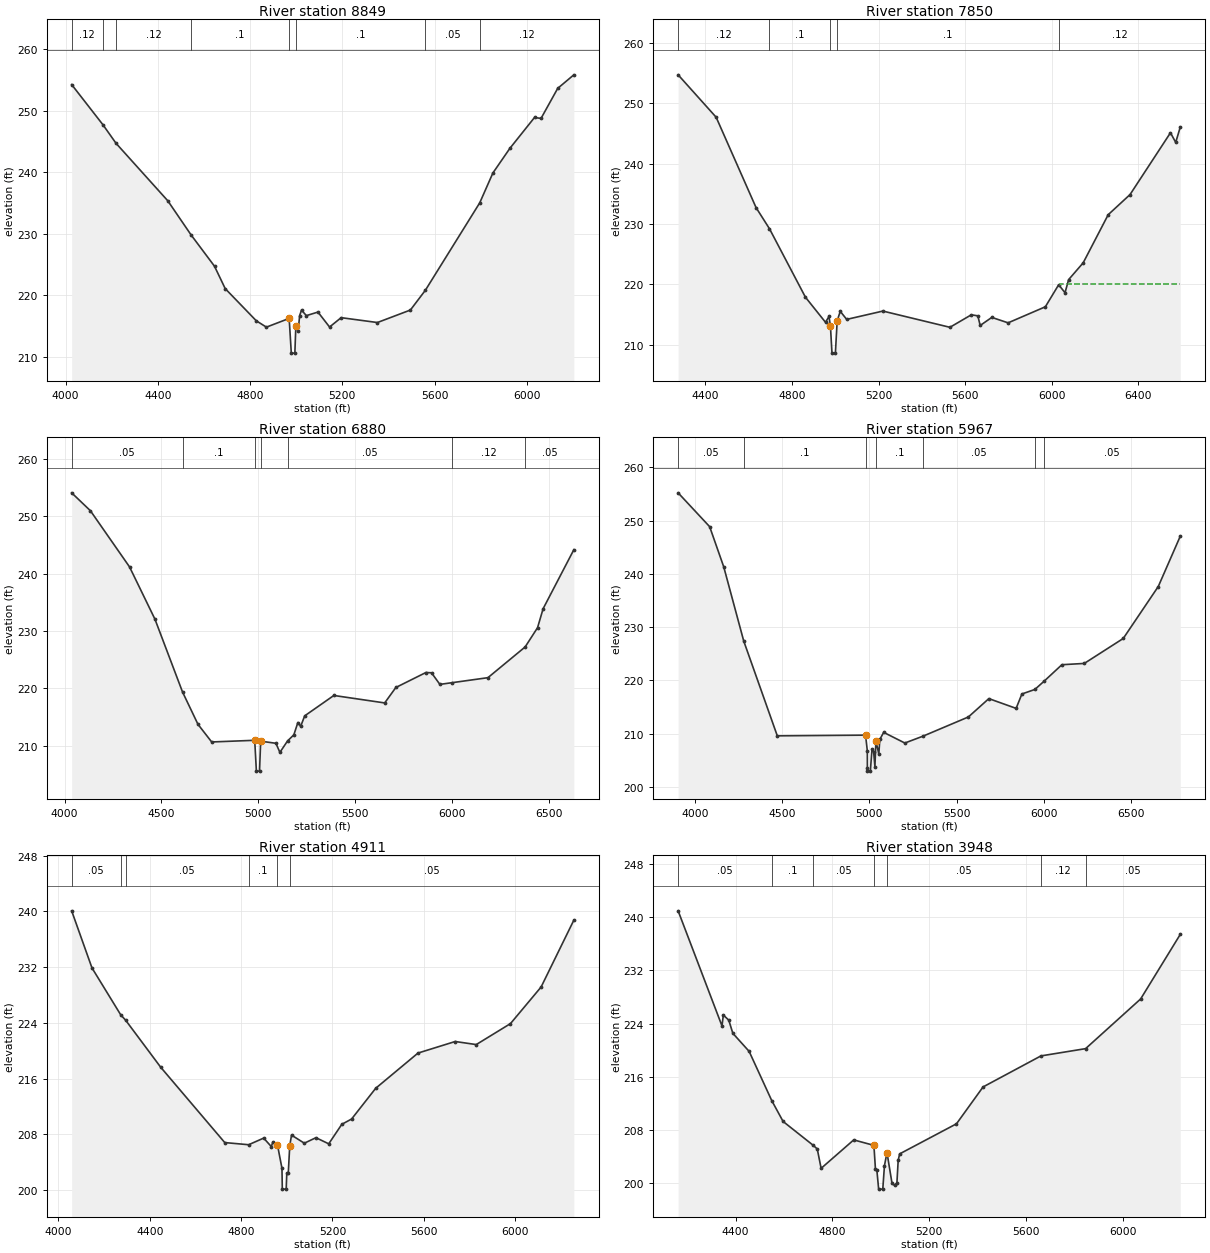
Type RM Length L Ch R = 1 ,8849    ,999,999,999
BEGIN DESCRIPTION:
HOSTETTER CREEK 17.0
END DESCRIPTION:
XS GIS Cut Line= 3
      3802756.81     10174610.72      3802357.48     10175498.99
       3801654.7      10176476.6
#Sta/Elev= 30
  4026.1  254.26  4162.4   247.7  4218.6  244.72  4443.1  235.38  4544.2  229.83
  4645.7  224.75    4692  221.12  4826.9  215.89  4870.7  214.86  4969.4  216.28
  4978.7  210.64  4994.1  210.64  4998.4  215.03  5008.3  214.21  5014.9  216.74
    5023  217.63  5043.9  216.73  5094.3  217.31  5144.6  214.88  5194.9   216.4
  5352.1  215.61  5495.2  217.64  5560.3  220.86  5795.9  235.05    5853   239.9
  5926.2  243.88  6033.4  248.91  6061.7  248.76    6134  253.64    6204  255.84
#Mann= 8 ,-1 , 0
  4026.1     .12       0  4162.4      .1       0  4218.6     .12       0
  4544.2      .1       0  4969.4     .07       0  4998.4      .1       0
  5560.3     .05       0  5795.9     .12       0
Bank Sta=4969.4,4998.4
XS Rating Curve= 0 ,0
Exp/Cntr=0.3,0.1

Type RM Length L Ch R = 1 ,7850    ,970,970,970
BEGIN DESCRIPTION:
HOSTETTER CREEK 15.0
END DESCRIPTION:
XS GIS Cut Line= 4
      3802563.43     10174519.27      3801928.09      10174870.8
      3801866.83     10174903.37      3801307.15     10176320.79
#Sta/Elev= 30
  4273.9  254.71  4449.6  247.68    4634   232.7  4695.9   229.2  4861.9  217.86
  4954.6   213.7  4970.6  214.66  4977.4  213.08  4984.5  208.59  5000.3  208.59
  5008.6  213.97  5022.9  215.51  5052.5  214.18  5219.6  215.56  5529.2  212.87
  5628.1  214.94  5658.2  214.77    5669  213.17  5722.7  214.51    5798  213.61
    5970  216.27  6031.5  219.92  6060.9   218.6  6077.5  220.77  6144.8  223.56
  6260.3  231.53  6361.2  234.87  6547.9  245.11  6572.1  243.51  6593.3  246.07
#Mann= 5 ,-1 , 0
  4273.9     .12       0  4695.9      .1       0  4977.4     .07       0
  5008.6      .1       0  6031.5     .12       0
#XS Ineff= 2 , 0
       0                  6036.6       0  220.05
Permanent Ineff=
       F       F
Bank Sta=4977.4,5008.6
XS Rating Curve= 0 ,0
Exp/Cntr=0.3,0.1

Type RM Length L Ch R = 1 ,6880    ,913,913,913
BEGIN DESCRIPTION:
HOSTETTER CREEK 13.0
END DESCRIPTION:
XS GIS Cut Line= 3
      3802513.73     10174272.19      3801559.82     10174135.13
      3800543.28     10175409.31
#Sta/Elev= 30
  4036.3  254.08  4133.2  250.96  4335.2  241.18  4466.5  232.07  4608.9  219.39
  4688.8  213.75  4759.5  210.68  4981.8  210.97  4990.4   205.6  5006.6   205.6
  5012.6  210.82  5091.1  210.45  5111.9  208.87  5151.6  210.87  5183.9  211.92
  5204.7  214.07  5219.2  213.41    5240  215.23  5390.5  218.78  5653.1  217.48
  5710.7  220.17  5866.1  222.78  5894.9  222.73  5938.1  220.71  5999.6     221
  6186.3  221.88  6378.4  227.23  6442.5  230.58  6471.3  233.89    6630  244.17
#Mann= 7 ,-1 , 0
  4036.3     .05       0  4608.9      .1       0  4981.8     .07       0
  5012.6      .1       0  5151.6     .05       0  5999.6     .12       0
  6378.4     .05       0
Bank Sta=4981.8,5012.6
XS Rating Curve= 0 ,0
Exp/Cntr=0.3,0.1

Type RM Length L Ch R = 1 ,5967    ,1056,1056,1056
BEGIN DESCRIPTION:
HOSTETTER CREEK 11.0
END DESCRIPTION:
XS GIS Cut Line= 3
      3802131.83     10173117.66      3801177.91     10173659.35
      3800378.31     10175253.12
#Sta/Elev= 30
    3903   255.2  4083.9  248.85  4164.7  241.31  4279.4  227.39  4471.8  209.62
    4978  209.75  4988.1  206.82  4988.4   203.5  4988.9     203  5005.5     203
    5015  207.18  5024.3  206.65  5031.7  203.82  5037.3  208.65  5054.1  206.22
  5059.7  208.95    5082  210.27  5203.3  208.27  5309.1  209.58  5567.8  213.16
  5685.1   216.6  5841.5  214.77  5874.6  217.47    5949  218.32    6003   219.9
    6104  222.96  6232.4   223.2  6455.8  227.88  6656.8  237.63  6783.1  247.08
#Mann= 7 ,-1 , 0
    3903     .05       0  4279.4      .1       0    4978     .07       0
  5037.3      .1       0  5309.1     .05       0    5949     .12       0
    6003     .05       0
Bank Sta=4978,5037.3
XS Rating Curve= 0 ,0
Exp/Cntr=0.3,0.1

Type RM Length L Ch R = 1 ,4911    ,963,963,963
BEGIN DESCRIPTION:
HOSTETTER CREEK 9.0
END DESCRIPTION:
XS GIS Cut Line= 3
      3800855.76     10172232.26      3800787.86     10173172.11
      3799987.73     10174141.95
#Sta/Elev= 30
  4057.7  240.09  4146.7   231.9  4272.6  225.17  4294.3  224.39  4447.5  217.66
  4728.3  206.84    4833  206.53  4898.7  207.48  4932.3  206.26  4938.8  206.91
  4958.9  206.55  4978.9  203.14  4980.4  200.16  4997.4  200.16    5000  202.41
  5006.5  202.45    5013  206.41  5020.8  207.91  5076.8  206.75  5127.7  207.54
  5183.7  206.66    5241  209.46  5283.9  210.22  5389.5  214.63  5574.6  219.68
  5737.6  221.34  5829.9   220.9  5979.8  223.91  6113.9  229.16  6257.3  238.75
#Mann= 6 ,-1 , 0
  4057.7     .05       0  4272.6     .12       0  4294.3     .05       0
    4833      .1       0  4958.9     .07       0    5013     .05       0
Bank Sta=4958.9,5013
XS Rating Curve= 0 ,0
Exp/Cntr=0.3,0.1

Type RM Length L Ch R = 1 ,3948    ,945,945,945
BEGIN DESCRIPTION:
HOSTETTER CREEK 7.0
END DESCRIPTION:
XS GIS Cut Line= 3
      3800604.02     10172145.45      3800233.45     10172896.61
      3799874.85     10174081.23
#Sta/Elev= 30
  4162.4  240.92  4343.7  223.64  4349.3  225.27  4371.7  224.51  4388.6  222.53
  4455.9  219.82  4549.2  212.44  4596.2   209.3  4720.9  205.71  4737.4  205.17
  4753.4  202.26  4888.1  206.53  4971.5  205.71  4977.9  202.13  4983.5  202.08
  4991.1  199.14  5008.2  199.14  5015.1  202.67  5025.6  204.62  5046.4     200
  5056.9   199.7  5066.6  200.09  5071.8  203.44  5077.8  204.43  5312.8  208.95
  5422.6  214.48  5661.8  219.14  5846.3  220.23  6073.8  227.69  6237.7  237.39
#Mann= 7 ,-1 , 0
  4162.4     .05       0  4549.2      .1       0  4720.9     .05       0
  4971.5     .04       0  5025.6     .05       0  5661.8     .12       0
  5846.3     .05       0
Bank Sta=4971.5,5025.6
XS Rating Curve= 0 ,0
Exp/Cntr=0.3,0.1

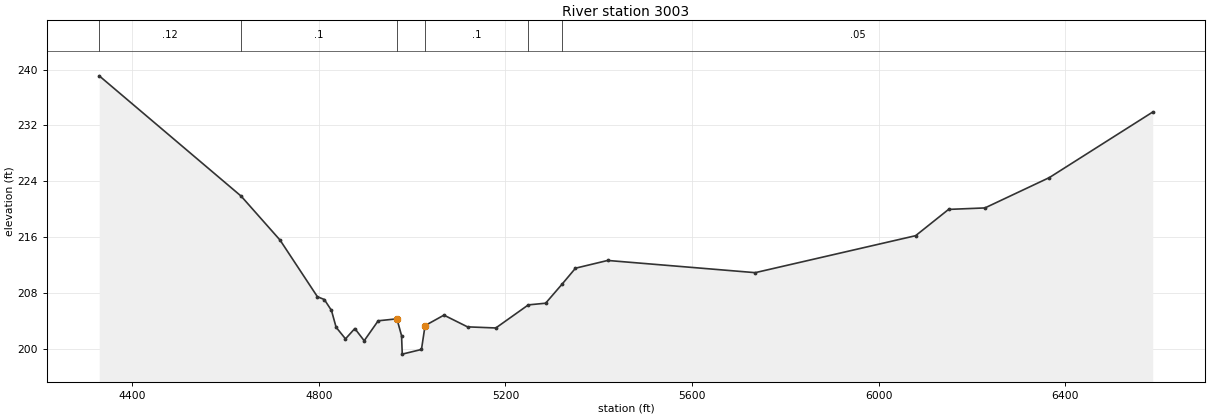
Type RM Length L Ch R = 1 ,3003    ,865,865,865
BEGIN DESCRIPTION:
HOSTETTER CREEK 5.0
END DESCRIPTION:
XS GIS Cut Line= 3
        3799545.     10171824.26      3799500.29     10172493.67
      3799735.97     10174063.88
#Sta/Elev= 30
  4329.1  239.11  4633.4  221.86  4716.8  215.56  4796.9  207.44  4811.7  207.04
    4827  205.48    4837  203.06  4857.1   201.4  4877.1  202.88  4897.2  201.13
  4927.2  203.99  4967.3  204.27  4977.3  201.86  4978.8  199.21    5020  199.88
  5027.7   203.3  5068.2   204.8  5118.7  203.12  5179.4  202.96  5249.1  206.27
  5286.2  206.51  5321.8  209.27  5350.2  211.53  5419.3  212.64  5735.5  210.89
  6079.4  216.19  6150.1  219.96    6228  220.17  6366.1  224.52  6587.8  233.92
#Mann= 6 ,-1 , 0
  4329.1     .12       0  4633.4      .1       0  4967.3     .07       0
  5027.7      .1       0  5249.1     .12       0  5321.8     .05       0
Bank Sta=4967.3,5027.7
XS Rating Curve= 0 ,0
Exp/Cntr=0.3,0.1