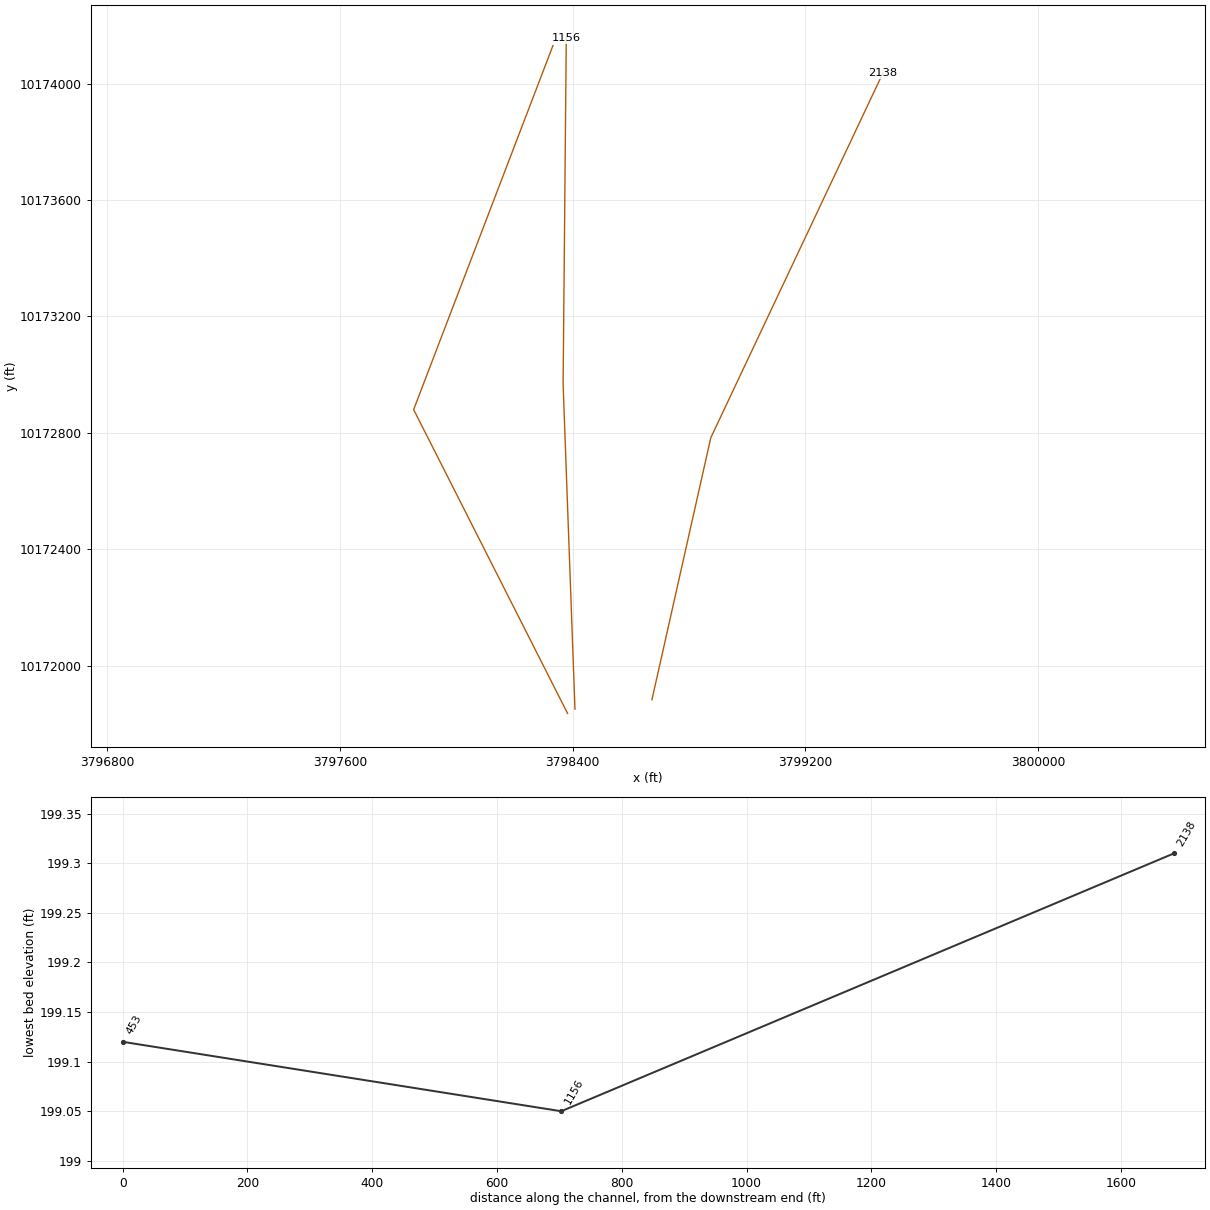
HEC-RAS study HOSTETTER CREEK.prj: HOSTETTER CREEK Base Level Engineering

--- HOSTETTER CREEK.g01 (geometry) --- (continued)

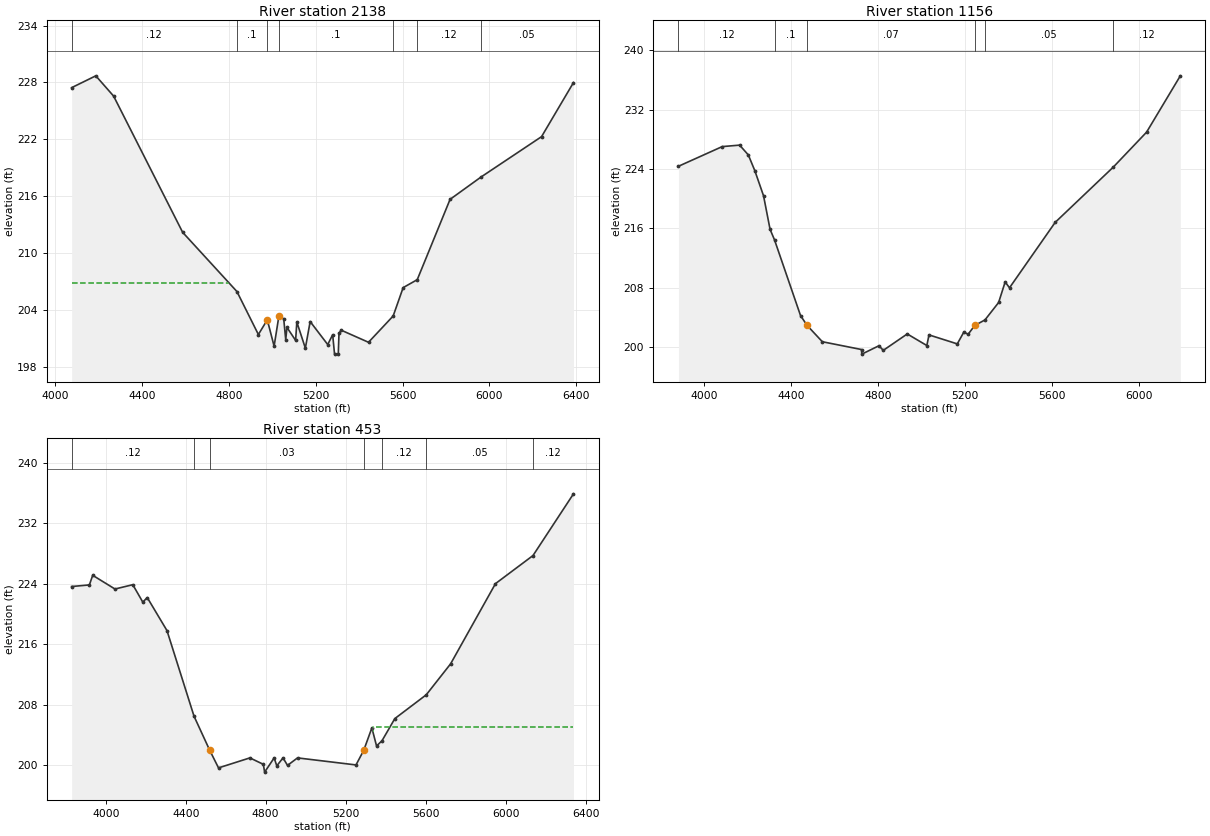
Type RM Length L Ch R = 1 ,2138    ,982,982,982
BEGIN DESCRIPTION:
HOSTETTER CREEK 3.0
END DESCRIPTION:
XS GIS Cut Line= 3
      3798672.39     10171882.56       3798874.7     10172783.11
      3799466.48     10174036.98
#Sta/Elev= 30
    4077  227.44  4188.2  228.69  4270.2  226.55  4587.9  212.17  4837.6  205.92
  4936.4  201.38  4977.4  202.93  5008.8  200.15  5030.9  203.34    5053  203.03
  5062.3  200.84  5067.8  202.13  5107.8  200.76  5113.3   202.7  5152.6  199.94
  5174.7  202.75  5255.5  200.32  5278.3  201.36  5286.9  199.31  5304.1  199.31
  5307.4  201.53  5318.3  201.83  5443.2  200.56  5556.8  203.34  5602.6  206.33
  5667.5  207.17  5818.6  215.65  5961.2  218.01  6239.6  222.27  6386.5  227.98
#Mann= 7 ,-1 , 0
    4077     .12       0  4837.6      .1       0  4977.4     .07       0
  5030.9      .1       0  5556.8     .05       0  5667.5     .12       0
  5961.2     .05       0
#XS Ineff= 2 , 0
       0  4803.2  206.87  5630.9       0  206.62
Permanent Ineff=
       F       F
Bank Sta=4977.4,5030.9
XS Rating Curve= 0 ,0
Exp/Cntr=0.3,0.1

Type RM Length L Ch R = 1 ,1156    ,703,703,703
BEGIN DESCRIPTION:
HOSTETTER CREEK 1.0
END DESCRIPTION:
XS GIS Cut Line= 3
      3798407.84     10171850.31      3798367.09     10172966.36
      3798377.94     10174156.11
#Sta/Elev= 30
  3883.2  224.37  4084.1  227.02  4164.2  227.22  4204.2   225.9  4234.2  223.77
  4274.2  220.39  4304.2  215.87  4324.6  214.45  4444.3  204.24  4474.4  202.92
  4544.4  200.72  4724.5  199.67  4725.9  199.05  4804.6  200.18  4824.6  199.56
  4934.7  201.77  5024.7  200.21  5034.7  201.64  5164.7  200.43  5194.7  202.02
  5214.7  201.73  5244.7  202.91  5291.9  203.66  5354.7  206.01  5384.7  208.78
  5404.7  207.99  5614.7  216.81  5881.8  224.26  6034.8  228.97  6189.8  236.56
#Mann= 6 ,-1 , 0
  3883.2     .12       0  4324.6      .1       0  4474.4     .07       0
  5244.7      .1       0  5291.9     .05       0  5881.8     .12       0
Bank Sta=4474.4,5244.7
XS Rating Curve= 0 ,0
Exp/Cntr=0.3,0.1

Type RM Length L Ch R = 1 ,453     ,0,0,0
BEGIN DESCRIPTION:
HOSTETTER CREEK 1.5
END DESCRIPTION:
XS GIS Cut Line= 3
      3798382.36     10171835.69      3797853.26     10172879.89
      3798332.11     10174131.09
#Sta/Elev= 30
  3829.4  223.63  3918.2  223.84  3934.8  225.11  4046.2   223.3  4135.3  223.87
  4185.4  221.57  4207.7  222.17  4306.3  217.81  4441.7   206.5  4519.5  202.04
  4564.1  199.68  4721.1     201  4788.3  200.15  4794.8  199.12  4842.4     201
  4855.6  199.95  4886.9     201  4909.2  200.01  4959.4     201  5251.8  200.07
  5290.4  201.99  5331.2  204.96  5354.6  202.58  5381.8  203.26  5446.1  206.19
  5603.2  209.33  5725.1  213.42  5949.5  224.01  6137.2  227.72  6339.7  235.87
#Mann= 7 ,-1 , 0
  3829.4     .12       0  4441.7      .1       0  4519.5     .03       0
  5290.4      .1       0  5381.8     .12       0  5603.2     .05       0
  6137.2     .12       0
#XS Ineff= 2 , 0
       0                  5336.6       0  205.02
Permanent Ineff=
       F       F
Bank Sta=4519.5,5290.4
XS Rating Curve= 0 ,0
Exp/Cntr=0.3,0.1

Chan Stop Cuts=-1
Use User Specified Reach Order=0
Composite Channel Slope=5