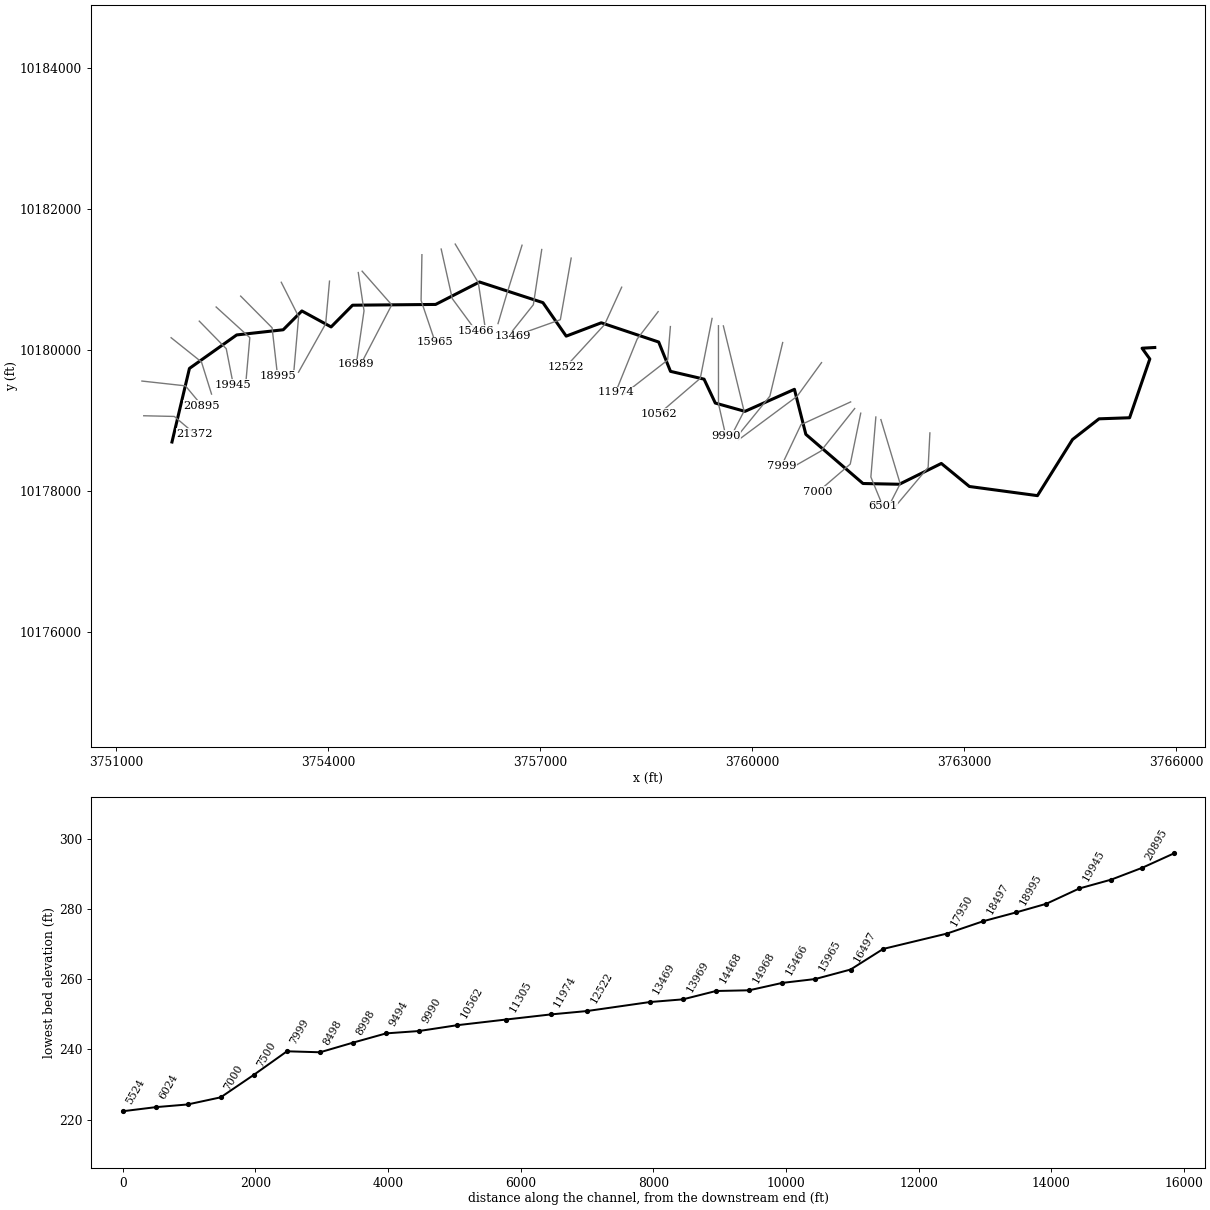
--- KELLY BRANCH.prj (project) ---

Proj Title=KELLY BRANCH Base Level Engineering
Current Plan=p01
Default Exp/Contr=0.3,0.1
English Units
Geom File=g01
Flow File=f01
Flow File=f02
Plan File=p01
Y Axis Title=Elevation
X Axis Title(PF)=Main Channel Distance
X Axis Title(XS)=Station
BEGIN DESCRIPTION:
KELLY BRANCH
END DESCRIPTION:
DSS Export Rating Curves= 0
DSS Export Rating Curve Sorted= 0
DSS Export Volume Flow Curves= 0
DXF OffsetX= 0
DXF OffsetY= 0
DXF ScaleX= 1
DXF ScaleY= 10

--- KELLY BRANCH.p01 (plan) ---

Plan Title=Multiple Run
Short Identifier=Multiple
Geom File=g01
Flow File=f01
Subcritical Flow
K Sum by GR= 0
Std Step Tol= 0.01
Critical Tol= 0.01
Num of Std Step Trials= 20
Max Error Tol= 0.3
Flow Tol Ratio= 0.001
Split Flow NTrial= 30
Split Flow Tol= 0.02
Split Flow Ratio= 0.02
Log Output Level= 0
Friction Slope Method= 1
Unsteady Friction Slope Method= 2
Unsteady Bridges Friction Slope Method= 1
Parabolic Critical Depth
Global Vel Dist=  1 , 1 , 1
Global Log Level= 0
CheckData=True
Encroach Param= -1, 0, 0, 0
BEGIN DESCRIPTION:
Multiple Run
END DESCRIPTION:

--- KELLY BRANCH.f01 (steady flow) ---

Flow Title=Multiple
Program Version=4.10
Number of Profiles= 7
Profile Names=10-year,25-year,50-year,1pct_min,100-year,1pct_plu,500-year
River Rch & RM=KELLY BRANCH,Reach-1         ,21372
     276     357     468     203     614    1854    1084
River Rch & RM=KELLY BRANCH,Reach-1         ,19448
     711     966    1309     583    1760    5315    3294
River Rch & RM=KELLY BRANCH,Reach-1         ,12522
     909    1238    1679     747    2257    6816    4216
River Rch & RM=KELLY BRANCH,Reach-1         ,5027
    1119    1546    2117     951    2872    8673    5466
Boundary for River Rch & Prof#=KELLY BRANCH,Reach-1         , 1
Up Type= 0
Dn Type= 3
Dn Slope=0.005
Boundary for River Rch & Prof#=KELLY BRANCH,Reach-1         , 2
Up Type= 0
Dn Type= 3
Dn Slope=0.005
Boundary for River Rch & Prof#=KELLY BRANCH,Reach-1         , 3
Up Type= 0
Dn Type= 3
Dn Slope=0.005
Boundary for River Rch & Prof#=KELLY BRANCH,Reach-1         , 4
Up Type= 0
Dn Type= 3
Dn Slope=0.005
Boundary for River Rch & Prof#=KELLY BRANCH,Reach-1         , 5
Up Type= 0
Dn Type= 3
Dn Slope=0.005
Boundary for River Rch & Prof#=KELLY BRANCH,Reach-1         , 6
Up Type= 0
Dn Type= 3
Dn Slope=0.005
Boundary for River Rch & Prof#=KELLY BRANCH,Reach-1         , 7
Up Type= 0
Dn Type= 3
Dn Slope=0.005
DSS Import GetInterval= 0
DSS Import GetPeak= 0
DSS Import FillOption= 0

--- KELLY BRANCH.f02 (steady flow) ---

Flow Title=Orig_BLE_Flow
Program Version=4.10
Number of Profiles= 7
Profile Names=10-year,25-year,50-year,1pct_min,100-year,1pct_plu,500-year
River Rch & RM=KELLY BRANCH,Reach-1         ,21372
     276     350     407     156     472    1425     630
River Rch & RM=KELLY BRANCH,Reach-1         ,19448
     711     947    1138     448    1354    4090    1915
River Rch & RM=KELLY BRANCH,Reach-1         ,12522
     909    1214    1460     575    1736    5242    2451
River Rch & RM=KELLY BRANCH,Reach-1         ,5027
    1119    1516    1841     731    2209    6670    3178
Boundary for River Rch & Prof#=KELLY BRANCH,Reach-1         , 1
Up Type= 0
Dn Type= 3
Dn Slope=0.005
Boundary for River Rch & Prof#=KELLY BRANCH,Reach-1         , 2
Up Type= 0
Dn Type= 3
Dn Slope=0.005
Boundary for River Rch & Prof#=KELLY BRANCH,Reach-1         , 3
Up Type= 0
Dn Type= 3
Dn Slope=0.005
Boundary for River Rch & Prof#=KELLY BRANCH,Reach-1         , 4
Up Type= 0
Dn Type= 3
Dn Slope=0.005
Boundary for River Rch & Prof#=KELLY BRANCH,Reach-1         , 5
Up Type= 0
Dn Type= 3
Dn Slope=0.005
Boundary for River Rch & Prof#=KELLY BRANCH,Reach-1         , 6
Up Type= 0
Dn Type= 3
Dn Slope=0.005
Boundary for River Rch & Prof#=KELLY BRANCH,Reach-1         , 7
Up Type= 0
Dn Type= 3
Dn Slope=0.005
DSS Import GetInterval= 0
DSS Import GetPeak= 0
DSS Import FillOption= 0

--- KELLY BRANCH.g01 (geometry) ---

Geom Title=Existing Conditions
Program Version=4.10

River Reach=KELLY BRANCH    ,Reach-1
Reach XY= 30
      3751792.93     10178696.68      3752040.07     10179740.15
      3752708.31     10180214.87      3753366.73     10180288.17
       3753630.7     10180555.02       3754044.4     10180328.32
      3754347.93     10180636.53      3755523.02     10180647.39
        3756144.     10180965.65      3757041.31     10180672.98
      3757370.74     10180197.98      3757867.13      10180387.1
      3758679.22     10180114.31      3758846.37     10179698.55
      3759321.13     10179587.95      3759480.14     10179248.89
      3759899.39     10179131.09      3760599.83     10179443.72
      3760761.35     10178805.44      3761569.87     10178108.17
      3762083.98     10178097.59      3762678.29      10178392.5
      3763075.23     10178065.94      3764038.14     10177936.04
      3764534.64     10178732.26      3764909.64     10179025.43
      3765342.02     10179040.54      3765628.04     10179873.95
      3765518.23     10180026.84      3765698.23     10180036.84

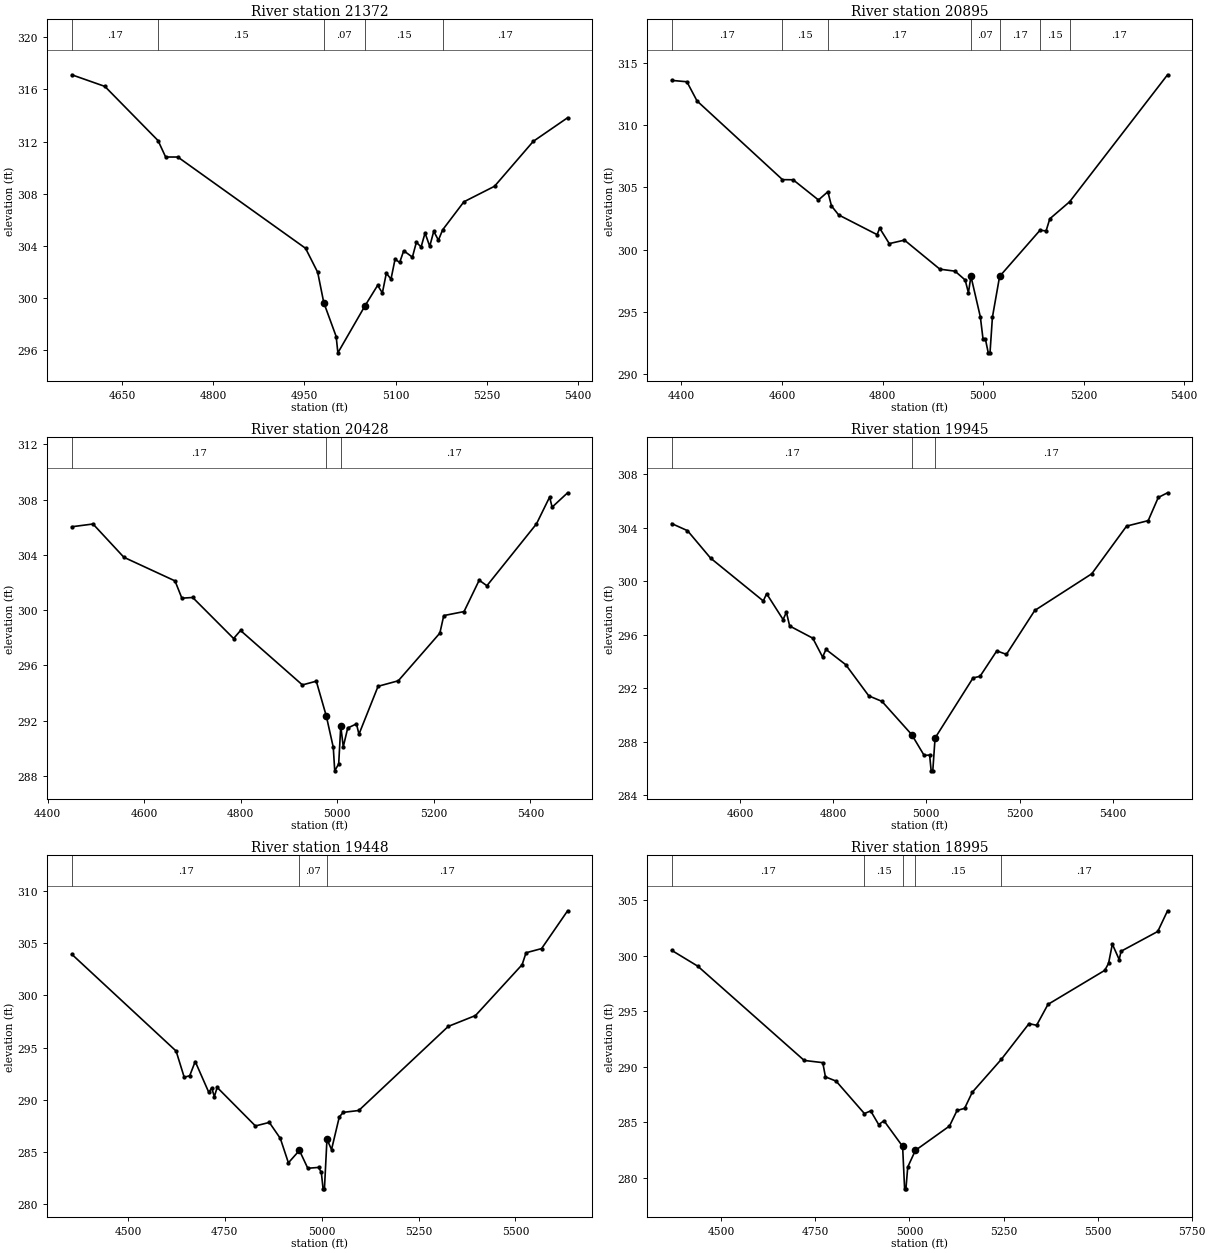
Type RM Length L Ch R = 1 ,21372   ,477,477,477
BEGIN DESCRIPTION:
KELLY BRANCH 39.0
END DESCRIPTION:
XS GIS Cut Line= 3
      3751393.49     10179068.81      3751825.88     10179059.15
      3752117.83     10178811.09
#Sta/Elev= 30
  4567.5  317.12  4621.9  316.23  4709.4  312.08  4721.9  310.82  4741.9  310.82
    4952  303.83    4972  301.99    4982  299.67  5002.4  297.07  5005.2  295.82
  5049.8  299.42  5070.6  300.99  5078.4  300.41  5084.9  301.92  5092.6  301.47
  5099.2  302.98  5106.9  302.75  5113.5  303.64  5127.8  303.15  5134.3  304.29
  5142.1  303.93  5148.6     305  5156.3  303.98  5162.9  305.13  5170.6  304.45
  5177.5  305.24  5212.5  307.39  5262.9  308.58  5326.6  312.02  5383.1  313.83
#Mann= 5 ,-1 , 0
  4567.5     .17       0  4709.4     .15       0    4982     .07       0
  5049.8     .15       0  5177.5     .17       0
#XS Ineff= 2 , 0
       0                  5084.9       0  301.92
Permanent Ineff=
       F       F
Bank Sta=4982,5049.8
XS Rating Curve= 0 ,0
Exp/Cntr=0.3,0.1

Type RM Length L Ch R = 1 ,20895   ,467,467,467
BEGIN DESCRIPTION:
KELLY BRANCH 38.0
END DESCRIPTION:
XS GIS Cut Line= 3
      3751367.87     10179561.07      3751983.32     10179493.01
      3752217.83      10179211.1
#Sta/Elev= 30
  4380.8  313.58    4411  313.47  4431.2  311.93  4601.1  305.62  4622.2  305.61
  4672.6  303.99  4691.3  304.65  4698.5  303.51  4712.8  302.79  4789.2  301.21
  4794.3  301.73  4813.4  300.49  4843.6  300.77    4914  298.44  4944.2  298.28
  4964.3  297.57  4970.8  296.55  4975.8  297.87  4994.5  294.61  4999.8  292.84
  5004.5  292.84  5010.2  291.73  5013.7  291.73  5018.5  294.59  5032.8  297.86
  5113.1  301.56  5125.2  301.51  5132.6  302.48  5172.1  303.85  5366.7  314.03
#Mann= 7 ,-1 , 0
  4380.8     .17       0  4601.1     .15       0  4691.3     .17       0
  4975.8     .07       0  5032.8     .17       0  5113.1     .15       0
  5172.1     .17       0
#XS Ineff= 2 , 0
       0  4975.8  297.87               0
Permanent Ineff=
       F       F
Bank Sta=4975.8,5032.8
XS Rating Curve= 0 ,0
Exp/Cntr=0.3,0.1

Type RM Length L Ch R = 1 ,20428   ,483,483,483
BEGIN DESCRIPTION:
KELLY BRANCH 37.0
END DESCRIPTION:
XS GIS Cut Line= 3
      3751780.87     10180175.47      3752210.31     10179831.68
      3752352.64      10179376.2
#Sta/Elev= 30
  4449.9  306.03  4493.9  306.23  4557.9  303.82  4663.8  302.11    4678  300.86
  4700.4  300.91  4785.2  297.94  4799.6  298.52  4927.7  294.58  4956.5  294.85
  4977.3  292.32  4991.7  290.06  4994.7  288.36  5002.9  288.86  5007.2  291.59
  5012.4   290.1  5021.6  291.46  5039.7  291.76  5044.9  291.01  5084.5  294.48
  5126.4  294.88  5212.5  298.33  5220.6   299.6  5262.6  299.89    5294  302.16
    5310  301.76  5412.7  306.24  5439.9  308.18  5445.1  307.45  5477.2  308.49
#Mann= 3 , 0 , 0
  4449.9     .17       0  4977.3     .07       0  5007.2     .17       0
Bank Sta=4977.3,5007.2
XS Rating Curve= 0 ,0
Exp/Cntr=0.3,0.1

Type RM Length L Ch R = 1 ,19945   ,497,497,497
BEGIN DESCRIPTION:
KELLY BRANCH 36.0
END DESCRIPTION:
XS GIS Cut Line= 3
      3752179.27      10180410.5      3752560.84      10180019.4
      3752660.04     10179511.49
#Sta/Elev= 30
  4453.6   304.3  4487.5  303.77    4537  301.72  4650.1  298.52  4657.3  299.06
  4692.6  297.13  4699.7  297.68  4706.7  296.65  4756.3  295.74  4777.4  294.33
  4784.6   294.9    4827  293.76  4876.5  291.43  4904.7  291.02  4968.5  288.54
  4995.3  286.98    5007  287.01  5010.3  285.83  5013.8  285.83  5018.7  288.28
  5100.2  292.77  5115.2  292.89  5151.1  294.79  5171.8  294.53  5232.6  297.81
  5354.9  300.55  5429.6  304.11    5476  304.52  5497.6  306.25  5517.5   306.6
#Mann= 3 , 0 , 0
  4453.6     .17       0  4968.5     .07       0  5018.7     .17       0
Bank Sta=4968.5,5018.7
XS Rating Curve= 0 ,0
Exp/Cntr=0.3,0.1

Type RM Length L Ch R = 1 ,19448   ,453,453,453
BEGIN DESCRIPTION:
KELLY BRANCH 35.0
END DESCRIPTION:
XS GIS Cut Line= 3
      3752417.82      10180611.1      3752894.34     10180176.41
      3752838.51     10179544.17
#Sta/Elev= 30
    4355  303.93  4624.3  294.66  4645.2  292.15  4659.4   292.3  4673.6  293.66
  4708.7   290.7  4716.2  291.14  4722.9  290.29  4730.3  291.18    4829  287.49
  4864.8  287.83  4893.2   286.3  4914.1  283.96  4942.5  285.15  4964.1  283.44
  4991.8  283.52    4999  283.06  5003.6  281.47  5007.1  281.47  5013.6  286.21
  5025.4  285.23  5045.5  288.36  5055.6  288.79  5095.7  288.97  5326.6  297.02
  5396.9  298.06  5517.3  302.93  5527.4  304.07  5567.5  304.47  5634.7  308.09
#Mann= 3 , 0 , 0
    4355     .17       0  4942.5     .07       0  5013.6     .17       0
Bank Sta=4942.5,5013.6
XS Rating Curve= 0 ,0
Exp/Cntr=0.3,0.1

Type RM Length L Ch R = 1 ,18995   ,498,498,498
BEGIN DESCRIPTION:
KELLY BRANCH 34.0
END DESCRIPTION:
XS GIS Cut Line= 3
      3752764.59     10180765.69      3753209.29     10180316.76
      3753287.07     10179635.28
#Sta/Elev= 30
  4368.1  300.48  4437.3  299.06  4720.2  290.58  4769.6  290.38  4776.7   289.1
    4805  288.72  4880.3   285.8  4896.9  286.04  4918.2  284.81  4932.3  285.15
  4981.8  282.85  4987.1  279.03  4990.6  279.03  4995.4  280.99  5015.8  282.49
  5106.4  284.68  5126.5  286.08  5146.6  286.27  5166.8  287.71  5244.2  290.68
  5317.7  293.89  5337.9  293.74  5368.1  295.62    5519  298.68  5529.1  299.31
  5539.2  301.04  5557.4  299.65  5562.4   300.4  5659.9  302.18  5685.9  304.04
#Mann= 5 ,-1 , 0
  4368.1     .17       0  4880.3     .15       0  4981.8     .07       0
  5015.8     .15       0  5244.2     .17       0
Bank Sta=4981.8,5015.8
XS Rating Curve= 0 ,0
Exp/Cntr=0.3,0.1

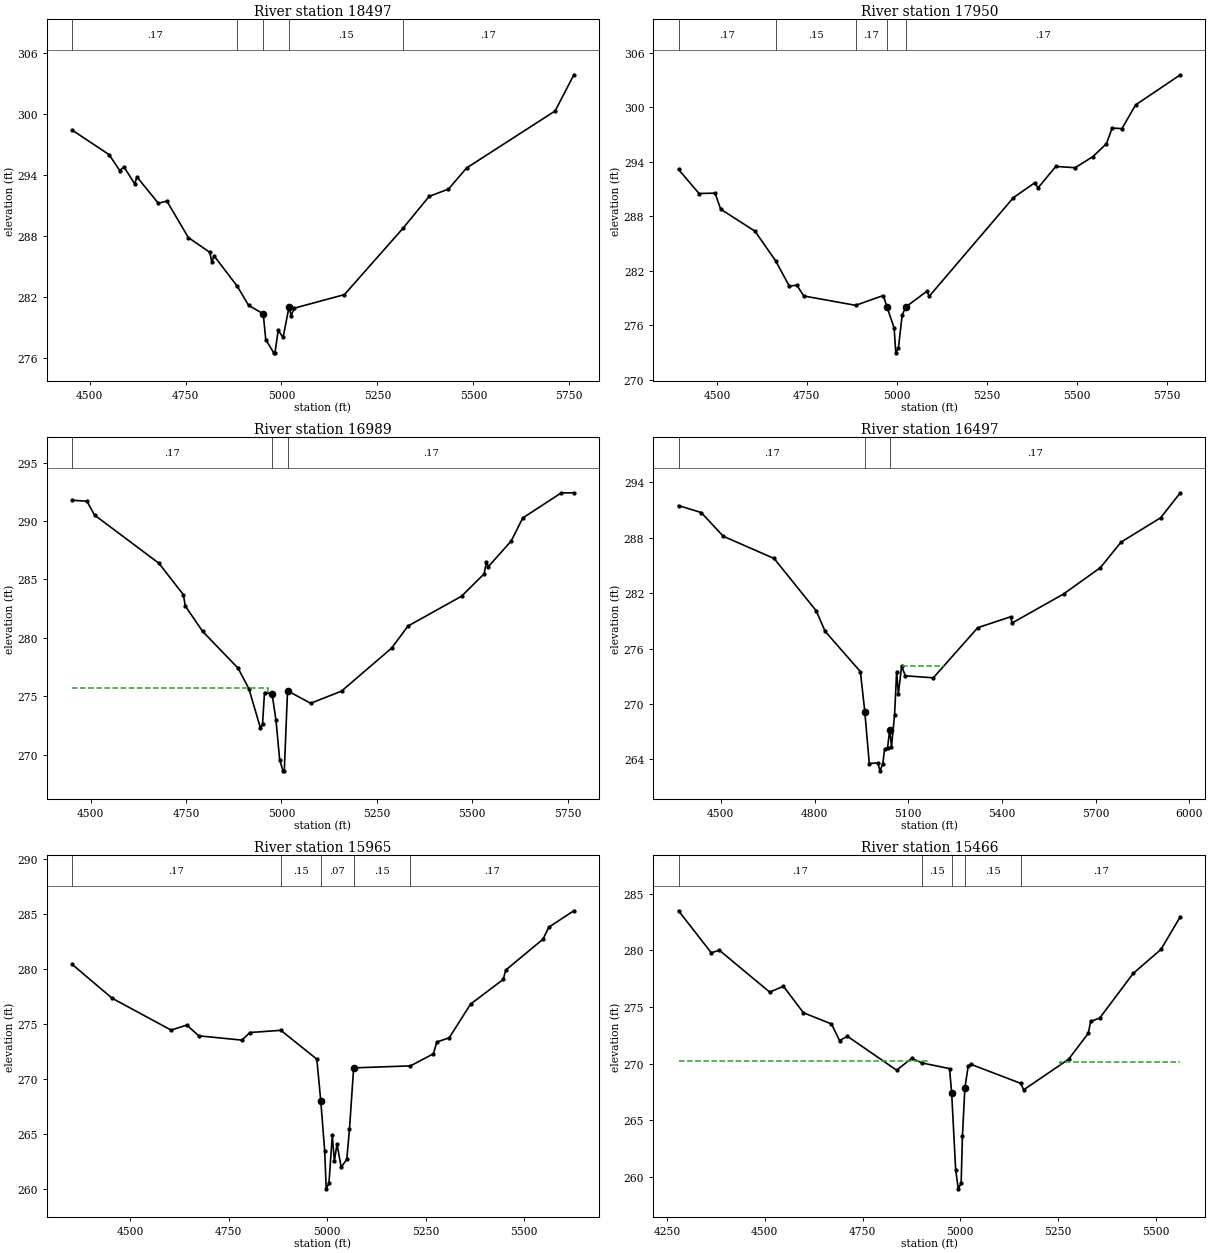
Type RM Length L Ch R = 1 ,18497   ,547,547,547
BEGIN DESCRIPTION:
KELLY BRANCH 33.0
END DESCRIPTION:
XS GIS Cut Line= 3
      3753339.31     10180961.73      3753584.69     10180474.42
      3753518.82     10179715.58
#Sta/Elev= 30
  4454.4  298.39  4550.8  295.98  4578.7  294.41  4589.5  294.78  4617.7   293.1
  4623.3  293.79    4679  291.21  4701.4  291.41  4757.4  287.83  4812.9  286.39
  4818.5  285.44  4824.6  286.02  4884.8  283.05  4914.2  281.18  4952.4  280.34
    4959  277.82  4979.6  276.51  4983.1  276.51  4991.4  278.72  5004.2  278.02
  5019.8  281.05  5024.9  280.17  5033.5   280.9    5164  282.23  5316.9  288.76
  5384.8  291.88    5435  292.59    5482  294.66    5713  300.27  5761.7  303.82
#Mann= 5 ,-1 , 0
  4454.4     .17       0  4884.8     .15       0  4952.4     .07       0
  5019.8     .15       0  5316.9     .17       0
Bank Sta=4952.4,5019.8
XS Rating Curve= 0 ,0
Exp/Cntr=0.3,0.1

Type RM Length L Ch R = 1 ,17950   ,961,961,961
BEGIN DESCRIPTION:
KELLY BRANCH 32.0
END DESCRIPTION:
XS GIS Cut Line= 3
       3754021.9     10180977.77      3753967.53     10180373.61
      3753582.85     10179686.23
#Sta/Elev= 30
  4393.4  293.18  4450.3  290.53  4494.9  290.57  4510.6   288.8  4605.9  286.38
    4663  283.13  4701.3  280.33    4722  280.44  4741.5  279.25  4885.5  278.22
  4962.4   279.3  4972.4  278.07  4992.5  275.73    4997  272.99  5004.3  273.49
  5014.8  277.15  5025.1  278.05  5083.1  279.76  5090.2  279.23  5323.8  290.07
  5382.5  291.69  5392.5  291.16  5441.8  293.51  5495.5  293.37  5544.6  294.59
  5582.3     296  5598.2  297.73  5625.7  297.68  5663.3  300.28  5787.7   303.6
#Mann= 5 ,-1 , 0
  4393.4     .17       0    4663     .15       0  4885.5     .17       0
  4972.4     .07       0  5025.1     .17       0
Bank Sta=4972.4,5025.1
XS Rating Curve= 0 ,0
Exp/Cntr=0.3,0.1

Type RM Length L Ch R = 1 ,16989   ,492,492,492
BEGIN DESCRIPTION:
KELLY BRANCH 30.0
END DESCRIPTION:
XS GIS Cut Line= 3
      3754428.89     10181099.45      3754510.14      10180556.7
      3754400.05     10179798.45
#Sta/Elev= 30
  4451.2  291.77    4490  291.69  4510.2   290.5  4678.8  286.38  4742.8  283.69
    4748  282.72  4793.4  280.55  4886.3   277.4  4914.7  275.64    4945  272.26
  4950.4  272.65  4955.5  275.32  4975.4  275.21  4985.5  272.97  4995.3  269.55
  5003.9  268.62  5007.4  268.62  5015.8  275.47  5076.4   274.4  5157.3  275.44
  5288.6  279.12  5331.6  281.01  5471.9  283.56  5531.1  285.48    5537   286.5
  5542.1  286.09  5601.9  288.28  5632.2  290.25  5733.2   292.4  5766.2  292.41
#Mann= 3 , 0 , 0
  4451.2     .17       0  4975.4     .07       0  5015.8     .17       0
#XS Ineff= 2 , 0
       0  4965.2  275.67  5015.8       0  275.47
Permanent Ineff=
       F       F
Bank Sta=4975.4,5015.8
XS Rating Curve= 0 ,0
Exp/Cntr=0.3,0.1

Type RM Length L Ch R = 1 ,16497   ,532,532,532
BEGIN DESCRIPTION:
KELLY BRANCH 29.0
END DESCRIPTION:
XS GIS Cut Line= 3
      3754483.33     10181118.76      3754902.27     10180641.03
      3754454.52      10179779.2
#Sta/Elev= 30
  4364.6  291.49  4437.2  290.74  4507.8  288.17  4670.6  285.76  4805.4  280.09
  4833.9  277.87  4946.8   273.5    4961  269.16  4975.3  263.54  5002.8  263.62
  5009.5  262.75  5018.6   263.5  5024.3  265.11  5033.8  265.24  5040.8  267.22
  5046.4  265.34  5056.3  268.82  5062.9  273.48  5068.5  271.09  5078.8  274.11
  5090.6  273.05  5180.3  272.83  5322.6  278.26  5427.5  279.44  5433.2  278.78
  5597.2  281.91    5715  284.76  5781.4  287.53  5908.4  290.18  5971.2  292.88
#Mann= 3 , 0 , 0
  4364.6     .17       0    4961     .07       0  5040.8     .17       0
#XS Ineff= 2 ,-1
  5062.9  5078.8  273.48  5078.8    5212  274.11
Permanent Ineff=
       F       F
Bank Sta=4961,5040.8
XS Rating Curve= 0 ,0
Exp/Cntr=0.3,0.1

Type RM Length L Ch R = 1 ,15965   ,499,499,499
BEGIN DESCRIPTION:
KELLY BRANCH 28.0
END DESCRIPTION:
XS GIS Cut Line= 3
      3755329.38     10181352.64      3755317.43     10180704.85
      3755517.85     10180111.06
#Sta/Elev= 30
  4352.1  280.45  4453.7  277.37  4603.7  274.47  4643.7  274.93  4673.7  273.95
  4783.7  273.56  4803.7  274.25  4882.5  274.45  4973.8  271.83  4983.8  268.05
  4993.8  263.48  4997.6  260.05  5004.6  260.55  5013.1  264.91  5018.4  262.58
  5025.1  264.12  5035.6  262.01  5049.9  262.73  5056.8  265.49  5067.3  271.04
  5211.7  271.22  5270.1  272.32  5278.4  273.39  5310.1  273.77  5364.5  276.84
  5447.3  279.07  5453.6  279.92    5548  282.72  5563.4  283.83  5626.7  285.31
#Mann= 5 ,-1 , 0
  4352.1     .17       0  4882.5     .15       0  4983.8     .07       0
  5067.3     .15       0  5211.7     .17       0
Bank Sta=4983.8,5067.3
XS Rating Curve= 0 ,0
Exp/Cntr=0.3,0.1

Type RM Length L Ch R = 1 ,15466   ,498,498,498
BEGIN DESCRIPTION:
KELLY BRANCH 27.0
END DESCRIPTION:
XS GIS Cut Line= 3
      3755601.76     10181432.82       3755758.9     10180729.56
      3756092.04     10180275.96
#Sta/Elev= 30
  4279.4  283.48  4363.2  279.77  4383.7     280  4512.7   276.3  4547.6  276.82
  4598.8  274.48  4670.6  273.49  4691.1  272.03  4711.5   272.4  4837.2  269.41
  4875.5  270.45  4902.5  270.05  4972.5  269.55    4978  267.39  4988.2  260.62
  4994.9  258.94  5002.2  259.44  5005.5  263.57  5011.7  267.82  5020.2  269.76
  5026.4  269.94  5154.5  268.25  5162.2  267.68  5277.1  270.38  5327.3  272.66
  5333.5  273.72  5356.6  274.01  5442.2  277.95  5513.3  280.07  5562.8  282.96
#Mann= 5 ,-1 , 0
  4279.4     .17       0  4902.5     .15       0    4978     .07       0
  5011.7     .15       0  5154.5     .17       0
#XS Ineff= 2 , 0
       0  4916.5   270.2  5256.3       0  270.14
Permanent Ineff=
       F       F
Bank Sta=4978,5011.7
XS Rating Curve= 0 ,0
Exp/Cntr=0.3,0.1

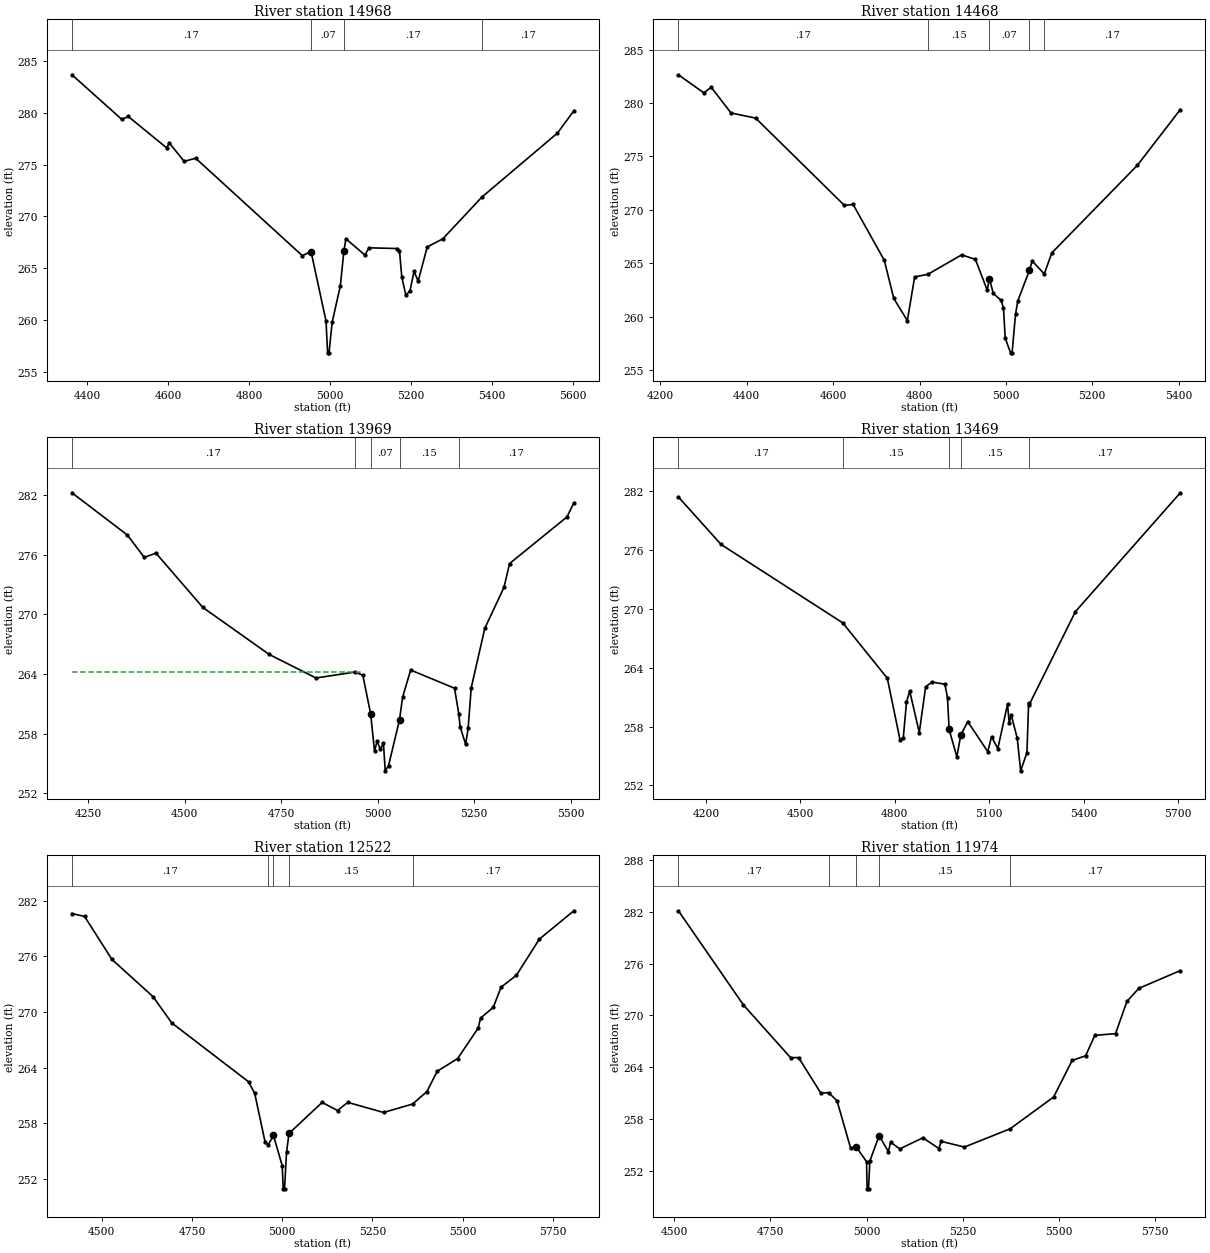
Type RM Length L Ch R = 1 ,14968   ,500,500,500
BEGIN DESCRIPTION:
KELLY BRANCH 26.0
END DESCRIPTION:
XS GIS Cut Line= 3
      3755800.44      10181503.3      3756127.13     10180956.33
      3756217.85      10180361.1
#Sta/Elev= 30
  4362.9  283.66  4486.2  279.35  4501.8  279.64  4597.1   276.6  4602.9   277.1
  4639.9  275.31  4668.3  275.61  4931.8  266.21  4953.2  266.61  4990.2  259.91
  4994.1  256.84  4997.6  256.84  5005.3  259.77  5025.6  263.32  5034.3  266.66
  5039.3  267.84  5086.2  266.27  5096.4  266.97  5166.4   266.9  5171.5  266.71
  5177.3  264.14  5187.4  262.39  5197.5  262.84  5207.6  264.69  5217.7  263.76
  5240.1  267.06  5278.4  267.83  5374.7  271.85  5561.7  278.04  5602.1  280.19
#Mann= 4 ,-1 , 0
  4362.9     .17       0  4953.2     .07       0  5034.3     .17       0
  5374.7     .17       0
#XS Ineff= 2 , 0
       0                  5039.3       0  267.84
Permanent Ineff=
       F       T
Bank Sta=4953.2,5034.3
XS Rating Curve= 0 ,0
Exp/Cntr=0.3,0.1

Type RM Length L Ch R = 1 ,14468   ,499,499,499
BEGIN DESCRIPTION:
KELLY BRANCH 25.0
END DESCRIPTION:
XS GIS Cut Line= 3
      3756745.82     10181487.27      3756520.49     10180763.22
      3756406.26     10180375.71
#Sta/Elev= 30
  4241.7  282.64  4300.6  280.95  4317.6  281.48  4363.4  279.07  4420.5  278.59
  4626.2  270.42  4646.2  270.52  4718.5  265.29  4740.4  261.73  4771.8  259.65
  4788.8  263.74  4819.7  263.99  4897.5   265.8  4929.5  265.38  4956.8   262.5
    4962  263.59  4970.8  262.19  4989.3  261.54  4994.5   260.8  4998.5  258.02
  5010.9  256.64  5014.4  256.64  5022.4  260.26  5027.7   261.5  5054.4  264.34
    5061  265.23  5088.9  264.02  5106.5  265.99  5304.6  274.18    5404  279.39
#Mann= 5 ,-1 , 0
  4241.7     .17       0  4819.7     .15       0    4962     .07       0
  5054.4     .15       0  5088.9     .17       0
#XS Ineff= 2 , 0
       0  4897.5   265.8    5061       0  265.23
Permanent Ineff=
       F       F
Bank Sta=4962,5054.4
XS Rating Curve= 0 ,0
Exp/Cntr=0.3,0.1

Type RM Length L Ch R = 1 ,13969   ,500,500,500
BEGIN DESCRIPTION:
KELLY BRANCH 24.0
END DESCRIPTION:
XS GIS Cut Line= 3
      3757024.61     10181426.32      3756905.96     10180643.06
      3756589.69     10180245.01
#Sta/Elev= 30
  4207.8  282.23  4351.4  277.98  4395.2  275.73  4425.5  276.16  4546.9   270.7
  4718.8  265.97  4840.2   263.6  4941.4   264.2  4961.6  263.87  4981.8     260
  4991.9  256.24  4998.5  257.23    5007  256.44    5015  257.05  5019.6  254.26
  5028.1  254.77  5056.6   259.4  5064.7  261.67  5085.5   264.4  5199.2  262.57
  5210.2  259.99  5213.6   258.7    5228  256.93  5234.4  258.53  5242.5  262.63
  5277.7   268.6  5327.4  272.72  5341.8  275.11  5490.8  279.81  5508.4  281.22
#Mann= 5 ,-1 , 0
  4207.8     .17       0  4941.4     .15       0  4981.8     .07       0
  5056.6     .15       0  5210.2     .17       0
#XS Ineff= 2 , 0
       0  4955.2  264.24  5085.5       0   264.4
Permanent Ineff=
       F       F
Bank Sta=4981.8,5056.6
XS Rating Curve= 0 ,0
Exp/Cntr=0.3,0.1

Type RM Length L Ch R = 1 ,13469   ,947,947,947
BEGIN DESCRIPTION:
KELLY BRANCH 23.0
END DESCRIPTION:
XS GIS Cut Line= 3
      3757441.21     10181304.62      3757287.85     10180430.88
      3756621.87     10180192.97
#Sta/Elev= 30
  4112.9   281.4  4248.5  276.56  4634.9  268.57  4776.4  262.93    4817  256.63
  4827.2  256.87  4837.4  260.47  4847.5  261.64    4878  257.39  4898.3  262.06
  4918.6  262.54  4959.2  262.32  4967.7  260.95  4972.7  257.71  4997.4  254.92
  5009.8  257.13  5031.9  258.51  5095.6  255.45  5107.5  256.97  5127.4  255.75
  5158.4  260.28  5163.7  258.36  5169.9  259.19  5189.2  256.82    5200  253.49
    5220  255.35  5225.3  260.41  5227.1  260.23    5374  269.72  5707.2  281.83
#Mann= 5 ,-1 , 0
  4112.9     .17       0  4634.9     .15       0  4972.7     .07       0
  5009.8     .15       0  5227.1     .17       0
#XS Ineff= 2 , 0
       0  4959.2  262.32               0
Permanent Ineff=
       F       F
Bank Sta=4972.7,5009.8
XS Rating Curve= 0 ,0
Exp/Cntr=0.3,0.1

Type RM Length L Ch R = 1 ,12522   ,548,548,548
BEGIN DESCRIPTION:
KELLY BRANCH 21.0
END DESCRIPTION:
XS GIS Cut Line= 3
      3758155.55     10180891.82      3757913.85     10180361.61
      3757367.47     10179766.35
#Sta/Elev= 30
  4417.3   280.6  4452.3  280.29    4528  275.66  4642.1  271.64  4693.7  268.82
  4906.6  262.47  4923.7  261.22  4952.7  255.93    4961  255.66  4975.7  256.68
    5000  253.42  5002.6  250.93  5006.3  250.93  5011.9  254.86  5018.7   256.9
  5110.6  260.25  5153.1  259.37  5181.5  260.25  5280.7  259.16  5361.1  260.07
    5401  261.42  5429.3   263.6    5486  264.97  5542.8  268.25  5549.6  269.34
  5584.7  270.49  5606.3  272.66  5648.8  273.95  5712.3  277.84    5808   280.9
#Mann= 5 ,-1 , 0
  4417.3     .17       0    4961     .15       0  4975.7     .07       0
  5018.7     .15       0  5361.1     .17       0
Bank Sta=4975.7,5018.7
XS Rating Curve= 0 ,0
Exp/Cntr=0.3,0.1

Type RM Length L Ch R = 1 ,11974   ,669,669,669
BEGIN DESCRIPTION:
KELLY BRANCH 20.0
END DESCRIPTION:
XS GIS Cut Line= 3
       3758671.8     10180545.14      3758374.99     10180156.77
      3758069.31     10179401.05
#Sta/Elev= 30
  4511.2   282.1  4680.2  271.21  4802.7  265.12  4823.5  265.13  4881.3  261.02
  4901.5  261.08  4923.3  260.14  4958.6  254.67  4973.1  254.81    5000   253.1
  5001.4  249.96  5005.1  249.96  5008.6  253.18  5032.7   256.1  5056.9  254.25
  5062.3  255.35  5086.4  254.58  5146.4  255.86  5188.3  254.61  5193.7  255.45
  5254.3  254.79    5373   256.9    5486  260.57  5534.2   264.8  5569.1  265.34
  5593.2   267.7  5646.9   267.9  5676.4  271.62  5707.3  273.13  5815.2  275.19
#Mann= 5 ,-1 , 0
  4511.2     .17       0  4901.5     .15       0  4973.1     .07       0
  5032.7     .15       0    5373     .17       0
Bank Sta=4973.1,5032.7
XS Rating Curve= 0 ,0
Exp/Cntr=0.3,0.1

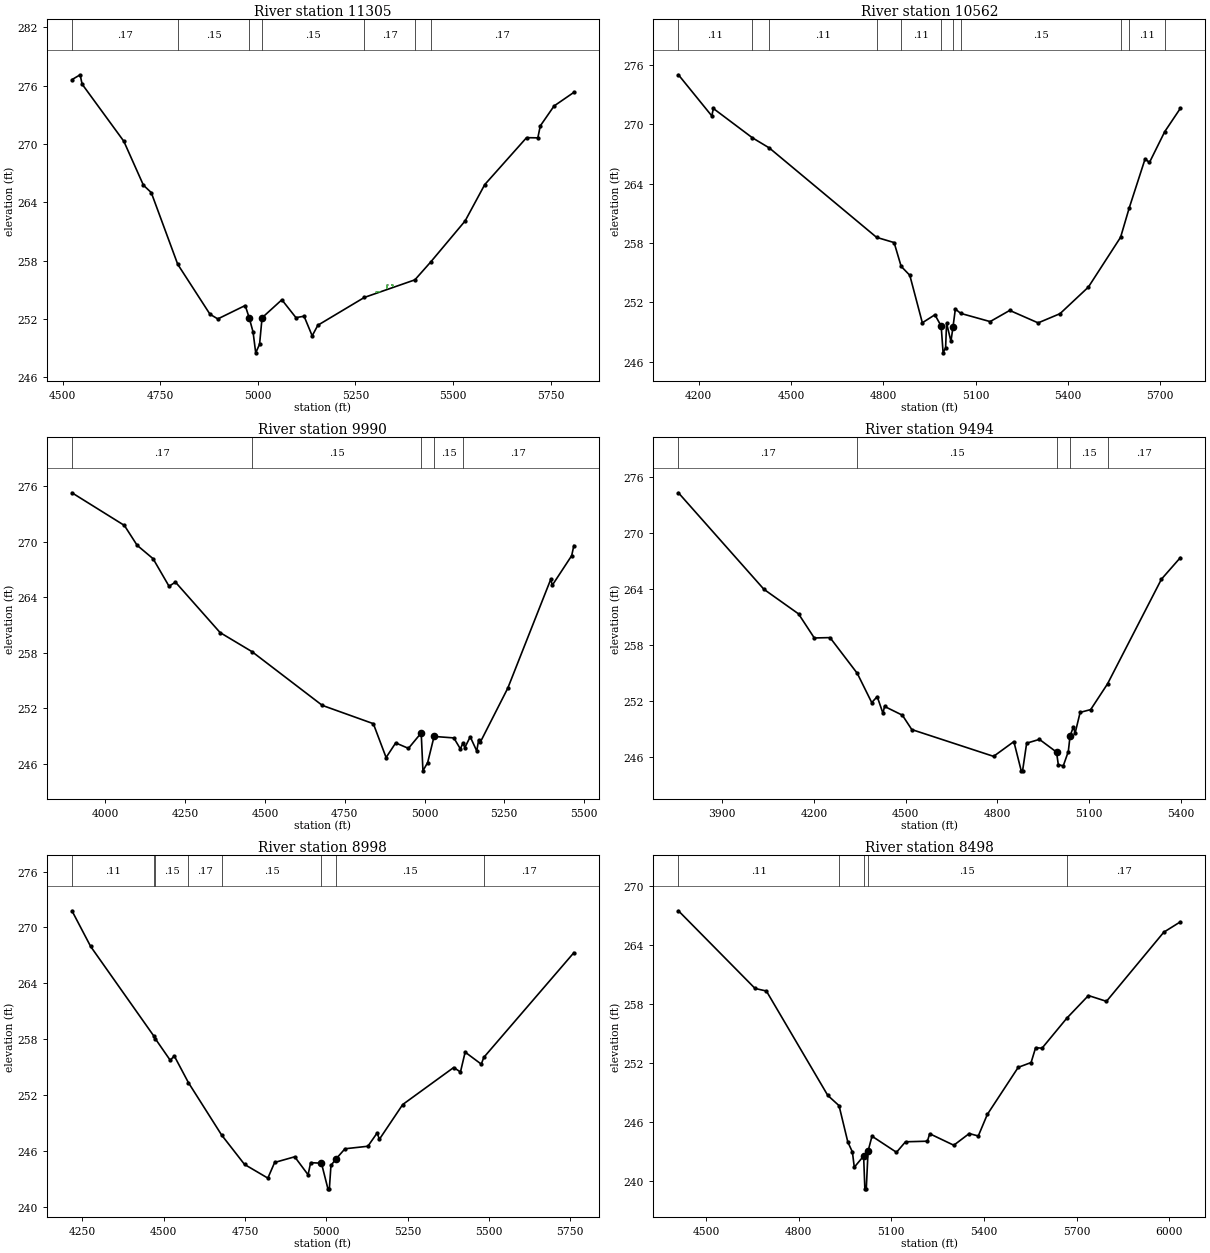
Type RM Length L Ch R = 1 ,11305   ,743,743,743
BEGIN DESCRIPTION:
KELLY BRANCH 19.0
END DESCRIPTION:
XS GIS Cut Line= 3
      3758844.82     10180333.57      3758806.34     10179858.82
      3758167.84     10179361.06
#Sta/Elev= 30
  4523.7  276.63  4544.7  277.13  4549.7  276.17  4656.6  270.29  4706.8  265.77
  4726.9  265.01  4794.7  257.63  4877.4  252.49  4897.4  252.01  4967.6  253.39
  4977.7  252.14  4987.7  250.67  4994.5  248.52  5004.4   249.4  5010.8  252.13
  5061.5  253.98  5097.6  252.14  5118.4  252.29  5139.2  250.27  5153.7  251.36
  5272.8  254.22  5402.3  256.03  5442.9  257.87    5531  262.09  5581.3  265.83
  5688.4  270.66  5717.3  270.64  5723.6  271.87  5758.9  273.92  5809.6  275.32
#Mann= 7 ,-1 , 0
  4523.7     .17       0  4794.7     .15       0  4977.7     .07       0
  5010.8     .15       0  5272.8     .17       0  5402.3     .15       0
  5442.9     .17       0
#XS Ineff= 2 ,-1
    5303  5317.5  254.78  5331.9  5346.4  255.46
Permanent Ineff=
       F       F
Bank Sta=4977.7,5010.8
XS Rating Curve= 0 ,0
Exp/Cntr=0.3,0.1

Type RM Length L Ch R = 1 ,10562   ,572,572,572
BEGIN DESCRIPTION:
KELLY BRANCH 18.0
END DESCRIPTION:
XS GIS Cut Line= 3
      3759434.47     10180448.96      3759267.74     10179599.67
      3758687.82     10179099.84
#Sta/Elev= 30
  4134.5  275.01    4243  270.85  4248.1   271.6  4374.8  268.64  4429.9  267.61
  4778.5  258.57  4835.5  258.04  4858.3  255.64  4886.5  254.73  4927.2  249.93
    4968  250.74  4988.4   249.6  4994.7  246.89  5002.8  247.39    5006  249.89
  5020.2  248.05  5026.8   249.5  5034.5  251.32  5051.9  250.88  5147.5  250.05
  5211.2  251.18  5303.5  249.92  5374.6  250.85  5466.8  253.54  5571.5  258.58
  5599.6  261.55  5651.1   266.5  5665.3  266.14    5715  269.26  5765.6  271.61
#Mann= 11 ,-1 , 0
  4134.5     .11       0  4374.8     .17       0  4429.9     .11       0
  4778.5     .17       0  4858.3     .11       0  4988.4     .03       0
  5026.8     .11       0  5051.9     .15       0  5571.5     .17       0
  5599.6     .11       0    5715     .15       0
Bank Sta=4988.4,5026.8
XS Rating Curve= 0 ,0
Exp/Cntr=0.3,0.1

Type RM Length L Ch R = 1 ,9990    ,496,496,496
BEGIN DESCRIPTION:
KELLY BRANCH 17.0
END DESCRIPTION:
XS GIS Cut Line= 3
      3759524.92     10180345.22      3759525.18     10179240.72
      3759628.69     10178784.42
#Sta/Elev= 30
  3895.5  275.31  4059.7  271.78  4099.7  269.63  4149.7  268.18  4199.7   265.2
  4219.7  265.65  4359.7  260.19  4459.5  258.13  4679.7  252.32  4839.7  250.34
  4879.7  246.68  4909.7  248.26  4949.7  247.67  4989.7  249.34  4995.1  245.24
  5009.9  246.14    5030  248.96  5091.9   248.8  5112.4  247.61  5120.1  248.22
  5126.4  247.76  5143.2  248.92  5163.7  247.39  5169.6  248.57  5174.7  248.33
  5260.9  254.18  5395.4  265.94  5400.5  265.32  5461.1  268.51  5467.9   269.6
#Mann= 5 ,-1 , 0
  3895.5     .17       0  4459.5     .15       0  4989.7     .07       0
    5030     .15       0  5120.1     .17       0
Bank Sta=4989.7,5030
XS Rating Curve= 0 ,0
Exp/Cntr=0.3,0.1

Type RM Length L Ch R = 1 ,9494    ,496,496,496
BEGIN DESCRIPTION:
KELLY BRANCH 16.0
END DESCRIPTION:
XS GIS Cut Line= 3
      3759594.37       10180343.      3759887.44     10179134.54
      3759705.02     10178780.47
#Sta/Elev= 30
  3756.5  274.35  4036.3  264.01  4149.5  261.38    4201   258.8  4252.4  258.84
  4341.6  255.01  4388.9  251.88  4406.8  252.52  4425.6  250.73  4430.7  251.47
  4489.1  250.53  4519.9  248.99  4787.5  246.12  4853.8   247.7  4877.9  244.57
  4882.3  244.57  4895.6  247.53  4937.4  247.94  4993.3  246.58  4999.2  245.23
  5015.4   245.1  5031.9  246.64  5037.6  248.29  5048.5  249.28  5054.1   248.6
  5070.6  250.83  5105.1  251.13  5160.1  253.88  5336.6   265.1  5398.3   267.4
#Mann= 5 ,-1 , 0
  3756.5     .17       0  4341.6     .15       0  4993.3     .07       0
  5037.6     .15       0  5160.1     .17       0
Bank Sta=4993.3,5037.6
XS Rating Curve= 0 ,0
Exp/Cntr=0.3,0.1

Type RM Length L Ch R = 1 ,8998    ,500,500,500
BEGIN DESCRIPTION:
KELLY BRANCH 15.0
END DESCRIPTION:
XS GIS Cut Line= 3
      3760433.56     10180107.01      3760252.37     10179346.81
      3759773.22     10178755.59
#Sta/Elev= 30
  4218.5  271.79    4276  267.96  4470.5  258.33  4474.5  258.07  4520.5  255.75
    4533  256.21  4576.4  253.35  4678.4  247.73  4748.9  244.57  4820.6   243.1
  4841.4  244.78  4903.1  245.39  4944.2  243.46  4952.1  244.76  4985.3   244.7
  5005.2  241.95  5009.6  241.95  5014.5  244.46  5028.8  245.11  5057.6  246.25
    5128  246.52  5156.7  247.96  5163.2  247.26  5235.1     251  5391.7  254.97
  5412.5  254.49  5426.9  256.62  5476.5  255.33  5484.1  256.05    5761  267.29
#Mann= 8 ,-1 , 0
  4218.5     .11       0  4470.5     .17       0  4474.5     .15       0
  4576.4     .17       0  4678.4     .15       0  4985.3     .07       0
  5028.8     .15       0  5484.1     .17       0
#XS Ineff= 2 , 0
       0                  5156.7       0  247.96
Permanent Ineff=
       F       F
Bank Sta=4985.3,5028.8
XS Rating Curve= 0 ,0
Exp/Cntr=0.3,0.1

Type RM Length L Ch R = 1 ,8498    ,499,499,499
BEGIN DESCRIPTION:
KELLY BRANCH 14.0
END DESCRIPTION:
XS GIS Cut Line= 3
      3760983.23     10179822.14      3760637.97     10179345.06
      3759807.07     10178726.28
#Sta/Elev= 30
  4411.1   267.5  4659.3  259.59  4695.9  259.33  4894.7   248.7  4931.1  247.66
  4959.6  243.95  4974.3  242.95  4980.5  241.39  5010.7  242.53  5014.7  239.19
  5019.3  239.19  5025.1  243.03  5037.8  244.55  5117.1  242.91  5146.3  243.98
  5217.2  244.04  5224.6   244.8  5302.6  243.63  5352.7  244.82  5381.9  244.57
  5411.1  246.76  5511.2  251.56  5552.9  252.05  5567.5  253.56  5588.3  253.51
  5668.4  256.56  5738.5  258.87  5796.9  258.28  5982.5  265.32    6036  266.37
#Mann= 5 ,-1 , 0
  4411.1     .11       0  4931.1     .15       0  5010.7     .07       0
  5025.1     .15       0  5668.4     .17       0
Bank Sta=5010.7,5025.1
XS Rating Curve= 0 ,0
Exp/Cntr=0.3,0.1

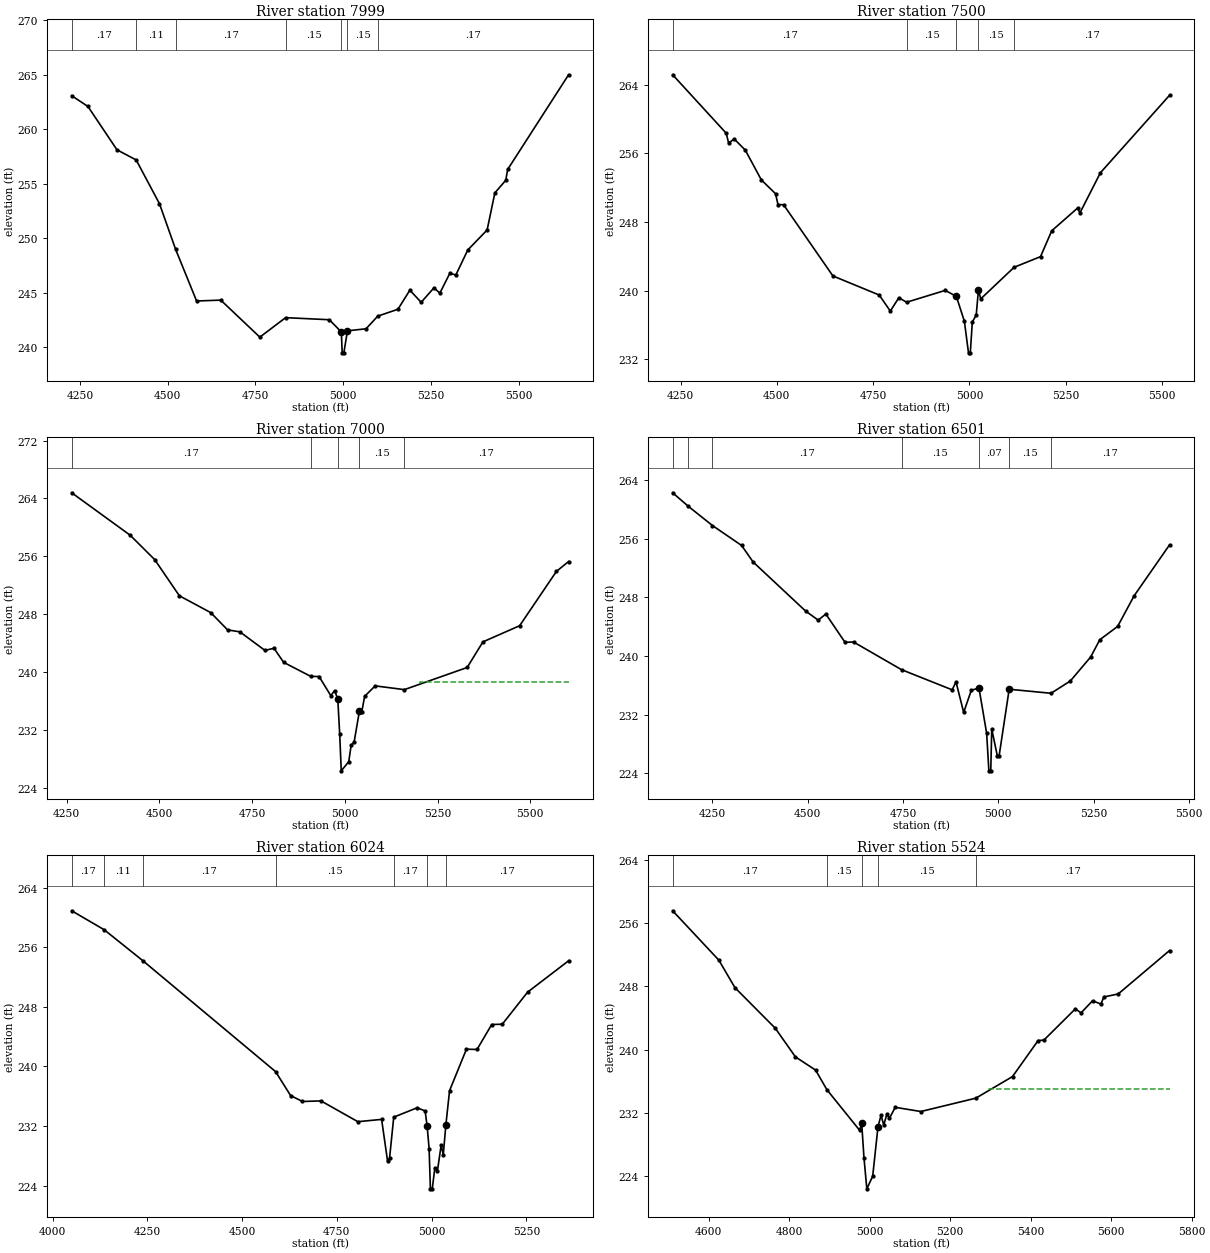
Type RM Length L Ch R = 1 ,7999    ,499,499,499
BEGIN DESCRIPTION:
KELLY BRANCH 13.0
END DESCRIPTION:
XS GIS Cut Line= 3
      3761395.16     10179265.27      3760692.07     10178942.11
      3760417.85     10178361.07
#Sta/Elev= 30
  4226.2  263.08  4272.5  262.09  4355.3  258.11    4410  257.18  4476.4  253.16
  4522.3  248.98  4582.2  244.23  4651.1  244.31  4762.5  240.91  4835.9   242.7
  4960.6  242.51  4994.8  241.38  4997.2  239.47  5001.9  239.47  5012.2  241.49
  5065.2  241.68  5098.6  242.84    5156  243.47  5190.1  245.22  5222.3  244.11
  5258.5  245.43  5275.7  244.96    5304  246.77  5321.2  246.62  5355.1  248.91
  5410.3  250.75  5432.4  254.16  5463.4  255.31  5468.9  256.31  5642.5     265
#Mann= 7 ,-1 , 0
  4226.2     .17       0    4410     .11       0  4522.3     .17       0
  4835.9     .15       0  4994.8     .07       0  5012.2     .15       0
  5098.6     .17       0
#XS Ineff= 2 , 0
       0  4651.1  244.31  5190.1       0  245.22
Permanent Ineff=
       F       F
Bank Sta=4994.8,5012.2
XS Rating Curve= 0 ,0
Exp/Cntr=0.3,0.1

Type RM Length L Ch R = 1 ,7500    ,500,500,500
BEGIN DESCRIPTION:
KELLY BRANCH 12.0
END DESCRIPTION:
XS GIS Cut Line= 3
      3761452.26     10179171.13      3760973.32     10178567.57
       3760522.4      10178309.6
#Sta/Elev= 30
  4229.5  265.14  4368.5  258.34  4374.9  257.19  4389.3  257.67  4418.1  256.37
  4459.8   252.9  4496.7  251.29    4503  250.03  4517.5  250.01  4645.6  241.72
  4765.8   239.5  4794.6  237.63  4816.8  239.19  4836.9  238.66  4937.2  240.04
  4966.1  239.34  4986.9  236.44  4997.6  232.77  5002.3  232.77  5007.5  236.37
  5017.6  237.15  5023.4   240.1  5029.3  239.05    5116  242.73  5184.6  243.97
  5213.7  246.98    5281  249.63  5286.8  249.05    5340  253.73  5519.5  262.75
#Mann= 5 ,-1 , 0
  4229.5     .17       0  4836.9     .15       0  4966.1     .07       0
  5023.4     .15       0    5116     .17       0
Bank Sta=4966.1,5023.4
XS Rating Curve= 0 ,0
Exp/Cntr=0.3,0.1

Type RM Length L Ch R = 1 ,7000    ,499,499,499
BEGIN DESCRIPTION:
KELLY BRANCH 11.0
END DESCRIPTION:
XS GIS Cut Line= 3
      3761537.84     10179105.47      3761389.73     10178383.91
      3760932.94     10177989.81
#Sta/Elev= 30
  4263.4  264.78    4421  258.92  4487.3  255.54  4553.7  250.55  4638.4  248.22
  4683.7  245.84  4717.1  245.56  4784.5     243  4808.9   243.3  4834.9  241.35
  4908.1  239.41  4930.5  239.39  4962.1  236.75  4972.3  237.44  4980.9   236.3
    4986  231.51  4990.3  226.36  5010.5  227.63  5017.1  229.93  5024.8  230.29
  5039.1  234.57  5045.7  234.52  5053.3  236.65  5081.7   238.1  5160.4  237.58
  5329.8  240.64  5372.3  244.18  5471.3  246.41  5570.4  253.91  5603.3  255.28
#Mann= 5 ,-1 , 0
  4263.4     .17       0  4908.1     .15       0  4980.9     .07       0
  5039.1     .15       0  5160.4     .17       0
#XS Ineff= 2 , 0
       0  4930.5  239.39  5201.4       0  238.68
Permanent Ineff=
       F       F
Bank Sta=4980.9,5039.1
XS Rating Curve= 0 ,0
Exp/Cntr=0.3,0.1

Type RM Length L Ch R = 1 ,6501    ,477,477,477
BEGIN DESCRIPTION:
KELLY BRANCH 10.0
END DESCRIPTION:
XS GIS Cut Line= 3
      3761751.85     10179051.23      3761681.28     10178200.45
      3761851.36     10177785.24
#Sta/Elev= 30
  4146.3  262.26  4187.7   260.4  4250.7  257.79  4327.1  255.07  4357.2  252.82
  4494.9  246.12  4527.8  244.89  4547.8  245.72    4598  241.87  4620.6   241.9
  4746.2  238.13    4879  235.38    4889  236.47  4909.1   232.3  4929.1  235.31
  4949.2  235.64  4969.3  229.46  4975.2  224.33  4980.1  224.33  4982.7  230.04
  4997.2   226.4  5002.1   226.4  5028.4  235.46    5138  234.91  5188.6  236.58
    5242  239.86    5266  242.22  5312.7  244.03  5355.9  248.21  5448.7  255.15
#Mann= 7 ,-1 , 0
  4146.3     .17       0  4187.7     .11       0  4250.7     .17       0
  4746.2     .15       0  4949.2     .07       0  5028.4     .15       0
    5138     .17       0
Bank Sta=4949.2,5028.4
XS Rating Curve= 0 ,0
Exp/Cntr=0.3,0.1

Type RM Length L Ch R = 1 ,6024    ,500,500,500
BEGIN DESCRIPTION:
KELLY BRANCH 9.0
END DESCRIPTION:
XS GIS Cut Line= 3
      3761823.18      10179014.2      3762096.24      10178104.7
      3761932.22     10177782.67
#Sta/Elev= 30
  4050.4  260.88  4136.3  258.33  4237.7   254.2  4588.3   239.3  4627.9  236.09
  4659.2  235.29  4708.1  235.37  4805.4  232.58  4868.1  232.89  4883.8  227.28
    4889  227.67  4900.1  233.19    4962  234.45  4982.9  234.02  4988.2  232.01
  4993.4  228.97  4996.8  223.57  5001.7  223.57  5008.6  226.41  5015.3  225.96
  5025.2  229.43  5030.8  228.17  5037.7  232.19  5047.4  236.75  5091.9  242.31
  5119.8  242.27  5158.6  245.62  5186.5  245.66  5253.2  249.96  5361.4  254.17
#Mann= 7 ,-1 , 0
  4050.4     .17       0  4136.3     .11       0  4237.7     .17       0
  4588.3     .15       0  4900.1     .17       0  4988.2     .07       0
  5037.7     .17       0
Bank Sta=4988.2,5037.7
XS Rating Curve= 0 ,0
Exp/Cntr=0.3,0.1

Type RM Length L Ch R = 1 ,5524    ,497,497,497
BEGIN DESCRIPTION:
KELLY BRANCH 8.0
END DESCRIPTION:
XS GIS Cut Line= 3
      3762516.57     10178825.82      3762491.81     10178336.75
      3762012.92     10177766.05
#Sta/Elev= 30
  4510.3  257.57  4625.2  251.32  4665.2  247.84  4765.4  242.71  4815.4  239.09
  4865.5  237.42  4893.7  234.93    4975   229.8    4980  230.73  4985.7  226.35
  4992.8   222.4  5007.4     224  5020.5  230.23  5028.2  231.72  5034.8  230.46
  5042.5  231.82  5049.1  231.33  5063.4  232.71  5127.1  232.18  5263.7  233.87
  5354.8   236.6  5418.5  241.16  5432.8  241.21  5510.9  245.16  5525.2  244.66
  5553.8  246.19  5574.6  245.77  5581.8  246.67  5617.5  247.05    5745  252.54
#Mann= 5 ,-1 , 0
  4510.3     .17       0  4893.7     .15       0    4980     .07       0
  5020.5     .15       0  5263.7     .17       0
#XS Ineff= 2 , 0
       0                  5297.5       0  235.03
Permanent Ineff=
       F       F
Bank Sta=4980,5020.5
XS Rating Curve= 0 ,0
Exp/Cntr=0.3,0.1