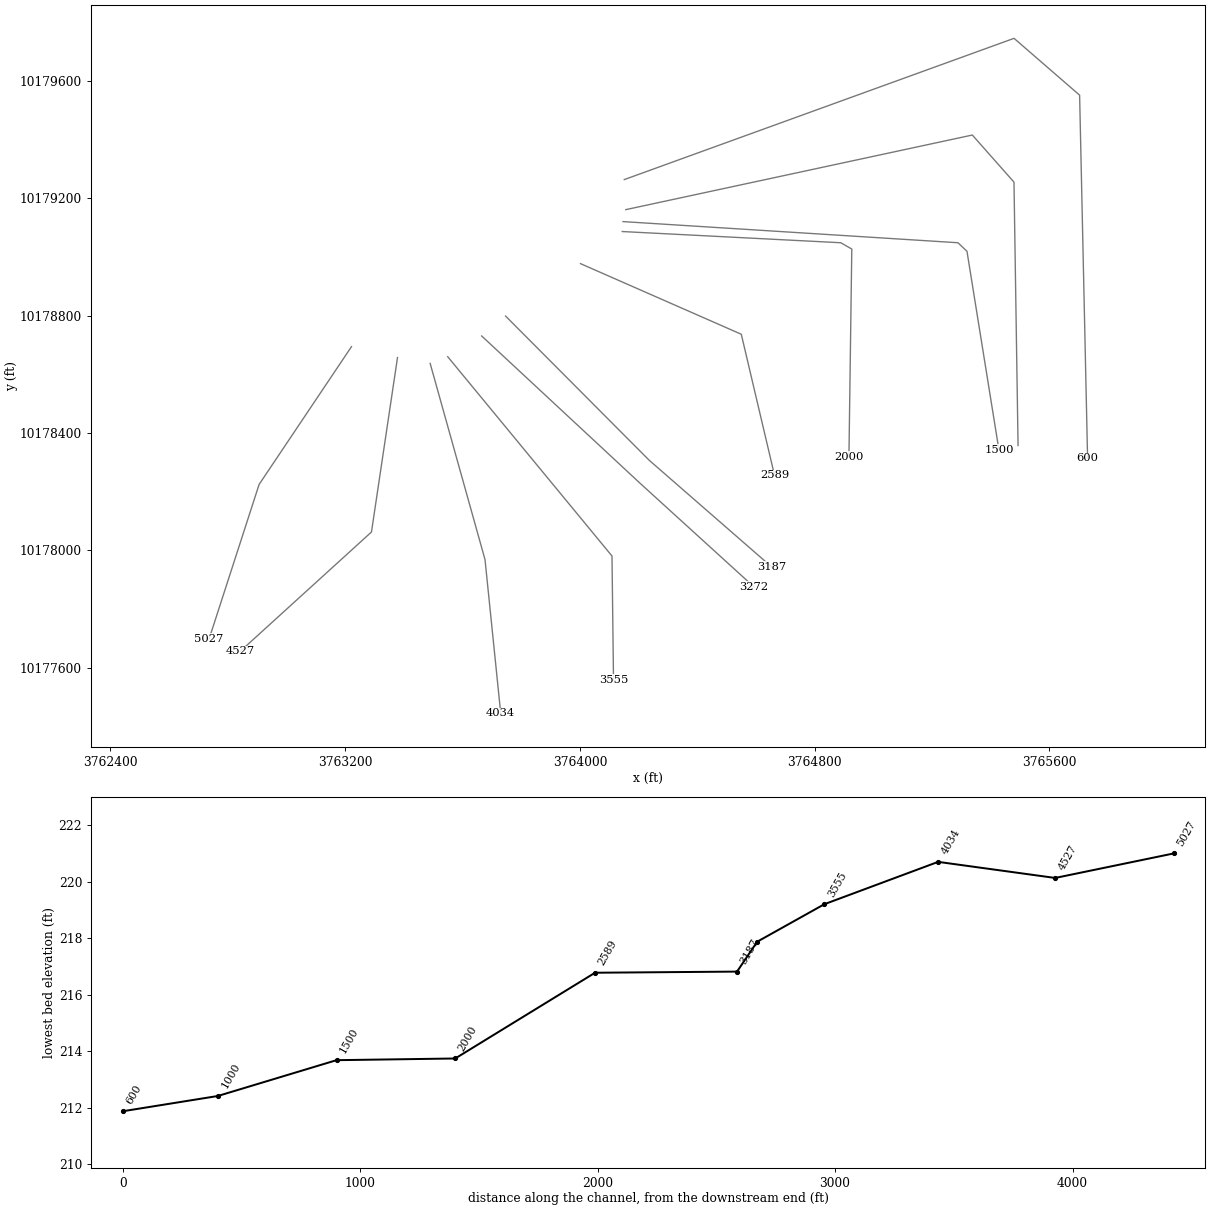
HEC-RAS study KELLY BRANCH.prj: KELLY BRANCH Base Level Engineering

--- KELLY BRANCH.g01 (geometry) --- (continued)

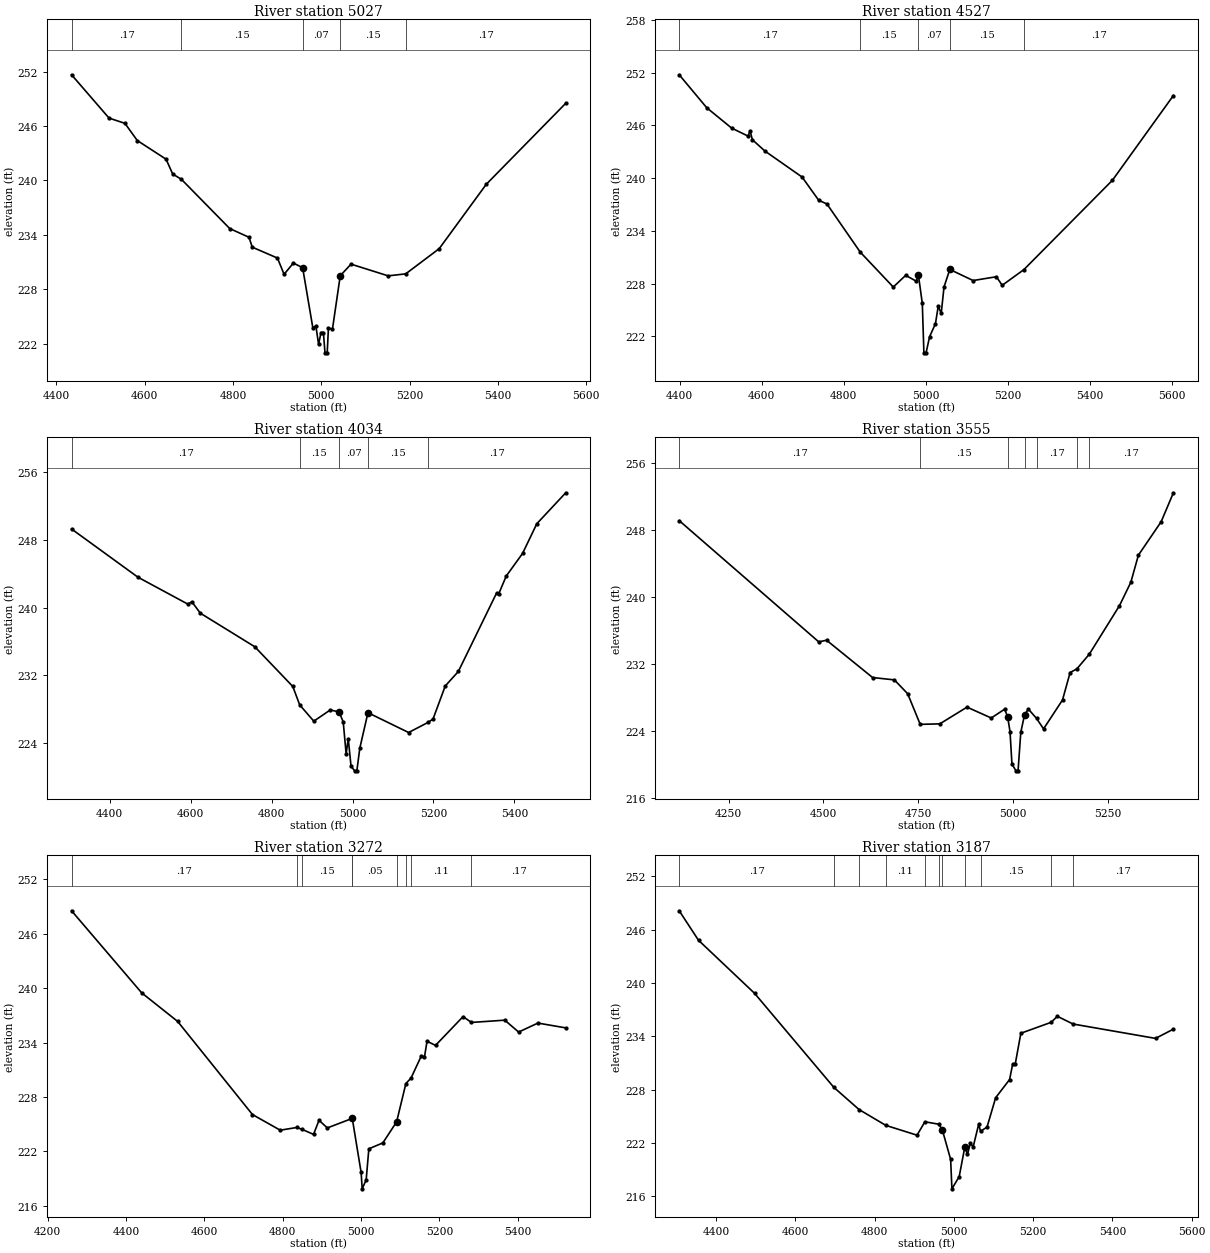
Type RM Length L Ch R = 1 ,5027    ,500,500,500
BEGIN DESCRIPTION:
KELLY BRANCH 7.0
END DESCRIPTION:
XS GIS Cut Line= 3
      3763221.37      10178694.6      3762906.63     10178225.15
      3762736.28     10177698.73
#Sta/Elev= 30
  4434.8  251.64  4519.6  246.87  4555.6  246.29  4583.5   244.4  4648.7  242.34
  4663.7  240.71  4683.5  240.12  4792.8   234.7  4836.4  233.74  4843.8  232.65
  4900.8  231.45  4915.8  229.66  4936.8   230.9  4957.8  230.39  4980.8  223.79
  4987.8  223.96  4993.9  221.95  4999.4  223.25  5004.8  223.25  5008.4  221.01
  5013.4  221.01  5016.2  223.75  5025.3  223.62  5042.9   229.5  5067.3  230.78
  5151.4  229.49  5191.1  229.71    5267  232.49  5373.5  239.58  5553.3   248.5
#Mann= 5 ,-1 , 0
  4434.8     .17       0  4683.5     .15       0  4957.8     .07       0
  5042.9     .15       0  5191.1     .17       0
Bank Sta=4957.8,5042.9
XS Rating Curve= 0 ,0
Exp/Cntr=0.3,0.1

Type RM Length L Ch R = 1 ,4527    ,493,493,493
BEGIN DESCRIPTION:
KELLY BRANCH 6.0
END DESCRIPTION:
XS GIS Cut Line= 3
      3763378.31     10178657.54      3763289.58     10178063.03
      3762842.39     10177656.43
#Sta/Elev= 30
  4398.9  251.75  4466.1     248  4526.8  245.69  4566.8  244.78  4571.8  245.38
  4577.3  244.37  4607.7  243.09  4698.7  240.12  4739.1  237.49  4759.3  237.06
  4840.5  231.59  4921.1  227.62  4951.4  228.95  4977.3  228.28  4982.3  229.01
  4991.9  225.76  4995.8  220.14  5001.1  220.14  5009.7  221.98  5023.9  223.44
  5030.7  225.41  5038.1  224.65  5044.9  227.63    5059  229.62  5115.8  228.36
  5172.6  228.79  5186.8  227.82  5239.7   229.6  5455.7  239.76  5604.4  249.39
#Mann= 5 ,-1 , 0
  4398.9     .17       0  4840.5     .15       0  4982.3     .07       0
    5059     .15       0  5239.7     .17       0
Bank Sta=4982.3,5059
XS Rating Curve= 0 ,0
Exp/Cntr=0.3,0.1

Type RM Length L Ch R = 1 ,4034    ,479,479,479
BEGIN DESCRIPTION:
KELLY BRANCH 5.0
END DESCRIPTION:
XS GIS Cut Line= 3
       3763489.6      10178637.5      3763676.57     10177968.95
      3763730.11     10177444.88
#Sta/Elev= 30
  4305.8  249.29  4469.9  243.59  4592.8  240.42  4603.2  240.68    4624  239.34
  4758.6  235.37  4852.4  230.68  4869.5   228.5  4904.3  226.58  4944.9   227.9
  4966.6  227.68    4977   226.5  4984.2  222.72  4989.4  224.51  4996.3  221.27
  5005.2  220.71  5010.7  220.71    5018  223.39  5038.1  227.58  5138.6  225.24
  5186.5  226.43  5198.9  226.83  5229.1  230.74  5261.4  232.45  5355.9  241.72
  5360.9  241.59  5379.8  243.73  5420.1   246.4  5455.3  249.91  5526.8  253.57
#Mann= 5 ,-1 , 0
  4305.8     .17       0  4869.5     .15       0  4966.6     .07       0
  5038.1     .15       0  5186.5     .17       0
Bank Sta=4966.6,5038.1
XS Rating Curve= 0 ,0
Exp/Cntr=0.3,0.1

Type RM Length L Ch R = 1 ,3555    ,283,283,283
BEGIN DESCRIPTION:
KELLY BRANCH 4.0
END DESCRIPTION:
XS GIS Cut Line= 3
      3763549.48     10178660.39      3764109.32     10177981.18
      3764114.49     10177558.91
#Sta/Elev= 30
  4119.8  249.14  4487.5  234.64  4508.3  234.83  4629.5  230.37  4686.9  230.09
    4722  228.43    4755  224.77  4806.7  224.83  4878.4  226.83  4942.2  225.53
  4977.4  226.58  4985.3   225.7  4991.7  223.91  4996.8  220.03  5007.4  219.21
  5012.9  219.21  5020.1  223.82  5030.1  225.93  5040.1   226.6  5061.6  225.48
  5080.1  224.23  5130.1  227.69  5150.1  230.97  5167.8   231.4  5200.6  233.16
  5280.1  238.96  5310.1  241.76  5330.1  245.01  5390.1  249.01  5422.3  252.47
#Mann= 7 ,-1 , 0
  4119.8     .17       0    4755     .15       0  4985.3     .07       0
  5030.1     .15       0  5061.6     .17       0  5167.8     .15       0
  5200.6     .17       0
Bank Sta=4985.3,5030.1
XS Rating Curve= 0 ,0
Exp/Cntr=0.3,0.1

Type RM Length L Ch R = 1 ,3272    ,85,85,85
BEGIN DESCRIPTION:
KELLY BRANCH 3.0
END DESCRIPTION:
XS GIS Cut Line= 3
      3763665.13     10178731.13      3764206.55      10178227.7
      3764592.94     10177876.14
#Sta/Elev= 30
  4260.7  248.51  4439.7  239.47  4531.6  236.32  4722.6  226.06  4793.5  224.34
  4835.9  224.64  4849.1  224.43  4878.5  223.88  4892.5  225.43  4913.7  224.59
  4975.6  225.61  4977.2  225.69    5000  219.68  5002.7  217.88  5012.9  218.88
  5019.7  222.29  5055.5  222.94  5090.6  225.26  5114.2  229.47  5127.6   230.1
  5154.1  232.56  5161.6  232.38  5168.3  234.14  5189.9  233.68  5260.2  236.85
  5281.7  236.21  5366.8  236.46  5402.1  235.15  5451.4  236.14  5522.4  235.61
#Mann= 9 ,-1 , 0
  4260.7     .17       0  4835.9     .11       0  4849.1     .15       0
  4975.6     .11       0  4977.2     .05       0  5090.6     .11       0
  5114.2     .15       0  5127.6     .11       0  5281.7     .17       0
Bank Sta=4977.2,5090.6
XS Rating Curve= 0 ,0
Exp/Cntr=0.3,0.1

Type RM Length L Ch R = 1 ,3187    ,598,598,598
BEGIN DESCRIPTION:
KELLY BRANCH 6.5
END DESCRIPTION:
XS GIS Cut Line= 3
      3763746.72     10178798.84      3764236.06     10178307.57
      3764653.75     10177943.77
#Sta/Elev= 30
  4306.6  248.13  4355.3  244.81  4496.7  238.84  4696.8  228.25  4760.5  225.75
  4827.9  223.97  4906.9  222.86  4926.6  224.37  4961.5   224.1  4970.5  223.49
  4991.7  220.13  4994.9  216.82  5013.3   218.2  5027.5  221.54  5034.1  220.69
  5041.7  221.99  5048.4  221.52  5062.6  224.12  5067.1   223.3  5083.5  223.77
  5105.3  227.08  5140.5  229.13  5148.1  230.83  5154.7  230.86  5168.9  234.34
  5245.4  235.57    5261  236.25  5300.5  235.38  5508.8  233.76  5553.9   234.8
#Mann= 11 ,-1 , 0
  4306.6     .17       0  4696.8     .11       0  4760.5     .17       0
  4827.9     .11       0  4926.6     .15       0  4961.5     .11       0
  4970.5     .05       0  5027.5     .11       0  5067.1     .15       0
  5245.4     .11       0  5300.5     .17       0
Bank Sta=4970.5,5027.5
XS Rating Curve= 0 ,0
Exp/Cntr=0.3,0.1

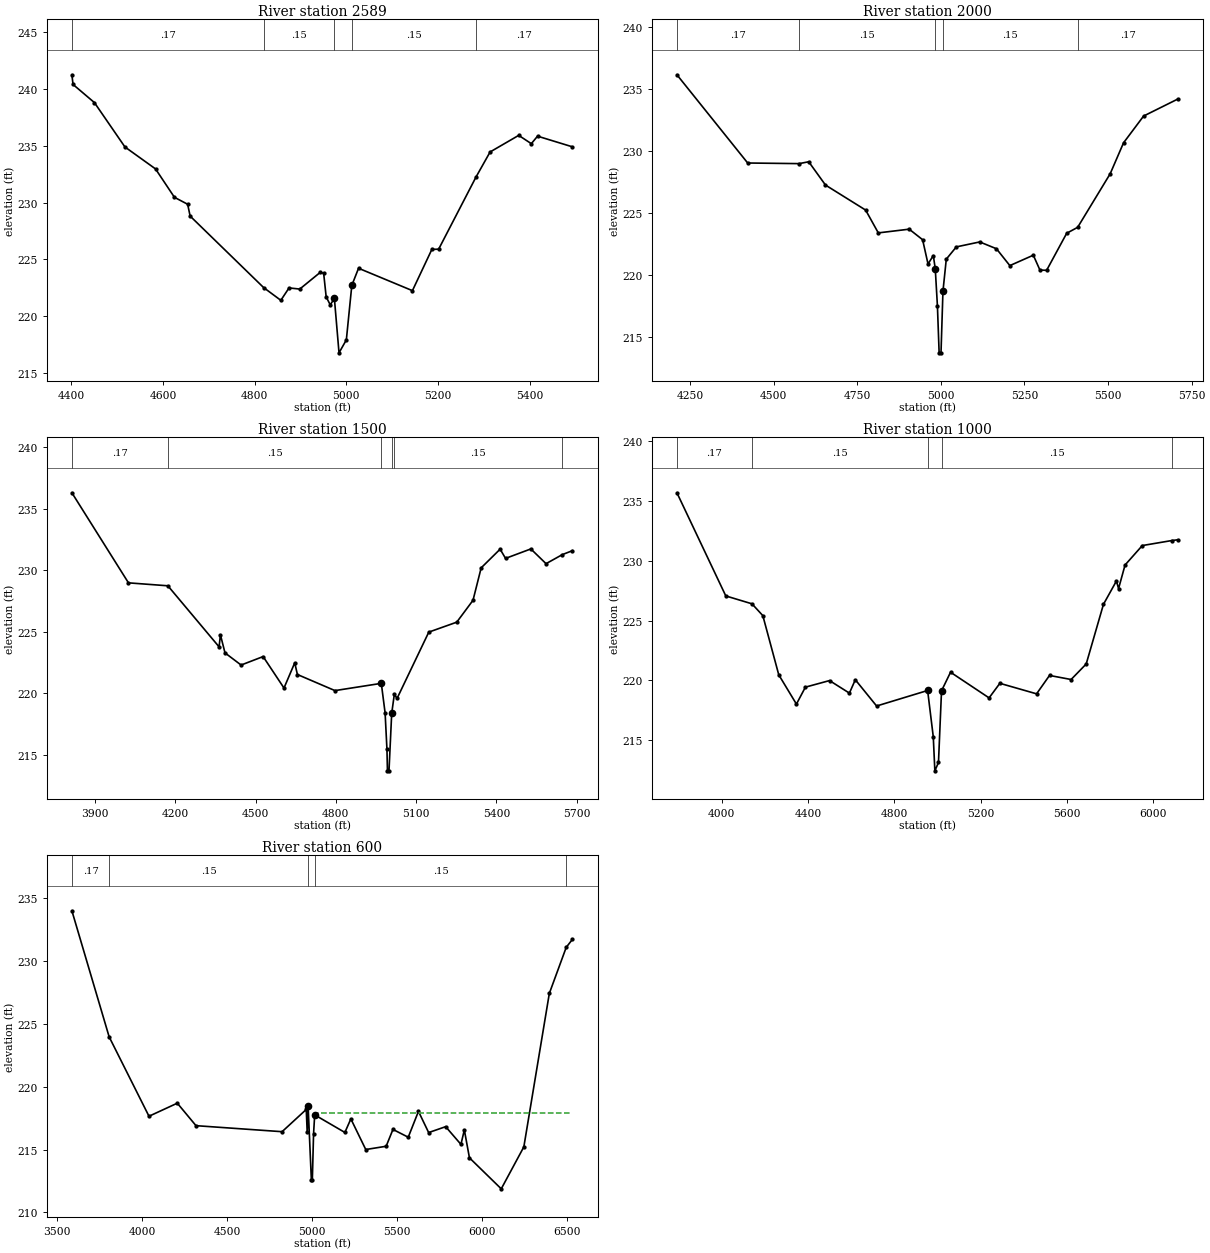
Type RM Length L Ch R = 1 ,2589    ,589,589,589
BEGIN DESCRIPTION:
KELLY BRANCH 2.0
END DESCRIPTION:
XS GIS Cut Line= 3
      3764001.88     10178977.68      3764549.96     10178736.98
      3764663.03     10178256.92
#Sta/Elev= 30
  4401.4  241.24  4403.9  240.39  4450.6  238.79  4517.1  234.89  4583.8  232.96
  4625.1  230.46  4653.9  229.85  4659.3  228.81  4819.6  222.52  4857.1   221.4
    4875  222.49  4898.4  222.39  4943.1  223.86  4950.5  223.78    4956   221.7
  4964.9     221  4973.9  221.57    4984  216.78    5000  217.92  5011.9  222.71
  5026.6  224.22  5144.1  222.25  5186.5  225.88  5201.3   225.9  5282.7  232.24
  5313.5  234.45  5375.9  235.91  5403.4  235.18    5417  235.84  5493.2   234.9
#Mann= 5 ,-1 , 0
  4401.4     .17       0  4819.6     .15       0  4973.9     .07       0
  5011.9     .15       0  5282.7     .17       0
Bank Sta=4973.9,5011.9
XS Rating Curve= 0 ,0
Exp/Cntr=0.3,0.1

Type RM Length L Ch R = 1 ,2000    ,500,500,500
BEGIN DESCRIPTION:
KELLY BRANCH 4.5
END DESCRIPTION:
XS GIS Cut Line= 4
      3764144.26     10179087.04      3764889.07     10179048.85
       3764926.6     10179027.43      3764916.85      10178319.7
#Sta/Elev= 30
    4211  236.18  4422.6  229.06  4576.3  229.01  4605.1  229.16  4655.2  227.28
  4775.3  225.26  4813.1  223.42  4905.5  223.72  4945.6  222.87  4961.8  220.91
  4977.6  221.59  4983.4  220.54  4989.9  217.52    4995  213.74  5000.6  213.74
  5006.4   218.7  5016.4   221.3  5046.4  222.29  5116.4  222.69  5166.4  222.14
  5206.4  220.78  5276.6  221.62  5296.4  220.42  5316.4   220.4  5376.4  223.39
  5409.2  223.87  5506.4  228.19  5546.4  230.69  5606.4  232.85  5707.8  234.21
#Mann= 5 ,-1 , 0
    4211     .17       0  4576.3     .15       0  4983.4     .07       0
  5006.4     .15       0  5409.2     .17       0
Bank Sta=4983.4,5006.4
XS Rating Curve= 0 ,0
Exp/Cntr=0.3,0.1

Type RM Length L Ch R = 1 ,1500    ,500,500,500
BEGIN DESCRIPTION:
KELLY BRANCH 3.5
END DESCRIPTION:
XS GIS Cut Line= 4
      3764146.88      10179120.9      3765288.38     10179048.85
      3765319.16     10179019.64      3765427.83     10178344.13
#Sta/Elev= 30
  3813.8  236.31  4025.2  228.98  4172.4  228.74  4363.8  223.77  4368.8  224.75
  4385.9  223.28    4446  222.29  4528.3  222.98  4606.3  220.42  4646.4  222.47
  4656.4  221.52  4796.7  220.21  4969.9   220.8  4984.1  218.39    4991  215.42
  4992.8  213.68  4998.6  213.68  5008.7  218.35  5018.5   219.9  5028.9  219.58
  5147.3  224.97  5251.8  225.78  5312.5  227.56    5343   230.2  5413.8  231.72
  5434.1  230.97  5528.6  231.74  5585.4  230.54  5646.4  231.28  5684.2   231.6
#Mann= 6 ,-1 , 0
  3813.8     .17       0  4172.4     .15       0  4969.9     .07       0
  5008.7     .12       0  5018.5     .15       0  5646.4     .17       0
Bank Sta=4969.9,5008.7
XS Rating Curve= 0 ,0
Exp/Cntr=0.3,0.1

Type RM Length L Ch R = 1 ,1000    ,400,400,400
BEGIN DESCRIPTION:
KELLY BRANCH 2.5
END DESCRIPTION:
XS GIS Cut Line= 4
      3764156.46      10179161.7       3765337.4     10179415.94
      3765479.35     10179255.45      3765493.24     10178357.92
#Sta/Elev= 30
    3792   235.7  4018.5  227.06  4139.8   226.4  4190.1  225.41    4264  220.45
  4345.8     218  4387.4  219.42  4499.2  219.97  4591.3  218.92  4618.7  220.04
  4717.4  217.84  4953.8  219.14    4980  215.26  4987.3  212.41  5004.1  213.11
  5018.2  219.11    5060  220.67  5238.6  218.52  5288.6  219.74  5458.7  218.86
  5518.7   220.4  5618.7  220.06  5688.7  221.36  5768.7  226.36  5828.7  228.31
  5838.7  227.68  5868.7  229.65  5948.7  231.28  6085.6   231.7  6111.9  231.76
#Mann= 5 ,-1 , 0
    3792     .17       0  4139.8     .15       0  4953.8     .07       0
  5018.2     .15       0  6085.6     .17       0
#XS Ineff= 2 , 0
       0  4618.7  220.04    5060       0  220.67
Permanent Ineff=
       F       F
Bank Sta=4953.8,5018.2
XS Rating Curve= 0 ,0
Exp/Cntr=0.3,0.1

Type RM Length L Ch R = 1 ,600     ,0,0,0
BEGIN DESCRIPTION:
KELLY BRANCH 1.0
END DESCRIPTION:
XS GIS Cut Line= 4
      3764151.27     10179264.14      3765479.54      10179745.5
      3765703.02     10179551.82      3765730.19     10178314.84
#Sta/Elev= 30
  3587.2  234.01  3806.5  223.97  4040.9  217.65  4207.5  218.69  4317.5   216.9
  4824.1  216.42  4966.3  218.19    4972  216.36  4977.3  218.45  4996.4   212.6
  5002.2   212.6  5009.4  216.26    5016  217.76  5193.6  216.36  5228.8  217.44
  5316.5     215  5436.5  215.26  5476.5   216.6  5566.5  215.98  5626.6  218.04
  5686.6  216.35  5786.6  216.82  5876.6  215.41  5896.6  216.56  5926.6  214.34
  6113.8  211.87  6246.7  215.21  6396.7  227.43  6496.2   231.1    6533  231.74
#Mann= 5 ,-1 , 0
  3587.2     .17       0  3806.5     .15       0  4977.3     .07       0
    5016     .15       0  6496.2     .17       0
#XS Ineff= 2 , 0
       0                  5023.6       0  217.88
Permanent Ineff=
       T       T
Bank Sta=4977.3,5016
XS Rating Curve= 0 ,0
Exp/Cntr=0.3,0.1

Chan Stop Cuts=-1
Use User Specified Reach Order=0
Composite Channel Slope=5