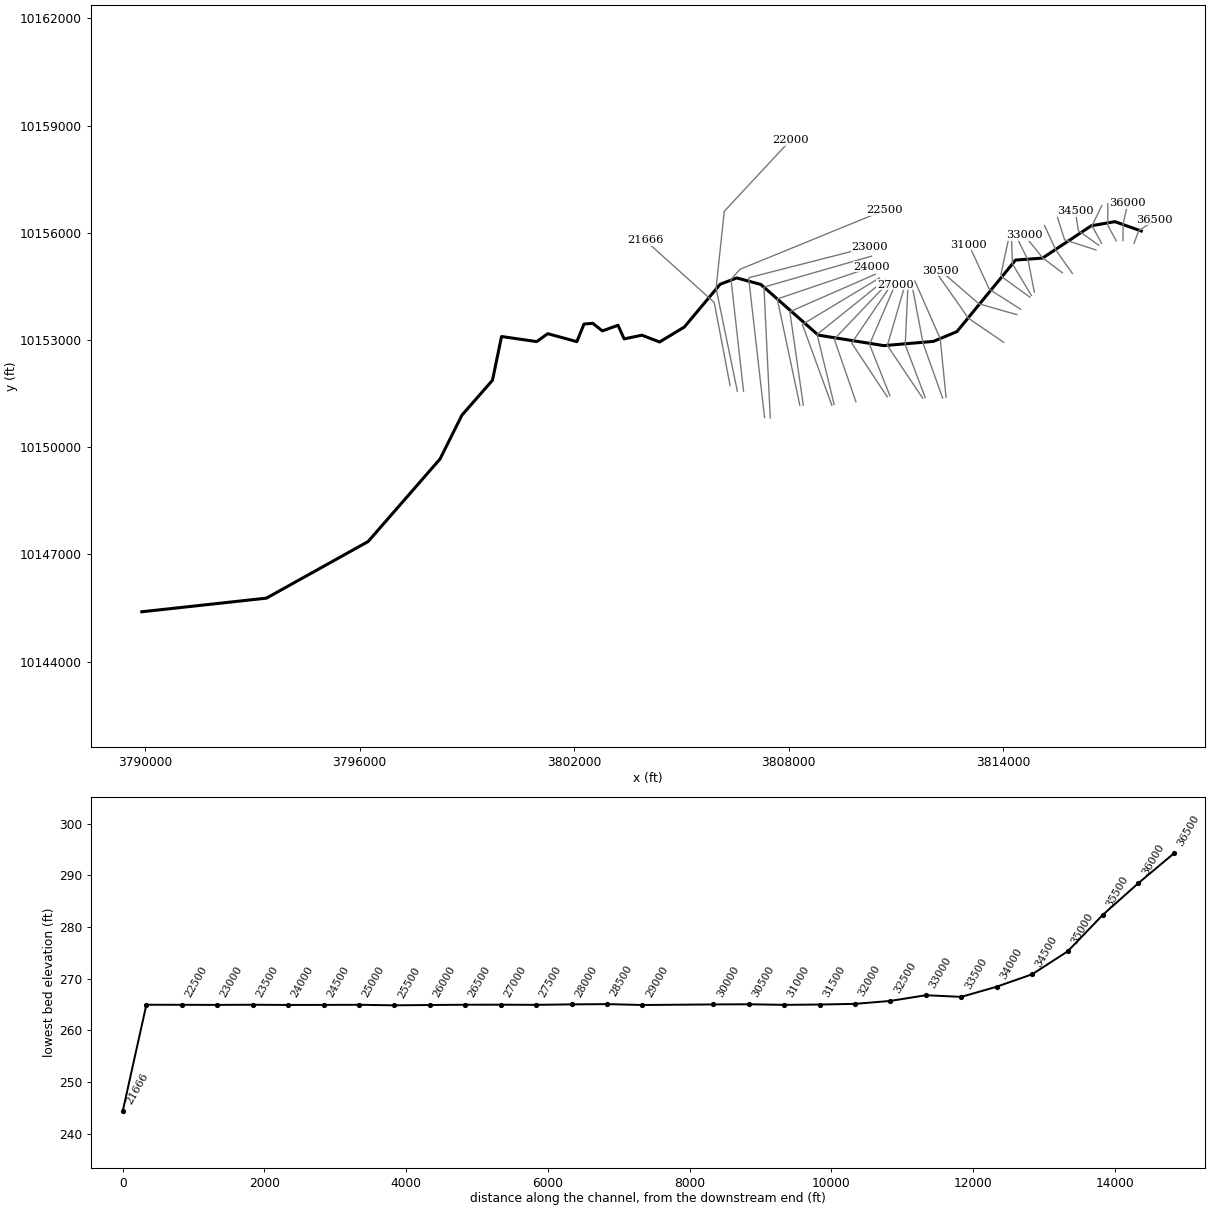
--- LEWIS CREEK.prj (project) ---

Proj Title=LEWIS CREEK Base Level Engineering
Current Plan=p01
Default Exp/Contr=0.3,0.1
English Units
Geom File=g01
Flow File=f01
Flow File=f02
Plan File=p01
Y Axis Title=Elevation
X Axis Title(PF)=Main Channel Distance
X Axis Title(XS)=Station
BEGIN DESCRIPTION:
LEWIS CREEK
END DESCRIPTION:
DSS Export Rating Curves= 0
DSS Export Rating Curve Sorted= 0
DSS Export Volume Flow Curves= 0
DXF OffsetX= 0
DXF OffsetY= 0
DXF ScaleX= 1
DXF ScaleY= 10

--- LEWIS CREEK.p01 (plan) ---

Plan Title=Multiple Run
Short Identifier=Multiple
Geom File=g01
Flow File=f01
Subcritical Flow
K Sum by GR= 0
Std Step Tol= 0.01
Critical Tol= 0.01
Num of Std Step Trials= 20
Max Error Tol= 0.3
Flow Tol Ratio= 0.001
Split Flow NTrial= 30
Split Flow Tol= 0.02
Split Flow Ratio= 0.02
Log Output Level= 0
Friction Slope Method= 1
Unsteady Friction Slope Method= 2
Unsteady Bridges Friction Slope Method= 1
Parabolic Critical Depth
Global Vel Dist=  1 , 1 , 1
Global Log Level= 0
CheckData=True
Encroach Param= -1, 0, 0, 0
BEGIN DESCRIPTION:
Multiple Run
END DESCRIPTION:

--- LEWIS CREEK.f01 (steady flow) ---

Flow Title=Multiple
Program Version=4.10
Number of Profiles= 7
Profile Names=10-year,25-year,50-year,1pct_min,100-year,1pct_plu,500-year
River Rch & RM=LEWIS CREEK,Reach-1         ,36500
     355     468     622     274     828    2501    1505
River Rch & RM=LEWIS CREEK,Reach-1         ,36000
    1027    1440    1994     908    2743    8284    5366
River Rch & RM=LEWIS CREEK,Reach-1         ,31500
    1185    1667    2312    1054    3182    9609    6235
River Rch & RM=LEWIS CREEK,Reach-1         ,29000
    1358    1902    2628    1191    3598   10866    6980
River Rch & RM=LEWIS CREEK,Reach-1         ,25500
    2486    3598    5082    2351    7101   21445   14348
River Rch & RM=LEWIS CREEK,Reach-1         ,15000
    2468    3546    4983    2292    6923   20907   13836
River Rch & RM=LEWIS CREEK,Reach-1         ,12000
    2533    3625    5081    2330    7036   21248   13968
River Rch & RM=LEWIS CREEK,Reach-1         ,9000
    2701    3872    5434    2494    7532   22746   14983
River Rch & RM=LEWIS CREEK,Reach-1         ,5000
    2614    3716    5184    2365    7141   21565   14023
River Rch & RM=LEWIS CREEK,Reach-1         ,2500
    2461    3472    4819    2186    6601   19935   12824
Boundary for River Rch & Prof#=LEWIS CREEK,Reach-1         , 1
Up Type= 0
Dn Type= 3
Dn Slope=0.005
Boundary for River Rch & Prof#=LEWIS CREEK,Reach-1         , 2
Up Type= 0
Dn Type= 3
Dn Slope=0.005
Boundary for River Rch & Prof#=LEWIS CREEK,Reach-1         , 3
Up Type= 0
Dn Type= 3
Dn Slope=0.005
Boundary for River Rch & Prof#=LEWIS CREEK,Reach-1         , 4
Up Type= 0
Dn Type= 3
Dn Slope=0.005
Boundary for River Rch & Prof#=LEWIS CREEK,Reach-1         , 5
Up Type= 0
Dn Type= 3
Dn Slope=0.005
Boundary for River Rch & Prof#=LEWIS CREEK,Reach-1         , 6
Up Type= 0
Dn Type= 3
Dn Slope=0.005
Boundary for River Rch & Prof#=LEWIS CREEK,Reach-1         , 7
Up Type= 0
Dn Type= 3
Dn Slope=0.005
DSS Import GetInterval= 0
DSS Import GetPeak= 0
DSS Import FillOption= 0

--- LEWIS CREEK.f02 (steady flow) ---

Flow Title=Orig_BLE_Flow
Program Version=4.10
Number of Profiles= 7
Profile Names=10-year,25-year,50-year,1pct_min,100-year,1pct_plu,500-year
River Rch & RM=LEWIS CREEK,Reach-1         ,36500
     355     459     541     211     637    1922     875
River Rch & RM=LEWIS CREEK,Reach-1         ,36000
    1027    1412    1734     699    2110    6373    3120
River Rch & RM=LEWIS CREEK,Reach-1         ,31500
    1185    1634    2010     811    2448    7393    3625
River Rch & RM=LEWIS CREEK,Reach-1         ,29000
    1358    1865    2285     917    2768    8360    4058
River Rch & RM=LEWIS CREEK,Reach-1         ,25500
    2486    3527    4419    1808    5462   16494    8342
River Rch & RM=LEWIS CREEK,Reach-1         ,15000
    2468    3476    4333    1763    5325   16082    8044
River Rch & RM=LEWIS CREEK,Reach-1         ,12000
    2533    3554    4418    1792    5412   16345    8121
River Rch & RM=LEWIS CREEK,Reach-1         ,9000
    2701    3796    4725    1918    5794   17497    8711
River Rch & RM=LEWIS CREEK,Reach-1         ,5000
    2614    3643    4508    1819    5493   16587    8153
River Rch & RM=LEWIS CREEK,Reach-1         ,2500
    2461    3404    4190    1681    5078   15335    7456
Boundary for River Rch & Prof#=LEWIS CREEK,Reach-1         , 1
Up Type= 0
Dn Type= 3
Dn Slope=0.005
Boundary for River Rch & Prof#=LEWIS CREEK,Reach-1         , 2
Up Type= 0
Dn Type= 3
Dn Slope=0.005
Boundary for River Rch & Prof#=LEWIS CREEK,Reach-1         , 3
Up Type= 0
Dn Type= 3
Dn Slope=0.005
Boundary for River Rch & Prof#=LEWIS CREEK,Reach-1         , 4
Up Type= 0
Dn Type= 3
Dn Slope=0.005
Boundary for River Rch & Prof#=LEWIS CREEK,Reach-1         , 5
Up Type= 0
Dn Type= 3
Dn Slope=0.005
Boundary for River Rch & Prof#=LEWIS CREEK,Reach-1         , 6
Up Type= 0
Dn Type= 3
Dn Slope=0.005
Boundary for River Rch & Prof#=LEWIS CREEK,Reach-1         , 7
Up Type= 0
Dn Type= 3
Dn Slope=0.005
DSS Import GetInterval= 0
DSS Import GetPeak= 0
DSS Import FillOption= 0

--- LEWIS CREEK.g01 (geometry) ---

Geom Title=Existing Conditions
Program Version=4.10

River Reach=LEWIS CREEK     ,Reach-1
Reach XY= 30
      3817859.98     10156047.82      3817120.65     10156309.54
       3816461.2     10156193.29      3815099.19      10155289.1
      3814346.09      10155234.5      3812705.37     10153231.61
      3812048.76     10152958.36      3810660.83     10152840.05
      3808827.99     10153133.91      3807224.19     10154551.45
      3806549.69     10154733.77      3806085.45     10154558.31
      3805084.21     10153360.94       3804391.5     10152941.67
      3803897.17     10153131.47      3803400.55     10153028.09
      3803229.72      10153409.6       3802791.7     10153251.79
      3802522.17     10153465.07      3802277.12     10153443.45
      3802078.42     10152950.95      3801264.45     10153174.12
      3800954.55     10152952.76      3799971.48     10153094.69
      3799718.67     10151871.45       3798864.8     10150894.95
       3798251.1     10149666.41      3796239.37     10147355.95
      3793397.16     10145773.35       3789912.5      10145391.7

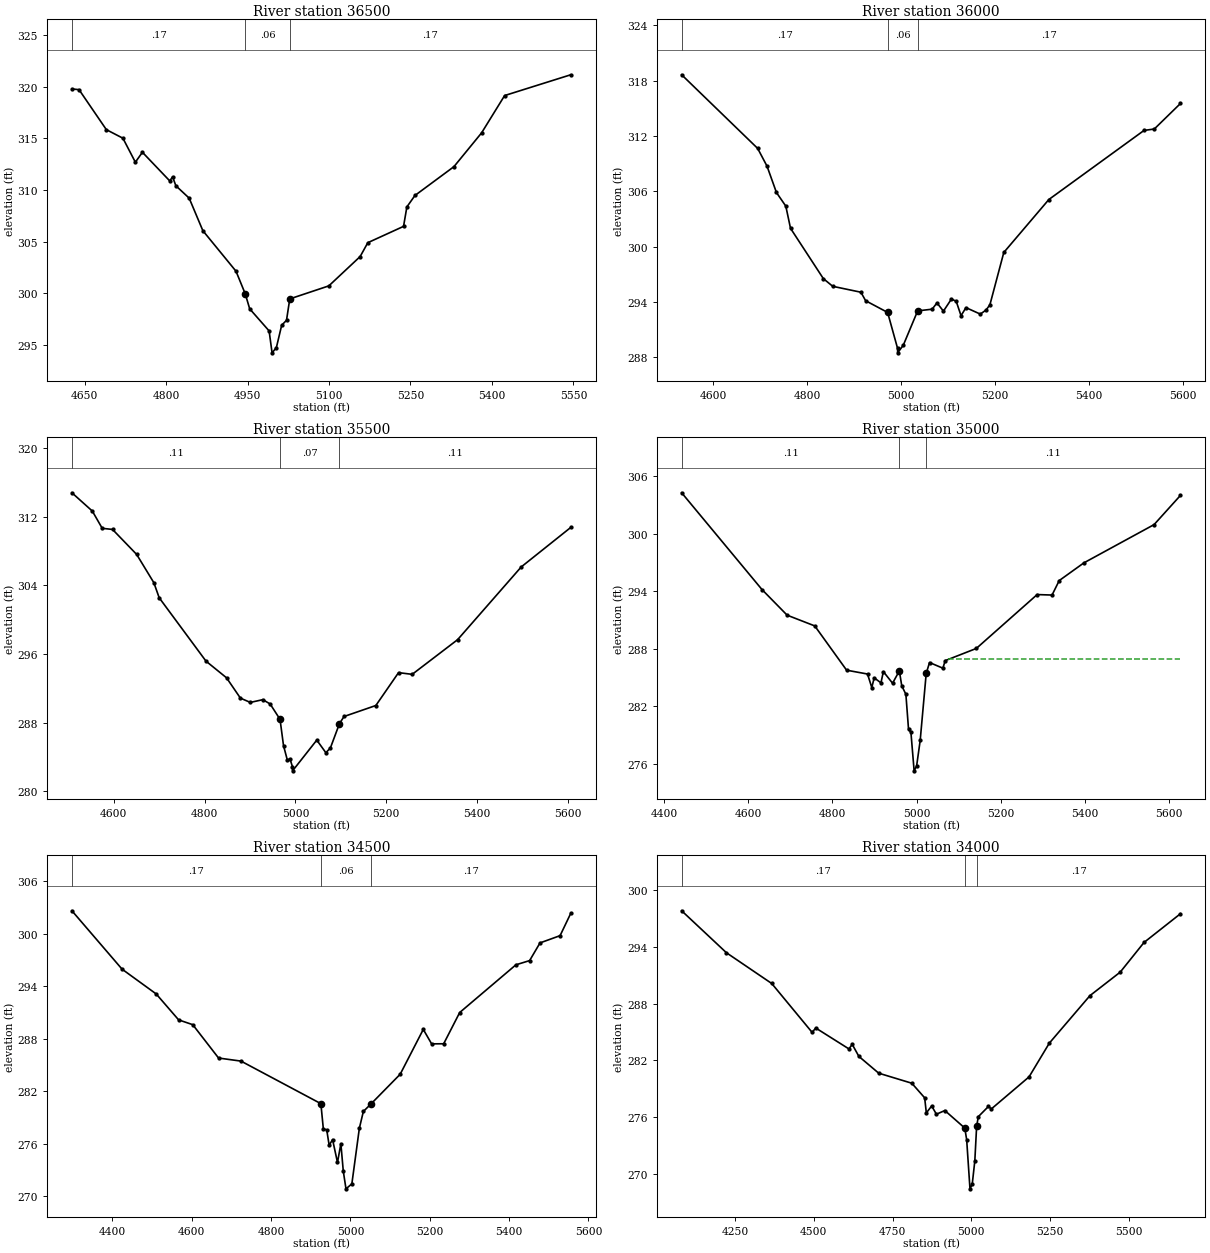
Type RM Length L Ch R = 1 ,36500   ,500,500,500
BEGIN DESCRIPTION:
LEWIS CREEK 73.0
END DESCRIPTION:
XS GIS Cut Line= 3
      3817659.25     10155701.38      3817787.71     10156051.88
      3818238.47      10156358.4
#Sta/Elev= 30
  4626.7  319.77  4639.8   319.7  4690.1  315.83  4720.6     315  4743.5  312.68
  4756.5  313.64  4806.8  310.87  4812.1  311.26  4818.1   310.4  4842.6   309.2
  4867.8  306.05  4928.8  302.13  4945.9  299.93    4954  298.49  4989.8  296.35
  4995.2  294.23  5003.1  294.73  5012.9   296.9  5021.8  297.38  5027.8  299.45
  5099.7  300.71  5157.4  303.55  5171.5  304.89  5237.3  306.47  5243.4  308.35
  5258.3  309.46  5330.1  312.25    5381  315.52  5423.4  319.13  5545.1  321.14
#Mann= 3 , 0 , 0
  4626.7     .17       0  4945.9     .06       0  5027.8     .17       0
Bank Sta=4945.9,5027.8
XS Rating Curve= 0 ,0
Exp/Cntr=0.3,0.1

Type RM Length L Ch R = 1 ,36000   ,500,500,500
BEGIN DESCRIPTION:
LEWIS CREEK 72.0
END DESCRIPTION:
XS GIS Cut Line= 3
       3817350.2     10155779.14      3817353.01     10156246.54
      3817486.21     10156826.74
#Sta/Elev= 30
  4532.6  318.63  4694.5  310.65  4714.5  308.72  4734.5  305.87  4754.5  304.39
  4764.5  301.99  4834.5  296.53  4854.5   295.7  4914.5  295.06  4924.5  294.14
  4971.4  292.87  4992.5  288.99  4992.8  288.49  5004.9  289.33  5035.4  293.04
  5066.2  293.22  5076.5   293.9  5090.3  293.01  5107.3  294.32  5117.5  294.08
  5127.8  292.52  5138.3  293.39  5168.8  292.69  5181.1  293.13  5189.3   293.7
  5218.9  299.37  5314.9  305.11  5517.7   312.6  5539.5  312.75  5595.3  315.52
#Mann= 3 , 0 , 0
  4532.6     .17       0  4971.4     .06       0  5035.4     .17       0
#XS Ineff= 2 , 0
       0                  5107.3       0  294.32
Permanent Ineff=
       F       T
Bank Sta=4971.4,5035.4
XS Rating Curve= 0 ,0
Exp/Cntr=0.3,0.1

Type RM Length L Ch R = 1 ,35500   ,500,500,500
BEGIN DESCRIPTION:
LEWIS CREEK 71.0
END DESCRIPTION:
XS GIS Cut Line= 3
      3817162.19     10155772.67      3816925.63     10156204.07
      3816924.44     10156810.06
#Sta/Elev= 30
    4508  314.78  4552.9  312.65  4574.7  310.64  4597.4  310.51  4650.5   307.6
  4688.4   304.3  4700.1  302.55  4803.1  295.17  4848.3  293.23  4878.9  290.86
  4900.7  290.36  4928.2  290.68  4944.3  290.18  4966.1  288.39  4973.8  285.32
  4982.2  283.64  4987.9  283.78  4993.4  282.89  4993.7  282.39    5047  285.97
    5067   284.5    5077  285.06    5097   287.9    5107  288.72    5177     290
    5227  293.83    5257  293.63    5357  297.67    5497  306.14    5606  310.74
#Mann= 3 , 0 , 0
    4508     .11       0  4966.1     .07       0    5097     .11       0
Bank Sta=4966.1,5097
XS Rating Curve= 0 ,0
Exp/Cntr=0.3,0.1

Type RM Length L Ch R = 1 ,35000   ,500,500,500
BEGIN DESCRIPTION:
LEWIS CREEK 70.0
END DESCRIPTION:
XS GIS Cut Line= 3
      3816751.54     10155703.54      3816483.92     10156193.41
      3816757.47     10156757.48
#Sta/Elev= 30
  4441.8  304.29  4632.7  294.19  4692.4  291.52    4758   290.4  4833.7  285.78
  4883.4  285.38  4893.5  283.97  4899.2  284.98  4915.3  284.46    4921  285.63
  4942.9  284.42    4959  285.71  4964.7  284.15  4974.5  283.27  4980.8  279.62
  4986.5  279.29  4994.1  275.28    5000  275.78  5008.5  278.45  5022.8  285.44
  5030.7  286.58  5062.4  285.99    5068  286.78  5141.9  288.05  5286.4  293.67
  5321.8  293.62  5338.8  295.13  5397.5  296.98  5564.2  300.97  5626.9  304.02
#Mann= 3 , 0 , 0
  4441.8     .11       0    4959     .06       0  5022.8     .11       0
#XS Ineff= 2 , 0
       0                  5075.2       0  286.94
Permanent Ineff=
       F       F
Bank Sta=4959,5022.8
XS Rating Curve= 0 ,0
Exp/Cntr=0.3,0.1

Type RM Length L Ch R = 1 ,34500   ,500,500,500
BEGIN DESCRIPTION:
LEWIS CREEK 69.0
END DESCRIPTION:
XS GIS Cut Line= 3
      3816671.58     10155649.51      3816101.45     10156058.74
      3816016.97     10156607.58
#Sta/Elev= 30
  4298.2  302.62  4424.6  295.95  4510.6  293.12  4567.1  290.16  4602.7  289.61
  4667.8   285.8  4724.3  285.45  4925.6  280.59  4931.8  277.72  4940.4  277.59
  4946.5  275.83  4955.1  276.49  4967.5  273.87    4976  276.02  4982.1  272.88
  4988.9  270.86  5003.7  271.43  5022.6  277.78  5032.7   279.7  5052.2  280.57
  5125.5  283.95  5183.7  289.07  5204.7  287.42  5235.1  287.43  5275.5     291
  5417.2  296.45  5451.7  296.93  5477.9  298.95  5528.5  299.78  5555.3  302.32
#Mann= 3 , 0 , 0
  4298.2     .17       0  4925.6     .06       0  5052.2     .17       0
Bank Sta=4925.6,5052.2
XS Rating Curve= 0 ,0
Exp/Cntr=0.3,0.1

Type RM Length L Ch R = 1 ,34000   ,500,500,500
BEGIN DESCRIPTION:
LEWIS CREEK 68.0
END DESCRIPTION:
XS GIS Cut Line= 3
      3816593.24     10155517.53      3815718.11     10155800.37
      3815516.82     10156433.33
#Sta/Elev= 30
  4080.3  297.79  4222.6  293.36  4366.3  290.12  4494.4  284.97  4506.3  285.42
  4611.4  283.22  4621.9   283.7    4643  282.43    4706  280.66  4811.1   279.6
  4851.9  278.06  4857.2  276.47  4874.2   277.2  4889.2  276.33    4916  276.72
  4979.3  274.87  4985.3  273.64  4995.8  268.46    5003  268.96  5011.2  271.42
  5016.9  275.04  5022.2  276.07  5054.4  277.15  5063.7  276.89  5183.4  280.27
  5247.8  283.83  5376.8  288.84  5472.9  291.32  5548.5  294.45  5664.2  297.48
#Mann= 3 , 0 , 0
  4080.3     .17       0  4979.3     .06       0  5016.9     .17       0
Bank Sta=4979.3,5016.9
XS Rating Curve= 0 ,0
Exp/Cntr=0.3,0.1

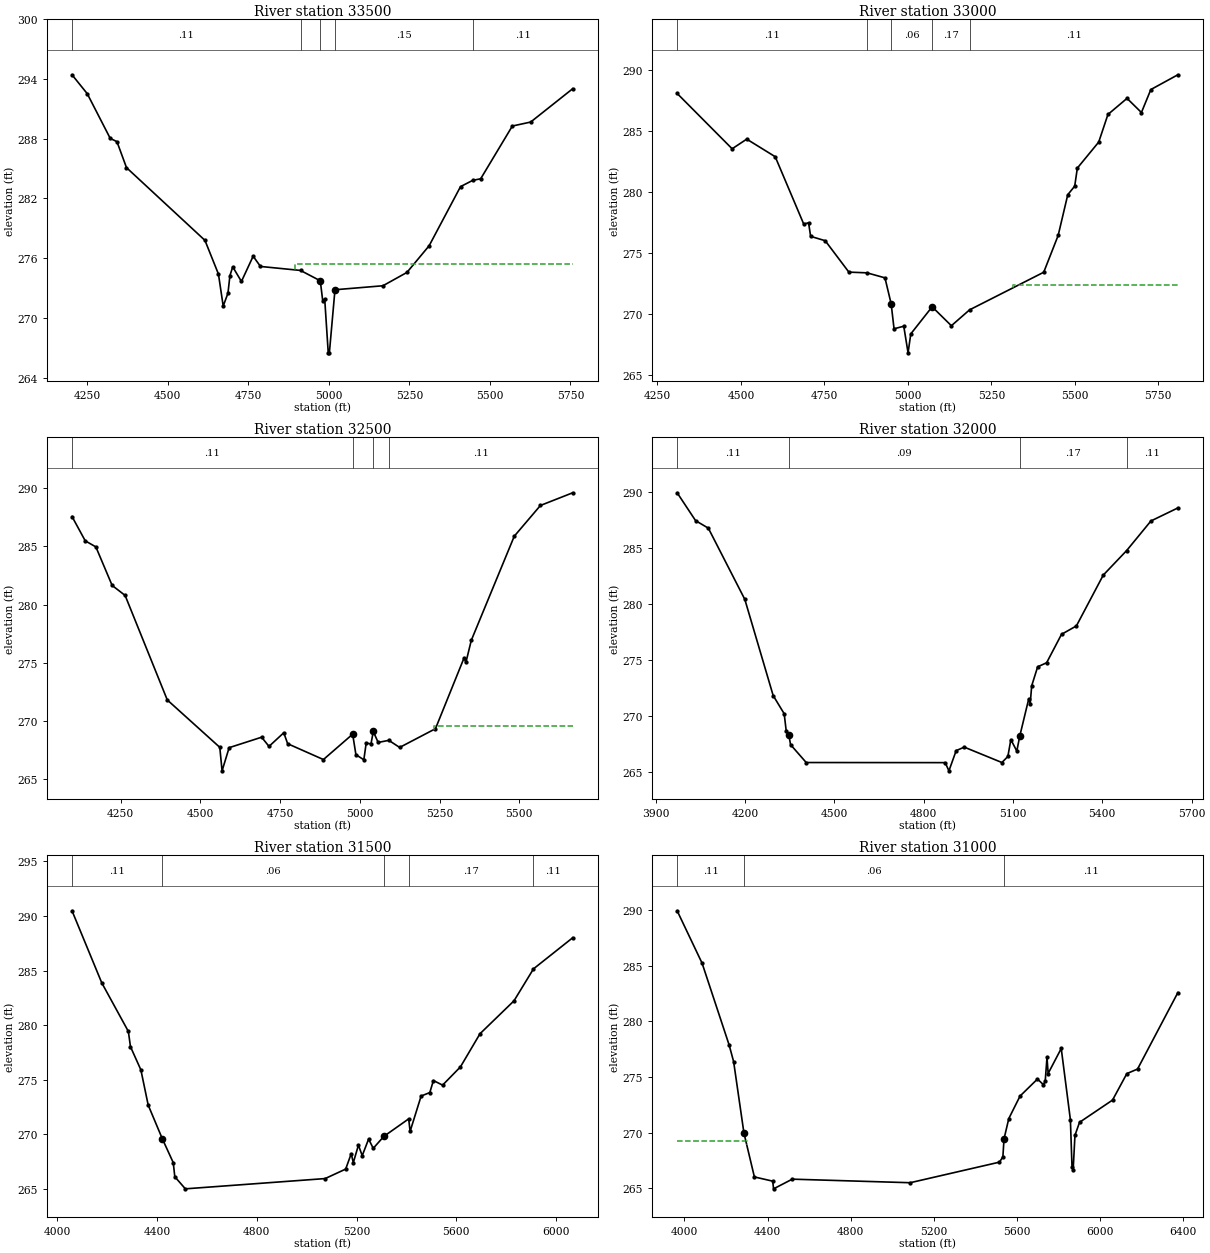
Type RM Length L Ch R = 1 ,33500   ,500,500,500
BEGIN DESCRIPTION:
LEWIS CREEK 67.0
END DESCRIPTION:
XS GIS Cut Line= 3
      3815933.48     10154862.17       3815472.6     10155512.89
      3815156.56     10156200.66
#Sta/Elev= 30
  4202.6  294.43  4249.9  292.53  4321.2  288.04  4342.1  287.71  4371.7   285.1
  4615.3  277.79  4657.2   274.4  4671.9  271.19  4686.7  272.48  4692.8  274.25
  4701.5  275.13  4728.5  273.66  4764.9   276.2  4787.6  275.17  4911.9  274.77
  4973.3  273.73  4980.8  271.74    4987  271.92    4998  266.49  5001.5  266.49
  5018.9  272.83  5167.8  273.23  5242.3  274.57  5311.2  277.25  5408.6  283.19
  5446.4  283.82  5471.2  283.98  5569.5  289.28  5626.4  289.68  5756.9  293.03
#Mann= 5 ,-1 , 0
  4202.6     .11       0  4911.9     .15       0  4973.3     .09       0
  5018.9     .15       0  5446.4     .11       0
#XS Ineff= 2 ,-1
  4764.9  4630.1   276.2  4894.7  4764.9  275.45
Permanent Ineff=
       F       F
Bank Sta=4973.3,5018.9
XS Rating Curve= 0 ,0
Exp/Cntr=0.3,0.1

Type RM Length L Ch R = 1 ,33000   ,500,500,500
BEGIN DESCRIPTION:
LEWIS CREEK 66.0
END DESCRIPTION:
XS GIS Cut Line= 3
      3815655.84     10154877.94      3815104.72     10155294.93
      3814596.82     10155923.99
#Sta/Elev= 30
  4308.9  288.05  4473.6  283.52  4517.3  284.31  4602.6  282.87  4687.9  277.36
  4702.5  277.46  4708.7  276.35  4752.4  275.99  4823.2  273.42  4877.7  273.36
  4931.3  272.95 4949.81  270.83  4958.5  268.78  4987.6  268.99  5000.5  266.81
  5008.6  268.36  5072.6  270.58  5130.2  269.03  5184.7  270.33  5406.8  273.41
    5450  276.42  5478.8  279.76  5499.6  280.46  5507.5  281.94  5571.5  284.07
  5599.1  286.33  5656.3  287.65  5699.4  286.49  5727.6  288.37  5808.5  289.58
#Mann= 5 ,-1 , 0
  4308.9     .11       0  4877.7     .17       0 4949.81     .06       0
  5072.6     .17       0  5184.7     .11       0
#XS Ineff= 2 , 0
       0                  5315.6       0   272.4
Permanent Ineff=
       F       F
Bank Sta=4949.81,5072.6
XS Rating Curve= 0 ,0
Exp/Cntr=0.3,0.1

Type RM Length L Ch R = 1 ,32500   ,500,500,500
BEGIN DESCRIPTION:
LEWIS CREEK 65.0
END DESCRIPTION:
XS GIS Cut Line= 3
       3814871.3     10154337.66      3814697.55     10155223.18
      3814402.59     10155821.86
#Sta/Elev= 30
  4097.6  287.56  4139.1  285.47  4172.4  284.95  4223.4  281.64  4264.1  280.78
  4396.3   271.8  4560.9  267.73  4568.1  265.71  4590.2   267.7  4692.1   268.6
  4715.2  267.81  4761.5  268.98  4773.7  268.04  4885.8  266.68  4977.5  268.86
  4987.7   267.1  5012.5  266.66  5019.9  268.09    5035  268.03  5042.2  269.09
  5057.4  268.15  5090.9  268.33  5124.8  267.72  5237.1  269.33    5327  275.43
  5332.5  275.02  5349.4  276.92  5484.2  285.87  5566.2  288.51  5667.4   289.6
#Mann= 4 ,-1 , 0
  4097.6     .11       0  4977.5     .09       0  5042.2     .15       0
  5090.9     .11       0
#XS Ineff= 2 , 0
       0                  5231.5       0  269.53
Permanent Ineff=
       F       F
Bank Sta=4977.5,5042.2
XS Rating Curve= 0 ,0
Exp/Cntr=0.3,0.1

Type RM Length L Ch R = 1 ,32000   ,500,500,500
BEGIN DESCRIPTION:
LEWIS CREEK 64.0
END DESCRIPTION:
XS GIS Cut Line= 3
      3814787.02     10154246.87      3814258.94     10155128.16
      3814233.74     10155781.38
#Sta/Elev= 30
  3972.6  289.89  4034.5  287.41  4077.3  286.74  4199.8   280.4    4295  271.84
    4332  270.22  4338.9  268.66  4347.5  268.34  4353.4  267.47  4405.9  265.88
  4872.5  265.87  4885.1  265.14  4909.4  266.94  4936.6  267.25    5063  265.88
    5083  266.42    5093  267.92    5113   266.9    5123  268.24    5153  271.54
    5158  271.13    5163  272.71    5183   274.4  5213.1  274.76  5263.1  277.29
  5313.1  278.04  5403.2  282.56  5481.9  284.75  5563.3  287.38  5653.7  288.54
#Mann= 4 ,-1 , 0
  3972.6     .11       0  4347.5     .09       0    5123     .17       0
  5481.9     .11       0
Bank Sta=4347.5,5123
XS Rating Curve= 0 ,0
Exp/Cntr=0.3,0.1

Type RM Length L Ch R = 1 ,31500   ,500,500,500
BEGIN DESCRIPTION:
LEWIS CREEK 63.0
END DESCRIPTION:
XS GIS Cut Line= 4
      3814748.09     10154195.03      3813986.27     10154748.08
      3813937.66     10154839.06      3814140.82     10155781.36
#Sta/Elev= 30
  4058.6  290.48  4177.9  283.88  4284.6  279.43  4293.1  278.03  4334.8  275.91
  4364.2  272.68  4420.6  269.61  4464.7  267.41  4470.9  266.12  4513.2  265.01
    5074  265.95  5156.4  266.82  5178.6  268.23    5187  267.41  5207.5  269.01
  5222.8  268.05  5248.4  269.57  5266.9  268.72  5309.8  269.82  5409.2  271.42
  5414.8  270.27    5459  273.51  5493.9  273.83  5508.3  274.93  5545.1  274.51
  5616.7  276.18  5695.3  279.22  5831.5  282.23  5909.8  285.16  6067.1  288.01
#Mann= 5 ,-1 , 0
  4058.6     .11       0  4420.6     .06       0  5309.8     .15       0
  5409.2     .17       0  5909.8     .11       0
#XS Ineff= 2 ,-1
  5207.5  5248.4  269.01  5248.4  5330.3  269.57
Permanent Ineff=
       F       F
Bank Sta=4420.6,5309.8
XS Rating Curve= 0 ,0
Exp/Cntr=0.3,0.1

Type RM Length L Ch R = 1 ,31000   ,500,500,500
BEGIN DESCRIPTION:
LEWIS CREEK 62.0
END DESCRIPTION:
XS GIS Cut Line= 3
      3814489.05      10153858.6      3813615.03     10154413.14
      3813041.12     10155660.66
#Sta/Elev= 30
  3964.9  289.95  4084.8  285.24    4215  277.88  4236.5  276.39  4286.1  269.97
  4336.4  266.02  4424.6  265.64  4428.6  264.95  4518.6  265.82  5085.8   265.5
  5515.1  267.35  5531.6  267.82  5537.1  269.44  5560.1  271.27  5614.1  273.29
  5697.9  274.82  5726.4  274.32  5735.2  274.62  5743.8  276.76  5749.3  275.32
  5812.3  277.57  5856.3  271.17  5864.2   266.9  5869.7  266.68  5878.3  269.76
  5900.3  270.93    6059  272.93  6127.9  275.31  6179.3  275.72  6373.2  282.59
#Mann= 3 , 0 , 0
  3964.9     .11       0  4286.1     .06       0  5537.1     .11       0
#XS Ineff= 2 , 0
       0    4300  269.28  5812.3       0  277.57
Permanent Ineff=
       F       F
Bank Sta=4286.1,5537.1
XS Rating Curve= 0 ,0
Exp/Cntr=0.3,0.1

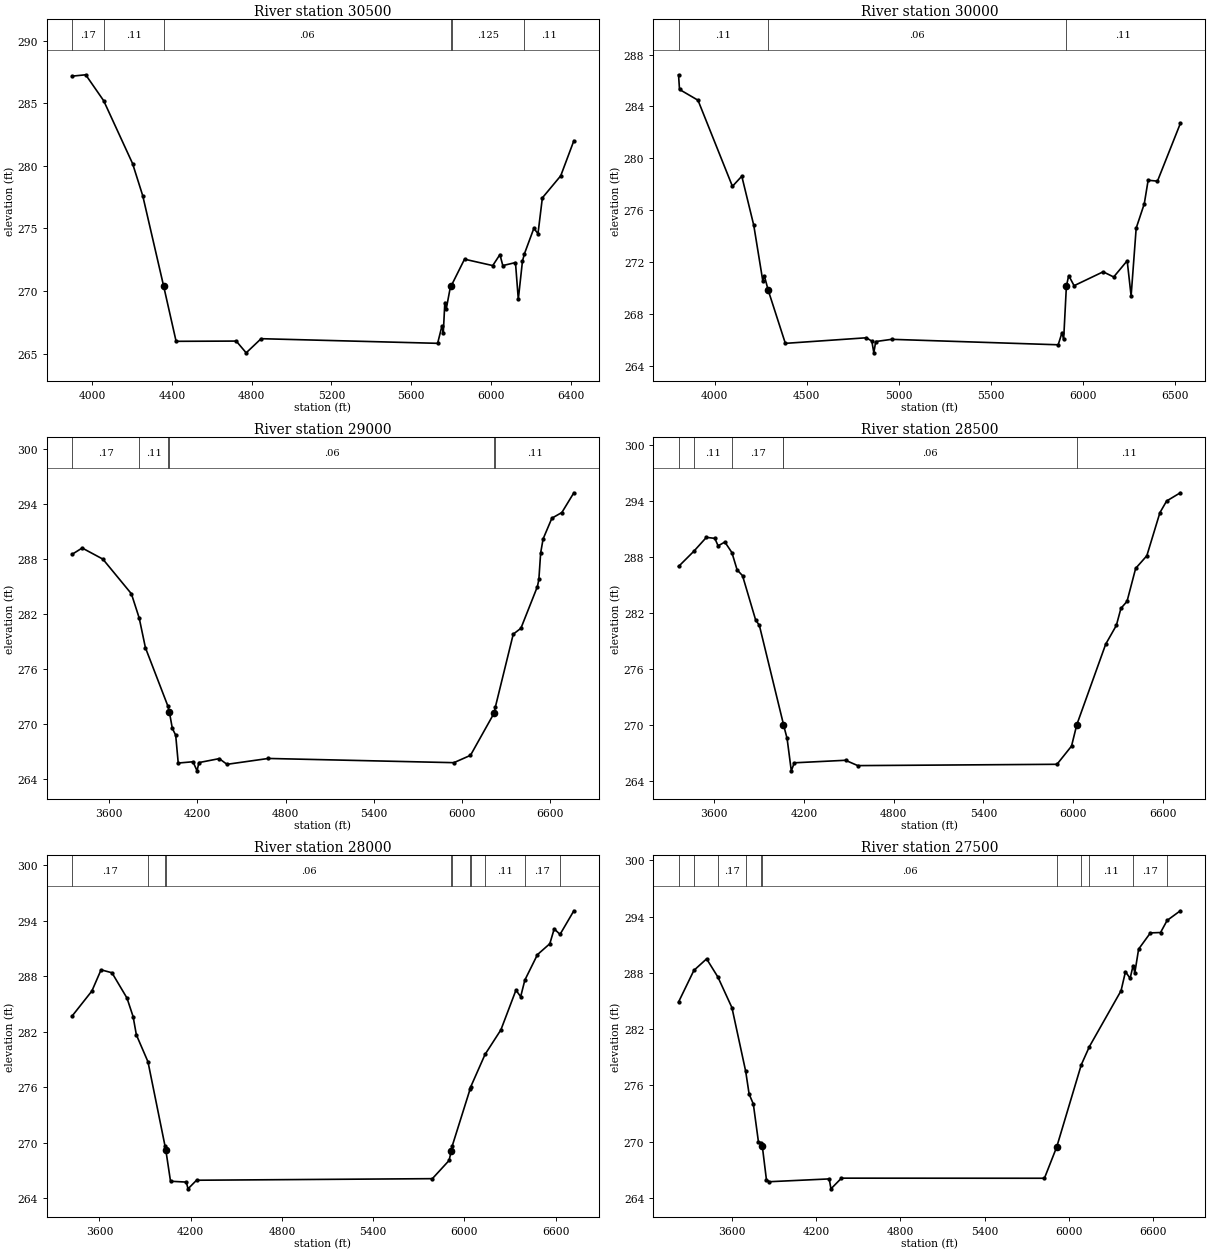
Type RM Length L Ch R = 1 ,30500   ,500,500,500
BEGIN DESCRIPTION:
LEWIS CREEK 61.0
END DESCRIPTION:
XS GIS Cut Line= 3
      3814379.68     10153707.57       3813321.5     10154009.82
      3812249.83      10154936.4
#Sta/Elev= 30
  3899.5  287.16  3967.9  287.27    4058   285.2    4203  280.18    4254  277.61
    4359  270.38  4421.4  265.98    4723     266  4772.9  265.06  4847.8  266.19
  5733.3  265.82  5755.2  267.22  5761.8  266.68  5769.5  269.08  5776.1  268.53
    5798  270.38  5804.6  270.51  5868.2  272.54  6009.7  272.03  6045.9  272.91
  6060.2  272.03  6123.8  272.27    6138  269.34  6158.9  272.39  6168.9  272.98
  6215.9     275  6236.8  274.58  6258.7  277.44  6350.8   279.2  6416.7     282
#Mann= 6 ,-1 , 0
  3899.5     .17       0    4058     .11       0    4359     .06       0
    5798     .08       0  5804.6    .125       0  6168.9     .11       0
Bank Sta=4359,5798
XS Rating Curve= 0 ,0
Exp/Cntr=0.3,0.1

Type RM Length L Ch R = 1 ,30000   ,1000,1000,1000
BEGIN DESCRIPTION:
LEWIS CREEK 60.0
END DESCRIPTION:
XS GIS Cut Line= 3
      3814015.03     10152931.55      3813027.85     10153605.69
      3812151.38     10154857.32
#Sta/Elev= 30
  3804.6  286.44  3809.9  285.31  3910.2  284.48  4097.1  277.85  4147.9  278.63
  4212.9  274.85  4261.7  270.59  4270.5  270.95  4291.5  269.84  4384.3  265.76
  4823.9  266.19  4853.7  265.93  4864.6  265.03  4874.7   265.9  4961.4  266.07
  5865.1  265.65    5886  266.59  5894.7  266.06  5909.6  270.16  5922.2  270.98
  5951.4   270.2  6109.2  271.27  6166.3  270.87  6239.6  272.12  6260.9  269.41
  6288.4  274.63  6332.4  276.51  6353.3  278.32  6403.9  278.25    6528  282.69
#Mann= 3 , 0 , 0
  3804.6     .11       0  4291.5     .06       0  5909.6     .11       0
Bank Sta=4291.5,5909.6
XS Rating Curve= 0 ,0
Exp/Cntr=0.3,0.1

Type RM Length L Ch R = 1 ,29000   ,500,500,500
BEGIN DESCRIPTION:
LEWIS CREEK 58.0
END DESCRIPTION:
XS GIS Cut Line= 3
      3812402.89     10151392.69      3812238.11     10153037.16
      3811528.69     10154647.85
#Sta/Elev= 30
  3347.3  288.52    3416  289.21  3556.7     288  3750.8  284.22  3803.8  281.58
  3846.2  278.34  3998.9  271.98    4009  271.35  4029.1  269.55    4052  268.81
  4069.3  265.77  4169.8  265.91  4197.3  264.92    4210  265.82  4348.2  266.25
  4400.9  265.63  4682.3  266.27    5944  265.81  6056.9  266.61  6217.2   271.2
  6225.7  271.85  6347.8  279.82  6399.9  280.46  6512.2  285.01    6522  285.79
  6534.1  288.66  6550.8   290.2  6610.5  292.46  6678.4  293.08    6760  295.23
#Mann= 6 ,-1 , 0
  3347.3     .17       0  3803.8     .11       0  3998.9     .08       0
    4009     .06       0  6217.2     .08       0  6225.7     .11       0
Bank Sta=4009,6217.2
XS Rating Curve= 0 ,0
Exp/Cntr=0.3,0.1

Type RM Length L Ch R = 1 ,28500   ,500,500,500
BEGIN DESCRIPTION:
LEWIS CREEK 57.0
END DESCRIPTION:
XS GIS Cut Line= 3
      3812305.66     10151371.89      3811756.99     10152915.47
       3811437.6     10154601.08
#Sta/Elev= 30
  3361.8  286.96  3464.6   288.6    3548  290.08  3604.4  289.97  3626.3  289.17
  3671.4  289.58  3718.5  288.45  3753.3   286.6  3789.5  285.98  3876.7  281.26
  3902.2  280.65  4061.8  270.15  4063.2  270.03  4087.3  268.56  4115.5  265.09
  4135.7  265.95  4477.8  266.22  4559.7  265.65  5891.2  265.79  5988.5  267.74
  6023.5  270.02  6216.9  278.65  6288.1  280.66  6318.6  282.48  6359.4  283.23
  6417.1  286.76  6491.7  288.11  6579.1  292.72    6624  293.97  6715.6  294.85
#Mann= 6 ,-1 , 0
  3361.8     .17       0  3464.6     .11       0  3718.5     .17       0
  4061.8     .08       0  4063.2     .06       0  6023.5     .11       0
Bank Sta=4063.2,6023.5
XS Rating Curve= 0 ,0
Exp/Cntr=0.3,0.1

Type RM Length L Ch R = 1 ,28000   ,500,500,500
BEGIN DESCRIPTION:
LEWIS CREEK 56.0
END DESCRIPTION:
XS GIS Cut Line= 3
      3811819.55     10151385.78      3811260.41     10152863.22
      3811340.38     10154580.25
#Sta/Elev= 30
  3420.3  283.71  3550.6  286.42  3610.9  288.71  3682.6  288.39  3781.2  285.66
  3821.6  283.65    3843  281.68  3919.3  278.77  4031.3  269.67  4036.6  269.23
  4067.5  265.86  4171.4  265.77  4182.4  265.04  4238.6  265.97  5788.7  266.14
  5898.8  268.11    5913  269.14  5918.9  269.65  6036.6  275.81  6040.3  276.04
  6135.2  279.57  6239.2  282.22  6338.2  286.51  6369.3  285.81  6396.7   287.6
  6479.5  290.35  6560.8  291.53  6589.6  293.13  6628.1  292.54  6718.9  295.09
#Mann= 11 ,-1 , 0
  3420.3     .17       0  3919.3     .11       0  4031.3     .08       0
  4036.6     .06       0    5913     .08       0  5918.9     .17       0
  6036.6     .11       0  6040.3     .17       0  6135.2     .11       0
  6396.7     .17       0  6628.1     .11       0
Bank Sta=4036.6,5913
XS Rating Curve= 0 ,0
Exp/Cntr=0.3,0.1

Type RM Length L Ch R = 1 ,27500   ,500,500,500
BEGIN DESCRIPTION:
LEWIS CREEK 55.0
END DESCRIPTION:
XS GIS Cut Line= 3
      3811750.13     10151364.91      3810760.78     10152843.91
      3811263.96     10154566.22
#Sta/Elev= 30
  3220.6  284.88    3330  288.26  3420.5  289.49  3500.9  287.55    3601  284.28
    3699  277.48  3723.3  275.06  3753.3     274  3789.4  269.99  3810.4  269.85
  3817.5  269.47  3846.4  265.94  3867.4  265.71  4293.8  266.01  4306.1  264.95
  4380.9  266.09  5826.4  266.08  5913.8  269.41  6089.2   278.2  6146.8  280.13
  6372.2  286.09  6403.5  288.12  6436.8  287.41  6457.9  288.77  6470.3  288.01
  6497.2  290.53  6581.1  292.26  6653.5   292.3  6700.2  293.59  6794.3  294.62
#Mann= 11 ,-1 , 0
  3220.6     .17       0    3330     .11       0  3500.9     .17       0
    3699     .11       0  3810.4     .08       0  3817.5     .06       0
  5913.8     .11       0  6089.2     .17       0  6146.8     .11       0
  6457.9     .17       0  6700.2     .11       0
Bank Sta=3817.5,5913.8
XS Rating Curve= 0 ,0
Exp/Cntr=0.3,0.1

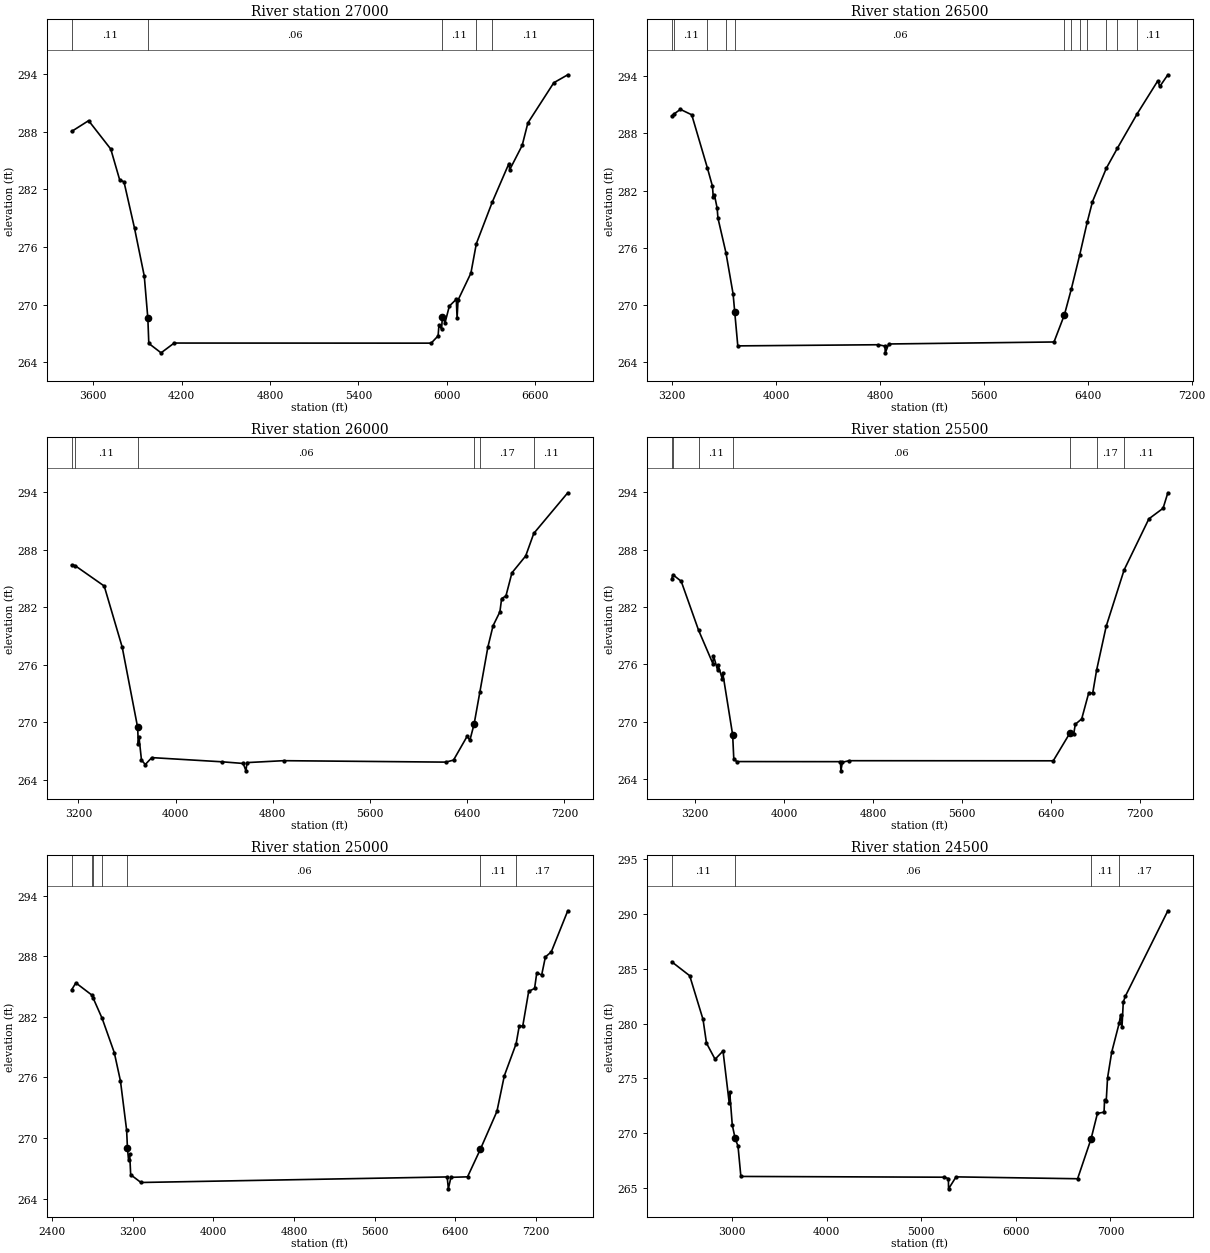
Type RM Length L Ch R = 1 ,27000   ,500,500,500
BEGIN DESCRIPTION:
LEWIS CREEK 54.0
END DESCRIPTION:
XS GIS Cut Line= 3
      3810833.45     10151434.38      3810262.14     10152872.02
      3810979.28     10154545.53
#Sta/Elev= 30
    3453  288.05  3568.1  289.17  3718.5  286.21  3778.6  283.02  3808.3  282.79
  3879.9  277.95  3945.9  272.98  3970.2  268.57  3976.7  265.96    4060  264.98
  4148.9     266  5893.5  265.99  5940.6  266.75  5946.1  267.85  5964.2  267.46
  5969.6  268.75  5987.8  268.13  6016.8  269.85  6063.9  270.56  6069.4  268.63
    6076  270.48  6163.1  273.28    6200  276.35  6308.8  280.71  6421.2   284.7
  6426.6  284.06  6511.2  286.59  6549.9  288.93  6725.8  293.12  6820.7  293.95
#Mann= 5 ,-1 , 0
    3453     .11       0  3970.2     .06       0  5969.6     .11       0
    6200     .17       0  6308.8     .11       0
#XS Ineff= 2 , 0
       0                  5969.6       0  268.75
Permanent Ineff=
       F       F
Bank Sta=3970.2,5969.6
XS Rating Curve= 0 ,0
Exp/Cntr=0.3,0.1

Type RM Length L Ch R = 1 ,26500   ,500,500,500
BEGIN DESCRIPTION:
LEWIS CREEK 53.0
END DESCRIPTION:
XS GIS Cut Line= 3
      3810757.03     10151406.66      3809763.73     10152911.97
      3810895.95     10154580.25
#Sta/Elev= 30
  3196.5  289.83  3212.3  290.02  3263.1  290.52  3350.4  289.95  3470.7  284.38
    3510  282.45    3516  281.35  3525.1  281.55  3546.2  280.14  3552.1  279.12
  3613.5  275.49    3669  271.14  3681.6  269.22    3705   265.7  4786.5  265.82
  4837.7  265.68  4840.6  264.97  4867.1   265.9  6139.6  266.11  6219.5  268.95
  6272.9  271.66  6337.6  275.25  6394.9  278.66  6435.9  280.84  6543.1  284.36
  6627.9  286.45  6781.1  290.08    6939  293.52    6954  292.92  7016.2  294.15
#Mann= 12 ,-1 , 0
  3196.5     .17       0  3212.3     .11       0  3470.7     .17       0
  3613.5     .11       0  3681.6     .06       0  6219.5     .11       0
  6272.9     .17       0  6337.6     .11       0  6394.9     .17       0
  6543.1     .11       0  6627.9     .17       0  6781.1     .11       0
Bank Sta=3681.6,6219.5
XS Rating Curve= 0 ,0
Exp/Cntr=0.3,0.1

Type RM Length L Ch R = 1 ,26000   ,500,500,500
BEGIN DESCRIPTION:
LEWIS CREEK 52.0
END DESCRIPTION:
XS GIS Cut Line= 3
      3809882.04     10151267.75       3809276.8     10153021.98
      3810812.61     10154635.79
#Sta/Elev= 30
  3144.3  286.39  3171.2  286.34  3412.3   284.2  3560.4  277.82  3687.3  269.46
  3693.2  267.71  3698.4  268.45    3719  266.04  3750.3  265.58  3803.7   266.3
  4385.5  265.86  4556.1  265.69    4579  264.92  4587.3  265.78  4888.7  265.98
  6223.9  265.83  6287.4  266.04  6400.6  268.55  6421.7  268.09  6457.2  269.82
  6504.5  273.16  6570.5  277.85    6613  280.06  6669.2  281.51  6683.4  282.89
  6718.9  283.17  6768.3  285.58  6881.5  287.34    6948  289.69  7227.8  293.93
#Mann= 6 ,-1 , 0
  3144.3     .17       0  3171.2     .11       0  3687.3     .06       0
  6457.2     .11       0  6504.5     .17       0    6948     .11       0
Bank Sta=3687.3,6457.2
XS Rating Curve= 0 ,0
Exp/Cntr=0.3,0.1

Type RM Length L Ch R = 1 ,25500   ,500,500,500
BEGIN DESCRIPTION:
LEWIS CREEK 51.0
END DESCRIPTION:
XS GIS Cut Line= 3
      3809270.93     10151198.33      3808795.99     10153153.36
       3810708.4     10154691.31
#Sta/Elev= 30
  2988.1  284.95  2998.4  285.38  3073.3  284.69  3229.6  279.57  3358.7  276.07
  3363.9  276.91  3400.5  275.41  3405.6  275.92  3442.3   274.5  3447.4  275.08
  3536.3  268.63  3546.6  266.13  3572.7  265.83  4506.9  265.82  4510.8  264.86
  4524.3  265.76  4585.3  265.92  6422.4  265.91  6571.2  268.79  6606.4  268.69
  6620.8  269.73  6678.4  270.29  6742.4  273.04  6777.6  272.98  6812.6  275.39
  6899.2  279.99  7060.4  285.88  7283.2  291.22  7411.1  292.33  7454.1  293.95
#Mann= 7 ,-1 , 0
  2988.1     .11       0  2998.4     .17       0  3229.6     .11       0
  3536.3     .06       0  6571.2     .11       0  6812.6     .17       0
  7060.4     .11       0
Bank Sta=3536.3,6571.2
XS Rating Curve= 0 ,0
Exp/Cntr=0.3,0.1

Type RM Length L Ch R = 1 ,25000   ,500,500,500
BEGIN DESCRIPTION:
LEWIS CREEK 50.0
END DESCRIPTION:
XS GIS Cut Line= 3
      3809208.45     10151170.48      3808384.66     10153433.19
      3810540.06     10154732.63
#Sta/Elev= 30
    2592   284.7  2633.7  285.38    2794  284.16  2803.9  283.91    2895  281.85
  3015.3  278.46  3076.5  275.65  3137.6  270.78    3146  268.96  3156.7  267.84
  3168.2  268.38  3177.9  266.36  3279.9  265.59    6320  266.14  6331.4  264.96
  6356.9   266.1  6521.9  266.15 6649.86   268.9  6813.6  272.64  6886.9  276.17
  7004.2  279.35  7034.4  281.06  7070.5  281.13  7128.9  284.54  7187.3  284.83
  7209.2  286.38  7257.7  286.16  7294.6  287.95  7352.9  288.45  7516.8  292.53
#Mann= 7 ,-1 , 0
    2592     .17       0    2794     .11       0  2803.9     .17       0
    2895     .11       0    3146     .06       0 6649.86     .11       0
  7004.2     .17       0
Bank Sta=3146,6649.86
XS Rating Curve= 0 ,0
Exp/Cntr=0.3,0.1

Type RM Length L Ch R = 1 ,24500   ,500,500,500
BEGIN DESCRIPTION:
LEWIS CREEK 49.0
END DESCRIPTION:
XS GIS Cut Line= 3
      3808409.82     10151177.49      3808033.87     10153789.47
      3810422.05     10154836.44
#Sta/Elev= 30
  2361.1  285.63    2551  284.36  2691.9  280.38  2728.4  278.22  2819.4  276.75
  2903.3   277.5  2968.7  272.78  2973.8  273.77  3001.2  270.76  3031.5  269.53
  3061.8  268.84  3092.1  266.07  5239.8     266  5286.6  265.88  5288.5  264.94
  5367.6  266.03  6653.1  265.86    6795  269.48  6862.7  271.81  6932.9  271.93
  6938.3  273.06  6956.2  272.99  6969.7  275.04  7013.9   277.4  7093.2  280.05
  7107.4  280.77  7122.6   279.7  7136.2  281.97  7159.6  282.52  7607.6  290.28
#Mann= 4 ,-1 , 0
  2361.1     .11       0  3031.5     .06       0    6795     .11       0
  7093.2     .17       0
Bank Sta=3031.5,6795
XS Rating Curve= 0 ,0
Exp/Cntr=0.3,0.1

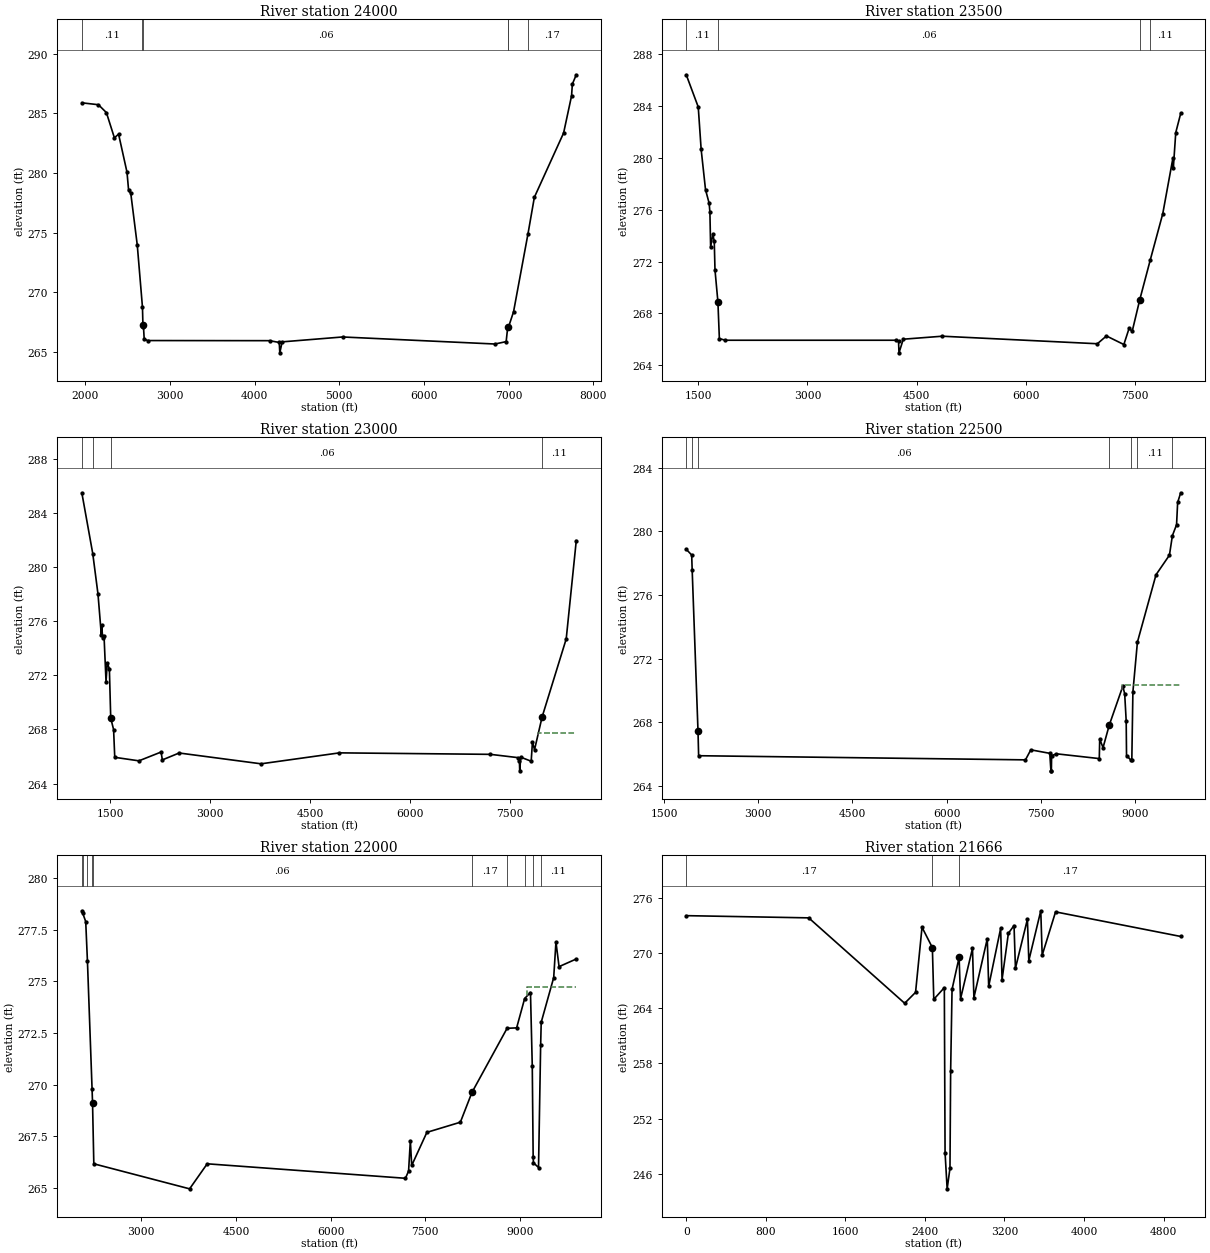
Type RM Length L Ch R = 1 ,24000   ,500,500,500
BEGIN DESCRIPTION:
LEWIS CREEK 48.0
END DESCRIPTION:
XS GIS Cut Line= 3
      3808312.61     10151170.47      3807682.59     10154145.29
      3810331.73     10155045.14
#Sta/Elev= 30
  1959.2  285.89  2155.1  285.73  2249.4  285.07  2343.6  282.96  2393.3  283.26
  2492.7  280.07  2511.8  278.54  2537.3   278.3    2614  273.96  2675.3  268.75
  2681.2  267.12  2686.3  267.23  2695.8  266.08  2736.7  265.96  4175.5  265.95
  4290.4   265.8  4297.1  264.93  4324.6  265.85    5038  266.26  6837.4  265.67
  6969.9  265.87    6989  267.13  6994.3  267.02  7057.1  268.37  7227.7  274.91
  7302.9  277.97  7648.2  283.36  7742.3  286.48  7751.5  287.46  7797.8  288.24
#Mann= 6 ,-1 , 0
  1959.2     .11       0  2675.3     .08       0  2686.3     .06       0
    6989     .08       0  6994.3     .11       0  7227.7     .17       0
Bank Sta=2686.3,6989
XS Rating Curve= 0 ,0
Exp/Cntr=0.3,0.1

Type RM Length L Ch R = 1 ,23500   ,500,500,500
BEGIN DESCRIPTION:
LEWIS CREEK 47.0
END DESCRIPTION:
XS GIS Cut Line= 3
      3807486.22     10150816.38      3807310.06     10154478.25
      3810318.71     10155344.62
#Sta/Elev= 30
  1333.9  286.38  1498.8   283.9  1538.8  280.63  1598.9  277.53    1649  276.48
    1659  275.81    1669  273.11    1699  274.11    1719  273.56    1729  271.35
  1769.1   268.9  1789.1  266.07  1869.2  265.94  4211.9  265.94    4252  265.87
  4258.4  264.97  4317.3  266.02  4852.7  266.25  6985.3  265.67  7110.2  266.27
  7349.5  265.61  7422.4  266.87    7464  266.62  7568.1  269.06    7713  272.13
  7884.3  275.68  8024.2  279.97  8029.4  279.18  8063.1  281.93  8130.9   283.4
#Mann= 4 ,-1 , 0
  1333.9     .11       0  1769.1     .06       0  7568.1     .17       0
    7713     .11       0
Bank Sta=1769.1,7568.1
XS Rating Curve= 0 ,0
Exp/Cntr=0.3,0.1

Type RM Length L Ch R = 1 ,23000   ,500,500,500
BEGIN DESCRIPTION:
LEWIS CREEK 46.0
END DESCRIPTION:
XS GIS Cut Line= 4
      3807326.49     10150830.23      3806882.98     10154727.48
      3806906.58     10154745.57      3810264.72     10155604.55
#Sta/Elev= 30
  1077.6  285.51  1241.6  281.01    1320  278.02  1370.2     275  1375.2  275.71
  1390.4  274.77  1410.6  274.94  1440.8  271.53  1459.7  272.94  1491.1  272.47
  1511.2  268.84  1554.3  267.99  1571.6  265.94  1933.9  265.68  2266.1  266.33
  2286.2  265.75  2537.8  266.26  3766.8  265.46  4943.2  266.27  7207.3  266.16
  7615.5  265.92  7642.5   265.7  7647.6  264.94  7663.2  265.95  7819.6  265.65
  7838.6  267.08  7869.6   266.5  7983.1  268.92  8345.1   274.7    8496  281.97
#Mann= 4 ,-1 , 0
  1077.6     .11       0  1241.6    .125       0  1511.2     .06       0
  7983.1     .11       0
#XS Ineff= 2 , 0
       0                  7921.2       0  267.71
Permanent Ineff=
       F       F
Bank Sta=1511.2,7983.1
XS Rating Curve= 0 ,0
Exp/Cntr=0.3,0.1

Type RM Length L Ch R = 1 ,22500   ,500,500,500
BEGIN DESCRIPTION:
LEWIS CREEK 45.0
END DESCRIPTION:
XS GIS Cut Line= 4
      3806738.75       10151565.      3806387.83     10154694.09
      3806638.99     10154976.06      3810668.83     10156624.06
#Sta/Elev= 30
  1851.3  278.88  1937.9  278.52    1946  277.55  2038.5  267.47  2048.6  265.91
  7257.5  265.65  7342.7  266.28  7644.7  266.06  7663.3  264.96  7670.4  264.96
  7674.1  265.91  7751.6  266.03  8433.9  265.73  8440.7  266.95  8494.2  266.42
  8592.6  267.83  8809.3  270.28  8838.8   269.8  8862.8   268.1  8868.2  265.92
  8936.8  265.64  8952.5  265.65  8969.6  269.92  9041.8  273.05  9338.2  277.28
  9551.9  278.51  9599.3  279.74  9665.5  280.42  9682.8  281.82  9731.4  282.43
#Mann= 7 ,-1 , 0
  1851.3     .17       0    1946     .11       0  2038.5     .06       0
  8592.6     .11       0  8936.8     .15       0  9041.8     .11       0
  9599.3     .17       0
#XS Ineff= 2 , 0
       0                  8790.7       0  270.37
Permanent Ineff=
       F       F
Bank Sta=2038.5,8592.6
XS Rating Curve= 0 ,0
Exp/Cntr=0.3,0.1

Type RM Length L Ch R = 1 ,22000   ,334,334,334
BEGIN DESCRIPTION:
LEWIS CREEK 44.0
END DESCRIPTION:
XS GIS Cut Line= 4
      3806565.14     10151565.01       3805970.8     10154446.66
      3806200.55     10156599.77      3808058.11     10158596.22
#Sta/Elev= 30
  2057.7  278.41  2072.2  278.29  2119.3  277.89  2146.7  275.97  2219.8  269.81
  2227.3  269.14  2247.7  266.18  3765.5  264.97  4044.4  266.18  7185.5  265.48
  7235.3  265.83  7263.2   267.3  7284.7   266.1  7525.1   267.7  8055.7  268.19
  8239.4  269.63    8796  272.73  8947.3  272.75  9074.4  274.17  9166.7  274.46
    9195  270.92  9209.2  266.53  9213.5  266.23  9294.2     266  9327.8   271.9
  9336.7  273.02  9534.6  275.18  9570.3   276.9  9619.6  275.71  9892.3  276.08
#Mann= 10 ,-1 , 0
  2057.7     .17       0  2072.2     .11       0  2146.7     .17       0
  2219.8     .08       0  2227.3     .06       0  8239.4     .17       0
    8796     .17       0  9074.4     .11       0  9213.5     .15       0
  9327.8     .11       0
#XS Ineff= 2 , 0
       0                    9110       0  274.71
Permanent Ineff=
       F       F
Bank Sta=2227.3,8239.4
XS Rating Curve= 0 ,0
Exp/Cntr=0.3,0.1

Type RM Length L Ch R = 1 ,21666   ,166,166,166
XS GIS Cut Line= 3
      3806363.09     10151716.92      3805920.02      10154046.6
      3803988.55     10155789.21
#Sta/Elev= 30
       0  274.06  1231.6  273.82  2196.8  264.54  2306.3  265.73  2371.2   272.8
  2475.3  270.59  2489.5  264.97  2595.6  266.24    2603   248.3    2624  244.38
  2652.4  246.62  2659.1  257.19  2673.3  266.06  2744.3  269.52  2758.5  265.02
  2878.8  270.51    2893  265.15  3027.5  271.55  3041.7  266.39    3162  272.68
  3176.2  267.12  3239.8  272.14  3296.6  272.99  3310.8  268.35  3431.1  273.66
  3445.3  269.18  3565.6  274.59  3579.8  269.77  3714.3  274.47  4972.8   271.8
#Mann= 3 , 0 , 0
       0     .17       0  2475.3     .06       0  2744.3     .17       0
Bank Sta=2475.3,2744.3
XS Rating Curve= 0 ,0
Exp/Cntr=0.3,0.1