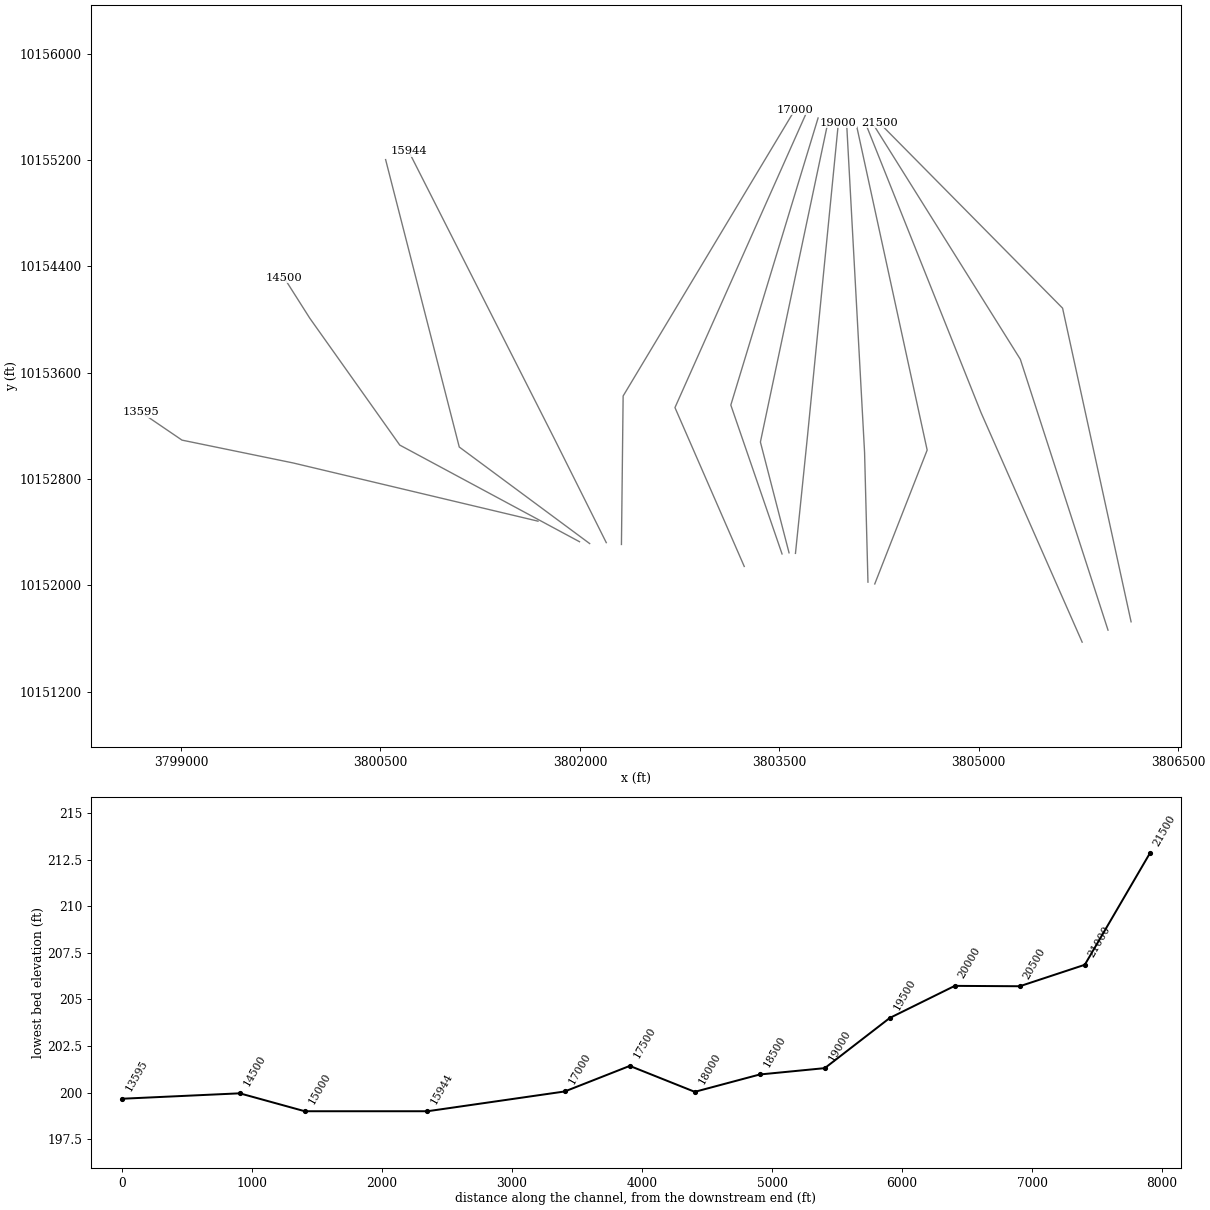
HEC-RAS study LEWIS CREEK.prj: LEWIS CREEK Base Level Engineering

--- LEWIS CREEK.g01 (geometry) --- (continued)

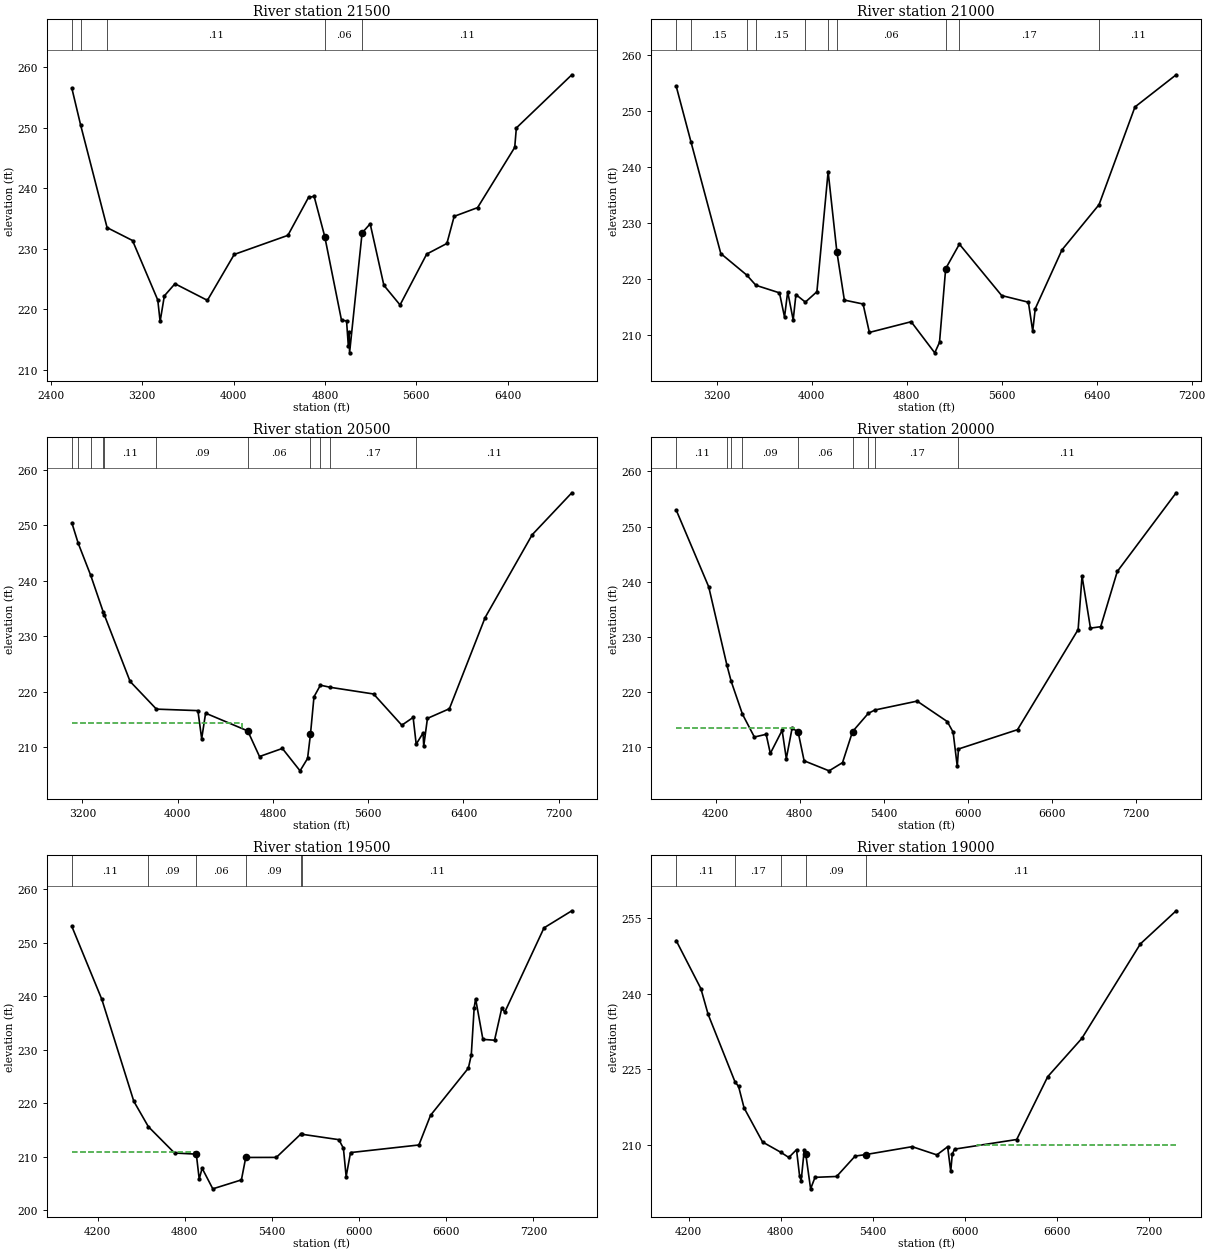
Type RM Length L Ch R = 1 ,21500   ,500,500,500
BEGIN DESCRIPTION:
LEWIS CREEK 43.0
END DESCRIPTION:
XS GIS Cut Line= 3
      3806145.93      10151726.1      3805630.62       10154086.
      3804251.47     10155481.63
#Sta/Elev= 30
  2584.5  256.53  2661.6  250.43    2893  233.51  3115.6  231.38  3336.8  221.55
  3357.3  218.01  3394.4  222.24  3487.4  224.24  3771.3   221.5  4006.2  229.08
    4476  232.23  4656.7   238.5  4705.8  238.67  4798.7  232.04  4945.8  218.18
  4989.7  218.12  5005.6  213.88  5012.6  216.28  5016.1  212.83  5125.8  232.64
  5196.5  234.14  5316.6  223.98  5458.1  220.74  5691.5  229.14  5868.2  230.89
  5931.9  235.37  6136.9  236.81  6462.2  246.76  6476.4  249.97  6962.1  258.75
#Mann= 5 ,-1 , 0
  2584.5     .17       0  2661.6     .15       0    2893     .11       0
  4798.7     .06       0  5125.8     .11       0
#XS Ineff= 2 , 0
       0  4705.8  238.67  5196.5       0  234.14
Permanent Ineff=
       F       F
Bank Sta=4798.7,5125.8
XS Rating Curve= 0 ,0
Exp/Cntr=0.3,0.1

Type RM Length L Ch R = 1 ,21000   ,500,500,500
BEGIN DESCRIPTION:
LEWIS CREEK 42.0
END DESCRIPTION:
XS GIS Cut Line= 3
      3805972.33     10151663.56      3805312.84      10153701.3
      3804215.38     10155455.24
#Sta/Elev= 30
  2858.2  254.43  2983.2  244.45    3234  224.57  3452.6  220.73  3529.6  218.91
    3728  217.56  3770.6  213.25  3797.3  217.76  3843.6  212.72  3866.6  217.25
  3946.1  215.91  4043.3  217.76  4137.9   239.2  4211.5  224.88  4274.5  216.27
  4432.2  215.57  4485.2   210.5  4837.2  212.41  5035.8  206.86  5075.9  208.73
  5127.8  221.88  5243.3  226.25  5599.4  217.08  5824.5  215.89  5860.9  210.74
  5882.3  214.74  6107.5  225.23  6419.4  233.29    6722  250.72    7069  256.46
#Mann= 10 ,-1 , 0
  2858.2     .17       0  2983.2     .15       0  3452.6     .11       0
  3529.6     .15       0  3946.1     .11       0  4137.9     .09       0
  4211.5     .06       0  5127.8     .09       0  5243.3     .17       0
  6419.4     .11       0
#XS Ineff= 2 , 0
       0  4137.9   239.2  5243.3       0  226.25
Permanent Ineff=
       F       F
Bank Sta=4211.5,5127.8
XS Rating Curve= 0 ,0
Exp/Cntr=0.3,0.1

Type RM Length L Ch R = 1 ,20500   ,500,500,500
BEGIN DESCRIPTION:
LEWIS CREEK 41.0
END DESCRIPTION:
XS GIS Cut Line= 3
      3805777.87     10151573.31      3805016.52     10153301.65
      3804160.26      10155447.2
#Sta/Elev= 30
  3111.4  250.44  3164.5  246.77  3270.1  240.95  3375.8  234.31  3383.3  233.88
  3600.7  221.83  3821.6  216.84    4170  216.57  4201.7   211.5  4234.5  216.11
  4588.5  212.91  4687.3  208.29  4879.2  209.75  5027.9  205.71  5090.9  207.94
  5115.1  212.28  5144.8  219.06  5198.7  221.16    5283  220.77  5645.4  219.57
  5882.3  213.94  5977.5  215.34  6003.2  210.52    6061  212.54  6066.4  210.15
  6097.6  215.17    6282  216.91  6582.1  233.36  6977.2  248.29  7310.1  255.86
#Mann= 11 ,-1 , 0
  3111.4     .11       0  3164.5     .15       0  3270.1     .11       0
  3375.8     .15       0  3383.3     .11       0  3821.6     .09       0
  4588.5     .06       0  5115.1     .09       0  5198.7     .11       0
    5283     .17       0  6003.2     .11       0
#XS Ineff= 2 , 0
       0  4541.8  214.29  5198.7       0  221.16
Permanent Ineff=
       F       F
Bank Sta=4588.5,5115.1
XS Rating Curve= 0 ,0
Exp/Cntr=0.3,0.1

Type RM Length L Ch R = 1 ,20000   ,500,500,500
BEGIN DESCRIPTION:
LEWIS CREEK 40.0
END DESCRIPTION:
XS GIS Cut Line= 3
      3804217.85     10152011.06      3804612.03     10153018.38
      3804083.68     10155447.18
#Sta/Elev= 30
  3918.3  253.02  4150.4  239.09  4280.7  224.84  4310.4  221.98  4390.8  216.02
  4476.1  211.86  4560.2  212.35    4590  208.89  4674.2  213.07    4704  207.95
  4745.2  213.46  4788.1   212.8  4831.1  207.55  5009.3  205.73  5105.1  207.22
  5176.7  212.85  5289.3  216.16  5336.5  216.76  5637.3  218.37  5852.2  214.67
  5894.1  212.75  5923.8  206.54  5932.6  209.69  6353.6  213.19  6786.2  231.34
  6814.1  241.05  6874.2   231.6  6947.2  231.86  7065.5  241.87  7485.6  256.14
#Mann= 9 ,-1 , 0
  3918.3     .11       0  4280.7     .17       0  4310.4     .15       0
  4390.8     .09       0  4788.1     .06       0  5176.7     .09       0
  5289.3     .11       0  5336.5     .17       0  5932.6     .11       0
#XS Ineff= 2 , 0
       0  4758.3  213.47  5289.3       0  216.16
Permanent Ineff=
       F       F
Bank Sta=4788.1,5176.7
XS Rating Curve= 0 ,0
Exp/Cntr=0.3,0.1

Type RM Length L Ch R = 1 ,19500   ,500,500,500
BEGIN DESCRIPTION:
LEWIS CREEK 39.0
END DESCRIPTION:
XS GIS Cut Line= 3
      3804166.77     10152024.63      3804141.23       10153001.
      3804007.05     10155462.14
#Sta/Elev= 30
  4023.3  253.01  4229.8  239.38  4449.9  220.35  4549.9  215.62    4730   210.7
    4880  210.49    4900  205.83    4920  207.86  4993.5  204.01  5190.4  205.68
  5220.4  209.87  5430.7  209.88    5601  214.28  5607.3   214.2  5861.4  213.19
  5892.6  211.58  5911.4   206.3  5941.5  210.78  6412.2   212.2  6492.3  217.74
  6752.7  226.55  6772.7  228.98  6792.7  237.85  6802.5   239.5  6852.8  231.92
  6932.9  231.76    6983  237.79    7003     237  7273.4  252.74  7464.8  255.93
#Mann= 6 ,-1 , 0
  4023.3     .11       0  4549.9     .09       0    4880     .06       0
  5220.4     .09       0    5601     .17       0  5607.3     .11       0
#XS Ineff= 2 , 0
       0    4870   210.8    5601       0  214.28
Permanent Ineff=
       F       F
Bank Sta=4880,5220.4
XS Rating Curve= 0 ,0
Exp/Cntr=0.3,0.1

Type RM Length L Ch R = 1 ,19000   ,500,500,500
BEGIN DESCRIPTION:
LEWIS CREEK 38.0
END DESCRIPTION:
XS GIS Cut Line= 3
      3803621.43     10152241.04      3803711.25     10153116.95
      3803944.55     10155482.97
#Sta/Elev= 30
  4119.5  250.53  4280.4  241.01  4327.6  235.91  4503.4  222.48  4526.1  221.62
  4561.8  217.37  4682.5   210.6    4801  208.57  4853.4  207.54  4903.6  209.08
  4923.7  203.85  4933.8  202.91  4953.9  209.03  4963.9   208.2  4995.5  201.32
  5024.2   203.6  5164.9  203.77  5285.5  207.81  5355.8  208.12  5657.3  209.68
  5818.1  208.05  5888.4  209.66  5908.5  204.78  5918.6  208.19  5933.6  209.19
  6338.4   211.1  6540.7  223.56  6762.6  231.13  7144.5  249.88  7377.5  256.44
#Mann= 5 ,-1 , 0
  4119.5     .11       0  4503.4     .17       0    4801     .15       0
  4963.9     .09       0  5355.8     .11       0
#XS Ineff= 2 , 0
       0                  6079.3       0  209.98
Permanent Ineff=
       F       F
Bank Sta=4963.9,5355.8
XS Rating Curve= 0 ,0
Exp/Cntr=0.3,0.1

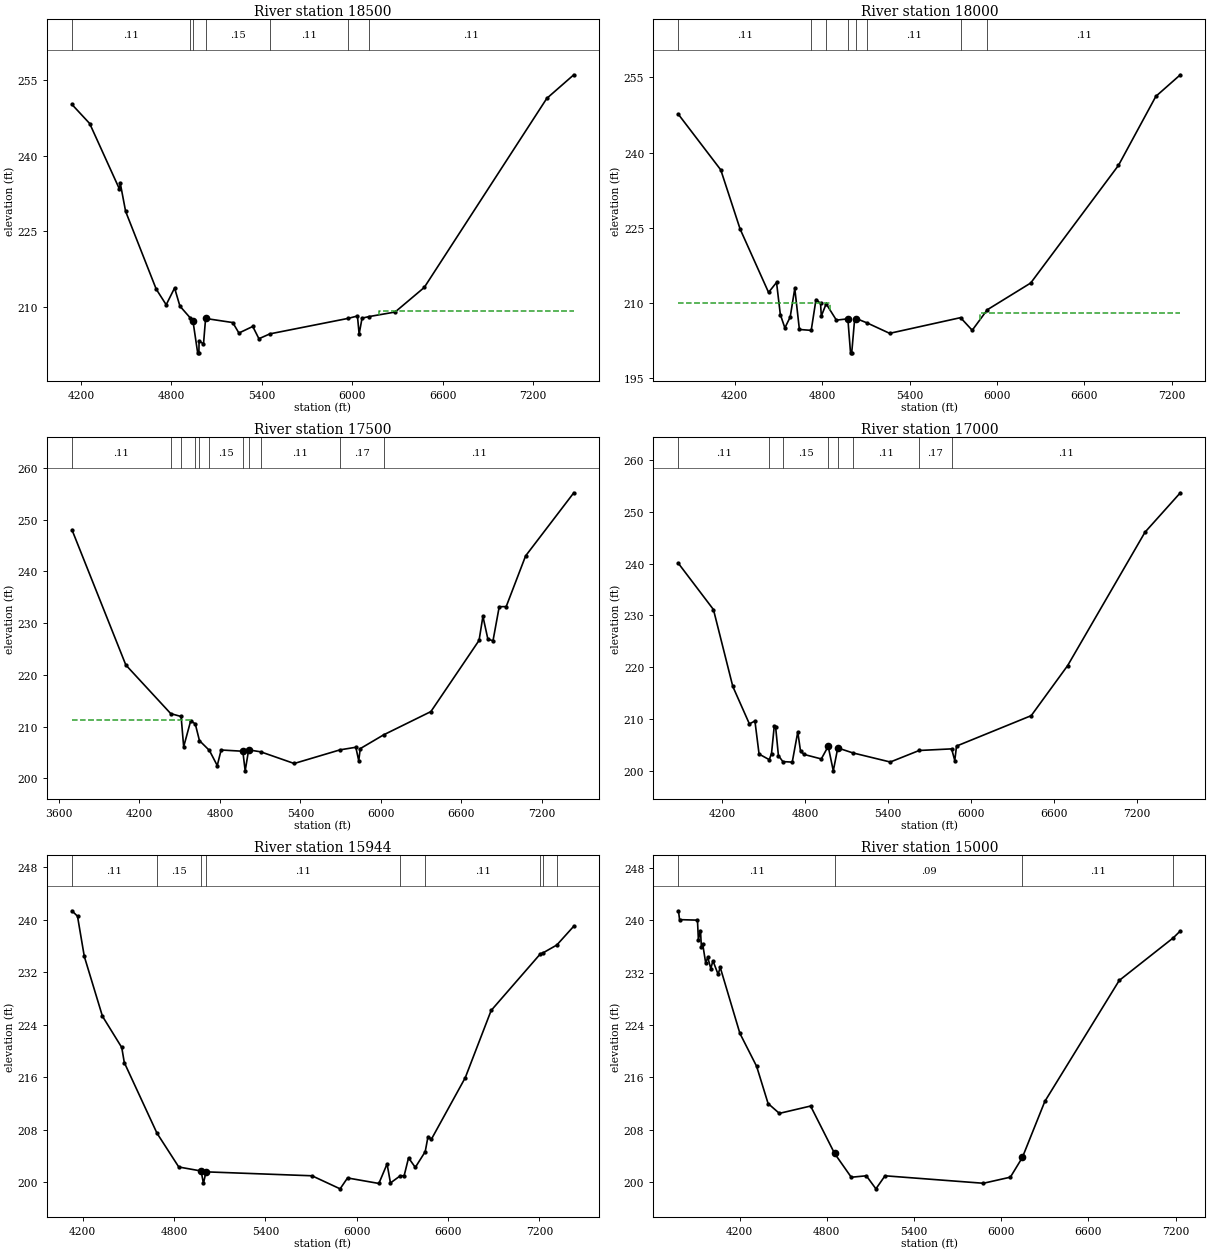
Type RM Length L Ch R = 1 ,18500   ,500,500,500
BEGIN DESCRIPTION:
LEWIS CREEK 37.0
END DESCRIPTION:
XS GIS Cut Line= 3
      3803573.06      10152245.3      3803357.68     10153078.82
      3803868.08     10155496.53
#Sta/Elev= 30
  4139.1  250.12  4256.7  246.35  4454.7  233.36  4459.9  234.55  4495.4  228.97
  4698.6  213.58  4764.8  210.49  4820.5  213.81    4856  210.22    4924  207.91
  4942.4  207.31  4973.8  200.98    4982  200.98  4983.1  203.36  5012.5  202.73
  5026.4  207.78  5206.7  206.97  5247.6   204.9  5339.6   206.2  5380.5  203.77
    5453  204.73  5974.9  207.81  6034.6  208.27  6045.8  204.69  6065.2  207.84
  6110.8  208.15  6284.4  209.05  6478.3  213.92  7291.7  251.32    7471  255.99
#Mann= 7 ,-1 , 0
  4139.1     .11       0    4924     .17       0  4942.4     .09       0
  5026.4     .15       0    5453     .11       0  5974.9     .17       0
  6110.8     .11       0
#XS Ineff= 2 , 0
       0                  6177.6       0  209.17
Permanent Ineff=
       F       F
Bank Sta=4942.4,5026.4
XS Rating Curve= 0 ,0
Exp/Cntr=0.3,0.1

Type RM Length L Ch R = 1 ,18000   ,500,500,500
BEGIN DESCRIPTION:
LEWIS CREEK 36.0
END DESCRIPTION:
XS GIS Cut Line= 3
      3803520.44     10152236.75       3803135.2     10153357.06
      3803791.53     10155516.94
#Sta/Elev= 30
  3815.3  247.61  4105.4  236.55    4238  224.75  4433.2   212.1  4487.9   214.1
  4513.9  207.69  4545.1  205.02  4581.6   207.2    4613  212.89  4644.7  204.71
  4725.7  204.53  4758.5  210.68  4789.7  209.92    4795  207.38  4828.3  209.83
  4898.5  206.57  4977.1  206.84  4995.4  200.05  5003.6  200.05  5023.1  206.62
  5035.5  206.88  5109.7  206.01  5263.7  203.94  5750.1  207.07  5829.9  204.55
  5933.3  208.64  6231.2  213.98  6833.2  237.45  7089.6  251.22  7257.4  255.52
#Mann= 8 ,-1 , 0
  3815.3     .11       0  4725.7     .17       0  4828.3     .15       0
  4977.1     .09       0  5035.5     .15       0  5109.7     .11       0
  5750.1     .17       0  5933.3     .11       0
#XS Ineff= 2 , 0
       0  4857.5   209.9  5881.5       0  208.04
Permanent Ineff=
       F       F
Bank Sta=4977.1,5035.5
XS Rating Curve= 0 ,0
Exp/Cntr=0.3,0.1

Type RM Length L Ch R = 1 ,17500   ,500,500,500
BEGIN DESCRIPTION:
LEWIS CREEK 35.0
END DESCRIPTION:
XS GIS Cut Line= 3
      3803236.23     10152142.69      3802715.05      10153337.9
      3803708.39     10155566.23
#Sta/Elev= 30
  3696.1  248.06    4098  221.91  4433.2   212.5  4510.4  211.95  4529.5   206.1
  4581.8   211.1  4615.9  210.53  4647.3  207.28  4721.3  205.39  4780.1  202.46
  4808.9  205.47  4970.7  205.23  4988.4  201.44  5014.1  205.49  5103.9  205.12
  5353.8  202.86  5696.2   205.5  5813.7     206  5835.6  203.38  5846.5  205.73
  6021.2   208.4  6373.8   212.9  6733.1  226.67  6761.8  231.32    6799  226.89
    6837   226.6  6883.5  233.18  6935.4   233.2  7080.2     243  7439.7  255.21
#Mann= 11 ,-1 , 0
  3696.1     .11       0  4433.2     .15       0  4510.4     .17       0
  4615.9     .15       0  4647.3     .11       0  4721.3     .15       0
  4970.7     .09       0  5014.1     .15       0  5103.9     .11       0
  5696.2     .17       0  6021.2     .11       0
#XS Ineff= 2 , 0
       0  4588.9  211.25               0
Permanent Ineff=
       F       F
Bank Sta=4970.7,5014.1
XS Rating Curve= 0 ,0
Exp/Cntr=0.3,0.1

Type RM Length L Ch R = 1 ,17000   ,1056,1056,1056
BEGIN DESCRIPTION:
LEWIS CREEK 34.0
END DESCRIPTION:
XS GIS Cut Line= 3
      3802312.45     10152308.09       3802325.2     10153425.32
      3803618.14     10155580.19
#Sta/Elev= 30
  3882.7  240.01  4135.7  231.13  4275.7  216.32  4395.7  209.11  4435.7  209.67
  4465.7   203.3  4539.4  202.22  4555.7   203.4  4575.7  208.72  4585.7  208.44
  4605.7     203  4637.8  201.85  4705.7  201.75  4745.7  207.56  4765.7  203.84
  4792.5  203.22  4915.8  202.36  4965.8  204.79  5002.6  200.07  5035.1  204.48
  5143.3  203.53  5414.9  201.77  5623.8  203.99  5858.5   204.3  5881.4  202.06
  5894.2  204.84  6434.5   210.7  6697.7  220.33  7257.5  246.03    7513  253.62
#Mann= 8 ,-1 , 0
  3882.7     .11       0  4539.4     .17       0  4637.8     .15       0
  4965.8     .09       0  5035.1     .15       0  5143.3     .11       0
  5623.8     .17       0  5858.5     .11       0
#XS Ineff= 2 , 0
       0  4745.7  207.56               0
Permanent Ineff=
       F       F
Bank Sta=4965.8,5035.1
XS Rating Curve= 0 ,0
Exp/Cntr=0.3,0.1

Type RM Length L Ch R = 1 ,15944   ,944,944,944
BEGIN DESCRIPTION:
LEWIS CREEK 32.0
END DESCRIPTION:
XS GIS Cut Line= 3
      3802198.35     10152321.86      3801809.15     10153100.95
      3800712.62     10155265.56
#Sta/Elev= 30
  4129.1   241.4  4165.6  240.57  4210.3  234.44  4329.4  225.33  4456.3  220.56
  4473.1  218.26  4687.7   207.5    4831  202.34  4977.8  201.73  4993.1  199.83
  5009.8   201.6  5706.4     201    5891  199.01  5939.8  200.67  6145.8  199.83
  6199.6   202.8    6222  199.91  6286.5     201  6311.7     201  6340.7  203.73
  6385.2  202.28  6450.1  204.67  6468.6  206.97    6491  206.58  6713.7  215.97
  6883.4   226.2  7206.8  234.83  7226.4  235.01  7314.9  236.18  7426.5  239.05
#Mann= 9 ,-1 , 0
  4129.1     .11       0  4687.7     .15       0  4977.8     .09       0
  5009.8     .11       0  6286.5     .17       0  6450.1     .11       0
  7206.8     .17       0  7226.4     .11       0  7314.9     .17       0
Bank Sta=4977.8,5009.8
XS Rating Curve= 0 ,0
Exp/Cntr=0.3,0.1

Type RM Length L Ch R = 1 ,15000   ,500,500,500
BEGIN DESCRIPTION:
LEWIS CREEK 30.0
END DESCRIPTION:
XS GIS Cut Line= 3
      3802073.33     10152314.92      3801092.55     10153041.34
      3800538.63     10155203.83
#Sta/Elev= 30
  3779.5  241.42    3787  240.07  3910.2  239.99  3916.4  237.02    3931  238.39
  3937.3  235.82  3945.7   236.4  3966.5  233.49  3981.1   234.3    4002   232.6
  4016.6   233.8  4052.1  231.73  4066.7  232.79  4202.3  222.71  4317.1   217.7
  4396.1  212.02  4473.6  210.52  4688.6  211.64  4853.5  204.41  4968.3  200.78
    5072     201  5137.9  199.01  5200.6     201  5877.2  199.86    6063  200.79
  6145.6   203.8  6300.4  212.36  6811.8  230.79  7184.8  237.31  7232.3  238.35
#Mann= 4 ,-1 , 0
  3779.5     .11       0  4853.5     .09       0  6145.6     .11       0
  7184.8     .17       0
Bank Sta=4853.5,6145.6
XS Rating Curve= 0 ,0
Exp/Cntr=0.3,0.1

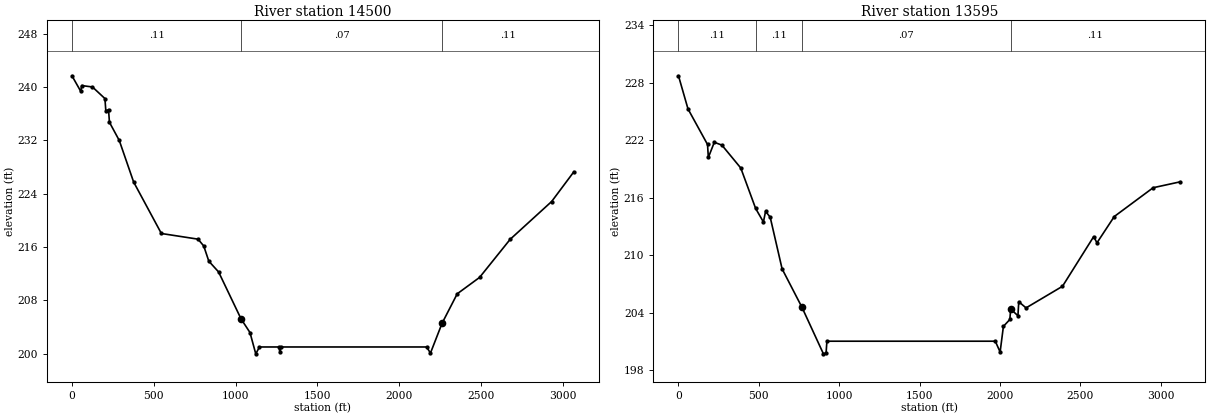
Type RM Length L Ch R = 1 ,14500   ,905,905,905
BEGIN DESCRIPTION:
LEWIS CREEK 29.0
END DESCRIPTION:
XS GIS Cut Line= 4
      3801996.98     10152328.79      3800645.06     10153055.89
      3799967.85     10154011.07      3799774.88     10154315.26
#Sta/Elev= 30
       0   241.7    53.9  239.36    59.5  240.23   125.3  240.02   201.5  238.28
   207.2  236.37   223.5  236.63   229.1  234.72   289.2  231.99   376.8  225.76
   546.4  218.03   770.4  217.18   805.2  216.16   836.2  213.88     896  212.26
  1033.3  205.21  1087.7  203.17  1123.1  199.97  1145.8     201    1263     201
  1270.7  200.28  1279.2     201    2167     201  2190.4  200.08  2261.8  204.58
    2354  208.98  2490.6  211.44  2677.6  217.16  2930.9  222.83  3066.2  227.28
#Mann= 3 , 0 , 0
       0     .11       0  1033.3     .07       0  2261.8     .11       0
Bank Sta=1033.3,2261.8
XS Rating Curve= 0 ,0
Exp/Cntr=0.3,0.1

Type RM Length L Ch R = 1 ,13595   ,126,126,126
BEGIN DESCRIPTION:
LEWIS CREEK 28.0
END DESCRIPTION:
XS GIS Cut Line= 4
      3801684.87     10152483.37      3799842.57     10152921.51
      3799007.06     10153093.21      3798697.24     10153304.02
#Sta/Elev= 30
       0  228.74    59.3  225.27   180.7  221.56   185.8   220.2   222.9  221.79
   270.2  221.49   387.5   219.1     480  214.87   528.3  213.46   541.7  214.57
   570.5  213.96   644.5  208.56   767.9  204.55   901.5  199.68   918.1  199.77
   923.2     201  1970.5     201  2000.6  199.87    2021  202.55    2061  203.27
  2066.2  204.36  2111.4  203.66  2116.5  205.13  2161.8  204.48  2388.5  206.74
  2582.5  211.93  2602.9  211.28  2710.6  214.03  2952.3  217.04  3121.4  217.66
#Mann= 4 ,-1 , 0
       0     .11       0     480     .11       0   767.9     .07       0
  2066.2     .11       0
Bank Sta=767.9,2066.2
XS Rating Curve= 0 ,0
Exp/Cntr=0.3,0.1