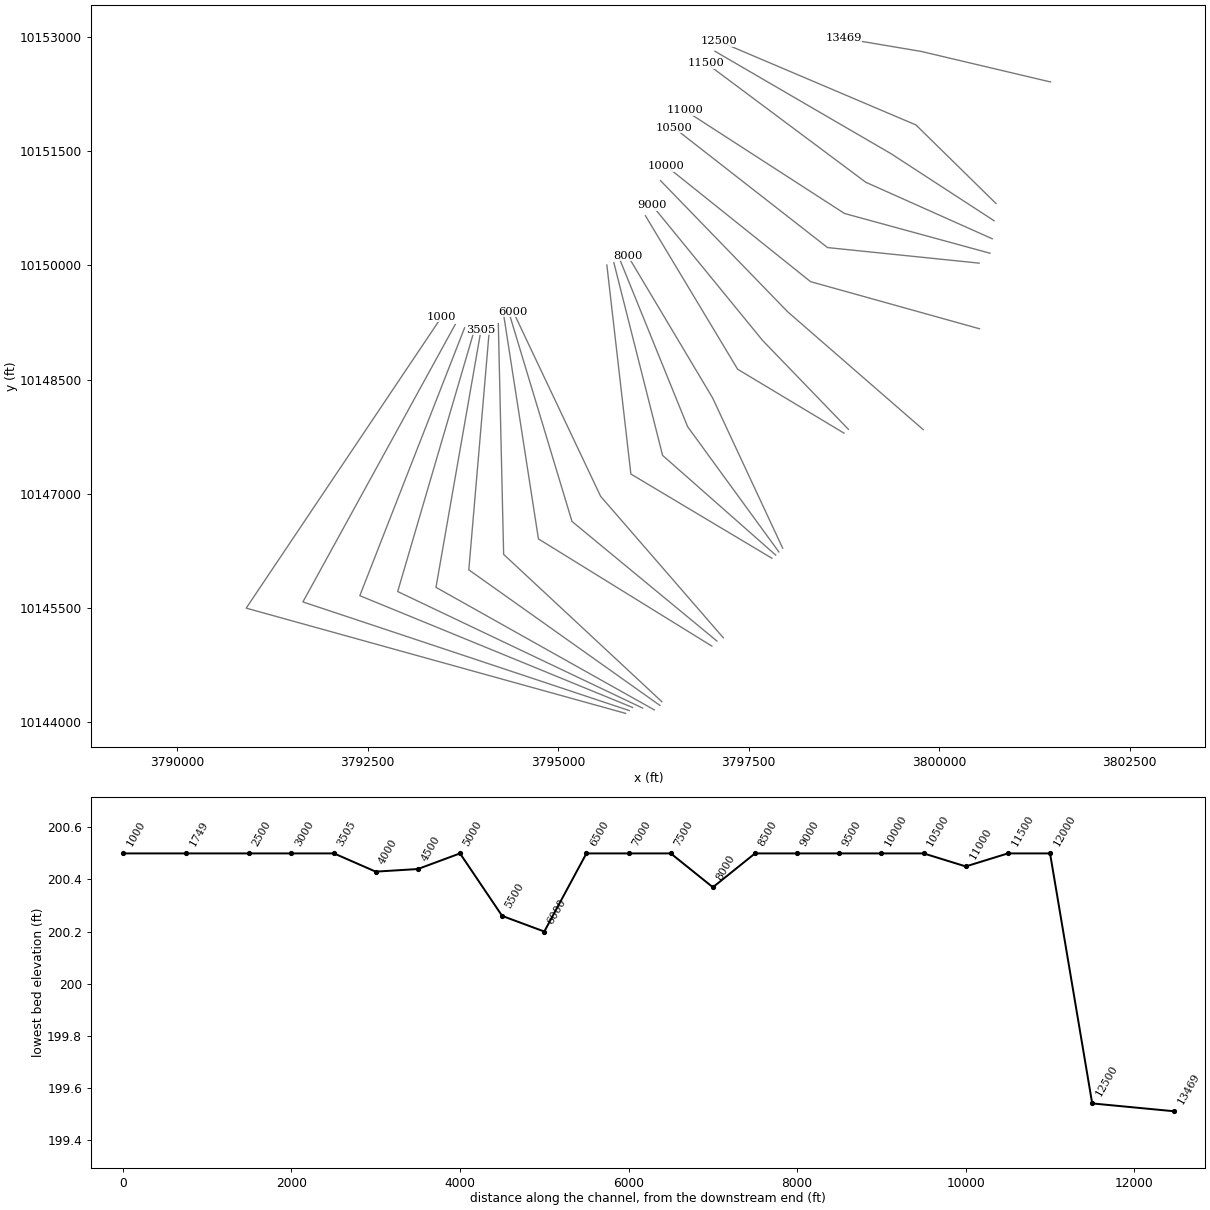
HEC-RAS study LEWIS CREEK.prj: LEWIS CREEK Base Level Engineering

--- LEWIS CREEK.g01 (geometry) --- (continued)

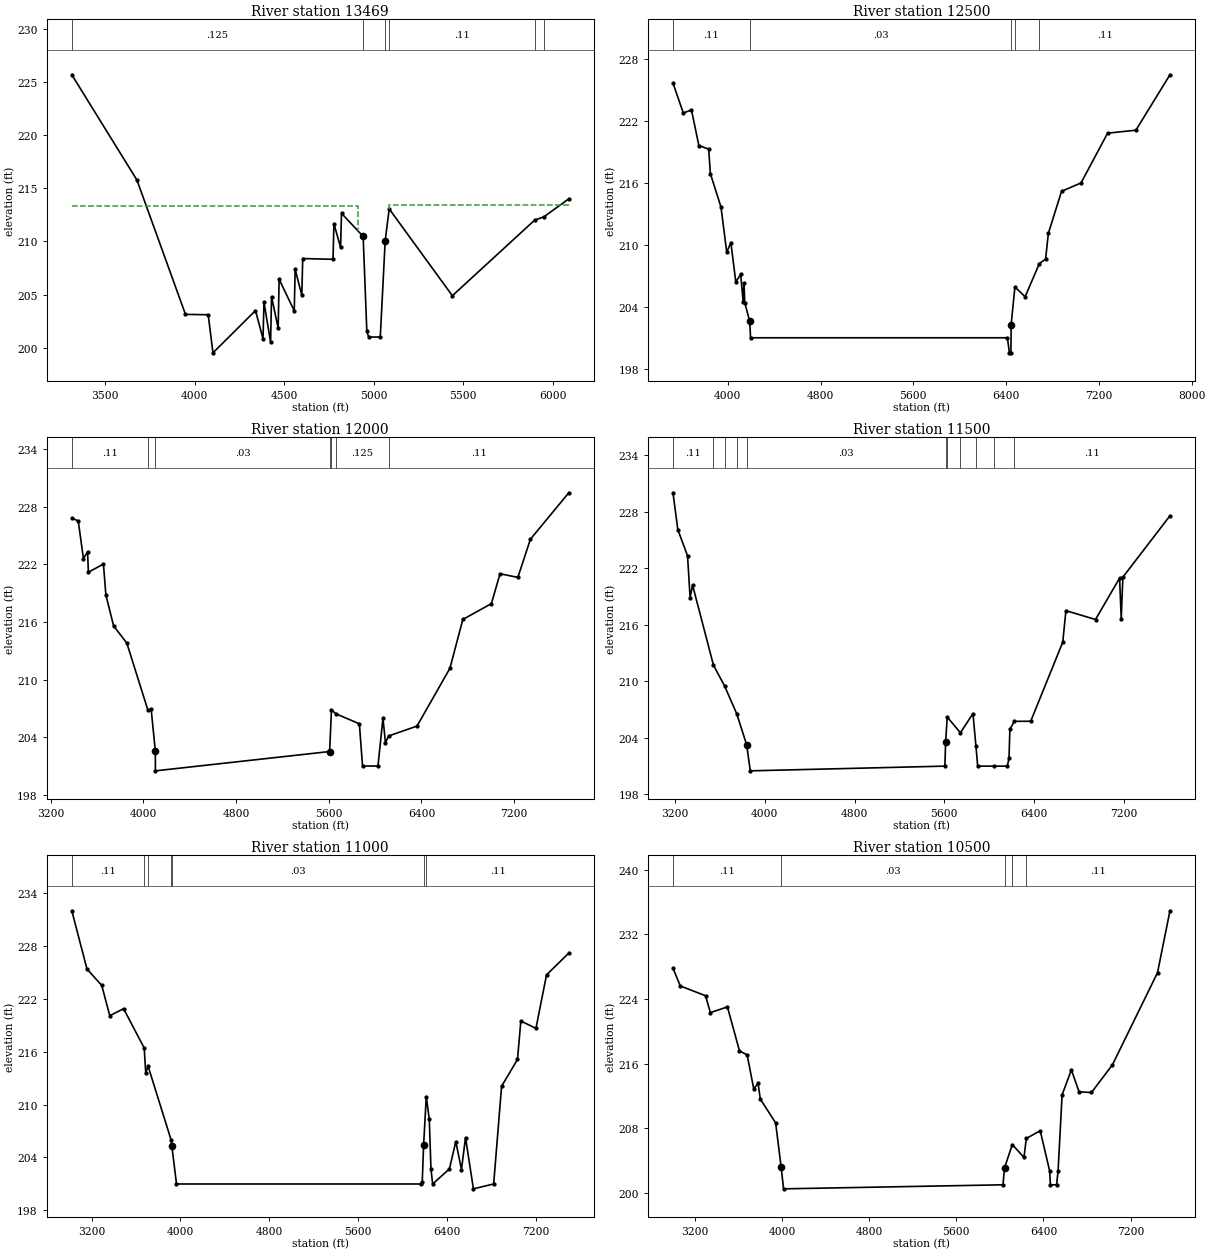
Type RM Length L Ch R = 1 ,13469   ,969,969,969
BEGIN DESCRIPTION:
LEWIS CREEK 27.0
END DESCRIPTION:
XS GIS Cut Line= 3
      3801461.74     10152410.23      3799765.59     10152811.04
      3798746.48     10152983.15
#Sta/Elev= 30
    3313   225.7  3676.6  215.79    3948  203.13  4074.9   203.1  4101.5  199.51
    4339  203.49  4381.2  200.83  4386.4  204.28  4423.5  200.52  4428.7   204.8
  4465.8  201.83    4471  206.44  4555.6  203.47  4560.7  207.37  4597.8  204.94
    4603  208.39  4772.2  208.32  4777.3  211.67  4814.4  209.44  4819.6  212.65
  4940.5  210.47  4961.1  201.54  4971.3     201  5036.2     201  5063.7  210.08
    5086  213.07  5438.9  204.89  5898.6  212.01  5949.3  212.31  6089.4  214.01
#Mann= 6 ,-1 , 0
    3313    .125       0  4940.5     .09       0  5063.7     .15       0
    5086     .11       0  5898.6    .125       0  5949.3     .11       0
#XS Ineff= 2 , 0
       0  4909.7  213.37  5087.6       0  213.44
Permanent Ineff=
       F       F
Bank Sta=4940.5,5063.7
XS Rating Curve= 0 ,0
Exp/Cntr=0.3,0.1

Type RM Length L Ch R = 1 ,12500   ,500,500,500
BEGIN DESCRIPTION:
LEWIS CREEK 25.0
END DESCRIPTION:
XS GIS Cut Line= 3
       3800746.4     10150814.04      3799696.06     10151845.61
      3797107.51      10152946.2
#Sta/Elev= 30
  3527.8  225.68  3616.6  222.79  3687.3  223.08  3750.9  219.63  3835.8  219.28
  3849.9  216.92  3941.9  213.66  3991.3  209.28  4026.8  210.23  4069.2  206.42
  4111.6  207.14  4132.8   204.5  4139.9  206.32  4146.9  204.38  4189.4   202.6
  4196.5     201  6411.5     201  6428.4  199.54  6441.8  199.54  6443.3  202.25
  6475.9  205.92  6564.2  204.98  6686.7  208.19  6740.6  208.63  6764.2  211.11
  6877.9  215.19  7046.1  216.01  7275.2  220.83    7519  221.12  7812.8  226.49
#Mann= 5 ,-1 , 0
  3527.8     .11       0  4189.4     .03       0  6443.3     .08       0
  6475.9    .125       0  6686.7     .11       0
#XS Ineff= 2 , 0
       0                  6475.9       0  205.92
Permanent Ineff=
       F       F
Bank Sta=4189.4,6443.3
XS Rating Curve= 0 ,0
Exp/Cntr=0.3,0.1

Type RM Length L Ch R = 1 ,12000   ,500,500,500
BEGIN DESCRIPTION:
LEWIS CREEK 24.0
END DESCRIPTION:
XS GIS Cut Line= 3
      3800721.75     10150587.54      3799366.73     10151469.39
      3797058.02     10152813.35
#Sta/Elev= 30
  3383.3  226.79  3438.6  226.53  3483.4  222.59  3519.2  223.31  3526.2  221.18
    3656  222.03  3677.1  218.81  3743.6   215.6  3858.2  213.79  4039.4  206.83
    4068  206.89  4103.8  202.57  4104.6   200.5  5607.9  202.51  5623.5  206.85
  5661.5  206.44  5864.4   205.4  5891.7     201  6024.9     201  6067.9  205.99
  6089.4  203.42  6116.8  204.13  6361.6  205.16  6645.4  211.17  6757.1  216.26
  7003.6  217.91  7078.1  221.02  7231.9  220.64  7340.4  224.62  7671.4  229.45
#Mann= 7 ,-1 , 0
  3383.3     .11       0  4039.4     .08       0  4103.8     .03       0
  5607.9     .08       0  5623.5     .15       0  5661.5    .125       0
  6116.8     .11       0
#XS Ineff= 2 , 0
       0                  5623.5       0  206.85
Permanent Ineff=
       F       F
Bank Sta=4103.8,5607.9
XS Rating Curve= 0 ,0
Exp/Cntr=0.3,0.1

Type RM Length L Ch R = 1 ,11500   ,500,500,500
BEGIN DESCRIPTION:
LEWIS CREEK 23.0
END DESCRIPTION:
XS GIS Cut Line= 3
       3800697.1     10150351.18      3799037.41     10151093.17
      3796944.75     10152655.78
#Sta/Elev= 30
    3182  229.99    3225  226.09  3311.8   223.3  3334.5  218.87  3356.4   220.2
  3542.9   211.7  3641.6  209.51  3750.8  206.53  3838.4  203.27    3871   200.5
  5605.6     201  5611.9  203.52  5626.5   206.2    5744  204.54  5855.8  206.57
    5882  203.16    5898     201  6038.9     201  6162.2     201  6176.8  201.82
  6185.1  204.92  6225.1  205.75  6370.7  205.76  6656.3  214.15  6684.3  217.49
  6948.1  216.55  7162.8  220.94  7177.4  216.62    7192  221.04  7611.7  227.55
#Mann= 11 ,-1 , 0
    3182     .11       0  3542.9    .125       0  3641.6     .11       0
  3750.8     .08       0  3838.4     .03       0  5611.9     .08       0
  5626.5     .15       0    5744    .125       0    5882     .11       0
  6038.9    .125       0  6225.1     .11       0
#XS Ineff= 2 , 0
       0                  5626.5       0   206.2
Permanent Ineff=
       F       F
Bank Sta=3838.4,5611.9
XS Rating Curve= 0 ,0
Exp/Cntr=0.3,0.1

Type RM Length L Ch R = 1 ,11000   ,500,500,500
BEGIN DESCRIPTION:
LEWIS CREEK 22.0
END DESCRIPTION:
XS GIS Cut Line= 3
      3800667.82     10150161.08      3798758.56     10150682.97
      3796659.18     10152040.21
#Sta/Elev= 30
  3020.7  231.94    3157  225.35  3290.2  223.49  3362.8  220.06  3487.2  220.85
    3673   216.4  3686.8  213.61  3708.6  214.32  3914.7  206.02  3922.6  205.26
  3964.1     201  6169.9     201  6179.1  201.22  6191.6  205.47  6215.4   210.9
  6242.5  208.32  6257.7   202.7  6272.8     201  6423.9   202.7  6481.3   205.8
  6532.7  202.64    6569  206.26  6640.2  200.45  6822.7     201  6894.2  212.07
  7037.4   215.1  7067.7  219.46  7203.8  218.62  7299.1  224.68  7499.9  227.15
#Mann= 7 ,-1 , 0
  3020.7     .11       0    3673    .125       0  3708.6     .11       0
  3914.7     .08       0  3922.6     .03       0  6191.6     .08       0
  6215.4     .11       0
#XS Ineff= 2 , 0
       0                  6215.4       0   210.9
Permanent Ineff=
       F       F
Bank Sta=3922.6,6191.6
XS Rating Curve= 0 ,0
Exp/Cntr=0.3,0.1

Type RM Length L Ch R = 1 ,10500   ,500,500,500
BEGIN DESCRIPTION:
LEWIS CREEK 21.0
END DESCRIPTION:
XS GIS Cut Line= 3
      3800524.76     10150031.09      3798535.82     10150235.33
      3796517.86     10151811.07
#Sta/Elev= 30
  3000.6  227.82  3067.9  225.62  3299.1  224.41  3343.7  222.32  3500.1  223.03
  3610.7  217.58  3681.1  217.09  3741.4  212.89  3781.6  213.55  3801.7  211.62
  3942.4  208.67  3992.7  203.21  4015.3   200.5  6028.2     201  6042.6  203.11
  6113.9  205.98  6220.8  204.39  6242.4  206.74    6370  207.69  6456.5  202.72
  6463.2     201  6519.9     201  6533.7  202.67  6570.7  212.14  6655.8  215.23
  6726.4  212.51  6840.4  212.43    7033  215.87  7446.1  227.26  7560.3  234.93
#Mann= 5 ,-1 , 0
  3000.6     .11       0  3992.7     .03       0  6042.6     .08       0
  6113.9    .125       0  6242.4     .11       0
#XS Ineff= 2 , 0
       0                  6113.9       0  205.98
Permanent Ineff=
       F       F
Bank Sta=3992.7,6042.6
XS Rating Curve= 0 ,0
Exp/Cntr=0.3,0.1

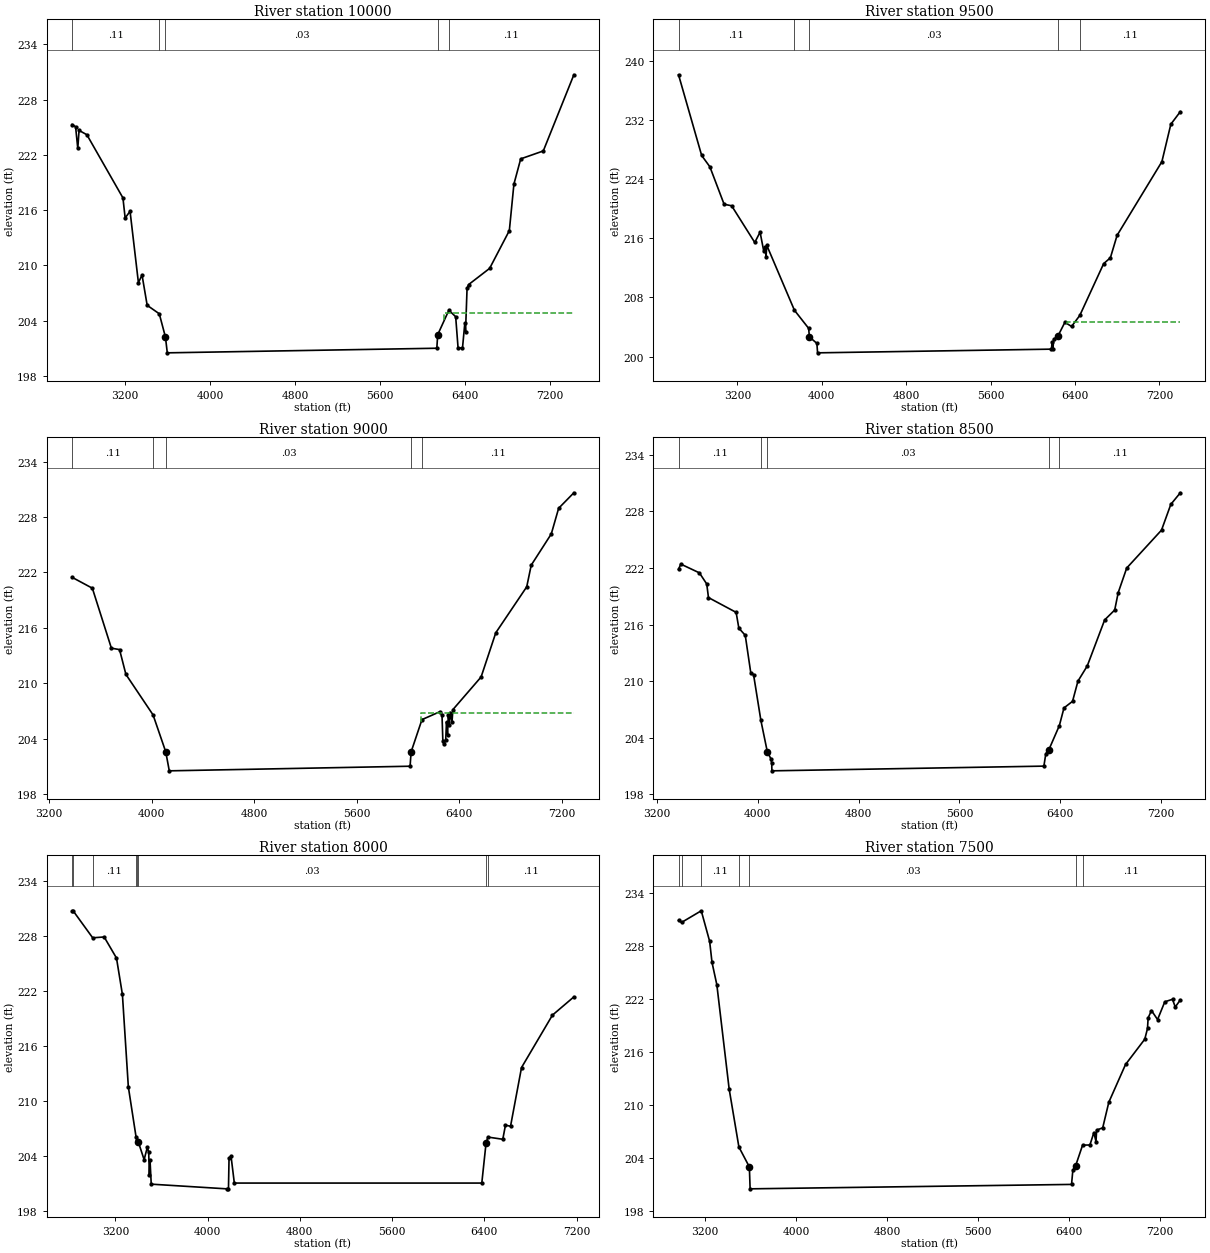
Type RM Length L Ch R = 1 ,10000   ,500,500,500
BEGIN DESCRIPTION:
LEWIS CREEK 20.0
END DESCRIPTION:
XS GIS Cut Line= 3
      3800529.74     10149169.31      3798313.08     10149787.68
       3796418.1     10151306.31
#Sta/Elev= 30
  2698.7  225.29  2731.8  225.05  2752.6  222.69  2764.6  224.65  2838.2  224.18
  3178.2  217.32    3199  215.14  3245.3  215.87    3324  208.12  3358.2  208.95
  3406.6  205.66  3520.8  204.74  3578.9  202.21  3596.2   200.5  6136.8     201
  6144.8  202.46  6250.4  205.13  6314.4  204.42  6336.8  201.07  6378.5     201
  6400.9  203.76  6407.3   202.8  6421.7  207.49  6436.1  207.91  6634.5  209.67
  6820.2  213.77  6863.4  218.82  6927.4  221.56  7140.3  222.42  7428.4  230.69
#Mann= 5 ,-1 , 0
  2698.7     .11       0  3520.8     .08       0  3578.9     .03       0
  6144.8     .08       0  6250.4     .11       0
#XS Ineff= 2 , 0
       0                  6208.8       0  204.87
Permanent Ineff=
       F       F
Bank Sta=3578.9,6144.8
XS Rating Curve= 0 ,0
Exp/Cntr=0.3,0.1

Type RM Length L Ch R = 1 ,9500    ,500,500,500
BEGIN DESCRIPTION:
LEWIS CREEK 19.0
END DESCRIPTION:
XS GIS Cut Line= 3
      3799791.04     10147844.68      3798012.46     10149391.93
      3796343.99     10151114.45
#Sta/Elev= 30
  2642.6  238.12  2861.8   227.2  2939.6  225.67  3074.5   220.6  3145.7   220.4
    3365  215.43  3415.4  216.83  3450.5  214.24  3464.7  214.79  3471.4  213.42
    3479  215.04    3741  206.26  3875.9  203.81  3882.5  202.66  3953.7  201.78
  3960.3   200.5  6176.6     201  6183.6  201.98  6190.8     201  6197.7  202.32
  6240.2  202.83    6304  204.63  6367.5  204.07  6445.4  205.56  6671.6  212.57
  6735.3  213.36  6798.9   216.4  7223.3  226.36  7308.2  231.43  7398.1  233.13
#Mann= 5 ,-1 , 0
  2642.6     .11       0    3741     .08       0  3882.5     .03       0
  6240.2     .08       0  6445.4     .11       0
#XS Ineff= 2 , 0
       0  3818.9  204.82  6325.1       0   204.7
Permanent Ineff=
       F       F
Bank Sta=3882.5,6240.2
XS Rating Curve= 0 ,0
Exp/Cntr=0.3,0.1

Type RM Length L Ch R = 1 ,9000    ,500,500,500
BEGIN DESCRIPTION:
LEWIS CREEK 18.0
END DESCRIPTION:
XS GIS Cut Line= 3
      3798809.45     10147848.67      3797684.19     10149014.78
      3796231.82     10150793.05
#Sta/Elev= 30
  3379.5  221.47  3537.8  220.29  3686.5  213.79  3750.1  213.64  3799.7  210.95
  4011.7  206.56  4110.7  202.56  4138.3   200.5  6017.8     201  6025.7  202.55
  6110.4  206.05  6252.5  206.92  6266.9  206.55  6273.4  203.77  6281.3   203.4
  6295.6  203.79  6302.1  205.82    6310  204.38  6316.4  206.53  6324.3  205.47
  6330.8  206.82  6345.2  205.82  6351.6  207.13    6572  210.67  6686.6  215.46
  6928.1  220.44  6963.3  222.79  7119.8  226.17  7177.2  228.95    7296  230.63
#Mann= 5 ,-1 , 0
  3379.5     .11       0  4011.7     .08       0  4110.7     .03       0
  6025.7     .08       0  6110.4     .11       0
#XS Ineff= 2 , 0
       0                  6103.9       0  206.74
Permanent Ineff=
       F       F
Bank Sta=4110.7,6025.7
XS Rating Curve= 0 ,0
Exp/Cntr=0.3,0.1

Type RM Length L Ch R = 1 ,8500    ,500,500,500
BEGIN DESCRIPTION:
LEWIS CREEK 17.0
END DESCRIPTION:
XS GIS Cut Line= 3
      3798751.35     10147798.88      3797355.92     10148637.63
      3796145.73     10150653.46
#Sta/Elev= 30
  3371.9  221.87  3389.7  222.42  3537.3  221.49  3595.6  220.31  3609.3  218.87
  3828.7   217.3  3850.1  215.63    3901  214.87  3945.3  210.84  3966.7  210.71
    4025  205.84    4076  202.52  4104.6  201.77    4111  201.28  4112.2   200.5
  6269.2     201  6284.7  202.33  6306.1  202.66    6392   205.3  6428.5  207.17
  6496.5  207.87  6539.3  210.01  6613.1  211.62  6751.1   216.5  6830.8  217.55
  6858.5  219.39    6926     222    7202  226.02  7275.8  228.75  7351.2  229.98
#Mann= 5 ,-1 , 0
  3371.9     .11       0    4025     .08       0    4076     .03       0
  6306.1     .08       0    6392     .11       0
Bank Sta=4076,6306.1
XS Rating Curve= 0 ,0
Exp/Cntr=0.3,0.1

Type RM Length L Ch R = 1 ,8000    ,500,500,500
BEGIN DESCRIPTION:
LEWIS CREEK 16.0
END DESCRIPTION:
XS GIS Cut Line= 3
      3797946.43     10146288.63      3797027.65     10148260.49
      3795913.37      10150130.7
#Sta/Elev= 30
  2824.6  230.67  2833.4  230.72  3003.3  227.77  3103.1  227.86  3209.9  225.56
  3261.2  221.59  3312.7   211.5  3379.8  206.02  3389.9  205.65  3398.4  205.52
  3449.6  203.55  3478.2  204.95  3489.2  204.34  3495.4  201.83  3500.9  203.47
  3511.3  200.88  4165.2  200.37  4181.2  200.37  4186.2  203.76  4203.6  203.92
    4232     201  6378.5     201  6415.5  205.38  6431.2  206.02  6560.5  205.78
  6583.8  207.32  6627.7   207.2  6723.1  213.61  6991.2  219.33    7177  221.32
#Mann= 8 ,-1 , 0
  2824.6    .125       0  2833.4     .15       0  3003.3     .11       0
  3379.8    .125       0  3389.9     .08       0  3398.4     .03       0
  6415.5    .125       0  6431.2     .11       0
Bank Sta=3398.4,6415.5
XS Rating Curve= 0 ,0
Exp/Cntr=0.3,0.1

Type RM Length L Ch R = 1 ,7500    ,500,500,500
BEGIN DESCRIPTION:
LEWIS CREEK 15.0
END DESCRIPTION:
XS GIS Cut Line= 3
      3797896.66      10146238.8      3796699.39     10147883.34
      3795806.14     10150087.63
#Sta/Elev= 30
  2965.8  230.85  2992.2  230.62  3165.6  231.94  3239.3  228.49  3260.2   226.1
  3302.6  223.58  3410.9  211.79  3496.6  205.23  3588.6  202.98  3595.3   200.5
  6421.8     201  6433.3  202.62  6457.4   203.1  6518.9  205.44  6583.3  205.46
  6618.2  206.86  6636.9  205.84  6642.3  207.14  6695.9   207.4  6749.5  210.29
  6896.6  214.56  7065.7  217.42  7089.8  218.63  7095.2  219.83  7124.7  220.66
  7178.3  219.64  7241.8  221.65  7309.6  221.93  7333.7  221.06  7378.4  221.86
#Mann= 7 ,-1 , 0
  2965.8    .125       0  2992.2     .15       0  3165.6     .11       0
  3496.6     .08       0  3588.6     .03       0  6457.4     .08       0
  6518.9     .11       0
Bank Sta=3588.6,6457.4
XS Rating Curve= 0 ,0
Exp/Cntr=0.3,0.1

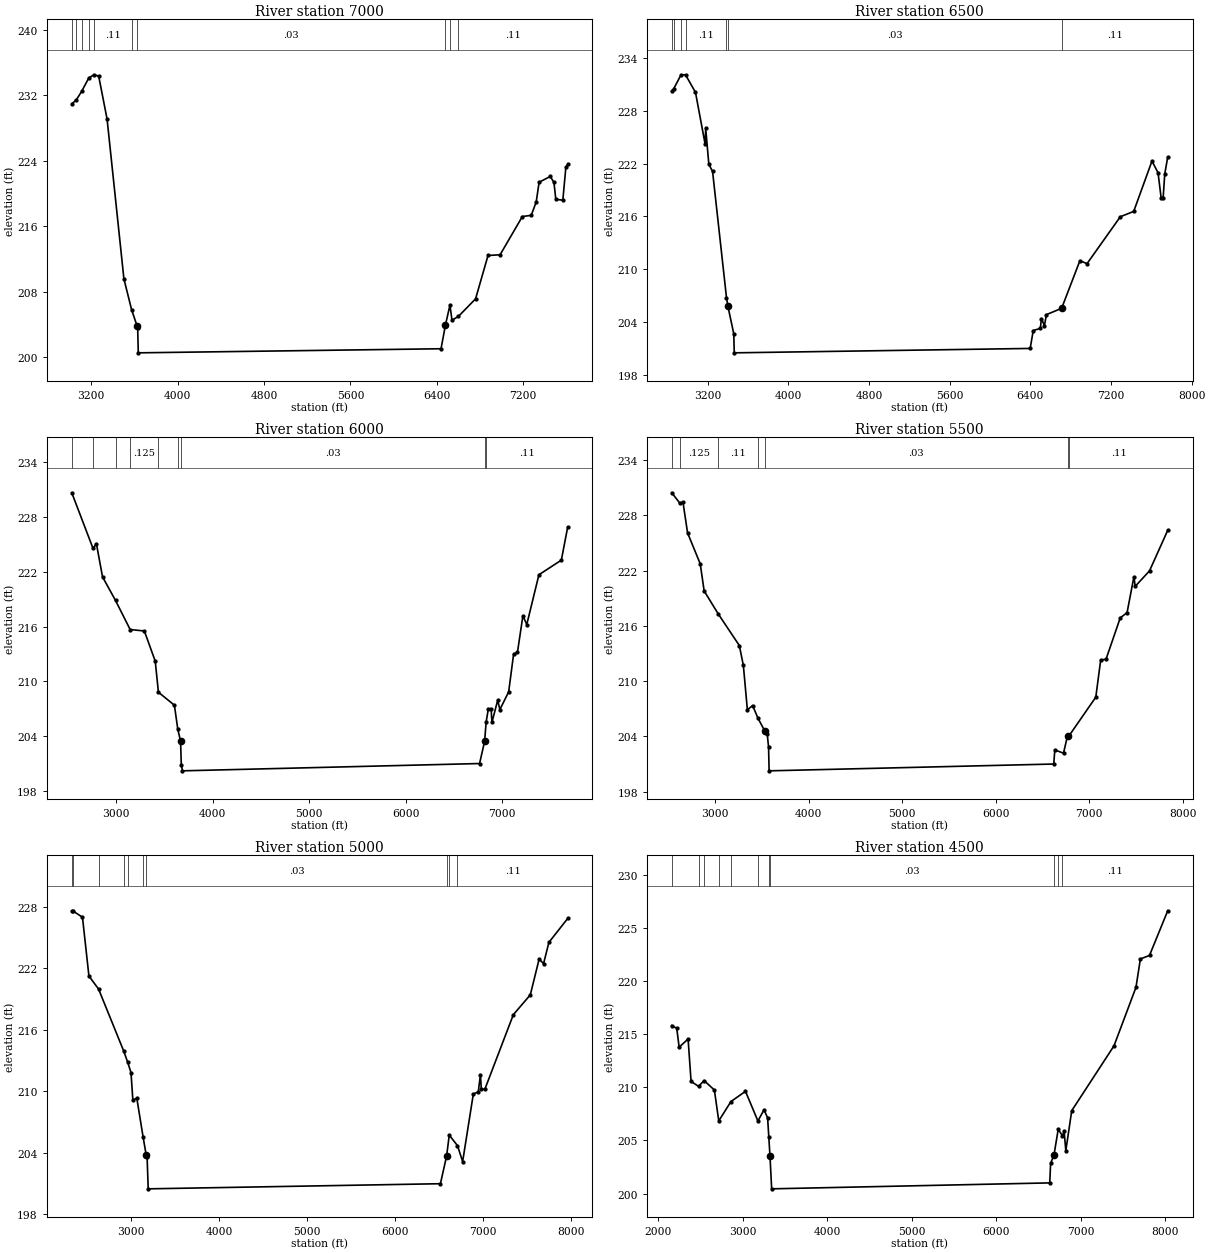
Type RM Length L Ch R = 1 ,7000    ,500,500,500
BEGIN DESCRIPTION:
LEWIS CREEK 14.0
END DESCRIPTION:
XS GIS Cut Line= 3
      3797855.19      10146197.3      3796371.12     10147506.19
      3795731.26     10150037.68
#Sta/Elev= 30
  3021.2  230.95  3064.2  231.47  3113.6  232.51  3178.5  234.13  3226.5  234.52
  3270.3  234.36  3348.1  229.09  3503.7  209.55  3574.9  205.78  3624.2  203.84
    3631  203.53  3636.8   200.5  6438.7     201    6480  203.93  6521.3  206.34
  6540.2  204.49  6599.9  204.96  6758.5  207.11  6873.6  212.41  6985.4   212.5
  7191.5  217.18  7273.6  217.32  7319.8  218.97  7346.4  221.37  7449.6  222.08
  7483.9  221.35  7501.1  219.28    7566  219.18    7594  223.19  7611.1  223.55
#Mann= 10 ,-1 , 0
  3021.2    .125       0  3064.2     .15       0  3113.6    .125       0
  3178.5     .15       0  3226.5     .11       0  3574.9     .08       0
  3624.2     .03       0    6480     .08       0  6521.3    .125       0
  6599.9     .11       0
Bank Sta=3624.2,6480
XS Rating Curve= 0 ,0
Exp/Cntr=0.3,0.1

Type RM Length L Ch R = 1 ,6500    ,500,500,500
BEGIN DESCRIPTION:
LEWIS CREEK 13.0
END DESCRIPTION:
XS GIS Cut Line= 3
      3797805.35     10146155.85      3795954.69     10147261.71
      3795639.55     10150006.18
#Sta/Elev= 30
  2844.1  230.24  2862.6  230.49  2935.4  232.08  2980.3  232.09  3079.2  230.09
  3174.6  224.22  3180.4  225.99  3211.5  221.92  3248.5  221.11  3386.6  206.77
  3400.4  205.81  3458.6  202.67  3463.7   200.5  6398.5     201  6428.7  203.03
  6499.1  203.28  6510.3   204.4  6539.4  203.58  6559.5  204.84  6710.5  205.56
  6891.7  210.97  6962.2  210.63  7292.3  215.96  7425.2  216.57  7606.4  222.29
  7666.8  220.95    7697  218.12  7717.1  218.12  7732.9   220.8  7762.5  222.75
#Mann= 7 ,-1 , 0
  2844.1    .125       0  2862.6     .11       0  2935.4    .125       0
  2980.3     .11       0  3386.6     .08       0  3400.4     .03       0
  6710.5     .11       0
#XS Ineff= 2 , 0
       0                  6510.3       0   204.4
Permanent Ineff=
       F       F
Bank Sta=3400.4,6710.5
XS Rating Curve= 0 ,0
Exp/Cntr=0.3,0.1

Type RM Length L Ch R = 1 ,6000    ,500,500,500
BEGIN DESCRIPTION:
LEWIS CREEK 12.0
END DESCRIPTION:
XS GIS Cut Line= 3
      3797167.87     10145111.05      3795557.53     10146969.14
      3794412.13     10149390.61
#Sta/Elev= 30
  2541.2  230.66  2761.5  224.56  2796.2  225.09  2859.8  221.45  2994.5  218.86
  3145.9  215.68    3293  215.52  3405.9  212.21  3438.7  208.81  3604.4  207.39
  3639.6  204.74  3668.1  203.46  3675.7  200.88    3688   200.2  6765.8     201
 6817.95  203.44    6834  205.56  6856.8  206.99  6885.1  207.01  6893.8  205.51
  6953.3  207.93  6976.1  206.91  7067.1  208.85  7118.2  212.98  7158.1  213.18
  7214.7  217.19  7254.7  216.23  7380.5  221.68  7612.8  223.28  7678.7  226.91
#Mann= 9 ,-1 , 0
  2541.2     .11       0  2761.5    .125       0  2994.5     .11       0
  3145.9    .125       0  3438.7     .11       0  3639.6     .08       0
  3668.1     .03       0 6817.95     .08       0    6834     .11       0
Bank Sta=3668.1,6817.95
XS Rating Curve= 0 ,0
Exp/Cntr=0.3,0.1

Type RM Length L Ch R = 1 ,5500    ,500,500,500
BEGIN DESCRIPTION:
LEWIS CREEK 11.0
END DESCRIPTION:
XS GIS Cut Line= 3
      3797083.43     10145068.77      3795182.13     10146638.87
      3794362.07     10149357.48
#Sta/Elev= 30
  2534.2  230.46  2622.7   229.3  2653.6  229.46  2703.1   226.1  2838.6  222.74
  2880.3   219.8  3033.8  217.26  3256.8  213.87  3299.8  211.71  3342.8  206.89
  3398.8  207.35  3456.1  205.98  3527.1  204.62  3555.1  204.26  3569.5  202.84
  3575.3  200.26  6620.5     201  6631.7  202.53  6724.7  202.18  6768.1  204.09
  6788.4  204.13  7070.1  208.26  7122.6   212.3  7179.5  212.38  7331.5  216.87
  7404.7  217.44  7477.8  221.33    7492   220.3  7644.9  221.98  7839.6  226.38
#Mann= 7 ,-1 , 0
  2534.2     .11       0  2622.7    .125       0  3033.8     .11       0
  3456.1     .08       0  3527.1     .03       0  6768.1     .08       0
  6788.4     .11       0
Bank Sta=3527.1,6768.1
XS Rating Curve= 0 ,0
Exp/Cntr=0.3,0.1

Type RM Length L Ch R = 1 ,5000    ,500,500,500
BEGIN DESCRIPTION:
LEWIS CREEK 10.0
END DESCRIPTION:
XS GIS Cut Line= 3
      3797017.09     10145002.36      3794741.75     10146409.71
      3794286.94     10149342.35
#Sta/Elev= 30
  2324.6  227.59  2334.5  227.61  2446.4  226.98  2519.7  221.25  2629.4  219.98
  2916.2  213.92  2959.6  212.87  2998.4  211.84  3019.7  209.14  3064.5  209.35
  3135.5  205.59  3172.1  203.76  3181.6  203.62  3194.3   200.5  6519.3     201
  6590.1  203.71  6619.8  205.74  6713.7  204.71  6772.3  203.16  6893.7  209.74
  6949.9  209.96  6974.7   211.6  6984.8  210.21  7025.3  210.22  7349.1  217.48
    7542  219.41  7642.6   222.9  7693.2  222.46  7753.9  224.53  7967.7  226.86
#Mann= 10 ,-1 , 0
  2324.6     .11       0  2334.5    .125       0  2629.4     .11       0
  2916.2    .125       0  2959.6     .11       0  3135.5     .08       0
  3172.1     .03       0  6590.1     .08       0  6619.8    .125       0
  6713.7     .11       0
#XS Ineff= 2 , 0
       0                  6619.8       0  205.74
Permanent Ineff=
       F       F
Bank Sta=3172.1,6590.1
XS Rating Curve= 0 ,0
Exp/Cntr=0.3,0.1

Type RM Length L Ch R = 1 ,4500    ,500,500,500
BEGIN DESCRIPTION:
LEWIS CREEK 9.0
END DESCRIPTION:
XS GIS Cut Line= 3
      3796361.51     10144272.13      3794284.85     10146206.63
      3794215.37     10149236.64
#Sta/Elev= 30
  2161.9   215.8  2220.6  215.53  2248.9  213.76  2354.9  214.53  2390.1  210.54
  2478.3  210.08  2544.7  210.62  2666.1  209.73  2717.7  206.83  2862.1  208.65
    3034  209.61  3181.1  206.82  3253.4  207.88  3295.9  207.11    3310  205.31
  3324.2   203.5  3343.8  200.44  6634.9     201  6644.9  202.83  6684.9  203.62
  6734.9  206.04  6785.1  205.43  6804.9  205.85  6824.9  204.03  6894.9  207.79
  7395.1  213.89  7655.1  219.39  7707.3  222.06  7815.2  222.39  8030.8  226.59
#Mann= 11 ,-1 , 0
  2161.9    .125       0  2478.3     .11       0  2544.7    .125       0
  2717.7     .11       0  2862.1    .125       0  3181.1     .11       0
    3310     .08       0  3324.2     .03       0  6684.9     .08       0
  6734.9    .125       0  6785.1     .11       0
Bank Sta=3324.2,6684.9
XS Rating Curve= 0 ,0
Exp/Cntr=0.3,0.1

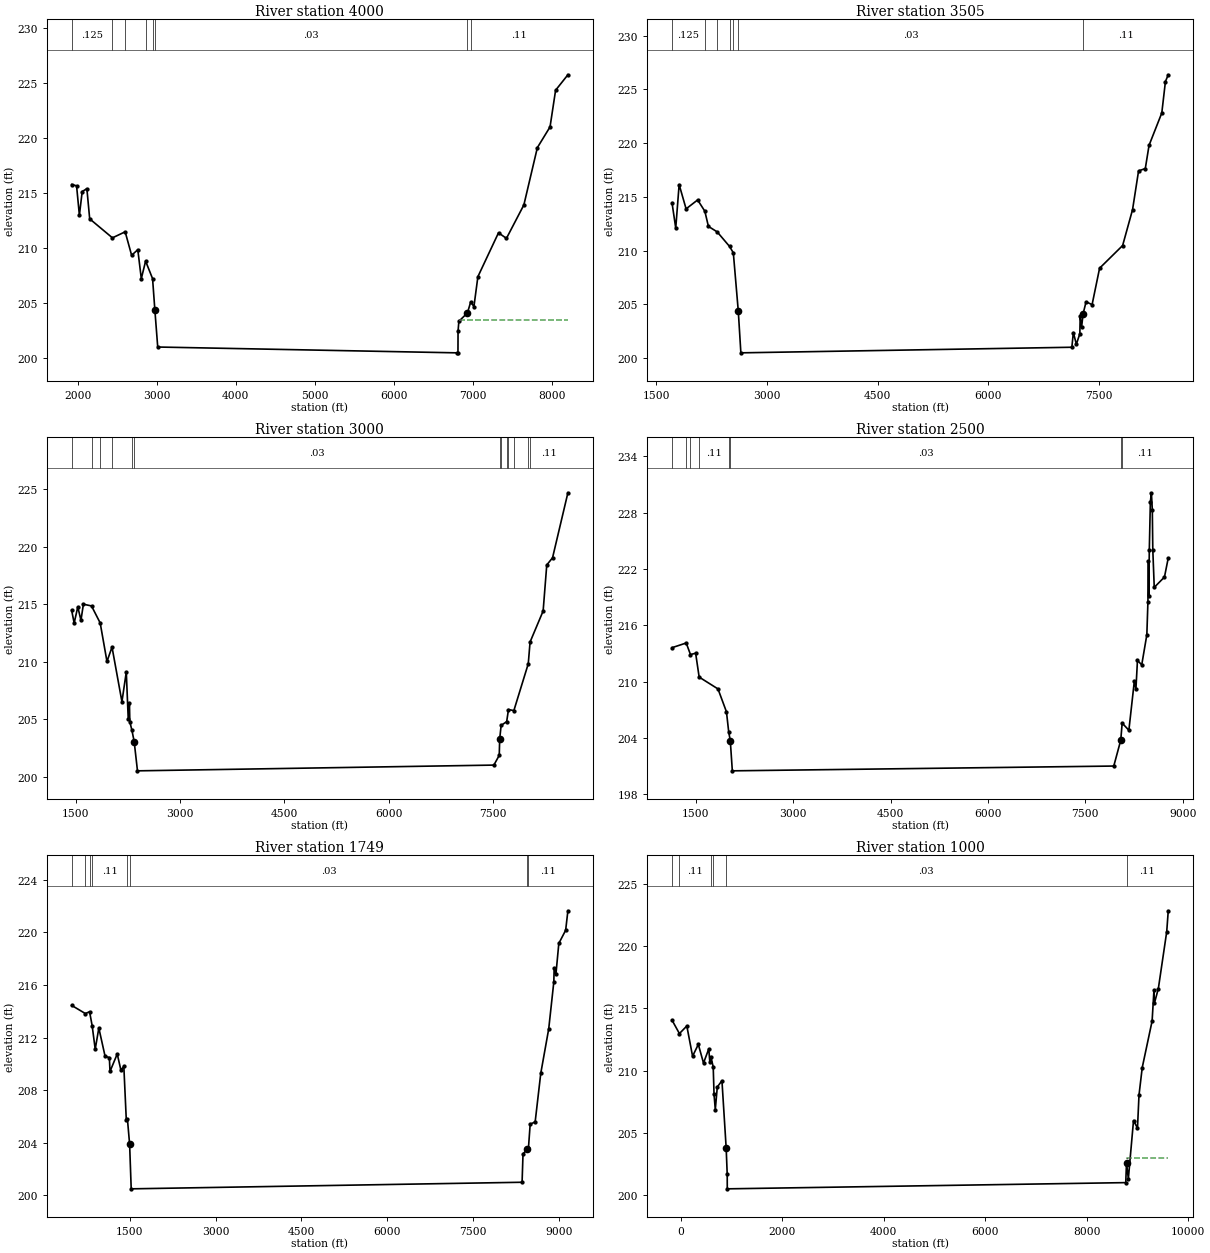
Type RM Length L Ch R = 1 ,4000    ,495,495,495
BEGIN DESCRIPTION:
LEWIS CREEK 8.0
END DESCRIPTION:
XS GIS Cut Line= 3
      3796336.61     10144222.35      3793827.95     10146003.55
      3794100.87     10149196.21
#Sta/Elev= 30
  1923.3  215.77  1985.4  215.65  2021.1  212.97  2056.7  215.13  2115.8  215.39
  2151.5  212.64  2439.3  210.91  2600.5  211.46  2682.2  209.32  2760.4  209.83
  2804.7  207.19  2859.2  208.79  2947.4  207.19  2976.5  204.32  3012.6  200.96
  6795.4  200.43  6812.8  200.43  6813.9  202.38  6824.1   203.3  6932.8  204.07
  6974.7  205.08  7014.8  204.64    7065  207.37    7326  211.37  7426.3  210.86
  7647.1  213.91  7817.8  219.13  7978.3  221.02  8048.6  224.36  8204.3  225.77
#Mann= 8 ,-1 , 0
  1923.3    .125       0  2439.3     .11       0  2600.5    .125       0
  2859.2     .11       0  2947.4     .08       0  2976.5     .03       0
  6932.8     .08       0  6974.7     .11       0
#XS Ineff= 2 , 0
       0                  6834.2       0  203.46
Permanent Ineff=
       F       F
Bank Sta=2976.5,6932.8
XS Rating Curve= 0 ,0
Exp/Cntr=0.3,0.1

Type RM Length L Ch R = 1 ,3505    ,505,505,505
BEGIN DESCRIPTION:
LEWIS CREEK 1.0
END DESCRIPTION:
XS GIS Cut Line= 3
       3796261.9     10144164.28      3793397.16     10145773.35
      3793988.84     10149157.11
#Sta/Elev= 30
  1714.3  214.46  1764.8   212.1  1810.7  216.15    1905  213.89  2061.2  214.72
    2159  213.67  2207.2  212.26  2325.9  211.75  2494.3  210.39  2544.7   209.8
  2612.1  204.36  2646.8   200.5  7129.6  201.02  7149.9  202.39  7190.5   201.3
  7237.7  202.27  7242.7  203.92  7261.5  202.89  7281.8  204.13  7322.4  205.25
  7403.6  204.98  7505.2  208.37  7817.3  210.48  7951.8  213.82  8033.1  217.42
  8124.4  217.64  8175.2   219.8  8347.8  222.81  8396.9  225.73  8435.1  226.36
#Mann= 7 ,-1 , 0
  1714.3    .125       0    2159     .11       0  2325.9    .125       0
  2494.3     .11       0  2544.7     .08       0  2612.1     .03       0
  7281.8     .11       0
Bank Sta=2612.1,7281.8
XS Rating Curve= 0 ,0
Exp/Cntr=0.3,0.1

Type RM Length L Ch R = 1 ,3000    ,500,500,500
BEGIN DESCRIPTION:
LEWIS CREEK 6.0
END DESCRIPTION:
XS GIS Cut Line= 3
      3796110.31     10144187.09      3792894.67     10145718.31
      3793900.88     10149152.96
#Sta/Elev= 30
  1438.4  214.45  1474.4  213.35  1526.6  214.76    1572  213.59  1607.3  214.99
  1723.9  214.84  1848.8  213.36  1946.4  210.01  2019.1  211.26  2161.8  206.51
  2224.4   209.1  2252.7  204.98  2269.8  206.36  2275.4  204.76    2305  204.04
  2337.9  203.05  2385.4   200.5  7513.9     201  7591.2  201.85  7597.5  203.28
  7618.4  204.45  7697.9  204.78  7724.2  205.83  7801.5  205.74  8008.7  209.81
  8034.6   211.7  8222.7   214.4  8274.8   218.4  8358.2  219.03    8579  224.68
#Mann= 13 ,-1 , 0
  1438.4    .125       0  1723.9     .11       0  1848.8    .125       0
  2019.1     .11       0    2305     .08       0  2337.9     .03       0
  7597.5     .08       0  7618.4    .125       0  7697.9     .11       0
  7724.2    .125       0  7801.5     .11       0  8008.7    .125       0
  8034.6     .11       0
Bank Sta=2337.9,7597.5
XS Rating Curve= 0 ,0
Exp/Cntr=0.3,0.1

Type RM Length L Ch R = 1 ,2500    ,751,751,751
BEGIN DESCRIPTION:
LEWIS CREEK 5.0
END DESCRIPTION:
XS GIS Cut Line= 3
      3795976.05     10144196.46      3792397.64     10145663.88
      3793773.05     10149182.73
#Sta/Elev= 30
  1132.4  213.61  1351.2  214.11  1416.7  212.88  1496.5  213.02  1550.5  210.48
  1840.7  209.22  1971.4  206.78  2006.2  204.62  2030.2  203.72  2061.7   200.5
  7938.9  201.01  8046.2  203.76  8068.2  205.58  8171.5  204.82  8255.6  210.05
  8280.1  209.21  8303.9  212.26  8369.6  211.78  8448.4  214.99    8465   218.5
  8472.9  222.83  8478.2  219.14  8486.4  224.04  8502.7  229.14  8518.6   230.1
  8532.5  228.32  8540.1  224.05  8562.4  220.03  8719.9  221.13  8778.1  223.16
#Mann= 8 ,-1 , 0
  1132.4    .125       0  1351.2     .11       0  1416.7    .125       0
  1550.5     .11       0  2006.2     .08       0  2030.2     .03       0
  8046.2     .08       0  8068.2     .11       0
Bank Sta=2030.2,8046.2
XS Rating Curve= 0 ,0
Exp/Cntr=0.3,0.1

Type RM Length L Ch R = 1 ,1749    ,749,749,749
BEGIN DESCRIPTION:
LEWIS CREEK 4.0
END DESCRIPTION:
XS GIS Cut Line= 3
      3795932.34     10144155.87      3791650.95      10145582.1
      3793649.28     10149224.65
#Sta/Elev= 30
   487.3  214.44   726.7  213.82   800.1  213.96   845.5  212.89   898.6  211.11
   961.8  212.72  1071.7  210.56  1145.5  210.48  1156.9  209.42  1283.4  210.75
  1346.7  209.53  1398.5   209.8  1441.5  205.73  1461.7  205.78  1499.5  203.89
  1527.3   200.5  8354.6     201  8370.7  203.15  8443.4  203.51  8466.3  203.63
  8495.8  205.41    8583  205.59  8680.6  209.27  8819.8  212.66    8909  216.23
  8914.7   217.3  8945.3   216.8  8996.2  219.15  9115.6  220.15  9154.7  221.63
#Mann= 8 ,-1 , 0
   487.3    .125       0   726.7     .11       0   800.1    .125       0
   845.5     .11       0  1461.7     .08       0  1499.5     .03       0
  8443.4     .08       0  8466.3     .11       0
Bank Sta=1499.5,8443.4
XS Rating Curve= 0 ,0
Exp/Cntr=0.3,0.1

Type RM Length L Ch R = 1 ,1000    ,0,0,0
BEGIN DESCRIPTION:
LEWIS CREEK 2.0
END DESCRIPTION:
XS GIS Cut Line= 3
      3795885.47     10144118.41      3790906.56     10145500.57
       3793472.3     10149326.38
#Sta/Elev= 30
  -167.2  214.06   -21.5  212.98   124.6  213.59   237.8  211.16   350.9  212.11
     453  210.61   556.8  211.75   577.6  210.69   598.3  211.13   644.4  210.29
   660.6  208.09   685.2  206.87   724.7  208.69   816.3  209.19   899.3  203.79
     920  201.66   921.3   200.5  8769.5     201  8784.5   202.6  8820.5   201.3
  8922.5  205.99  9000.6  205.38  9030.6  208.04  9094.4  210.25  9288.7  213.99
  9324.7  216.45  9333.7  215.42  9411.7   216.6  9576.8  221.18  9606.5  222.85
#Mann= 6 ,-1 , 0
  -167.2    .125       0   -21.5     .11       0   598.3    .125       0
   644.4     .11       0   899.3     .03       0  8784.5     .11       0
#XS Ineff= 2 , 0
       0                  8793.4       0  202.94
Permanent Ineff=
       F       F
Bank Sta=899.3,8784.5
XS Rating Curve= 0 ,0
Exp/Cntr=0.3,0.1

Chan Stop Cuts=-1
Use User Specified Reach Order=0
Composite Channel Slope=5