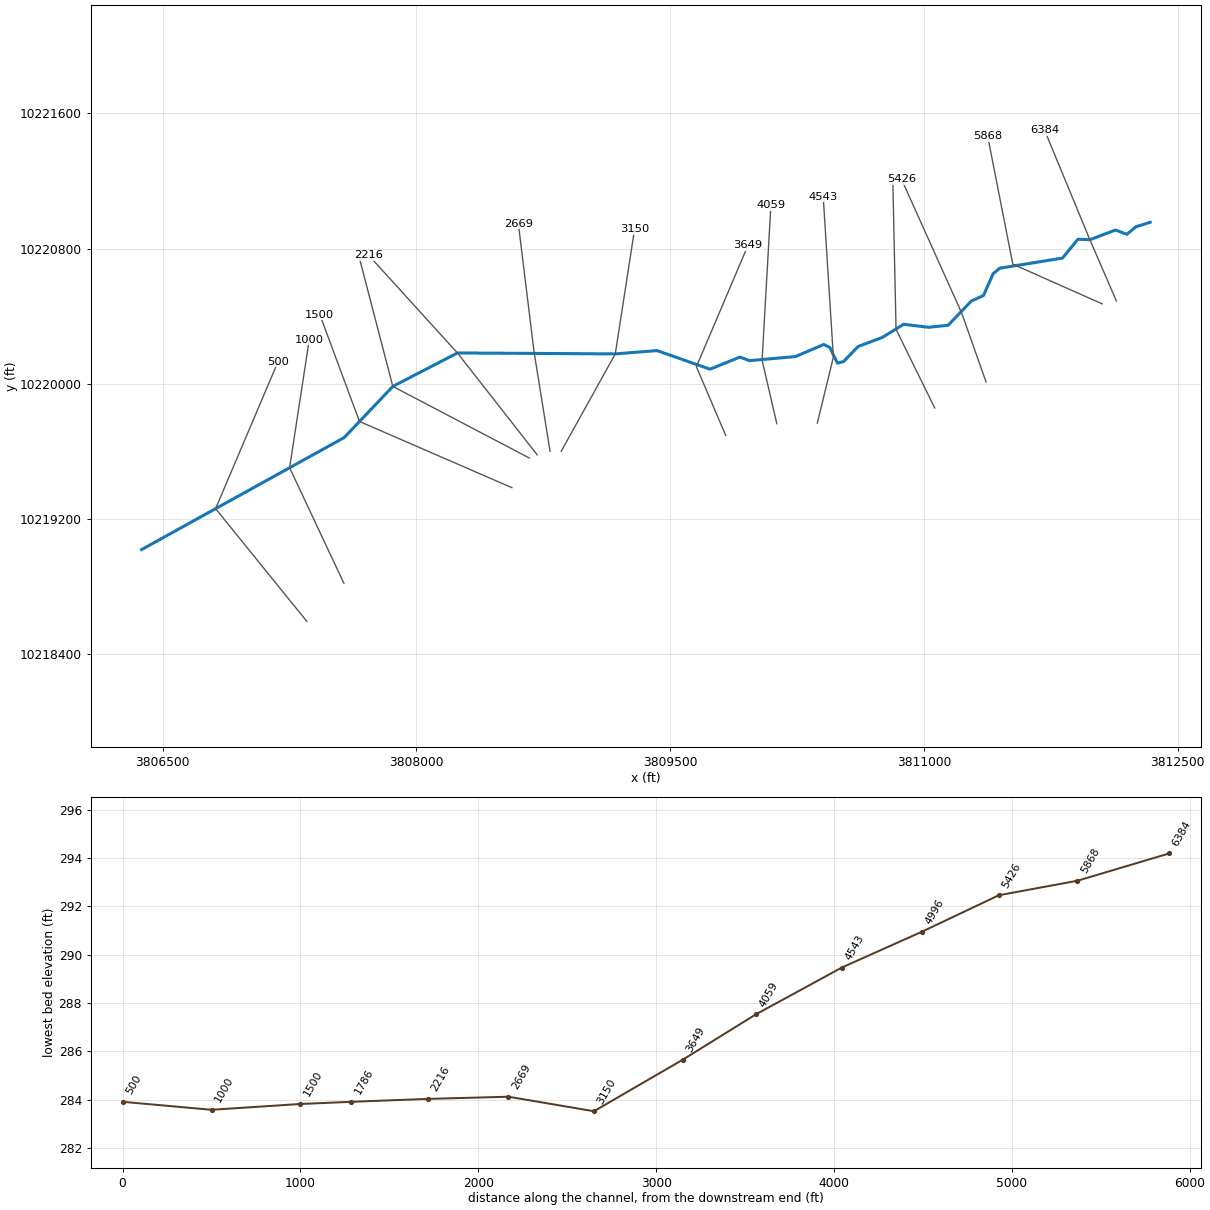
--- LITTLE CHINQUAPIN CREEK.prj (project) ---

Proj Title=LITTLE CHINQUAPIN CREEK Base Level Engineering
Current Plan=p01
Default Exp/Contr=0.3,0.1
English Units
Geom File=g01
Flow File=f01
Flow File=f02
Plan File=p01
Y Axis Title=Elevation
X Axis Title(PF)=Main Channel Distance
X Axis Title(XS)=Station
BEGIN DESCRIPTION:
LITTLE CHINQUAPIN CREEK
END DESCRIPTION:
DSS Export Rating Curves= 0
DSS Export Rating Curve Sorted= 0
DSS Export Volume Flow Curves= 0
DXF OffsetX= 0
DXF OffsetY= 0
DXF ScaleX= 1
DXF ScaleY= 10

--- LITTLE CHINQUAPIN CREEK.p01 (plan) ---

Plan Title=Multiple Run
Short Identifier=Multiple
Geom File=g01
Flow File=f01
Subcritical Flow
K Sum by GR= 0
Std Step Tol= 0.01
Critical Tol= 0.01
Num of Std Step Trials= 20
Max Error Tol= 0.3
Flow Tol Ratio= 0.001
Split Flow NTrial= 30
Split Flow Tol= 0.02
Split Flow Ratio= 0.02
Log Output Level= 0
Friction Slope Method= 1
Unsteady Friction Slope Method= 2
Unsteady Bridges Friction Slope Method= 1
Parabolic Critical Depth
Global Vel Dist=  1 , 1 , 1
Global Log Level= 0
CheckData=True
Encroach Param= -1, 0, 0, 0
BEGIN DESCRIPTION:
Multiple Run
END DESCRIPTION:

--- LITTLE CHINQUAPIN CREEK.f01 (steady flow) ---

Flow Title=Multiple
Program Version=4.10
Number of Profiles= 7
Profile Names=10-year,25-year,50-year,1pct_min,100-year,1pct_plu,500-year
River Rch & RM=LITTLE CHINQUAPI,Reach-1         ,6384
    1368    1932    2688    1227    3706   11192    7295
River Rch & RM=LITTLE CHINQUAPI,Reach-1         ,4543
    1584    2243    3122    1426    4307   13007    8480
Boundary for River Rch & Prof#=LITTLE CHINQUAPI,Reach-1         , 1
Up Type= 0
Dn Type= 3
Dn Slope=0.005
Boundary for River Rch & Prof#=LITTLE CHINQUAPI,Reach-1         , 2
Up Type= 0
Dn Type= 3
Dn Slope=0.005
Boundary for River Rch & Prof#=LITTLE CHINQUAPI,Reach-1         , 3
Up Type= 0
Dn Type= 3
Dn Slope=0.005
Boundary for River Rch & Prof#=LITTLE CHINQUAPI,Reach-1         , 4
Up Type= 0
Dn Type= 3
Dn Slope=0.005
Boundary for River Rch & Prof#=LITTLE CHINQUAPI,Reach-1         , 5
Up Type= 0
Dn Type= 3
Dn Slope=0.005
Boundary for River Rch & Prof#=LITTLE CHINQUAPI,Reach-1         , 6
Up Type= 0
Dn Type= 3
Dn Slope=0.005
Boundary for River Rch & Prof#=LITTLE CHINQUAPI,Reach-1         , 7
Up Type= 0
Dn Type= 3
Dn Slope=0.005
DSS Import GetInterval= 0
DSS Import GetPeak= 0
DSS Import FillOption= 0

--- LITTLE CHINQUAPIN CREEK.f02 (steady flow) ---

Flow Title=Orig_BLE_Flow
Program Version=4.10
Number of Profiles= 7
Profile Names=10-year,25-year,50-year,1pct_min,100-year,1pct_plu,500-year
River Rch & RM=LITTLE CHINQUAPI,Reach-1         ,6384
    1368    1894    2337     944    2851    8611    4241
River Rch & RM=LITTLE CHINQUAPI,Reach-1         ,4543
    1584    2199    2715    1097    3313   10006    4930
Boundary for River Rch & Prof#=LITTLE CHINQUAPI,Reach-1         , 1
Up Type= 0
Dn Type= 3
Dn Slope=0.005
Boundary for River Rch & Prof#=LITTLE CHINQUAPI,Reach-1         , 2
Up Type= 0
Dn Type= 3
Dn Slope=0.005
Boundary for River Rch & Prof#=LITTLE CHINQUAPI,Reach-1         , 3
Up Type= 0
Dn Type= 3
Dn Slope=0.005
Boundary for River Rch & Prof#=LITTLE CHINQUAPI,Reach-1         , 4
Up Type= 0
Dn Type= 3
Dn Slope=0.005
Boundary for River Rch & Prof#=LITTLE CHINQUAPI,Reach-1         , 5
Up Type= 0
Dn Type= 3
Dn Slope=0.005
Boundary for River Rch & Prof#=LITTLE CHINQUAPI,Reach-1         , 6
Up Type= 0
Dn Type= 3
Dn Slope=0.005
Boundary for River Rch & Prof#=LITTLE CHINQUAPI,Reach-1         , 7
Up Type= 0
Dn Type= 3
Dn Slope=0.005
DSS Import GetInterval= 0
DSS Import GetPeak= 0
DSS Import FillOption= 0

--- LITTLE CHINQUAPIN CREEK.g01 (geometry) ---

Geom Title=Existing Conditions
Program Version=4.10

River Reach=LITTLE CHINQUAPI,Reach-1
Reach XY= 30
      3812338.27     10220956.08      3812252.86     10220928.86
       3812200.3     10220884.75      3812132.73     10220910.09
      3811981.62     10220852.84      3811911.22     10220855.65
      3811819.24     10220743.96      3811448.28     10220684.17
      3811409.44      10220651.3      3811352.67     10220522.83
      3811280.96     10220489.96      3811143.52     10220346.55
        3811027.     10220334.59       3810880.6     10220352.52
      3810755.11     10220274.84       3810611.7     10220221.06
      3810525.05     10220131.42       3810489.2     10220122.46
      3810444.38     10220215.08      3810408.53     10220233.01
      3810241.21      10220161.3      3809969.32      10220137.4
      3809912.56     10220158.31      3809736.28     10220086.61
       3809422.5     10220196.84      3809176.15     10220177.14
      3808243.09     10220182.75      3807861.13     10219984.72
       3807573.7     10219682.05      3806376.09     10219019.32

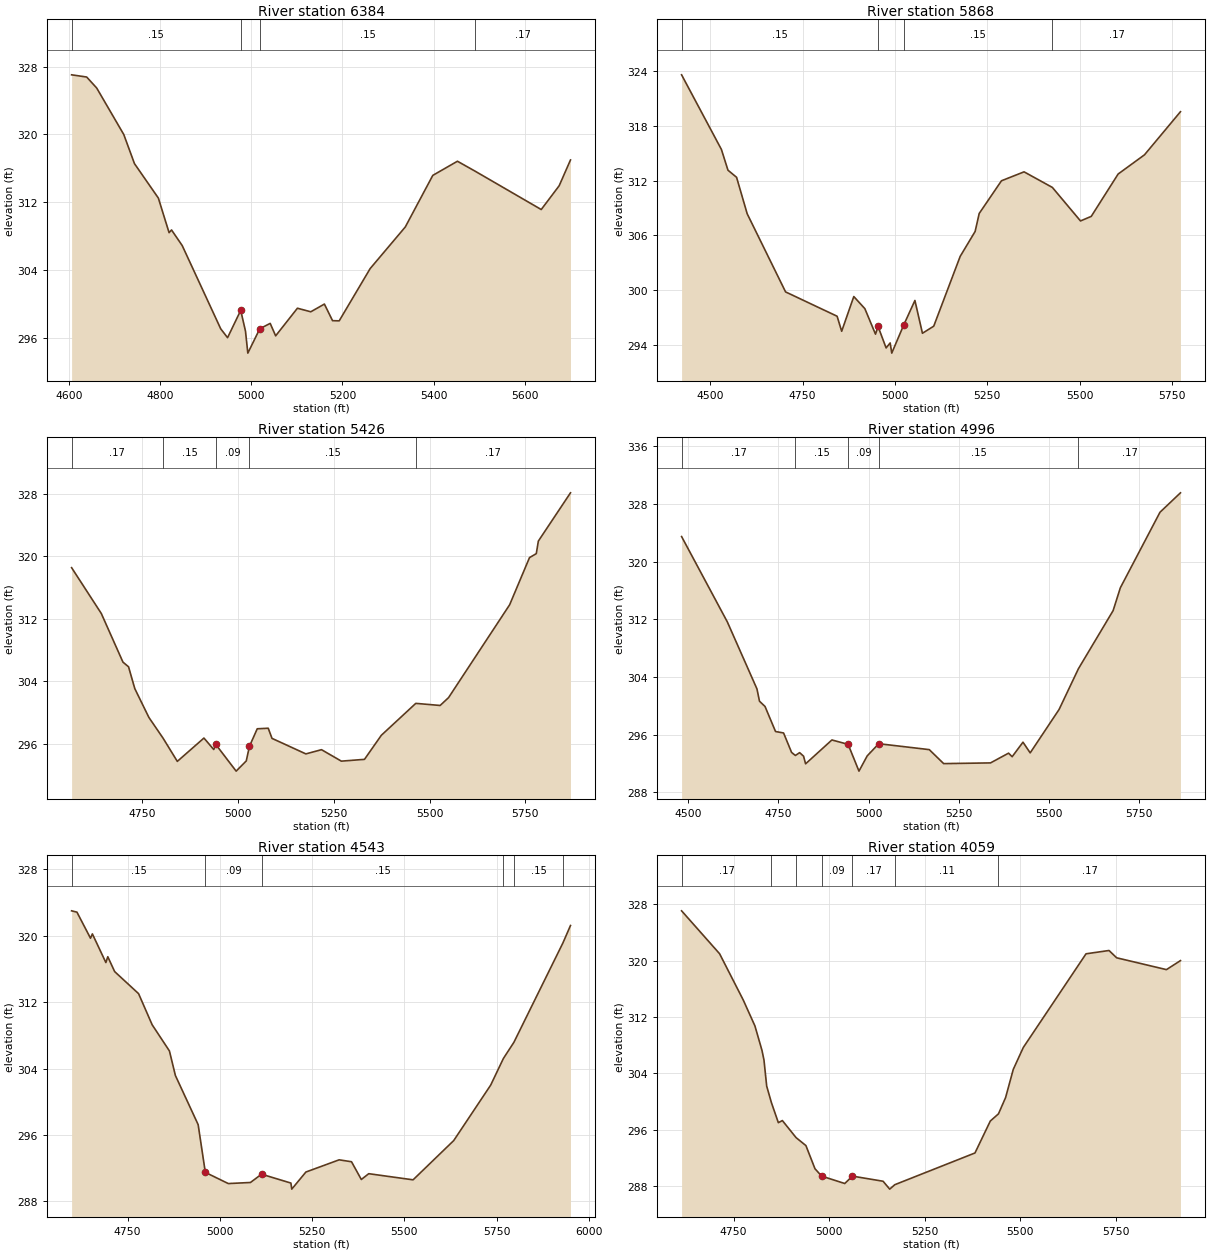
Type RM Length L Ch R = 1 ,6384    ,516,516,516
BEGIN DESCRIPTION:
LITTLE CHINQUAPIN CREEK 11.0
END DESCRIPTION:
XS GIS Cut Line= 3
      3812138.13      10220490.6      3811981.62     10220852.84
      3811714.01     10221500.42
#Sta/Elev= 30
  4605.4  327.04  4638.5  326.78  4660.4  325.49  4719.9     320  4743.4  316.56
  4795.9  312.49  4819.4  308.41  4824.8  308.73  4848.3  306.88  4932.7  297.07
  4947.8  296.01  4976.7  299.24  4987.2  296.77  4992.3  294.19  5018.6  297.07
  5041.4   297.7  5053.4  296.23  5101.2  299.49  5130.5  299.07  5160.4  299.98
  5178.3  298.02  5192.9     298  5260.9  304.17    5338  309.08  5398.4  315.17
  5452.5  316.84  5491.2  315.67  5636.5  311.14  5675.9  313.95  5700.7  316.99
#Mann= 4 ,-1 , 0
  4605.4     .15       0  4976.7     .09       0  5018.6     .15       0
  5491.2     .17       0
Bank Sta=4976.7,5018.6
XS Rating Curve= 0 ,0
Exp/Cntr=0.3,0.1

Type RM Length L Ch R = 1 ,5868    ,442,442,442
BEGIN DESCRIPTION:
LITTLE CHINQUAPIN CREEK 10.0
END DESCRIPTION:
XS GIS Cut Line= 3
      3812053.98     10220473.44      3811525.96     10220708.07
      3811377.01     10221466.68
#Sta/Elev= 30
  4422.2  323.61    4530  315.42  4547.8  313.14  4571.1  312.36  4599.8  308.36
  4703.8  299.78  4843.3  297.11  4855.7  295.46  4888.5  299.27  4918.5  297.94
  4947.3  295.14  4954.2  295.99    4976  293.63    4987  294.18  4991.3  293.06
  5023.4  296.12    5054  298.84  5074.4  295.24    5105  296.02  5176.6  303.68
  5217.1  306.42  5228.1  308.39  5288.4  311.98  5349.6  312.96  5426.2  311.25
  5502.4  307.57  5531.5  308.07  5604.3  312.72  5675.7  314.83  5773.1  319.56
#Mann= 4 ,-1 , 0
  4422.2     .15       0  4954.2     .09       0  5023.4     .15       0
  5426.2     .17       0
Bank Sta=4954.2,5023.4
XS Rating Curve= 0 ,0
Exp/Cntr=0.3,0.1

Type RM Length L Ch R = 1 ,5426    ,430,430,430
BEGIN DESCRIPTION:
LITTLE CHINQUAPIN CREEK 9.0
END DESCRIPTION:
XS GIS Cut Line= 3
      3811367.86     10220011.04      3811223.58     10220419.83
      3810867.86     10221211.04
#Sta/Elev= 30
  4566.5  318.55  4643.9  312.68  4700.4  306.44    4715  305.84  4731.3  303.04
    4768  299.35  4805.1  296.68  4842.2  293.71  4911.6   296.7  4937.2  295.23
  4942.5  295.88  4995.6  292.46    5022  293.77 5030.27  295.64  5050.6  297.89
  5079.3  297.96  5089.1  296.66  5177.4  294.67  5218.2  295.21    5270  293.74
  5330.3  293.97  5374.1  297.05  5464.1  301.15  5527.6  300.88  5549.6  301.89
  5708.8  313.79  5760.6  319.84  5778.3  320.35  5783.7  321.96  5867.5  328.15
#Mann= 5 ,-1 , 0
  4566.5     .17       0  4805.1     .15       0  4942.5     .09       0
 5030.27     .15       0  5464.1     .17       0
#XS Ineff= 2 , 0
       0                  5050.6       0  297.89
Permanent Ineff=
       F       T
Bank Sta=4942.5,5030.27
XS Rating Curve= 0 ,0
Exp/Cntr=0.3,0.1

Type RM Length L Ch R = 1 ,4996    ,453,453,453
BEGIN DESCRIPTION:
LITTLE CHINQUAPIN CREEK 8.0
END DESCRIPTION:
XS GIS Cut Line= 3
      3811064.37     10219857.14      3810835.78     10220322.64
      3810817.01     10221187.84
#Sta/Elev= 30
  4481.4  323.47  4608.3  311.64  4690.5  302.35  4697.5  300.65  4712.9  299.92
    4742  296.45  4764.3  296.25  4786.6  293.55  4797.1  293.13  4808.9  293.52
  4819.8  293.03  4825.4  291.97  4898.4  295.28  4943.4  294.67  4973.5  290.96
  4996.3  293.07  5028.4  294.76  5168.5  293.94  5208.5     292  5338.5   292.1
  5388.5  293.45  5398.5  292.96  5428.5  294.97  5448.5  293.49  5528.6   299.5
  5582.4  305.16  5678.6  313.21  5698.6  316.37  5808.6  326.84  5865.4  329.53
#Mann= 5 ,-1 , 0
  4481.4     .17       0  4797.1     .15       0  4943.4     .09       0
  5028.4     .15       0  5582.4     .17       0
Bank Sta=4943.4,5028.4
XS Rating Curve= 0 ,0
Exp/Cntr=0.3,0.1

Type RM Length L Ch R = 1 ,4543    ,484,484,484
BEGIN DESCRIPTION:
LITTLE CHINQUAPIN CREEK 7.0
END DESCRIPTION:
XS GIS Cut Line= 3
      3810370.46     10219767.66       3810465.3     10220158.31
      3810405.25     10221107.02
#Sta/Elev= 30
    4598     323  4612.5  322.84  4649.2   319.7  4654.3  320.22  4690.9  316.77
  4696.1  317.47  4714.7  315.68  4779.6  313.02  4816.3  309.28  4863.2  306.12
  4879.4  303.16  4941.1  297.24 4960.52  291.49  5022.8  290.14  5082.9  290.27
    5113  291.27  5192.6   290.2  5194.9  289.47  5233.2  291.53  5323.4     293
  5356.9  292.77  5383.5  290.63  5403.6  291.33  5523.8  290.59    5634  295.32
  5734.2     302  5768.8  305.22  5797.2  307.16  5930.2  319.14  5950.6  321.23
#Mann= 6 ,-1 , 0
    4598     .15       0 4960.52     .09       0    5113     .15       0
  5768.8     .17       0  5797.2     .15       0  5930.2     .17       0
Bank Sta=4960.52,5113
XS Rating Curve= 0 ,0
Exp/Cntr=0.3,0.1

Type RM Length L Ch R = 1 ,4059    ,410,410,410
BEGIN DESCRIPTION:
LITTLE CHINQUAPIN CREEK 6.0
END DESCRIPTION:
XS GIS Cut Line= 3
      3810130.89     10219764.19      3810044.02     10220140.39
      3810096.07     10221057.71
#Sta/Elev= 30
  4613.9   327.1  4713.3     321  4774.9  314.45  4805.7  310.74  4824.2  307.25
  4829.4  305.88  4836.5  302.17  4848.9  299.82    4867  296.98  4877.5  297.28
  4913.4  294.85  4939.1  293.72  4962.8  290.43  4980.2  289.38  5040.7  288.33
  5060.8  289.38  5140.9  288.65  5158.3  287.53  5171.6  288.16  5381.3  292.67
  5421.4  297.21  5442.7  298.23  5461.4  300.55  5481.5  304.56  5507.7  307.67
  5671.8  320.99  5731.9  321.46  5751.9  320.42  5882.1  318.74  5918.8  320.02
#Mann= 7 ,-1 , 0
  4613.9     .17       0  4848.9     .11       0  4913.4     .17       0
  4980.2     .09       0  5060.8     .17       0  5171.6     .11       0
  5442.7     .17       0
Bank Sta=4980.2,5060.8
XS Rating Curve= 0 ,0
Exp/Cntr=0.3,0.1

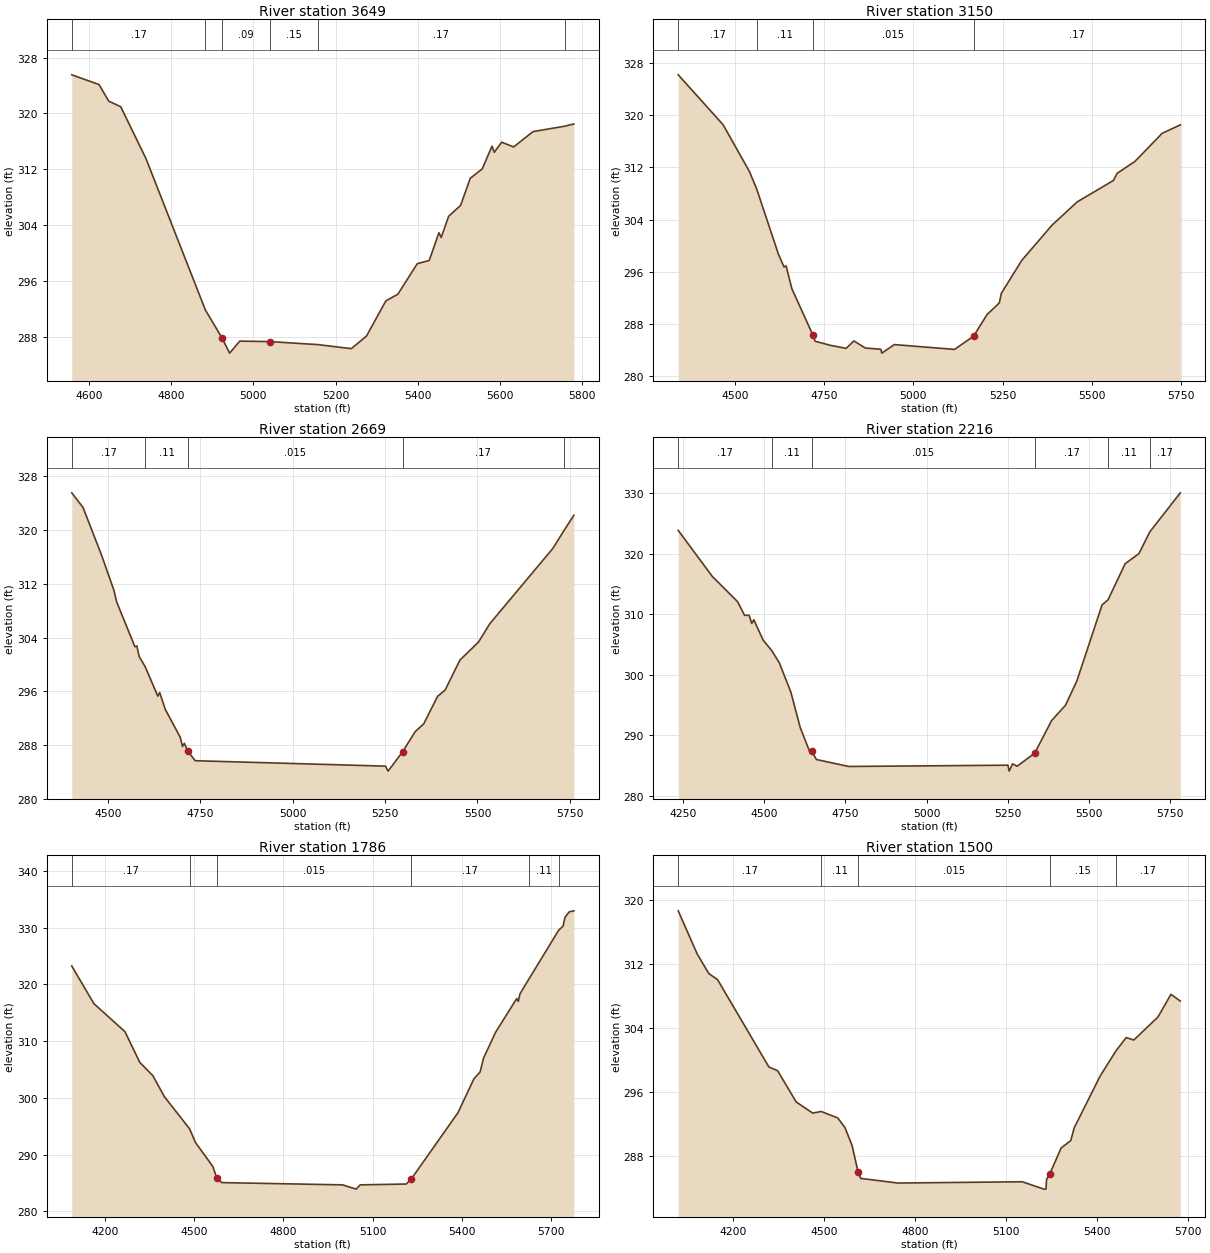
Type RM Length L Ch R = 1 ,3649    ,499,499,499
BEGIN DESCRIPTION:
LITTLE CHINQUAPIN CREEK 5.0
END DESCRIPTION:
XS GIS Cut Line= 3
      3809828.79     10219694.78      3809655.61     10220101.55
      3809960.73     10220819.72
#Sta/Elev= 30
  4557.9  325.52  4624.3  324.13  4647.9  321.75    4677  320.96  4738.6  313.52
  4883.2  291.84  4923.4  287.86  4942.3  285.66  4966.9  287.38  5040.8  287.31
  5157.1  286.88  5238.5   286.3  5275.4   288.1  5322.7  293.15  5351.8  294.09
  5399.1  298.47  5428.2  298.93  5451.8  302.91  5457.3  302.22  5475.5  305.26
  5504.6  306.82  5528.2  310.71  5557.3  312.05    5581   315.3  5586.4  314.42
  5604.6  315.87  5633.7  315.19    5681  317.39  5757.9  318.16  5780.3  318.48
#Mann= 6 ,-1 , 0
  4557.9     .17       0  4883.2     .15       0  4923.4     .09       0
  5040.8     .15       0  5157.1     .17       0  5757.9     .11       0
Bank Sta=4923.4,5040.8
XS Rating Curve= 0 ,0
Exp/Cntr=0.3,0.1

Type RM Length L Ch R = 1 ,3150    ,481,481,481
BEGIN DESCRIPTION:
LITTLE CHINQUAPIN CREEK 4.0
END DESCRIPTION:
XS GIS Cut Line= 3
      3808856.59     10219601.04      3809176.15     10220177.14
      3809290.54     10220916.55
#Sta/Elev= 30
  4341.2  326.18    4467  318.53  4540.5  311.39  4561.1  308.68  4621.8  298.72
  4637.8  296.72  4643.5  296.91  4659.5  293.42  4718.6  286.29  4724.8  285.35
  4768.2  284.72  4811.7  284.26  4833.5   285.4  4865.5  284.31    4909  284.12
  4911.7  283.53  4946.8  284.84  5115.3   284.1 5168.96  286.12  5206.4  289.43
  5240.9  291.22  5246.8  292.71    5304  297.75  5388.5  303.13  5459.3  306.71
  5560.5  309.98  5571.4  311.09  5621.2  312.92  5697.5  317.22  5748.2  318.51
#Mann= 4 ,-1 , 0
  4341.2     .17       0  4561.1     .11       0  4718.6    .015       0
 5168.96     .17       0
Bank Sta=4718.6,5168.96
XS Rating Curve= 0 ,0
Exp/Cntr=0.3,0.1

Type RM Length L Ch R = 1 ,2669    ,453,453,453
BEGIN DESCRIPTION:
LITTLE CHINQUAPIN CREEK 3.0
END DESCRIPTION:
XS GIS Cut Line= 3
      3808790.61     10219600.99      3808695.58      10220191.9
      3808603.24     10220947.17
#Sta/Elev= 30
  4401.5  325.55    4432  323.37  4482.6  316.21  4515.7  311.03  4523.1   309.3
  4572.5  302.64  4577.6  302.77  4583.9  301.21  4600.9   299.6  4634.4  295.29
  4639.5  295.83  4654.8  293.31  4695.3  289.16  4701.3   287.8  4706.4  288.27
  4715.6  287.09  4735.8  285.68    5251  284.87    5258  284.13 5297.25  287.01
  5331.6  290.03  5354.4  291.16  5392.1  295.27  5412.2  296.18  5452.5  300.66
  5502.9  303.35  5533.1  306.05  5704.4   317.3    5733  319.83  5760.9  322.21
#Mann= 5 ,-1 , 0
  4401.5     .17       0  4600.9     .11       0  4715.6    .015       0
 5297.25     .17       0    5733     .11       0
Bank Sta=4715.6,5297.25
XS Rating Curve= 0 ,0
Exp/Cntr=0.3,0.1

Type RM Length L Ch R = 1 ,2216    ,430,430,430
BEGIN DESCRIPTION:
LITTLE CHINQUAPIN CREEK 2.0
END DESCRIPTION:
XS GIS Cut Line= 3
      3808714.22     10219580.17      3808243.09     10220182.75
      3807717.88     10220761.04
#Sta/Elev= 30
  4235.1  323.84  4339.4  316.27  4418.1  312.04  4439.3   309.8  4453.4   309.8
  4461.5  308.45  4467.9  309.06  4496.8  305.68  4523.1  303.97  4546.5  301.93
  4581.8  297.12  4610.7  291.26  4639.7  287.28    4646  287.38  4660.5  285.96
  4759.9  284.81  5250.4  285.02  5254.1  284.04  5264.6  285.24  5278.8  284.85
 5332.94  287.02  5384.9   292.4  5427.5  294.92  5462.6  298.95  5540.3  311.53
  5558.8  312.38  5611.3  318.33  5653.9  320.01  5687.1  323.58  5781.2  330.05
#Mann= 6 ,-1 , 0
  4235.1     .17       0  4523.1     .11       0    4646    .015       0
 5332.94     .17       0  5558.8     .11       0  5687.1     .17       0
Bank Sta=4646,5332.94
XS Rating Curve= 0 ,0
Exp/Cntr=0.3,0.1

Type RM Length L Ch R = 1 ,1786    ,286,286,286
BEGIN DESCRIPTION:
LITTLE CHINQUAPIN CREEK 1.0
END DESCRIPTION:
XS GIS Cut Line= 3
      3808667.85     10219561.07      3807861.13     10219984.72
      3807665.66     10220736.22
#Sta/Elev= 30
  4088.8  323.25  4163.2  316.61  4267.8  311.66  4317.5  306.26  4361.6   303.9
    4400  300.22    4485  294.54  4504.6  292.14  4563.2  287.89  4576.4  285.84
  4592.8  285.07    4999  284.67  5044.7  283.92  5058.2  284.67  5213.2  284.82
  5230.1  285.71  5387.1   297.4  5440.5  303.35  5461.2  304.55  5473.3  307.05
  5513.8   311.6  5584.5   317.5  5589.7  317.01  5595.5  318.34  5625.6  320.96
  5726.1   329.6  5740.2  330.25  5746.6   331.8  5760.9  332.79  5776.5  332.97
#Mann= 6 ,-1 , 0
  4088.8     .17       0    4485     .11       0  4576.4    .015       0
  5230.1     .17       0  5625.6     .11       0  5726.1     .17       0
Bank Sta=4576.4,5230.1
XS Rating Curve= 0 ,0
Exp/Cntr=0.3,0.1

Type RM Length L Ch R = 1 ,1500    ,500,500,500
BEGIN DESCRIPTION:
LITTLE CHINQUAPIN CREEK 3.5
END DESCRIPTION:
XS GIS Cut Line= 3
      3808564.89     10219385.74      3807664.08     10219777.22
      3807429.49     10220410.04
#Sta/Elev= 30
  4017.8   318.6    4080  313.24  4118.6  310.77  4147.5  310.01  4317.1  299.09
    4346  298.62  4407.1  294.72  4461.6  293.33  4489.7  293.53  4544.4  292.72
  4567.9  291.53  4591.3  289.32 4611.56  285.96  4620.2  285.17  4742.9  284.59
  5153.4  284.75  5224.7  283.83  5231.5  283.83  5233.5  285.06 5243.54  285.68
  5281.4  288.96  5313.4   289.9  5324.7  291.49  5410.5  297.97  5462.1  301.08
  5496.3  302.76  5521.4  302.46  5601.3  305.34    5644  308.17  5674.9  307.33
#Mann= 5 ,-1 , 0
  4017.8     .17       0  4489.7     .11       0 4611.56    .015       0
 5243.54     .15       0  5462.1     .17       0
Bank Sta=4611.56,5243.54
XS Rating Curve= 0 ,0
Exp/Cntr=0.3,0.1

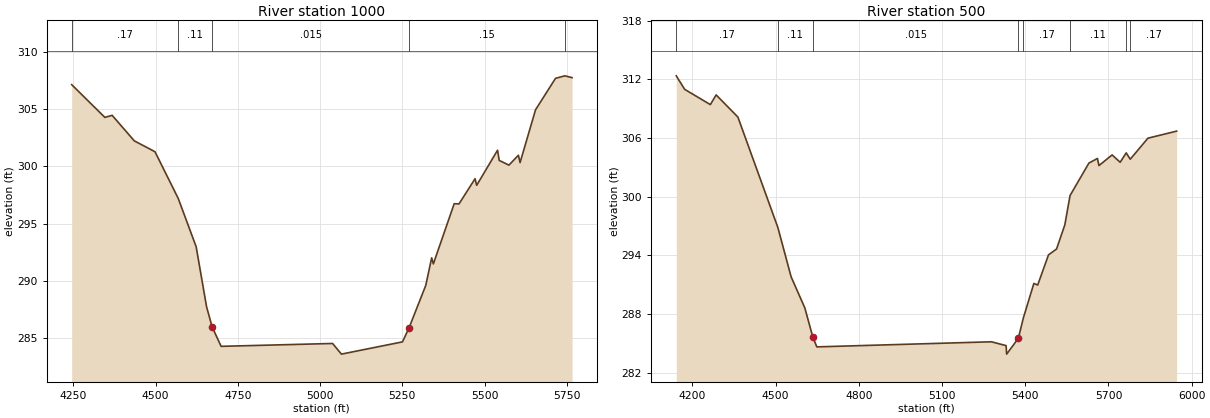
Type RM Length L Ch R = 1 ,1000    ,500,500,500
BEGIN DESCRIPTION:
LITTLE CHINQUAPIN CREEK 2.5
END DESCRIPTION:
XS GIS Cut Line= 3
      3807571.87     10218819.72      3807251.05      10219503.5
        3807367.     10220260.78
#Sta/Elev= 30
  4244.7  307.13  4345.6  304.27  4367.7  304.45  4435.1  302.22    4498  301.27
  4568.7  297.19  4623.2  292.97  4654.9  287.72 4671.76  285.97  4699.1  284.27
    5038  284.52  5064.9  283.59  5250.5  284.66  5270.7   285.9  5321.3  289.59
  5339.3     292  5344.4  291.47  5407.8  296.73  5422.4  296.71  5471.2  298.91
  5476.2  298.34  5539.6   301.4  5544.7  300.51  5574.2   300.1    5603  300.96
  5608.1  300.32  5655.1  304.93  5715.8  307.68  5744.2   307.9  5766.1  307.74
#Mann= 5 ,-1 , 0
  4244.7     .17       0  4568.7     .11       0 4671.76    .015       0
  5270.7     .15       0  5744.2     .17       0
Bank Sta=4671.76,5270.7
XS Rating Curve= 0 ,0
Exp/Cntr=0.3,0.1

Type RM Length L Ch R = 1 ,500     ,0,0,0
BEGIN DESCRIPTION:
LITTLE CHINQUAPIN CREEK 1.5
END DESCRIPTION:
XS GIS Cut Line= 3
      3807353.13     10218594.04      3806813.57     10219261.41
      3807182.91     10220132.11
#Sta/Elev= 30
  4141.8  312.35  4172.1  310.97  4264.8  309.41  4285.6   310.4    4364  308.14
  4508.1  296.86  4555.9  291.82  4605.4  288.64  4634.2  285.66  4648.6  284.66
  5278.2  285.18    5331  284.79    5333  283.92 5375.04  285.53  5393.4  287.63
  5431.1  291.14    5445  290.98  5483.9  294.06    5513  294.66  5542.8  297.13
  5561.6  300.12  5629.7  303.44  5660.4  303.91  5665.8  303.18  5713.2  304.27
  5742.3  303.52  5764.2  304.48  5778.6  303.83  5842.4  305.98  5945.8   306.7
#Mann= 8 ,-1 , 0
  4141.8     .17       0  4508.1     .11       0  4634.2    .015       0
 5375.04     .11       0  5393.4     .17       0  5561.6     .11       0
  5764.2     .15       0  5778.6     .17       0
Bank Sta=4634.2,5375.04
XS Rating Curve= 0 ,0
Exp/Cntr=0.3,0.1

Chan Stop Cuts=-1
Use User Specified Reach Order=0
Composite Channel Slope=5