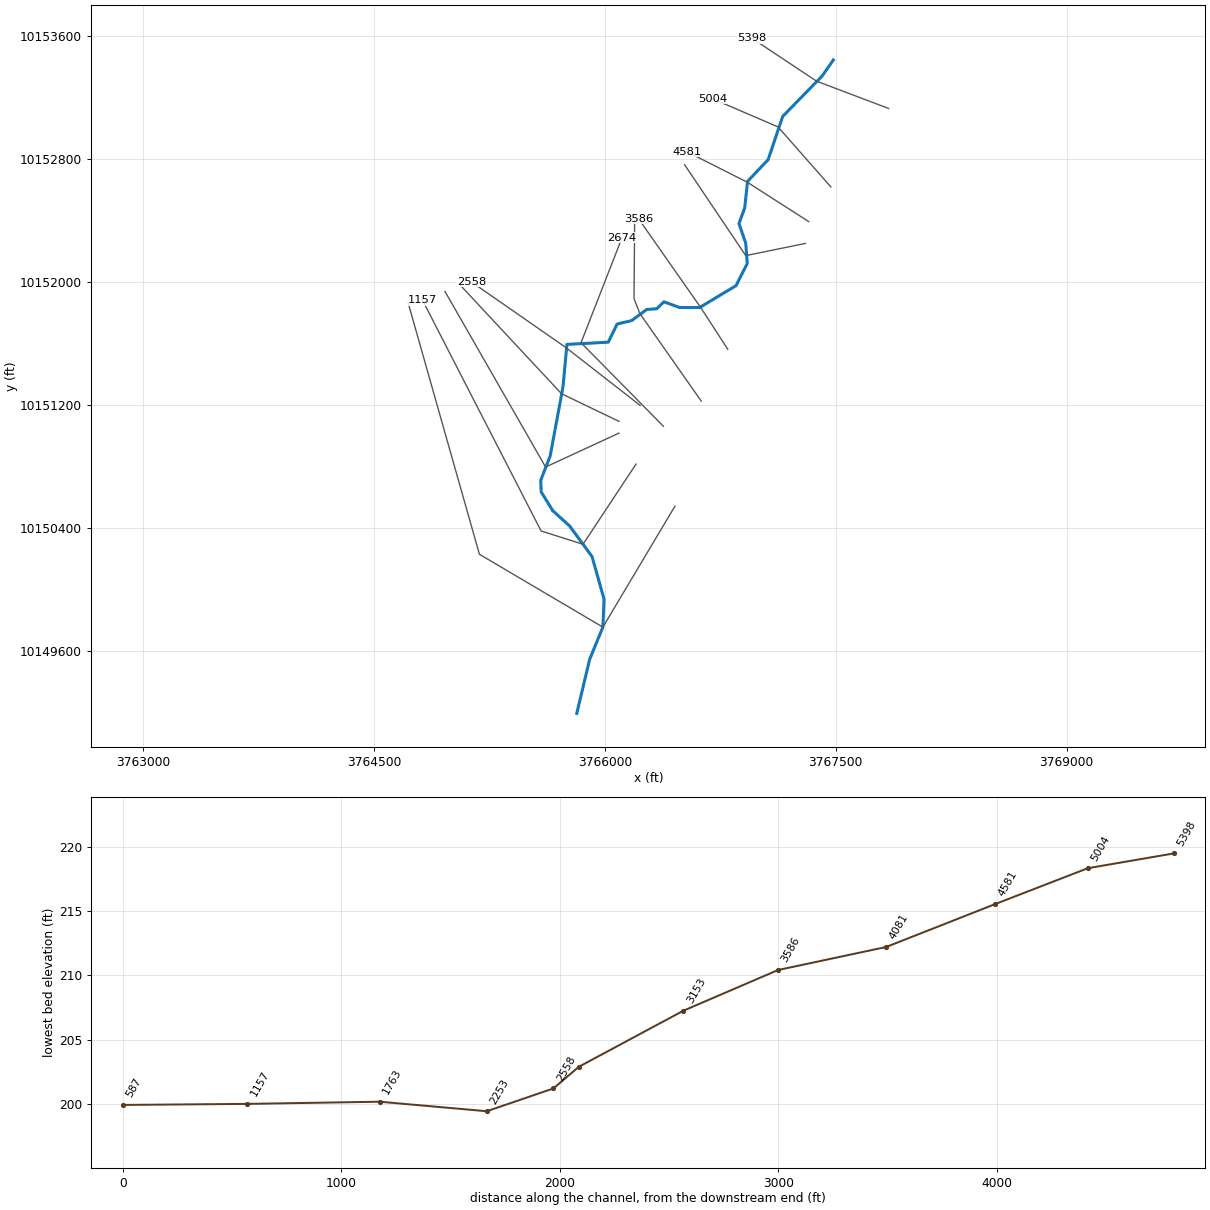
--- LITTLE LAKE CREEK TRIB NO 1.prj (project) ---

Proj Title=LITTLE LAKE CREEK TRIB NO 1 Base Level Engineering
Current Plan=p01
Default Exp/Contr=0.3,0.1
English Units
Geom File=g01
Flow File=f01
Plan File=p01
Y Axis Title=Elevation
X Axis Title(PF)=Main Channel Distance
X Axis Title(XS)=Station
BEGIN DESCRIPTION:
LITTLE LAKE CREEK TRIB NO 1
END DESCRIPTION:
DSS Export Rating Curves= 0
DSS Export Rating Curve Sorted= 0
DSS Export Volume Flow Curves= 0
DXF OffsetX= 0
DXF OffsetY= 0
DXF ScaleX= 1
DXF ScaleY= 10

--- LITTLE LAKE CREEK TRIB NO 1.p01 (plan) ---

Plan Title=Multiple Run
Short Identifier=Multiple
Geom File=g01
Flow File=f01
Subcritical Flow
K Sum by GR= 0
Std Step Tol= 0.01
Critical Tol= 0.01
Num of Std Step Trials= 20
Max Error Tol= 0.3
Flow Tol Ratio= 0.001
Split Flow NTrial= 30
Split Flow Tol= 0.02
Split Flow Ratio= 0.02
Log Output Level= 0
Friction Slope Method= 1
Unsteady Friction Slope Method= 2
Unsteady Bridges Friction Slope Method= 1
Parabolic Critical Depth
Global Vel Dist=  1 , 1 , 1
Global Log Level= 0
CheckData=True
Encroach Param= -1, 0, 0, 0
BEGIN DESCRIPTION:
Multiple Run
END DESCRIPTION:

--- LITTLE LAKE CREEK TRIB NO 1.f01 (steady flow) ---

Flow Title=Multiple
Program Version=4.10
Number of Profiles= 7
Profile Names=10-year,25-year,50-year,1pct_min,100-year,1pct_plu,500-year
River Rch & RM=LITTLE LAKE CREE,Reach-1         ,5398
     595     803    1082     480    1450    4379    2692
River Rch & RM=LITTLE LAKE CREE,Reach-1         ,2253
     103     121     151      62     186     562     292
Boundary for River Rch & Prof#=LITTLE LAKE CREE,Reach-1         , 1
Up Type= 0
Dn Type= 3
Dn Slope=0.0001
Boundary for River Rch & Prof#=LITTLE LAKE CREE,Reach-1         , 2
Up Type= 0
Dn Type= 3
Dn Slope=0.0001
Boundary for River Rch & Prof#=LITTLE LAKE CREE,Reach-1         , 3
Up Type= 0
Dn Type= 3
Dn Slope=0.0001
Boundary for River Rch & Prof#=LITTLE LAKE CREE,Reach-1         , 4
Up Type= 0
Dn Type= 3
Dn Slope=0.0001
Boundary for River Rch & Prof#=LITTLE LAKE CREE,Reach-1         , 5
Up Type= 0
Dn Type= 3
Dn Slope=0.0001
Boundary for River Rch & Prof#=LITTLE LAKE CREE,Reach-1         , 6
Up Type= 0
Dn Type= 3
Dn Slope=0.0001
Boundary for River Rch & Prof#=LITTLE LAKE CREE,Reach-1         , 7
Up Type= 0
Dn Type= 3
Dn Slope=0.0001
DSS Import GetInterval= 0
DSS Import GetPeak= 0
DSS Import FillOption= 0

--- LITTLE LAKE CREEK TRIB NO 1.g01 (geometry) ---

Geom Title=Existing Conditions
Program Version=4.10

River Reach=LITTLE LAKE CREE,Reach-1
Reach XY= 30
      3767484.22     10153442.11      3767411.49     10153337.99
      3767155.23     10153075.33      3767060.28     10152794.07
      3766926.71     10152653.05      3766908.35     10152480.75
      3766870.91     10152378.92      3766914.91     10152251.46
      3766924.99     10152119.65      3766851.77     10151975.62
      3766615.61     10151833.53      3766485.37     10151833.44
      3766383.15      10151870.8       3766336.8     10151825.48
       3766271.7      10151820.8      3766173.26      10151748.4
      3766078.99       10151726.       3766021.7      10151608.3
      3765752.86      10151593.8      3765727.42     10151317.67
      3765644.09     10150868.45      3765582.89      10150710.9
       3765585.5     10150635.38      3765661.02     10150512.98
      3765770.39     10150414.02      3765916.23     10150214.81
      3765994.35     10149937.46      3765986.54     10149756.47
       3765900.6     10149546.84      3765816.95     10149195.95

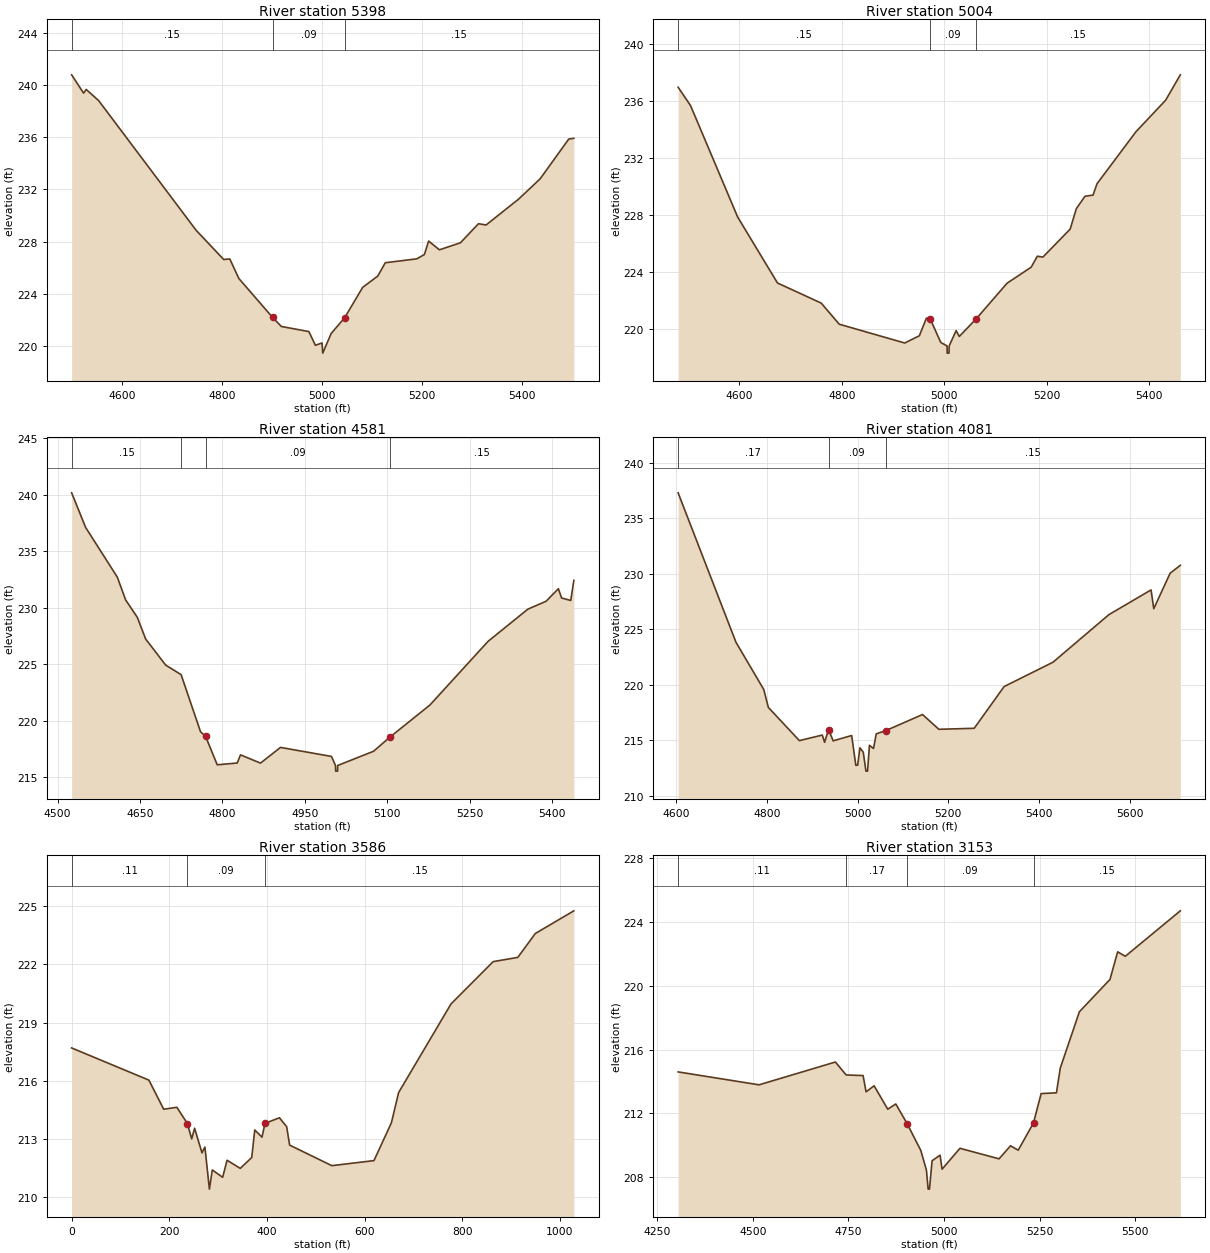
Type RM Length L Ch R = 1 ,5398    ,394,394,394
BEGIN DESCRIPTION:
LITTLE LAKE CREEK TRIB NO 1 1.0
END DESCRIPTION:
XS GIS Cut Line= 3
       3767843.6      10153127.1      3767375.41     10153304.32
      3766956.06      10153582.8
#Sta/Elev= 30
  4499.4  240.78  4523.2  239.38  4528.5  239.66  4553.3  238.81  4748.4  228.87
  4803.4  226.64  4815.6  226.68  4833.6  225.19  4901.2   222.2  4918.7  221.51
  4973.7  221.12  4986.7  220.07    5000  220.25  5001.4  219.47  5018.2  220.97
  5045.2  222.18  5081.3  224.51  5111.4  225.37  5126.4  226.39  5189.5  226.69
  5204.6  227.02  5213.1  228.05  5234.7  227.38  5276.7  227.92  5312.8  229.38
  5327.9  229.28  5393.2  231.27  5436.1  232.82  5493.2  235.86  5503.4  235.92
#Mann= 3 , 0 , 0
  4499.4     .15       0  4901.2     .09       0  5045.2     .15       0
Bank Sta=4901.2,5045.2
XS Rating Curve= 0 ,0
Exp/Cntr=0.3,0.1

Type RM Length L Ch R = 1 ,5004    ,423,423,423
BEGIN DESCRIPTION:
Mapping XS a680af77
END DESCRIPTION:
XS GIS Cut Line= 3
       3767468.2     10152617.08      3767124.72     10153007.23
      3766701.36     10153189.42
#Sta/Elev= 30
  4480.2  236.98  4504.5  235.69  4596.5  227.87  4674.3  223.24  4759.7  221.83
  4794.8  220.35  4922.8  219.03  4951.3  219.54  4965.1  220.77  4972.2  220.75
  4993.1  219.07  5005.5  218.82  5005.7  218.32  5009.2  218.32  5009.5  218.82
  5023.1   219.9  5029.3  219.49  5061.9  220.71  5122.7  223.23  5169.7  224.35
  5181.7  225.12  5192.6  225.06  5245.8  227.02  5257.9  228.46  5274.8  229.33
  5290.5  229.41  5298.3  230.21  5374.4  233.86  5432.3  236.07  5460.9  237.85
#Mann= 3 ,-1 , 0
  4480.2     .15       0  4972.2     .09       0  5061.9     .15       0
Bank Sta=4972.2,5061.9
XS Rating Curve= 0 ,0
Exp/Cntr=0.3,0.1

Type RM Length L Ch R = 1 ,4581    ,500,500,500
BEGIN DESCRIPTION:
LITTLE LAKE CREEK TRIB NO 1 2.0
END DESCRIPTION:
XS GIS Cut Line= 3
      3767324.06      10152392.1      3766924.66      10152647.9
      3766532.82     10152846.07
#Sta/Elev= 30
  4525.7  240.18  4551.2  237.11  4608.7  232.72    4624  230.69  4645.1  229.16
  4660.3  227.24  4696.7  224.93  4724.8  224.08  4760.1  219.03  4769.4  218.61
  4790.5   216.1  4826.9  216.26  4832.8  216.98  4869.2  216.25  4905.5  217.64
  4998.3  216.84  5005.6  216.04  5005.9  215.54  5009.4  215.54  5009.6  216.04
  5074.9   217.3  5104.8  218.56  5177.3  221.39  5283.1  227.03  5355.5  229.88
  5388.6  230.58    5411  231.69  5416.8  230.87  5433.5  230.65  5439.1  232.43
#Mann= 4 ,-1 , 0
  4525.7     .15       0  4724.8     .17       0  4769.4     .09       0
  5104.8     .15       0
Bank Sta=4769.4,5104.8
XS Rating Curve= 0 ,0
Exp/Cntr=0.3,0.1

Type RM Length L Ch R = 1 ,4081    ,495,495,495
BEGIN DESCRIPTION:
LITTLE LAKE CREEK TRIB NO 1 3.0
END DESCRIPTION:
XS GIS Cut Line= 3
      3767302.82     10152249.95      3766915.02      10152170.8
      3766517.83     10152761.11
#Sta/Elev= 30
  4604.2  237.28  4731.7  223.82    4793  219.56  4803.2  217.94  4871.6  214.95
  4922.1  215.45  4927.2   214.8  4935.9  215.94  4946.1  214.93  4986.9  215.41
    4996  212.73    5000  212.73  5005.1   214.3  5012.4  213.91  5018.4   212.2
  5021.9   212.2  5026.1  214.53  5035.1  214.24  5041.1  215.56  5062.1  215.85
  5143.1   217.3  5179.1  215.97  5257.1  216.06    5323  219.82    5431  222.02
    5554   226.3    5647  228.53    5653  226.84    5689  230.03  5711.5  230.75
#Mann= 3 ,-1 , 0
  4604.2     .17       0  4935.9     .09       0  5062.1     .15       0
Bank Sta=4935.9,5062.1
XS Rating Curve= 0 ,0
Exp/Cntr=0.3,0.1

Type RM Length L Ch R = 1 ,3586    ,433,433,433
XS GIS Cut Line= 3
      3766798.15     10151562.22      3766621.37     10151834.87
      3766217.85     10152411.07
#Sta/Elev= 30
       0  217.69   158.2  216.03   188.5  214.53   215.5  214.63     237  213.79
   245.8     213   251.8  213.55   266.9  212.28   272.9  212.58   282.1  210.41
     288   211.4   309.2  211.02   318.3   211.9   345.3  211.48   368.8  212.04
     375  213.46   389.8  213.09   395.9   213.8   425.5  214.09   440.3  213.63
   446.4  212.68   532.8  211.62   619.1  211.88   654.8  213.83   669.6  215.39
   776.9  219.96   863.2  222.14   913.7  222.36   949.5  223.59  1028.4  224.76
#Mann= 3 , 0 , 0
       0     .11       0     237     .09       0   395.9     .15       0
Bank Sta=237,395.9
XS Rating Curve= 0 ,0
Exp/Cntr=0.3,0.1

Type RM Length L Ch R = 1 ,3153    ,479,479,479
BEGIN DESCRIPTION:
LITTLE LAKE CREEK TRIB NO 1 5.0
END DESCRIPTION:
XS GIS Cut Line= 4
      3766625.99     10151225.12       3766226.9     10151794.23
       3766188.9     10151891.37      3766193.14     10152404.85
#Sta/Elev= 30
  4304.9   214.6  4516.5  213.79  4716.1  215.22  4744.1  214.41  4788.5  214.37
  4796.3  213.35  4817.3  213.73    4853  212.26    4874  212.59  4903.5  211.36
  4939.3  209.68  4954.1  208.44  4958.5  207.25    4962  207.25  4968.9  209.03
  4989.8  209.38    4995   208.5  5041.7  209.81    5144  209.15    5174  209.97
    5194  209.69    5234   211.4    5254  213.24    5294  213.29    5304  214.84
    5354  218.37    5434   220.4    5454  222.13    5474  221.85  5617.8   224.7
#Mann= 4 ,-1 , 0
  4304.9     .11       0  4744.1     .17       0  4903.5     .09       0
    5234     .15       0
#XS Ineff= 2 , 0
       0    4874  212.59               0
Permanent Ineff=
       F       F
Bank Sta=4903.5,5234
XS Rating Curve= 0 ,0
Exp/Cntr=0.3,0.1

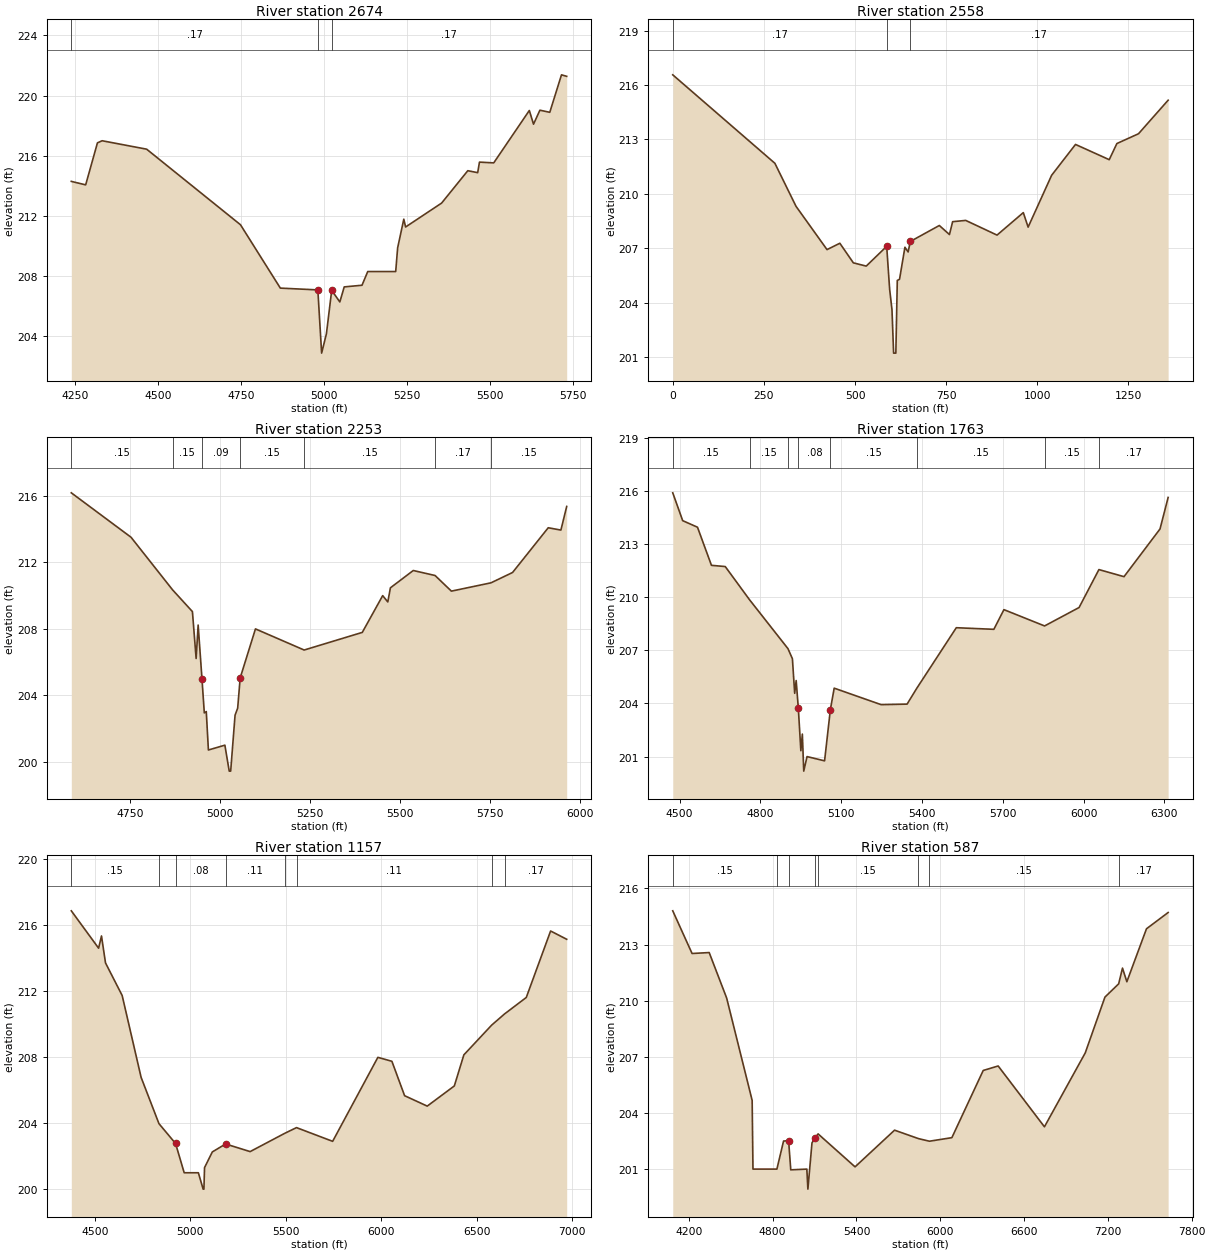
Type RM Length L Ch R = 1 ,2674    ,116,116,116
BEGIN DESCRIPTION:
LITTLE LAKE CREEK TRIB NO 1 6.0
END DESCRIPTION:
XS GIS Cut Line= 3
      3766379.88     10151061.74      3765844.61     10151604.65
       3766110.4     10152286.05
#Sta/Elev= 30
  4237.6   214.3  4280.9  214.07  4316.4  216.86  4330.5     217  4464.8  216.44
  4747.7  211.42  4867.9  207.21    4981  207.09  4992.4  202.89  5006.9  204.18
  5022.8  207.06  5047.3  206.29  5060.6  207.29  5114.2   207.4  5131.5  208.31
  5215.8  208.31  5221.6  209.88  5240.2  211.79  5245.6  211.27  5354.3  212.86
  5433.2  215.01    5463  214.88  5468.4  215.58  5511.4  215.53  5618.7  219.01
  5631.4   218.1  5650.6  219.03  5680.4  218.89  5715.7  221.38  5731.4  221.28
#Mann= 3 , 0 , 0
  4237.6     .17       0    4981     .09       0  5022.8     .17       0
Bank Sta=4981,5022.8
XS Rating Curve= 0 ,0
Exp/Cntr=0.3,0.1

Type RM Length L Ch R = 1 ,2558    ,305,305,305
XS GIS Cut Line= 3
      3766228.61     10151197.49      3765748.69     10151571.58
        3765132.     10152000.17
#Sta/Elev= 30
       0  216.56   280.2  211.68   338.1  209.31   423.2  206.92   458.4  207.27
   495.4  206.19   530.8  206.01   586.9   207.1     595  204.73   601.4  203.61
   605.9  201.21     612  201.21     616  205.22   622.1  205.28   636.9  207.05
   645.7  206.79   651.8  207.37   731.3  208.25   759.1  207.75   767.8  208.46
   803.7  208.53   889.6  207.72   961.7  208.96   974.9  208.16  1039.4  211.02
  1104.9  212.72  1197.4  211.88  1218.4  212.77  1277.7  213.31    1359  215.16
#Mann= 3 , 0 , 0
       0     .17       0   586.9     .09       0   651.8     .17       0
Bank Sta=586.9,651.8
XS Rating Curve= 0 ,0
Exp/Cntr=0.3,0.1

Type RM Length L Ch R = 1 ,2253    ,490,490,490
BEGIN DESCRIPTION:
LITTLE LAKE CREEK TRIB NO 1 7.0
END DESCRIPTION:
XS GIS Cut Line= 3
       3766091.3     10151093.59      3765717.74     10151273.23
      3765061.21     10151977.19
#Sta/Elev= 30
  4585.5  216.17  4751.5   213.5  4867.3  210.33  4922.2  209.03  4932.5  206.21
  4938.1  208.22 4948.73  204.99  4955.2  202.94  4960.7  203.02  4966.6  200.71
  5012.4     201  5024.5  199.44  5028.5  199.44  5040.7   202.8    5048  203.23
  5054.9  205.04  5097.4  207.99  5232.8  206.72  5394.4  207.78  5451.1  209.99
  5465.3  209.61  5472.6  210.46  5536.1   211.5  5596.7   211.2  5642.1  210.26
  5752.2  210.76  5812.1  211.38  5911.3  214.07  5946.5  213.93  5962.6  215.35
#Mann= 7 ,-1 , 0
  4585.5     .15       0  4867.3     .15       0 4948.73     .09       0
  5054.9     .15       0  5232.8     .15       0  5596.7     .17       0
  5752.2     .15       0
Bank Sta=4948.73,5054.9
XS Rating Curve= 0 ,0
Exp/Cntr=0.3,0.1

Type RM Length L Ch R = 1 ,1763    ,606,606,606
BEGIN DESCRIPTION:
LITTLE LAKE CREEK TRIB NO 1 8.0
END DESCRIPTION:
XS GIS Cut Line= 3
      3766091.31     10151017.21      3765614.14     10150796.84
      3764960.84     10151937.26
#Sta/Elev= 30
  4474.4  215.88  4511.3  214.31  4566.3  213.94  4618.1  211.79  4669.4  211.72
  4759.5  209.85  4902.3  207.09  4918.8  206.52  4927.3  204.57  4932.8  205.29
  4940.8  203.72  4950.2  201.33  4955.7  202.27  4960.9  200.18  4973.2     201
  5038.3  200.76  5059.8  203.65    5074  204.86  5248.3  203.93  5344.7  203.96
  5380.6  204.85  5527.5  208.27    5667  208.18  5704.4  209.29  5855.4  208.37
  5983.5  209.41  6057.2  211.55  6150.4  211.15  6284.1  213.84  6314.3  215.62
#Mann= 8 ,-1 , 0
  4474.4     .15       0  4759.5     .15       0  4902.3     .15       0
  4940.8     .08       0  5059.8     .15       0  5380.6     .15       0
  5855.4     .15       0  6057.2     .17       0
Bank Sta=4940.8,5059.8
XS Rating Curve= 0 ,0
Exp/Cntr=0.3,0.1

Type RM Length L Ch R = 1 ,1157    ,570,570,570
BEGIN DESCRIPTION:
LITTLE LAKE CREEK TRIB NO 1 9.5
END DESCRIPTION:
XS GIS Cut Line= 4
      3766201.64     10150815.66      3765857.51     10150295.02
       3765585.2     10150381.08      3764814.35     10151881.12
#Sta/Elev= 30
  4375.9  216.84    4519  214.58  4534.1  215.32  4555.1  213.69  4642.4  211.72
  4741.7  206.77  4835.2  203.97  4922.3  202.77  4967.5     201  5041.8     201
  5066.8  200.01  5070.9  200.01  5074.1  201.31    5115  202.26  5184.4  202.74
  5313.1  202.28  5493.7  203.38  5556.1  203.73  5745.5   202.9  5982.6  207.98
  6056.1  207.74  6122.6  205.66  6241.2  205.03  6383.2  206.25  6433.2  208.13
  6579.1  209.93    6647  210.61  6760.3   211.6  6887.8  215.62  6972.1  215.12
#Mann= 8 ,-1 , 0
  4375.9     .15       0  4835.2     .15       0  4922.3     .08       0
  5184.4     .11       0  5493.7     .17       0  5556.1     .11       0
  6579.1     .15       0    6647     .17       0
Bank Sta=4922.3,5184.4
XS Rating Curve= 0 ,0
Exp/Cntr=0.3,0.1

Type RM Length L Ch R = 1 ,587     ,0,0,0
BEGIN DESCRIPTION:
LITTLE LAKE CREEK TRIB NO 1 9.0
END DESCRIPTION:
XS GIS Cut Line= 4
      3766455.01     10150542.57      3765986.54     10149756.47
      3765184.16     10150230.04       3764720.6     10151865.51
#Sta/Elev= 30
  4084.9   214.8  4223.2  212.52  4345.8  212.57  4470.8  210.14  4653.4  204.67
  4659.2     201  4830.5     201  4878.2   202.5  4914.3  202.52  4929.8  200.96
  5044.9     201  5052.4  199.93  5081.7   202.4  5103.2  202.67  5125.6  202.88
  5390.1  201.12  5672.9  203.08  5843.6  202.63  5922.6  202.49  6083.3  202.68
  6307.7  206.27  6414.7  206.51    6746  203.26  7038.2  207.21  7179.1  210.19
  7277.5   210.9  7304.8  211.74    7336  211.01  7476.5  213.84  7631.6  214.71
#Mann= 8 ,-1 , 0
  4084.9     .15       0  4830.5     .15       0  4914.3     .09       0
  5103.2     .15       0  5125.6     .15       0  5843.6     .15       0
  5922.6     .15       0  7277.5     .17       0
Bank Sta=4914.3,5103.2
XS Rating Curve= 0 ,0
Exp/Cntr=0.3,0.1

Chan Stop Cuts=-1
Use User Specified Reach Order=0
Composite Channel Slope=5