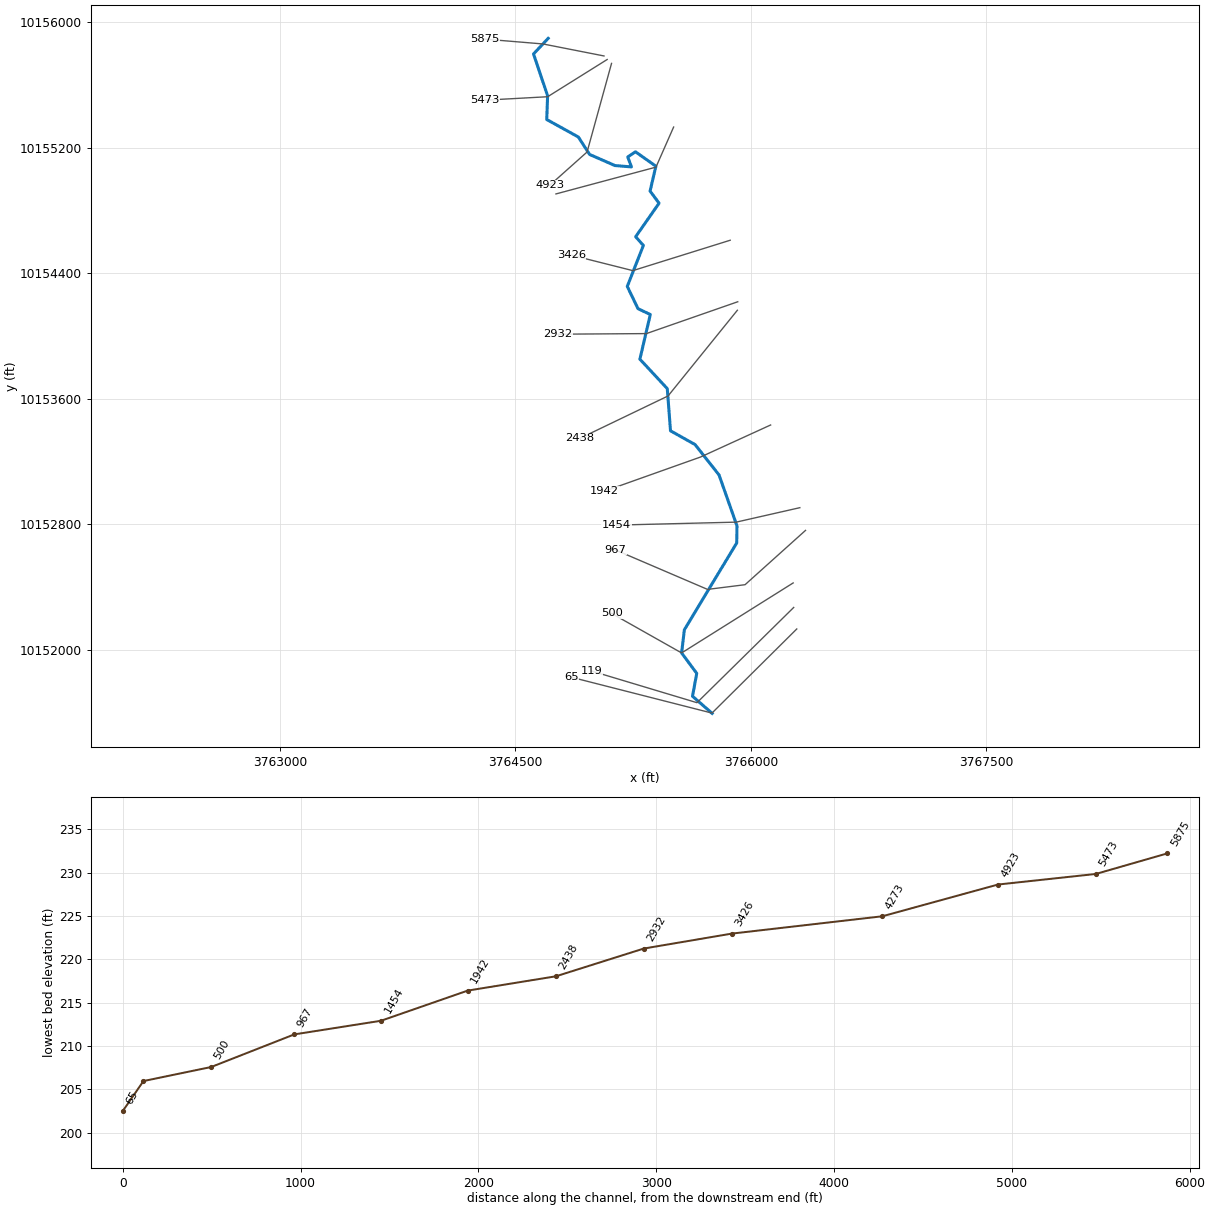
--- LITTLE LAKE CREEK TRIB NO 2.prj (project) ---

Proj Title=LITTLE LAKE CREEK TRIB NO 2 Base Level Engineering
Current Plan=p01
Default Exp/Contr=0.3,0.1
English Units
Geom File=g01
Flow File=f01
Plan File=p01
Y Axis Title=Elevation
X Axis Title(PF)=Main Channel Distance
X Axis Title(XS)=Station
BEGIN DESCRIPTION:
LITTLE LAKE CREEK TRIB NO 2
END DESCRIPTION:
DSS File=dss
DSS Export Rating Curves= 0
DSS Export Rating Curve Sorted= 0
DSS Export Volume Flow Curves= 0
DXF OffsetX= 0
DXF OffsetY= 0
DXF ScaleX= 1
DXF ScaleY= 10

--- LITTLE LAKE CREEK TRIB NO 2.p01 (plan) ---

Plan Title=Multiple Run
Program Version=4.10
Short Identifier=Multiple Run
Geom File=g01
Flow File=f01
Subcritical Flow
K Sum by GR= 0
Std Step Tol= 0.01
Critical Tol= 0.01
Num of Std Step Trials= 20
Max Error Tol= 0.3
Flow Tol Ratio= 0.001
Split Flow NTrial= 30
Split Flow Tol= 0.02
Split Flow Ratio= 0.02
Log Output Level= 0
Friction Slope Method= 1
Unsteady Friction Slope Method= 2
Unsteady Bridges Friction Slope Method= 1
Parabolic Critical Depth
Global Vel Dist= 1 , 1 , 1
Global Log Level= 0
CheckData=True
Encroach Param=-1 ,0,0, 0
BEGIN DESCRIPTION:
Multiple Run
END DESCRIPTION:
Computation Interval=1HOUR
Output Interval=1HOUR
Run HTab= 0
Run UNet= 0
Run PostProcess= 0
Run WQNet= 0
UNET Theta= 1
UNET Theta Warmup= 1
UNET ZTol= 0.02
UNET ZSATol= 0.05
UNET MxIter= 20
UNET MaxInSteps= 0
UNET DtIC= 0
UNET DtMin= 0
UNET MaxCRTS= 20
UNET WFStab= 2
UNET SFStab= 1
UNET WFX= 1
UNET SFX= 1
UNET DSS MLevel= 4
UNET DZMax Abort= 100
UNET Convert EG Bridges= 0
UNET Use Existing IB Tables=-1
UNET Froude Reduction=False
UNET Froude Limit= 1
UNET Froude Power= 10
UNET Time Slicing=0,0, 5
UNET Junction Losses=0
Instantaneous Interval=1HOUR
DSS File=dss
Write IC File= 0
Write IC File at Sim End=0
Echo Input=False
Echo Parameters=False
Echo Output=False
Write Detailed= 0
WQ AD Non Conservative
WQ ULTIMATE=-1
WQ Max Comp Step=1HOUR
WQ Output Interval=15MIN
WQ Output Selected Increments= 0
WQ Output face flow=0
WQ Output face velocity=0
WQ Output face area=0
WQ Output face dispersion=0
WQ Output cell volume=0
WQ Output cell surface area=0
WQ Output cell continuity=0
WQ Output cumulative cell continuity=0
WQ Output face conc=0
WQ Output face dconc_dx=0
WQ Output face courant=0
WQ Output face peclet=0
WQ Output face adv mass=0
WQ Output face disp mass=0
WQ Output cell mass=0
WQ Output cell source sink temp=0
WQ Output cell source sink nsm=0
WQ Output MaxMinRange=-1
WQ Daily Max Min Mean=-1
WQ Daily Range=0
WQ Daily Time=0
WQ Create Restart=0
WQ Fixed Restart=0
WQ System Summary=0
WQ Use Fixed Temperature=0
Sorting and Armoring Iterations= 10
XS Update Threshold= 0.02
Hydraulics Update Threshold= 0.02
Energy Slope Method= 1
Volume Change Method= 0
XS Weighting Method= 0
Number of US Weighted Cross Sections= 1
Number of DS Weighted Cross Sections= 1
Upstream XS Weight=0.25
Main XS Weight=0.5
Downstream XS Weight=0.25
Number of DS XS's Weighted with US Boundary= 1
Upstream Boundary Weight= 1
Weight of XSs Associated with US Boundary= 0
Number of US XS's Weighted with DS Boundary= 1
Downstream Boundary Weight= 0.5
Weight of XSs Associated with DS Boundary= 0.5
Sediment Output Level= 4
Mass or Volume Output= 0
Output Increment Type= 1
Profile and TS Output Increment= 10
XS Output Flag= 0
XS Output Increment= 10
Disregard all LS=0
Disregard all Conn=0
Disregard all Breaches=0
Disregard all Pumps=0

--- LITTLE LAKE CREEK TRIB NO 2.f01 (steady flow) ---

Flow Title=Multiple
Program Version=4.10
Number of Profiles= 7
Profile Names=10-year,25-year,50-year,1pct_min,100-year,1pct_plu,500-year
River Rch & RM=LITTLE LAKE CREE,Reach-1         ,5875
     452     597     791     346    1044    3153    1878
Boundary for River Rch & Prof#=LITTLE LAKE CREE,Reach-1         , 1
Up Type= 0
Dn Type= 3
Dn Slope=0.035
Boundary for River Rch & Prof#=LITTLE LAKE CREE,Reach-1         , 2
Up Type= 0
Dn Type= 3
Dn Slope=0.035
Boundary for River Rch & Prof#=LITTLE LAKE CREE,Reach-1         , 3
Up Type= 0
Dn Type= 3
Dn Slope=0.035
Boundary for River Rch & Prof#=LITTLE LAKE CREE,Reach-1         , 4
Up Type= 0
Dn Type= 3
Dn Slope=0.035
Boundary for River Rch & Prof#=LITTLE LAKE CREE,Reach-1         , 5
Up Type= 0
Dn Type= 3
Dn Slope=0.035
Boundary for River Rch & Prof#=LITTLE LAKE CREE,Reach-1         , 6
Up Type= 0
Dn Type= 3
Dn Slope=0.035
Boundary for River Rch & Prof#=LITTLE LAKE CREE,Reach-1         , 7
Up Type= 0
Dn Type= 3
Dn Slope=0.035
DSS Import GetInterval= 0
DSS Import GetPeak= 0
DSS Import FillOption= 0

--- LITTLE LAKE CREEK TRIB NO 2.g01 (geometry) ---

Geom Title=Existing Conditions
Program Version=4.10

River Reach=LITTLE LAKE CREE,Reach-1
Reach XY= 30
      3764708.64     10155898.61        3764615.     10155799.07
      3764704.76      10155532.2      3764699.21     10155380.82
      3764900.62     10155269.35      3764972.17     10155158.06
      3765133.75     10155087.28      3765238.64      10155078.8
       3765215.2     10155142.13      3765264.48     10155175.01
      3765394.48     10155083.26      3765357.51     10154924.58
      3765414.63     10154847.28      3765265.57     10154633.31
      3765314.79     10154577.89      3765212.23     10154316.63
      3765280.41     10154174.63      3765358.96     10154137.34
      3765292.54     10153852.58      3765467.03     10153664.81
      3765487.56     10153395.83      3765644.16     10153307.88
      3765796.81     10153114.01      3765910.99      10152789.4
      3765909.31     10152680.84      3765575.93     10152127.18
      3765558.29     10151979.21      3765654.59     10151848.89
      3765627.77     10151703.05      3765752.86      10151593.8

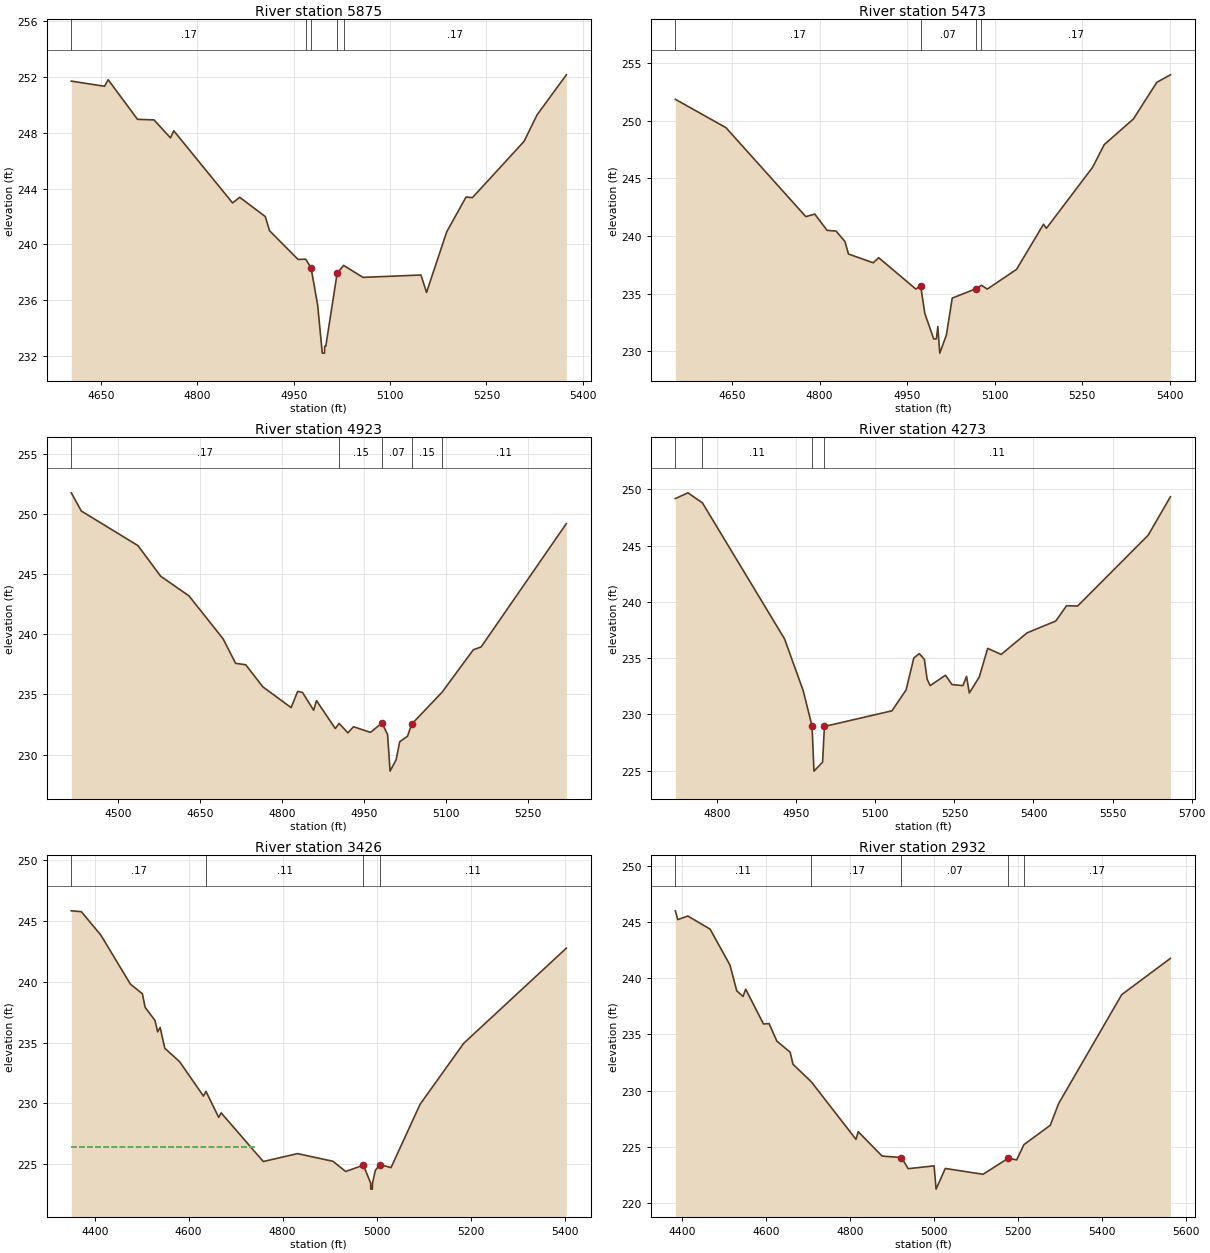
Type RM Length L Ch R = 1 ,5875    ,402,402,402
BEGIN DESCRIPTION:
LITTLE LAKE CREEK TRIB NO 2 1.0
END DESCRIPTION:
XS GIS Cut Line= 3
      3765064.14     10155786.18      3764675.41     10155862.74
       3764302.3     10155893.83
#Sta/Elev= 30
  4603.8  251.71  4655.5  251.34  4661.2  251.81  4706.9  248.97  4732.5  248.93
  4758.2  247.64  4763.3  248.15  4854.8  242.98    4866  243.38  4905.8     242
  4912.3  240.99  4956.7  238.93  4968.8  238.94  4977.1  238.31  4987.3  235.65
  4994.5  232.21    4998  232.21  4998.2  232.71    5000  232.71  5017.6  237.93
  5027.7   238.5  5057.8  237.64  5148.1  237.81  5156.8  236.56  5188.2  240.91
  5218.3   243.4  5228.3  243.36  5308.6  247.39  5328.7  249.28  5374.4  252.16
#Mann= 5 ,-1 , 0
  4603.8     .17       0  4968.8     .11       0  4977.1     .07       0
  5017.6     .11       0  5027.7     .17       0
Bank Sta=4977.1,5017.6
XS Rating Curve= 0 ,0
Exp/Cntr=0.3,0.1

Type RM Length L Ch R = 1 ,5473    ,550,550,550
BEGIN DESCRIPTION:
Mapping XS a443be7d
END DESCRIPTION:
XS GIS Cut Line= 3
      3765084.05     10155763.53      3764705.01     10155526.23
      3764304.61     10155504.18
#Sta/Elev= 30
  4552.8  251.84  4639.5  249.38  4776.3  241.67  4791.6  241.89  4812.8  240.48
  4828.1  240.42  4843.3  239.52  4849.4  238.43  4891.8  237.67  4901.2  238.11
  4964.9  235.39    4973   235.7  4980.2  233.29  4995.4  231.07    5000  231.07
  5002.5  232.14  5005.8  229.84  5017.2  231.41  5027.2  234.61  5067.3  235.41
  5077.3  235.72  5087.3  235.39  5137.4   237.1  5183.6  241.01  5188.6  240.66
  5267.6  245.94  5287.6  247.91  5337.7  250.14  5377.7  253.31    5401  253.96
#Mann= 4 ,-1 , 0
  4552.8     .17       0    4973     .07       0  5067.3     .11       0
  5077.3     .17       0
#XS Ineff= 2 , 0
       0  4901.2  238.11               0
Permanent Ineff=
       F       F
Bank Sta=4973,5067.3
XS Rating Curve= 0 ,0
Exp/Cntr=0.3,0.1

Type RM Length L Ch R = 1 ,4923    ,650,650,650
BEGIN DESCRIPTION:
LITTLE LAKE CREEK TRIB NO 2 2.0
END DESCRIPTION:
XS GIS Cut Line= 3
      3765111.98     10155738.73      3764956.23     10155173.81
      3764717.85     10154961.07
#Sta/Elev= 30
    4414  251.75  4432.3  250.24    4536  247.36  4577.5  244.82  4629.4  243.18
  4691.6  239.62  4714.6  237.58  4733.1  237.46  4764.3  235.63  4816.1   233.9
  4828.1  235.25  4836.9  235.16  4857.3  233.68  4862.5  234.48  4896.9  232.16
  4903.9  232.59  4919.9   231.8  4930.2  232.31  4961.3  231.84  4982.1  232.61
  4992.5  231.68  4997.1  228.62  5008.1  229.56  5014.8  231.07    5029  231.52
  5036.5  232.52  5092.4  235.19  5149.4  238.71  5163.6  238.94  5319.5  249.19
#Mann= 5 ,-1 , 0
    4414     .17       0  4903.9     .15       0  4982.1     .07       0
  5036.5     .15       0  5092.4     .11       0
#XS Ineff= 2 ,-1
  4828.1  4764.3  235.25  4862.5  4828.1  234.48
Permanent Ineff=
       F       F
Bank Sta=4982.1,5036.5
XS Rating Curve= 0 ,0
Exp/Cntr=0.3,0.1

Type RM Length L Ch R = 1 ,4273    ,847,847,847
BEGIN DESCRIPTION:
LITTLE LAKE CREEK TRIB NO 2 3.0
END DESCRIPTION:
XS GIS Cut Line= 3
      3765507.47     10155332.84      3765394.99      10155077.3
      3764757.83     10154906.34
#Sta/Elev= 30
  4720.8  249.18  4744.6  249.69  4772.1   248.8  4927.9  236.71  4963.1  232.13
    4980  228.98  4983.7  224.96    5000  225.76  5003.5  228.93  5131.6  230.32
  5158.3  232.17  5173.1  235.02  5183.4   235.4  5193.1  234.89  5198.3  233.13
  5204.1  232.56  5233.1  233.48  5245.5  232.65  5266.2  232.56  5273.1  233.38
  5278.3   231.9  5297.3  233.34  5313.1  235.87  5338.7  235.33    5388  237.25
  5442.3   238.3  5462.8  239.66  5483.7  239.63  5617.6  245.93  5659.7  249.34
#Mann= 4 ,-1 , 0
  4720.8     .17       0  4772.1     .11       0    4980     .06       0
  5003.5     .11       0
Bank Sta=4980,5003.5
XS Rating Curve= 0 ,0
Exp/Cntr=0.3,0.1

Type RM Length L Ch R = 1 ,3426    ,494,494,494
BEGIN DESCRIPTION:
LITTLE LAKE CREEK TRIB NO 2 4.0
END DESCRIPTION:
XS GIS Cut Line= 3
      3765867.82     10154611.06      3765247.61     10154417.21
      3764856.08       10154516.
#Sta/Elev= 30
  4350.2  245.84  4371.6  245.77    4413  243.85  4475.9  239.82  4501.6  239.02
  4507.3  237.91  4528.3  236.83    4534  235.89  4539.3  236.25  4549.2  234.54
  4580.7  233.44  4631.5  230.61  4636.8     231  4663.9  228.86  4669.2  229.23
  4758.8  225.23  4831.6  225.88    4907  225.25  4934.2  224.41  4971.9  224.93
  4987.3  223.46  4987.5  222.96    4991  222.96  4991.3  223.46  4997.3   224.5
 5006.88  224.98  5030.7  224.73  5092.6  229.94  5185.4  234.95  5403.8  242.77
#Mann= 4 ,-1 , 0
  4350.2     .17       0  4636.8     .11       0  4971.9     .07       0
 5006.88     .11       0
#XS Ineff= 2 , 0
       0  4739.4  226.44               0
Permanent Ineff=
       F       F
Bank Sta=4971.9,5006.88
XS Rating Curve= 0 ,0
Exp/Cntr=0.3,0.1

Type RM Length L Ch R = 1 ,2932    ,494,494,494
BEGIN DESCRIPTION:
LITTLE LAKE CREEK TRIB NO 2 5.0
END DESCRIPTION:
XS GIS Cut Line= 3
      3765915.93     10154218.74      3765333.92     10154015.71
      3764771.84     10154011.94
#Sta/Elev= 30
  4383.6     246  4389.3  245.22  4413.3  245.54  4466.3  244.37  4513.5  241.18
  4529.8  238.88  4544.6  238.38    4551  239.03  4593.4  235.93  4606.7  235.97
  4625.2  234.41  4656.9  233.42  4663.6  232.35  4707.4  230.78  4813.6  225.67
  4818.9  226.35  4875.8  224.18  4921.7  224.05  4937.9  223.06  4999.5  223.31
  5004.3  221.24  5026.1  223.08  5116.1  222.56  5176.1  223.99  5196.1  223.84
  5213.4   225.2  5276.1  226.92  5296.1  228.86  5446.1  238.54  5562.1  241.77
#Mann= 5 ,-1 , 0
  4383.6     .11       0  4707.4     .17       0  4921.7     .07       0
  5176.1     .11       0  5213.4     .17       0
Bank Sta=4921.7,5176.1
XS Rating Curve= 0 ,0
Exp/Cntr=0.3,0.1

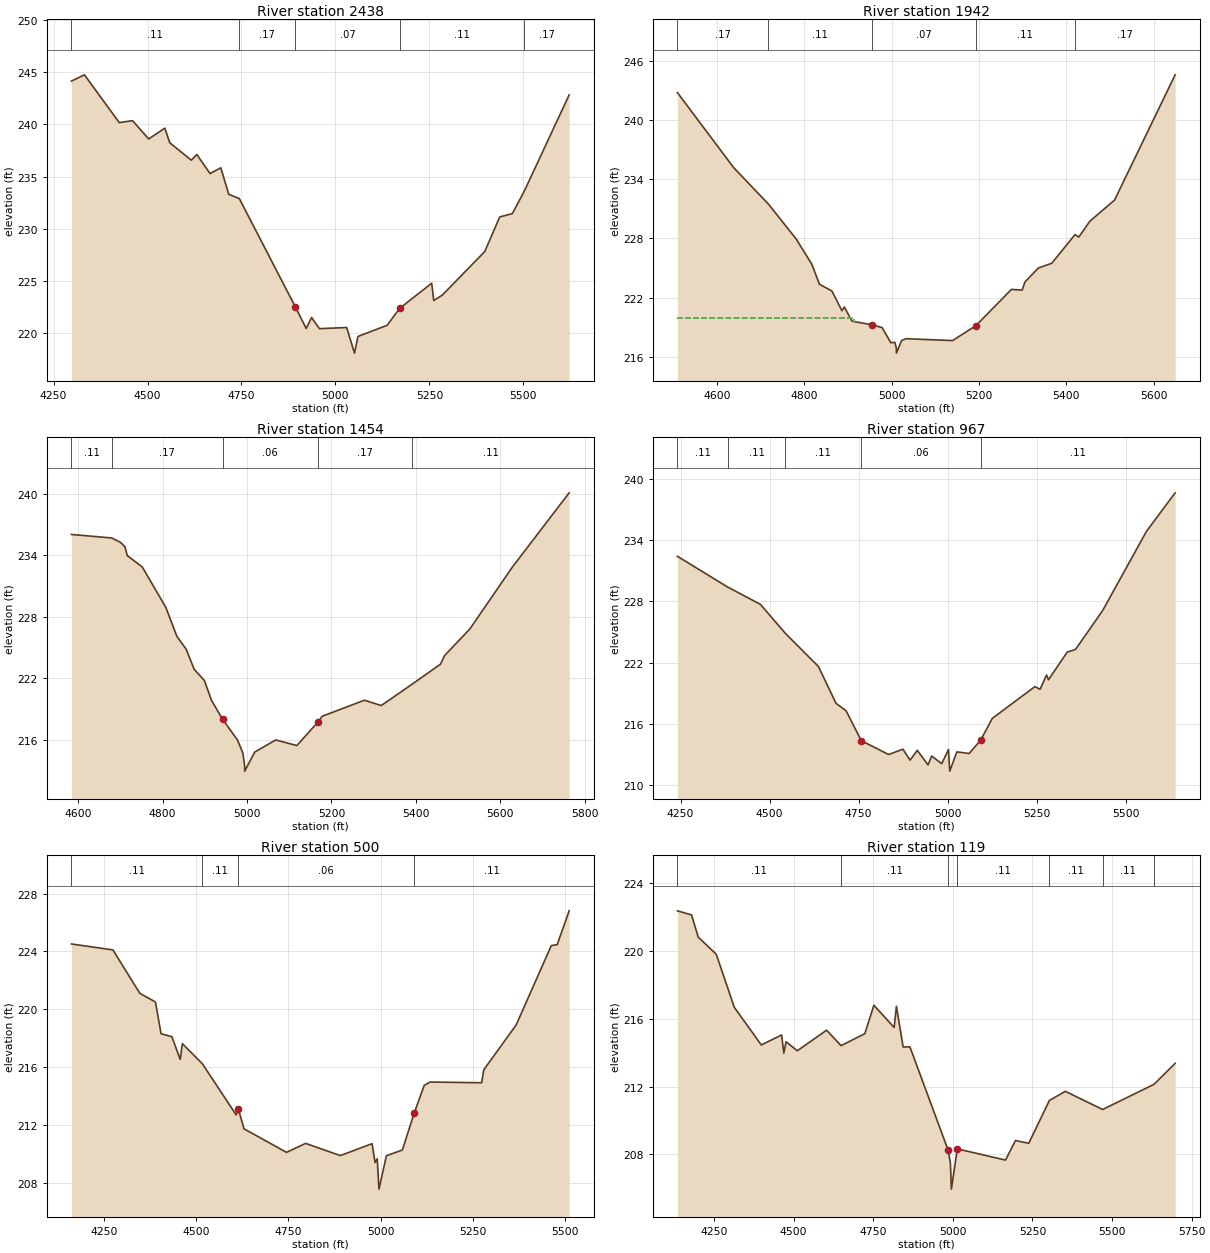
Type RM Length L Ch R = 1 ,2438    ,496,496,496
BEGIN DESCRIPTION:
LITTLE LAKE CREEK TRIB NO 2 6.0
END DESCRIPTION:
XS GIS Cut Line= 3
      3765913.35     10154164.48      3765471.95     10153617.97
      3764911.61      10153348.2
#Sta/Elev= 30
  4297.5  244.17  4332.1  244.77  4424.8  240.18    4460  240.37  4503.2  238.61
  4546.1  239.65  4559.2  238.24  4616.7  236.57  4631.1  237.12  4666.3  235.29
  4695.1  235.84  4715.9   233.3  4744.1  232.89  4893.4  222.48  4922.2  220.41
  4936.5  221.46  4957.4  220.39  5029.9   220.5  5050.7  218.04    5060  219.64
  5137.4  220.71  5171.2  222.35  5256.1  224.75  5261.7  223.09  5284.3  223.61
  5397.4   227.8  5437.1  231.12  5470.8  231.44  5501.9  233.55  5621.9  242.84
#Mann= 5 ,-1 , 0
  4297.5     .11       0  4744.1     .17       0  4893.4     .07       0
  5171.2     .11       0  5501.9     .17       0
Bank Sta=4893.4,5171.2
XS Rating Curve= 0 ,0
Exp/Cntr=0.3,0.1

Type RM Length L Ch R = 1 ,1942    ,488,488,488
BEGIN DESCRIPTION:
LITTLE LAKE CREEK TRIB NO 2 7.0
END DESCRIPTION:
XS GIS Cut Line= 3
      3766125.26     10153432.88      3765679.26     10153228.74
      3765067.85     10153011.07
#Sta/Elev= 30
  4509.5  242.76  4638.6  235.15    4718  231.47  4781.6  227.93  4817.1   225.4
  4834.7  223.36  4863.2  222.68  4886.2  220.68  4891.7  221.06  4909.2  219.62
  4955.2  219.26  4978.2  218.97    4998  217.45  5007.4  217.48  5010.7  216.89
  5010.9  216.39  5022.7  217.66  5032.9  217.85  5139.5  217.66  5192.6  219.16
  5274.2  222.84  5298.7  222.77  5305.1  223.59  5335.9  225.01  5366.7  225.49
  5419.7  228.39  5428.4  228.14  5453.9  229.75  5510.3  231.88    5649  244.56
#Mann= 5 ,-1 , 0
  4509.5     .17       0    4718     .11       0  4955.2     .07       0
  5192.6     .11       0  5419.7     .17       0
#XS Ineff= 2 , 0
       0  4914.7  219.99               0
Permanent Ineff=
       F       F
Bank Sta=4955.2,5192.6
XS Rating Curve= 0 ,0
Exp/Cntr=0.3,0.1

Type RM Length L Ch R = 1 ,1454    ,487,487,487
BEGIN DESCRIPTION:
LITTLE LAKE CREEK TRIB NO 2 8.0
END DESCRIPTION:
XS GIS Cut Line= 3
      3766311.42     10152905.55      3765905.97     10152813.36
      3765143.01      10152794.4
#Sta/Elev= 30
  4584.2  236.04  4679.6   235.7  4700.7  235.26  4710.9  234.84  4716.6  233.97
  4751.9  232.87  4807.9  228.91    4834  226.08    4856  224.83    4875  222.86
  4899.1  221.77    4916  219.83  4942.2  217.98  4977.6  215.95  4990.4  214.67
  4994.5  213.41  4994.7  212.91  5018.1  214.76  5068.1  215.96  5118.2  215.41
  5168.2  217.71  5178.2  218.27  5278.2  219.84  5318.2  219.32  5391.7  221.42
  5458.3  223.36  5468.3  224.21  5528.3  226.82  5628.3  232.83  5763.2  240.11
#Mann= 5 ,-1 , 0
  4584.2     .11       0  4679.6     .17       0  4942.2     .06       0
  5168.2     .17       0  5391.7     .11       0
Bank Sta=4942.2,5168.2
XS Rating Curve= 0 ,0
Exp/Cntr=0.3,0.1

Type RM Length L Ch R = 1 ,967     ,467,467,467
BEGIN DESCRIPTION:
LITTLE LAKE CREEK TRIB NO 2 9.0
END DESCRIPTION:
XS GIS Cut Line= 4
      3766347.58     10152760.77      3765962.44      10152414.4
       3765723.3      10152384.4      3765135.97      10152636.4
#Sta/Elev= 30
    4241  232.43  4381.7  229.42  4474.2  227.71  4544.3  224.86  4637.1  221.61
  4686.4     218  4714.9  217.26  4757.5  214.33  4834.2  212.97  4874.5  213.49
  4894.6  212.42  4914.8  213.38    4945  211.95  4955.1  212.82  4983.4  212.07
  5002.4  213.46    5006  211.34  5025.9  213.23  5060.4  213.07    5093  214.39
  5125.6  216.52  5245.3  219.64  5259.7  219.37  5277.9  220.78  5283.3  220.31
  5335.9  223.02  5359.4  223.29  5435.6  227.11  5558.8  234.89  5639.1  238.66
#Mann= 5 ,-1 , 0
    4241     .11       0  4381.7     .11       0  4544.3     .11       0
  4757.5     .06       0    5093     .11       0
Bank Sta=4757.5,5093
XS Rating Curve= 0 ,0
Exp/Cntr=0.3,0.1

Type RM Length L Ch R = 1 ,500     ,381,381,381
BEGIN DESCRIPTION:
Mapping XS d2c32261
END DESCRIPTION:
XS GIS Cut Line= 3
      3766268.81     10152425.59      3765558.29     10151979.21
      3765112.74     10152231.06
#Sta/Elev= 30
  4160.9  224.52  4273.5  224.11  4346.5  221.11  4388.9  220.51  4404.2  218.32
  4433.7  218.11  4456.1  216.54    4462  217.63  4516.1  216.25    4608  212.71
  4613.9  213.13  4629.2  211.75  4744.7  210.12  4796.5  210.74  4890.7   209.9
  4976.9  210.72    4985  209.42  4990.9  209.68  4995.6  207.58  5015.8  209.89
  5059.1  210.28  5090.9  212.81  5118.3  214.74  5134.2  214.98  5274.3  214.93
    5280  215.82  5368.1  218.93  5463.4  224.41  5479.3  224.47  5511.8  226.81
#Mann= 4 ,-1 , 0
  4160.9     .11       0  4516.1     .11       0  4613.9     .06       0
  5090.9     .11       0
Bank Sta=4613.9,5090.9
XS Rating Curve= 0 ,0
Exp/Cntr=0.3,0.1

Type RM Length L Ch R = 1 ,119     ,117,117,117
BEGIN DESCRIPTION:
LITTLE LAKE CREEK TRIB NO 2 10.0
END DESCRIPTION:
XS GIS Cut Line= 3
      3766272.26     10152269.31      3765656.21     10151661.96
       3764987.6     10151863.09
#Sta/Elev= 30
  4134.9  222.35  4179.2  222.11  4200.4   220.8    4257  219.79  4313.5  216.67
  4398.4  214.45  4462.1  215.04  4469.1  213.97  4476.2  214.64  4511.5  214.11
  4603.5  215.32    4649  214.41  4723.7  215.12    4752  216.79  4815.6  215.48
  4822.7  216.73  4843.9  214.33  4865.1  214.34  4985.3  208.25  4992.4  207.48
  4995.3  205.96  5014.1  208.33  5165.4  207.67  5196.7  208.82  5238.5  208.66
  5303.2  211.18  5353.3  211.72  5470.4  210.65  5631.7  212.13  5698.2  213.37
#Mann= 7 ,-1 , 0
  4134.9     .11       0    4649     .11       0  4985.3     .06       0
  5014.1     .11       0  5303.2     .11       0  5470.4     .11       0
  5631.7     .11       0
Bank Sta=4985.3,5014.1
XS Rating Curve= 0 ,0
Exp/Cntr=0.3,0.1

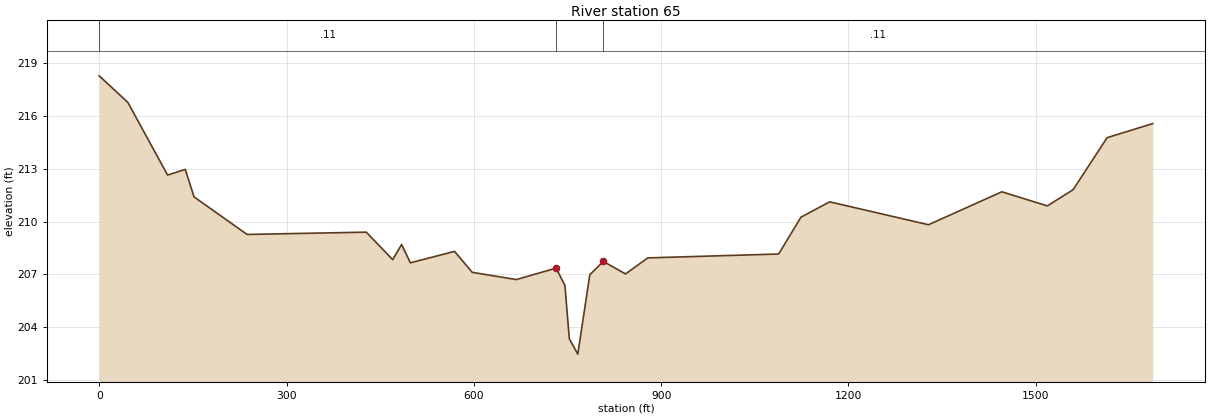
Type RM Length L Ch R = 1 ,65      ,0,0,0
XS GIS Cut Line= 3
      3766291.76     10152132.01      3765751.65      10151595.7
      3764854.26     10151824.72
#Sta/Elev= 30
       0  218.27    45.9  216.76   109.5  212.64   137.8  212.96   151.9   211.4
   236.8  209.27   427.7   209.4   470.1  207.84   484.3   208.7   498.4  207.66
   569.1  208.31   597.4  207.12   668.1  206.71   731.8  207.36   745.9  206.37
   752.9  203.35   766.5  202.48   785.7  206.98   807.3  207.74     843  207.03
   878.6  207.94  1088.2  208.16  1123.9  210.25  1169.9  211.12  1328.2  209.82
  1445.6  211.69  1518.5  210.89  1559.8  211.81  1614.2  214.76  1687.3  215.56
#Mann= 3 , 0 , 0
       0     .11       0   731.8     .06       0   807.3     .11       0
Bank Sta=731.8,807.3
XS Rating Curve= 0 ,0
Exp/Cntr=0.3,0.1

Chan Stop Cuts=-1
Use User Specified Reach Order=0
Composite Channel Slope=5