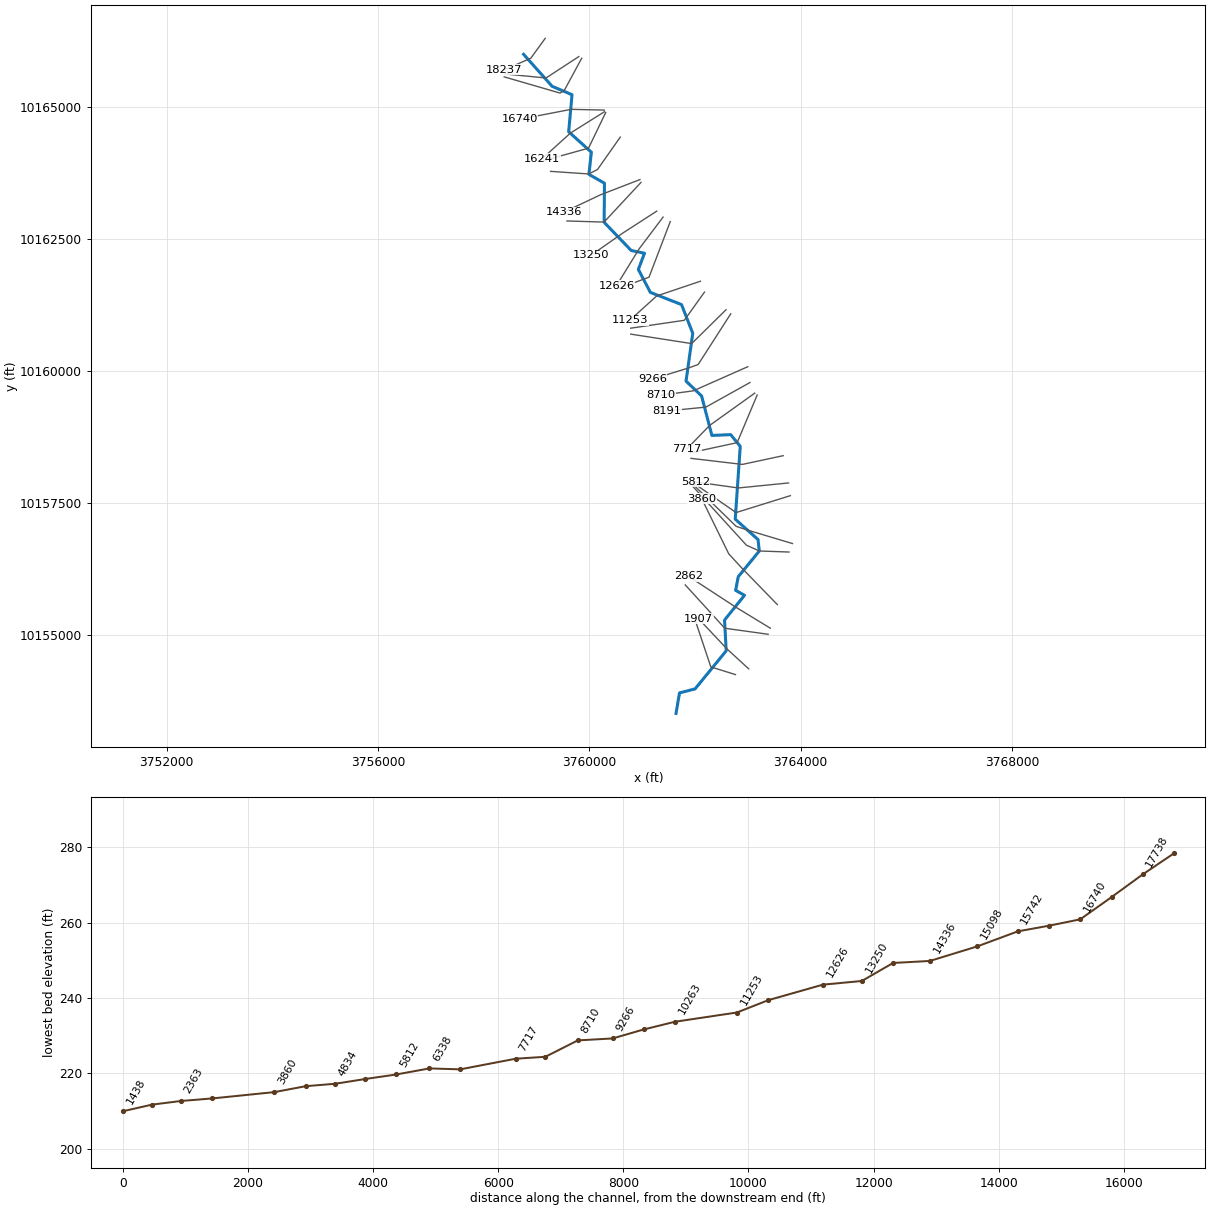
--- LITTLE LAKE CREEK TRIB NO 3.prj (project) ---

Proj Title=LITTLE LAKE CREEK TRIB NO 3 Base Level Engineering
Current Plan=p01
Default Exp/Contr=0.3,0.1
English Units
Geom File=g01
Flow File=f01
Flow File=f02
Plan File=p01
Y Axis Title=Elevation
X Axis Title(PF)=Main Channel Distance
X Axis Title(XS)=Station
BEGIN DESCRIPTION:
LITTLE LAKE CREEK TRIB NO 3
END DESCRIPTION:
DSS Export Rating Curves= 0
DSS Export Rating Curve Sorted= 0
DSS Export Volume Flow Curves= 0
DXF OffsetX= 0
DXF OffsetY= 0
DXF ScaleX= 1
DXF ScaleY= 10

--- LITTLE LAKE CREEK TRIB NO 3.p01 (plan) ---

Plan Title=Multiple Run
Short Identifier=Multiple
Geom File=g01
Flow File=f01
Subcritical Flow
K Sum by GR= 0
Std Step Tol= 0.01
Critical Tol= 0.01
Num of Std Step Trials= 20
Max Error Tol= 0.3
Flow Tol Ratio= 0.001
Split Flow NTrial= 30
Split Flow Tol= 0.02
Split Flow Ratio= 0.02
Log Output Level= 0
Friction Slope Method= 1
Unsteady Friction Slope Method= 2
Unsteady Bridges Friction Slope Method= 1
Parabolic Critical Depth
Global Vel Dist=  1 , 1 , 1
Global Log Level= 0
CheckData=True
Encroach Param= -1, 0, 0, 0
BEGIN DESCRIPTION:
Multiple Run
END DESCRIPTION:

--- LITTLE LAKE CREEK TRIB NO 3.f01 (steady flow) ---

Flow Title=Multiple
Program Version=4.10
Number of Profiles= 7
Profile Names=10-year,25-year,50-year,1pct_min,100-year,1pct_plu,500-year
River Rch & RM=LITTLE LAKE CREE,Reach-1         ,18237
     187     235     302     129     389    1175     662
River Rch & RM=LITTLE LAKE CREE,Reach-1         ,17240
     682     925    1252     558    1684    5086    3142
River Rch & RM=LITTLE LAKE CREE,Reach-1         ,8710
     791    1071    1447     641    1937    5850    3595
Boundary for River Rch & Prof#=LITTLE LAKE CREE,Reach-1         , 1
Up Type= 0
Dn Type= 3
Dn Slope=0.007
Boundary for River Rch & Prof#=LITTLE LAKE CREE,Reach-1         , 2
Up Type= 0
Dn Type= 3
Dn Slope=0.007
Boundary for River Rch & Prof#=LITTLE LAKE CREE,Reach-1         , 3
Up Type= 0
Dn Type= 3
Dn Slope=0.007
Boundary for River Rch & Prof#=LITTLE LAKE CREE,Reach-1         , 4
Up Type= 0
Dn Type= 3
Dn Slope=0.007
Boundary for River Rch & Prof#=LITTLE LAKE CREE,Reach-1         , 5
Up Type= 0
Dn Type= 3
Dn Slope=0.007
Boundary for River Rch & Prof#=LITTLE LAKE CREE,Reach-1         , 6
Up Type= 0
Dn Type= 3
Dn Slope=0.007
Boundary for River Rch & Prof#=LITTLE LAKE CREE,Reach-1         , 7
Up Type= 0
Dn Type= 3
Dn Slope=0.007
DSS Import GetInterval= 0
DSS Import GetPeak= 0
DSS Import FillOption= 0

--- LITTLE LAKE CREEK TRIB NO 3.f02 (steady flow) ---

Flow Title=Orig_BLE_Flow
Program Version=4.10
Number of Profiles= 7
Profile Names=10-year,25-year,50-year,1pct_min,100-year,1pct_plu,500-year
River Rch & RM=LITTLE LAKE CREE,Reach-1         ,18237
     187     230     263      99     299     904     385
River Rch & RM=LITTLE LAKE CREE,Reach-1         ,17240
     682     907    1089     429    1295    3909    1827
River Rch & RM=LITTLE LAKE CREE,Reach-1         ,8710
     791    1050    1258     494    1490    4501    2090
Boundary for River Rch & Prof#=LITTLE LAKE CREE,Reach-1         , 1
Up Type= 0
Dn Type= 3
Dn Slope=0.005
Boundary for River Rch & Prof#=LITTLE LAKE CREE,Reach-1         , 2
Up Type= 0
Dn Type= 3
Dn Slope=0.005
Boundary for River Rch & Prof#=LITTLE LAKE CREE,Reach-1         , 3
Up Type= 0
Dn Type= 3
Dn Slope=0.005
Boundary for River Rch & Prof#=LITTLE LAKE CREE,Reach-1         , 4
Up Type= 0
Dn Type= 3
Dn Slope=0.005
Boundary for River Rch & Prof#=LITTLE LAKE CREE,Reach-1         , 5
Up Type= 0
Dn Type= 3
Dn Slope=0.005
Boundary for River Rch & Prof#=LITTLE LAKE CREE,Reach-1         , 6
Up Type= 0
Dn Type= 3
Dn Slope=0.005
Boundary for River Rch & Prof#=LITTLE LAKE CREE,Reach-1         , 7
Up Type= 0
Dn Type= 3
Dn Slope=0.005
DSS Import GetInterval= 0
DSS Import GetPeak= 0
DSS Import FillOption= 0

--- LITTLE LAKE CREEK TRIB NO 3.g01 (geometry) ---

Geom Title=Existing Conditions
Program Version=4.10

River Reach=LITTLE LAKE CREE,Reach-1
Reach XY= 30
      3758756.21      10165995.7      3759294.68     10165391.36
      3759672.41      10165231.7      3759609.21     10164530.01
      3760038.02     10164143.59      3759992.14      10163723.7
      3760286.41     10163556.24      3760280.67     10162815.98
      3760793.51     10162281.82      3761044.26     10162230.05
      3760928.41     10161922.89      3761156.33      10161488.4
      3761745.16     10161258.39      3761958.25     10160714.67
      3761831.15     10159808.87       3762125.7     10159527.63
      3762320.34     10158780.68       3762676.6     10158795.38
      3762857.42     10158573.36       3762762.7     10157194.83
      3763194.24     10156810.06      3763217.37     10156591.03
      3762820.54     10156106.85      3762769.51     10155848.17
       3762937.8     10155753.12      3762559.97     10155285.19
      3762591.52     10154702.33      3762002.42     10153981.74
      3761707.47     10153906.16      3761641.68     10153518.23

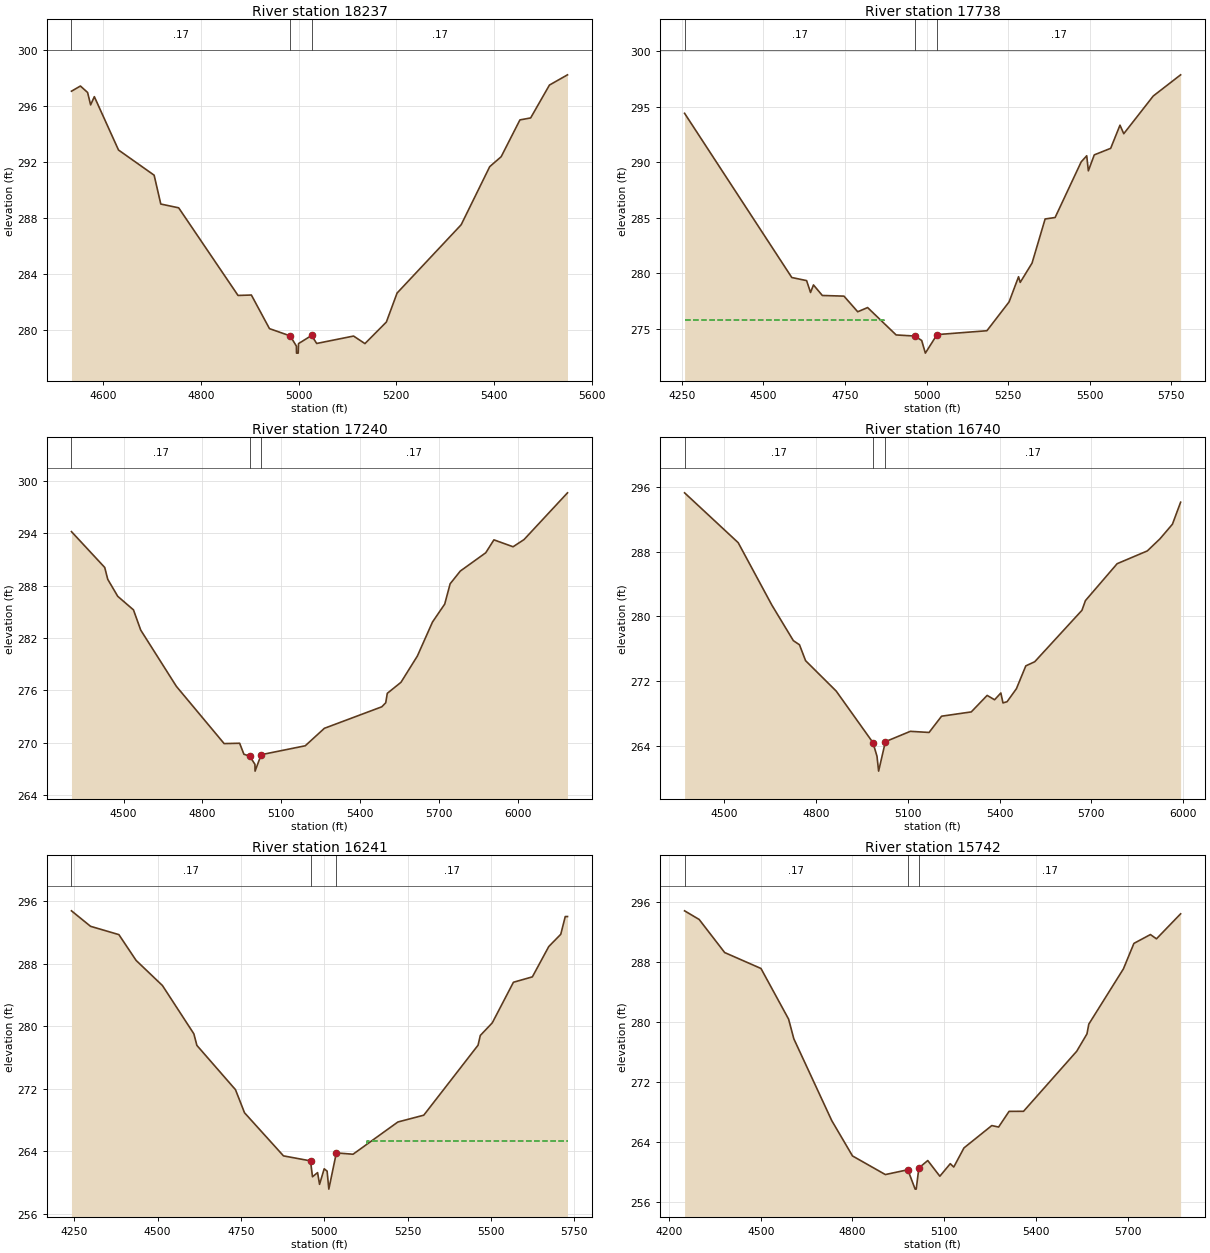
Type RM Length L Ch R = 1 ,18237   ,499,499,499
BEGIN DESCRIPTION:
LITTLE LAKE CREEK TRIB NO 3 34.0
END DESCRIPTION:
XS GIS Cut Line= 3
        3759165.     10166298.96      3758892.35     10165923.03
       3758388.8      10165701.3
#Sta/Elev= 30
  4535.6  297.08  4553.9  297.45  4568.6  296.99  4574.8   296.1  4582.4  296.69
  4631.8  292.88  4704.7  291.08  4718.3  289.02  4754.9  288.75  4876.3  282.49
  4903.6  282.52  4940.6  280.12    4983   279.6  4995.7  278.87  4995.9  278.37
  4999.4  278.37    5000  279.05  5026.8  279.63  5037.2  279.06  5112.6  279.59
  5135.9  279.05  5179.7  280.59  5201.6  282.66  5332.7  287.54  5391.1  291.69
  5414.5   292.4  5452.9  295.03  5474.8  295.17  5513.3  297.52  5550.2  298.25
#Mann= 3 ,-1 , 0
  4535.6     .17       0    4983     .09       0  5026.8     .17       0
Bank Sta=4983,5026.8
XS Rating Curve= 0 ,0
Exp/Cntr=0.3,0.1

Type RM Length L Ch R = 1 ,17738   ,498,498,498
BEGIN DESCRIPTION:
LITTLE LAKE CREEK TRIB NO 3 33.0
END DESCRIPTION:
XS GIS Cut Line= 3
      3759801.51     10165953.57        3759180.     10165548.43
      3758404.34     10165623.69
#Sta/Elev= 30
  4258.1  294.42  4586.9  279.61  4632.3  279.33  4644.4  278.26  4653.4  278.94
  4680.5  277.99  4746.9  277.93  4789.1  276.52  4819.4   276.9  4906.9  274.43
  4964.2  274.33  4985.3  273.93  4996.5  272.79  5032.3  274.46  5185.3  274.81
  5253.3  277.41  5282.3  279.68  5287.4  279.17  5323.7  280.91  5363.8  284.89
  5394.4  285.02  5474.4  290.04  5491.4  290.59  5496.4  289.23  5514.5  290.67
  5564.8  291.26  5593.4  293.35    5605  292.58  5695.4  295.98  5779.3  297.89
#Mann= 3 ,-1 , 0
  4258.1     .17       0  4964.2     .09       0  5032.3     .17       0
#XS Ineff= 2 , 0
       0  4870.7  275.77               0
Permanent Ineff=
       F       F
Bank Sta=4964.2,5032.3
XS Rating Curve= 0 ,0
Exp/Cntr=0.3,0.1

Type RM Length L Ch R = 1 ,17240   ,500,500,500
BEGIN DESCRIPTION:
LITTLE LAKE CREEK TRIB NO 3 32.0
END DESCRIPTION:
XS GIS Cut Line= 4
      3759855.85     10165922.51      3759523.48     10165307.92
      3759444.47     10165262.75      3758388.81     10165569.36
#Sta/Elev= 30
  4301.3  294.17    4428  290.07  4439.4  288.72  4477.5  286.77  4537.4  285.22
    4565  282.91  4700.8  276.47  4882.7  269.92  4941.8  269.96    4958   268.7
  4979.8  268.49    5000  267.55  5000.5  266.77  5023.8  268.65  5191.6  269.67
  5264.5  271.67  5483.2  274.13  5498.1  274.59    5504  275.67  5556.1  276.93
  5618.6  279.94  5676.2  283.83  5722.7  285.88  5743.3   288.2  5782.1  289.66
  5878.9  291.75  5910.1  293.23    5983  292.44  6024.7  293.26  6190.3  298.61
#Mann= 3 ,-1 , 0
  4301.3     .17       0  4979.8     .09       0  5023.8     .17       0
#XS Ineff= 2 , 0
       0                  5274.9       0  271.75
Permanent Ineff=
       F       F
Bank Sta=4979.8,5023.8
XS Rating Curve= 0 ,0
Exp/Cntr=0.3,0.1

Type RM Length L Ch R = 1 ,16740   ,499,499,499
BEGIN DESCRIPTION:
LITTLE LAKE CREEK TRIB NO 3 31.0
END DESCRIPTION:
XS GIS Cut Line= 3
      3760282.81     10164940.62      3759654.77     10164954.58
      3758681.61     10164766.31
#Sta/Elev= 30
  4371.8  295.28  4546.8  289.12  4656.8   281.4  4726.9  277.01  4746.9   276.5
  4766.9  274.53  4866.9  270.77  4986.9   264.4    5000  262.71  5005.3  260.88
  5027.4  264.52  5108.9   265.8    5170  265.66  5210.8  267.67  5307.8   268.2
  5359.6  270.24  5383.9   269.7  5404.3  270.54  5411.3  269.31  5424.6  269.46
  5455.2  271.07  5485.8  273.89  5514.9   274.4  5669.1  280.76  5680.5  281.96
    5784  286.52  5882.5   288.1  5923.7  289.59  5964.5   291.4  5991.2  294.12
#Mann= 3 ,-1 , 0
  4371.8     .17       0  4986.9     .09       0  5027.4     .17       0
Bank Sta=4986.9,5027.4
XS Rating Curve= 0 ,0
Exp/Cntr=0.3,0.1

Type RM Length L Ch R = 1 ,16241   ,499,499,499
BEGIN DESCRIPTION:
LITTLE LAKE CREEK TRIB NO 3 30.0
END DESCRIPTION:
XS GIS Cut Line= 3
      3760286.63     10164909.56      3759644.39     10164506.57
      3759102.94     10164016.94
#Sta/Elev= 30
  4241.8  294.76  4299.1  292.78    4384  291.72  4435.8  288.42  4514.8  285.21
    4609  279.04  4618.1  277.56  4733.9   271.9    4761  268.95  4877.9  263.44
    4959   262.8  4964.9  260.77  4980.2   261.3  4986.1   259.8    5000  261.79
  5008.8  261.49  5013.9  259.19  5036.5  263.82  5086.6  263.65  5221.1  267.77
  5298.8  268.64  5461.7  277.59  5468.4  278.83  5504.3  280.44  5567.8  285.63
  5624.6  286.32  5673.9   290.2  5709.8  291.76  5723.3  294.03    5730  294.03
#Mann= 3 ,-1 , 0
  4241.8     .17       0    4959     .09       0  5036.5     .17       0
#XS Ineff= 2 , 0
       0                  5129.2       0  265.29
Permanent Ineff=
       F       F
Bank Sta=4959,5036.5
XS Rating Curve= 0 ,0
Exp/Cntr=0.3,0.1

Type RM Length L Ch R = 1 ,15742   ,644,644,644
BEGIN DESCRIPTION:
LITTLE LAKE CREEK TRIB NO 3 29.0
END DESCRIPTION:
XS GIS Cut Line= 3
      3760309.95     10164894.07      3759984.61     10164219.31
       3759142.6     10163986.12
#Sta/Elev= 30
  4250.9  294.77  4298.6  293.62  4382.1  289.21  4500.8  287.09  4591.2  280.34
  4608.3  277.72  4732.4  266.82  4800.3  262.11  4907.8  259.63  4981.2  260.27
  5005.2  257.69  5008.7  257.69  5017.4  260.51  5046.5   261.5    5086  259.41
  5120.2  261.08  5131.5  260.63  5164.9  263.18    5256  266.16  5278.2  265.96
  5312.5  268.05  5359.8  268.06  5533.8  276.06  5567.3  278.37  5573.3  279.67
  5686.6  287.04  5720.9  290.43  5774.9  291.61  5794.7  291.04  5873.7  294.37
#Mann= 3 ,-1 , 0
  4250.9     .17       0  4981.2     .09       0  5017.4     .17       0
#XS Ineff= 2 , 0
       0                  5164.9       0  263.18
Permanent Ineff=
       F       F
Bank Sta=4981.2,5017.4
XS Rating Curve= 0 ,0
Exp/Cntr=0.3,0.1

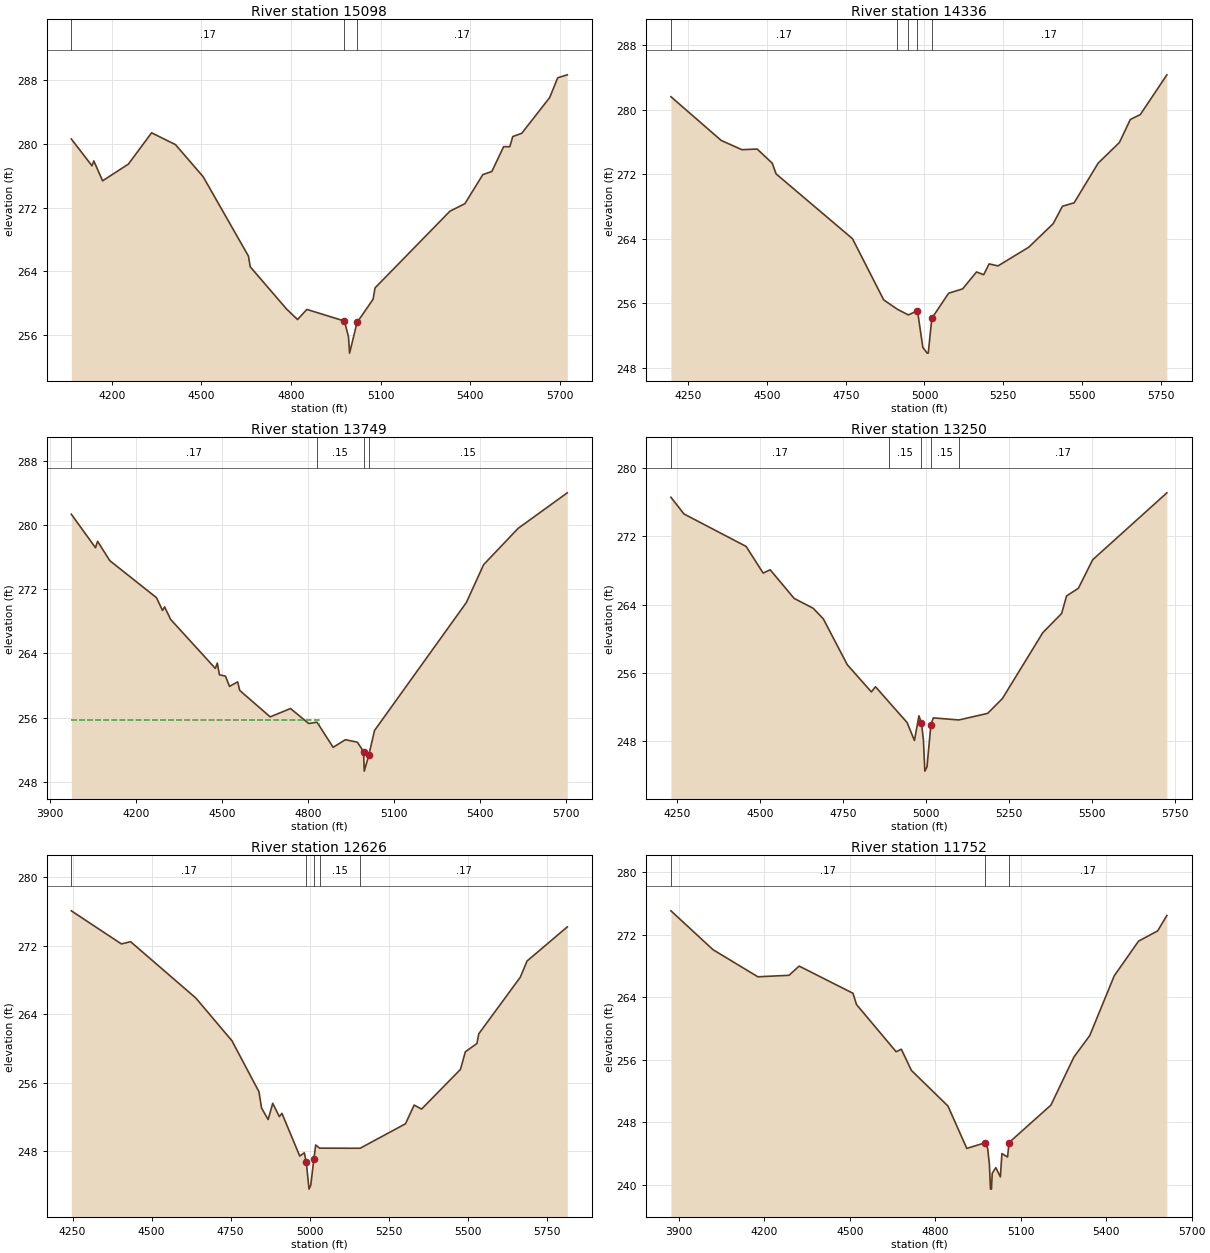
Type RM Length L Ch R = 1 ,15098   ,762,762,762
BEGIN DESCRIPTION:
LITTLE LAKE CREEK TRIB NO 3 28.0
END DESCRIPTION:
XS GIS Cut Line= 4
      3760585.48      10164428.3       3760154.7     10163815.12
      3759988.83     10163731.14      3759265.89     10163780.19
#Sta/Elev= 30
  4064.7  280.61  4133.7  277.25  4139.8  277.86  4169.4  275.36  4255.7  277.46
  4333.3  281.39  4413.4   279.9  4505.8  275.88  4657.4  265.91  4663.5  264.56
  4785.5  259.24  4821.8  257.94    4853  259.21  4978.7  257.75  4992.3  255.77
    4996  253.72    5021  257.57  5074.5  260.48  5081.2  261.91  5331.7  271.54
  5381.9  272.49    5442  276.14  5472.1  276.53  5511.6  279.65  5532.2  279.64
  5542.2  280.92  5572.3  281.33  5665.6  285.81  5692.6   288.3  5724.6  288.67
#Mann= 3 ,-1 , 0
  4064.7     .17       0  4978.7     .09       0    5021     .17       0
Bank Sta=4978.7,5021
XS Rating Curve= 0 ,0
Exp/Cntr=0.3,0.1

Type RM Length L Ch R = 1 ,14336   ,587,587,587
BEGIN DESCRIPTION:
LITTLE LAKE CREEK TRIB NO 3 27.0
END DESCRIPTION:
XS GIS Cut Line= 3
      3760958.07     10163624.94      3760207.14     10163334.61
      3759511.68     10163004.56
#Sta/Elev= 30
  4194.9  281.59  4354.4  276.18  4420.3  275.03  4468.8  275.11  4516.8  273.35
  4528.7  272.04  4771.4  264.01  4870.6  256.43  4913.2  255.29  4948.8  254.57
  4977.8  255.09  4994.9  250.55  5008.5  249.84    5012  249.84  5023.4  254.15
  5076.7  257.26    5121  257.79  5165.3  259.89  5188.1  259.55  5205.2  260.89
  5233.5  260.64  5331.3  262.96  5408.8  265.87  5438.1  268.03  5475.2  268.45
  5551.7  273.37  5619.1  275.92  5653.7  278.77  5685.5  279.38  5769.8   284.3
#Mann= 5 ,-1 , 0
  4194.9     .17       0  4913.2     .15       0  4948.8     .17       0
  4977.8     .09       0  5023.4     .17       0
Bank Sta=4977.8,5023.4
XS Rating Curve= 0 ,0
Exp/Cntr=0.3,0.1

Type RM Length L Ch R = 1 ,13749   ,499,499,499
BEGIN DESCRIPTION:
LITTLE LAKE CREEK TRIB NO 3 26.0
END DESCRIPTION:
XS GIS Cut Line= 3
      3760977.47      10163570.6      3760279.23     10162820.07
      3759576.44     10162840.97
#Sta/Elev= 30
  3974.9  281.36  4059.1  277.18  4066.4  277.98  4108.9  275.57  4271.6  270.95
  4292.6  269.36  4299.9   269.8  4320.9  268.24  4476.8  262.12  4483.6  262.79
    4491  261.33    4512  261.16  4526.2  259.88  4554.5  260.45  4561.6  259.38
  4667.8  256.08  4738.7  257.12  4802.2  255.25    4831  255.42  4887.2  252.28
  4929.7  253.23  4971.7  252.92  4993.2  251.75  4995.6  249.31  5011.4  251.29
  5031.4  254.38  5351.5  270.35  5411.6  275.07  5531.6  279.59  5703.1  284.03
#Mann= 4 ,-1 , 0
  3974.9     .17       0    4831     .15       0  4993.2     .09       0
  5011.4     .15       0
#XS Ineff= 2 , 0
       0  4837.4   255.7               0
Permanent Ineff=
       F       F
Bank Sta=4993.2,5011.4
XS Rating Curve= 0 ,0
Exp/Cntr=0.3,0.1

Type RM Length L Ch R = 1 ,13250   ,624,624,624
BEGIN DESCRIPTION:
LITTLE LAKE CREEK TRIB NO 3 25.0
END DESCRIPTION:
XS GIS Cut Line= 3
      3761276.32     10163027.26       3760629.8     10162609.41
      3760034.36     10162192.82
#Sta/Elev= 30
  4230.2  276.53  4269.6  274.58    4457  270.79  4508.5  267.67  4529.6  268.06
  4602.1  264.71  4659.5  263.56  4689.9  262.33  4762.4  256.96    4835  253.79
  4847.5  254.39  4887.5  252.63  4942.8  250.21    4965  248.11  4978.5  250.99
  4986.1  250.17    4992  248.22  4996.4  244.53  5002.9  245.03  5014.6  249.96
    5022  250.75  5099.2  250.51  5185.9  251.28  5230.4  253.01  5352.5  260.72
  5409.1  262.95    5424     265  5459.7   265.9  5502.8  269.23  5726.7  277.05
#Mann= 5 ,-1 , 0
  4230.2     .17       0  4887.5     .15       0  4986.1     .09       0
  5014.6     .15       0  5099.2     .17       0
Bank Sta=4986.1,5014.6
XS Rating Curve= 0 ,0
Exp/Cntr=0.3,0.1

Type RM Length L Ch R = 1 ,12626   ,874,874,874
BEGIN DESCRIPTION:
LITTLE LAKE CREEK TRIB NO 3 24.0
END DESCRIPTION:
XS GIS Cut Line= 3
      3761396.61     10162914.68      3760942.81     10162312.78
      3760515.65     10161618.46
#Sta/Elev= 30
  4246.2  276.09  4404.6  272.22  4433.7  272.48  4639.9   265.9  4754.3   260.9
  4839.7  254.94    4848  253.03  4868.8  251.69  4883.4  253.58  4904.2  252.03
  4912.5  252.41  4968.8  247.42  4983.3   247.8  4989.6  246.68  4998.2  243.55
  5003.9  244.05  5013.4  247.06  5019.3  248.71  5031.6  248.34  5159.9  248.33
  5303.3  251.19  5330.8  253.38  5354.2  252.91  5477.3  257.55  5492.7  259.61
  5529.4  260.58  5535.2  261.71  5666.6  268.33  5687.9  270.22  5815.2  274.21
#Mann= 5 ,-1 , 0
  4246.2     .17       0  4989.6     .09       0  5013.4     .17       0
  5031.6     .15       0  5159.9     .17       0
Bank Sta=4989.6,5013.4
XS Rating Curve= 0 ,0
Exp/Cntr=0.3,0.1

Type RM Length L Ch R = 1 ,11752   ,499,499,499
BEGIN DESCRIPTION:
LITTLE LAKE CREEK TRIB NO 3 23.0
END DESCRIPTION:
XS GIS Cut Line= 3
      3761532.47     10162829.31       3761129.7     10161775.98
      3760554.48     10161564.12
#Sta/Elev= 30
  3872.3  275.04  4020.3  270.06  4177.4   266.6  4286.9  266.79  4322.3  267.97
  4511.3  264.49  4523.5  263.06  4662.7  257.01    4681  257.33  4716.4  254.62
  4844.7  250.06  4910.7  244.64  4973.1  245.34  4983.8  244.69  4990.2  242.57
  4993.8  239.43  4997.3  239.43    5000  241.45  5012.6  242.18  5028.6     241
    5034  243.98  5053.8  243.54  5059.1  245.39    5206  250.18  5286.7  256.33
  5342.3  259.08  5428.2  266.72  5513.5  271.16  5580.6  272.47    5613  274.45
#Mann= 3 ,-1 , 0
  3872.3     .17       0  4973.1     .09       0  5059.1     .17       0
Bank Sta=4973.1,5059.1
XS Rating Curve= 0 ,0
Exp/Cntr=0.3,0.1

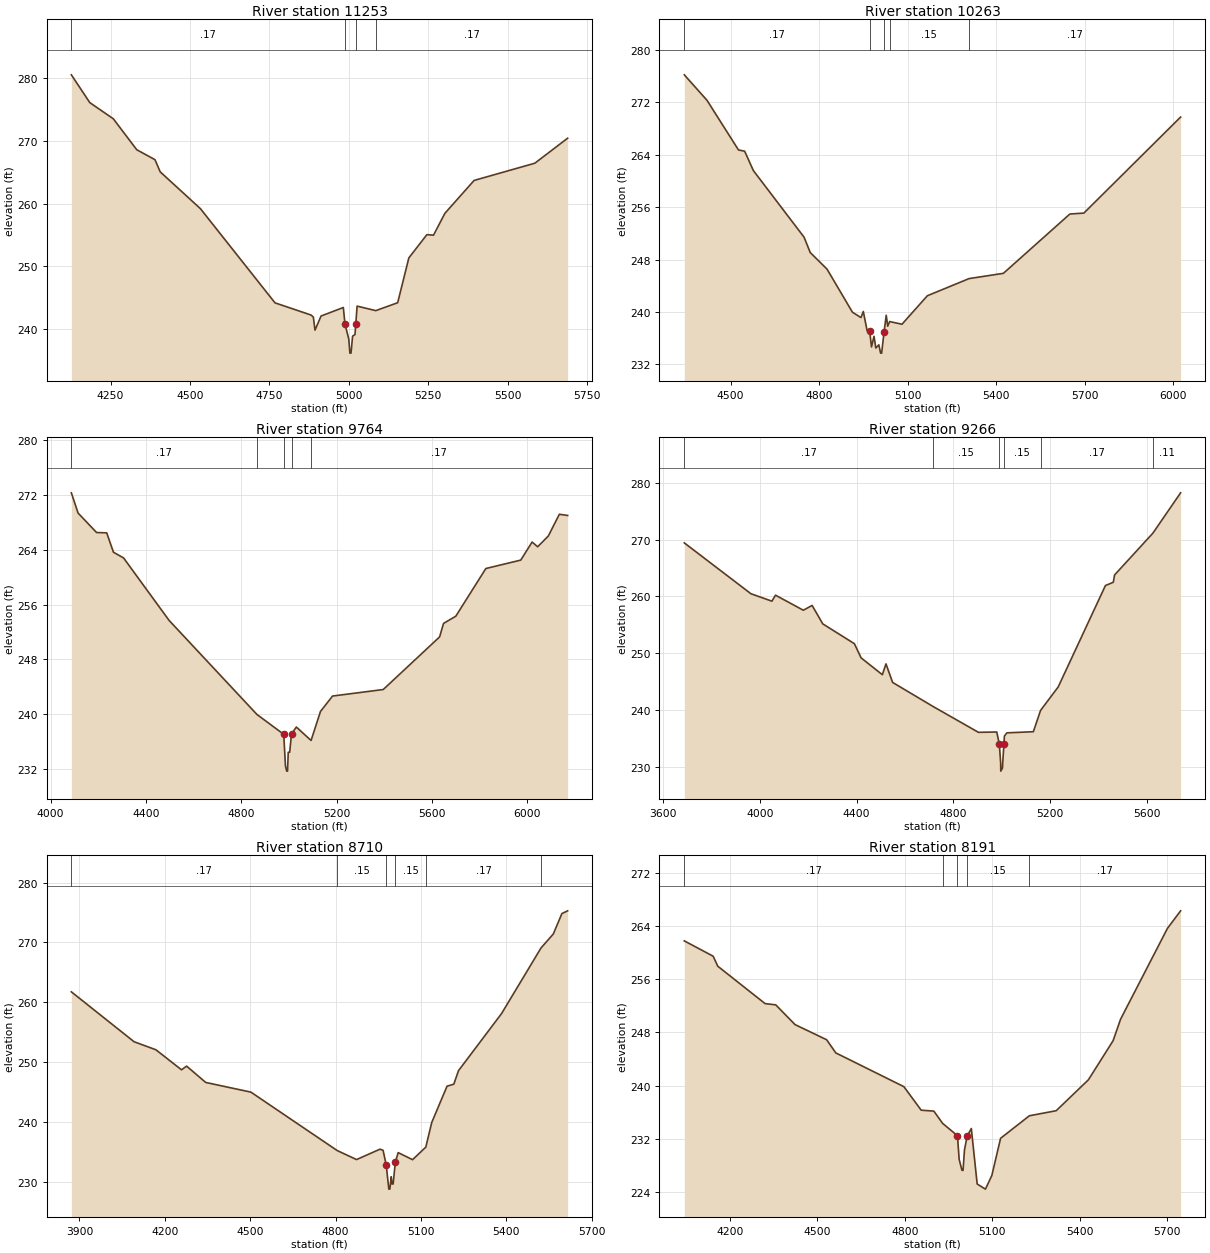
Type RM Length L Ch R = 1 ,11253   ,990,990,990
BEGIN DESCRIPTION:
LITTLE LAKE CREEK TRIB NO 3 22.0
END DESCRIPTION:
XS GIS Cut Line= 3
      3762103.02     10161699.95      3761275.13     10161421.08
      3760764.06     10160958.69
#Sta/Elev= 30
  4126.4  280.57  4184.6  276.13  4258.5  273.56  4332.3  268.62  4389.8  267.03
  4406.2  265.09  4532.8  259.22  4767.7  244.19  4881.1  242.25  4888.4  241.92
  4893.6  239.84  4912.7  242.09  4982.8  243.45  4988.1  240.79    5000  238.41
  5003.5  236.17    5007  236.17    5012  238.88  5019.5  239.13 5022.14  240.88
  5026.2  243.67    5085  242.95    5154  244.21  5189.1  251.36  5245.9  255.07
  5266.8  254.99  5302.7  258.48  5394.6  263.72  5585.9  266.47  5689.2  270.46
#Mann= 4 ,-1 , 0
  4126.4     .17       0  4988.1     .09       0 5022.14     .15       0
    5085     .17       0
Bank Sta=4988.1,5022.14
XS Rating Curve= 0 ,0
Exp/Cntr=0.3,0.1

Type RM Length L Ch R = 1 ,10263   ,499,499,499
BEGIN DESCRIPTION:
LITTLE LAKE CREEK TRIB NO 3 20.0
END DESCRIPTION:
XS GIS Cut Line= 3
      3762180.64     10161494.28      3761798.06     10160960.41
      3760783.47     10160811.19
#Sta/Elev= 30
  4343.2  276.21    4420  272.33  4526.9  264.74  4547.8  264.55  4577.2   261.6
  4749.2  251.42  4770.1  249.08    4827  246.55  4913.1  239.97    4942  239.15
    4950  240.08  4962.9  237.15  4971.5  237.08  4977.7  234.67  4986.3  236.29
  4992.4   234.5  5002.6  234.99  5008.6  233.72  5012.1  233.72  5020.4  236.98
  5027.7   239.5  5032.7  237.83  5039.3  238.54  5081.1  238.13  5167.1  242.48
  5308.5   245.1  5424.7   245.9  5650.2  254.96  5697.6   255.1  6025.5  269.76
#Mann= 5 ,-1 , 0
  4343.2     .17       0  4971.5     .09       0  5020.4     .17       0
  5039.3     .15       0  5308.5     .17       0
#XS Ineff= 2 , 0
       0                  5172.2       0  242.48
Permanent Ineff=
       F       F
Bank Sta=4971.5,5020.4
XS Rating Curve= 0 ,0
Exp/Cntr=0.3,0.1

Type RM Length L Ch R = 1 ,9764    ,498,498,498
BEGIN DESCRIPTION:
LITTLE LAKE CREEK TRIB NO 3 19.0
END DESCRIPTION:
XS GIS Cut Line= 3
      3762588.12     10161160.48      3761938.15     10160519.44
      3760783.47     10160698.62
#Sta/Elev= 30
  4087.1  272.33  4115.2  269.38  4192.9  266.53  4235.4  266.48  4263.7  263.65
  4306.1  262.82    4497  253.69  4865.4  239.95  4977.8  237.05    4985  232.43
  4990.2  231.67  4993.7  231.67  4996.7  234.43  5002.7  234.43  5010.4   237.1
  5030.7  238.11  5092.4  236.15  5131.9  240.39  5182.5  242.64    5395  243.59
  5631.5  251.28    5648  253.25  5699.5  254.31  5825.4  261.27  5971.8   262.5
  6019.4  265.14  6042.6  264.45  6087.4  266.02  6133.7   269.2  6168.5  269.02
#Mann= 5 ,-1 , 0
  4087.1     .17       0  4865.4     .15       0  4977.8     .09       0
  5010.4     .15       0  5092.4     .17       0
Bank Sta=4977.8,5010.4
XS Rating Curve= 0 ,0
Exp/Cntr=0.3,0.1

Type RM Length L Ch R = 1 ,9266    ,556,556,556
BEGIN DESCRIPTION:
LITTLE LAKE CREEK TRIB NO 3 18.0
END DESCRIPTION:
XS GIS Cut Line= 4
       3762677.4     10161082.88      3762060.68     10160123.45
      3761898.64     10160064.71      3761191.88     10159845.09
#Sta/Elev= 30
  3687.1  269.42  3962.7  260.48  4049.4  259.17  4064.5  260.22  4179.5  257.58
  4215.8  258.42  4259.9  255.18  4390.6   251.7  4418.6   249.2  4506.4  246.24
  4521.4  248.15  4548.7  244.89  4717.6  240.62  4903.9  236.11  4979.6  236.17
  4990.2  234.06  4995.8  230.69  4996.2  229.29    5003  229.79 5009.25   234.1
  5011.3  235.47  5021.8  236.02    5131  236.22  5160.8  239.96  5233.9   244.1
  5429.2  261.92  5461.6  262.49    5467  263.78  5625.9  271.15  5740.1  278.22
#Mann= 6 ,-1 , 0
  3687.1     .17       0  4717.6     .15       0  4990.2     .09       0
 5009.25     .15       0  5160.8     .17       0  5625.9     .11       0
Bank Sta=4990.2,5009.25
XS Rating Curve= 0 ,0
Exp/Cntr=0.3,0.1

Type RM Length L Ch R = 1 ,8710    ,519,519,519
BEGIN DESCRIPTION:
LITTLE LAKE CREEK TRIB NO 3 17.0
END DESCRIPTION:
XS GIS Cut Line= 3
      3762999.52     10160081.54      3761967.87      10159624.9
      3761357.87     10159542.08
#Sta/Elev= 30
  3871.8  261.74  4092.3   253.4  4168.9  252.06  4258.9  248.71  4276.7  249.33
  4343.9   246.6  4502.7  244.98  4805.8  235.22  4873.9  233.71  4956.3  235.45
  4967.1  235.26  4978.1  232.82  4987.3  228.77  4990.8  228.77  4995.8  230.84
  4998.5  229.63  5002.5  229.63  5010.1   233.3  5020.2  234.87  5070.7  233.69
  5117.2  235.79  5138.1  239.91  5191.8  245.97  5215.6  246.31  5232.1  248.57
  5383.5  258.12  5522.1  269.08  5565.2  271.41  5595.4  274.82  5615.6  275.28
#Mann= 6 ,-1 , 0
  3871.8     .17       0  4805.8     .15       0  4978.1     .09       0
  5010.1     .15       0  5117.2     .17       0  5522.1     .11       0
Bank Sta=4978.1,5010.1
XS Rating Curve= 0 ,0
Exp/Cntr=0.3,0.1

Type RM Length L Ch R = 1 ,8191    ,474,474,474
BEGIN DESCRIPTION:
LITTLE LAKE CREEK TRIB NO 3 16.0
END DESCRIPTION:
XS GIS Cut Line= 3
      3763042.24     10159782.72      3762206.14     10159316.71
      3761462.76     10159243.25
#Sta/Elev= 30
  4042.8  261.78  4141.9  259.47  4157.9  257.96  4320.2  252.34  4356.9  252.15
    4423  249.18  4531.6   246.9    4563  244.92  4796.8  239.84  4856.2   236.3
  4899.7  236.16  4929.7  234.32  4980.8  232.46  4986.6   228.9  4996.2  227.25
    5000  227.25  5004.9  230.31    5014  232.39  5028.4  233.54  5048.5  225.19
  5076.9  224.42  5098.8  226.47  5128.9  232.07  5227.8  235.46  5319.8  236.22
  5430.4  240.87  5515.3  246.76  5540.9  249.99  5701.7  263.65    5747   266.3
#Mann= 5 ,-1 , 0
  4042.8     .17       0  4929.7     .15       0  4980.8     .09       0
    5014     .15       0  5227.8     .17       0
Bank Sta=4980.8,5014
XS Rating Curve= 0 ,0
Exp/Cntr=0.3,0.1

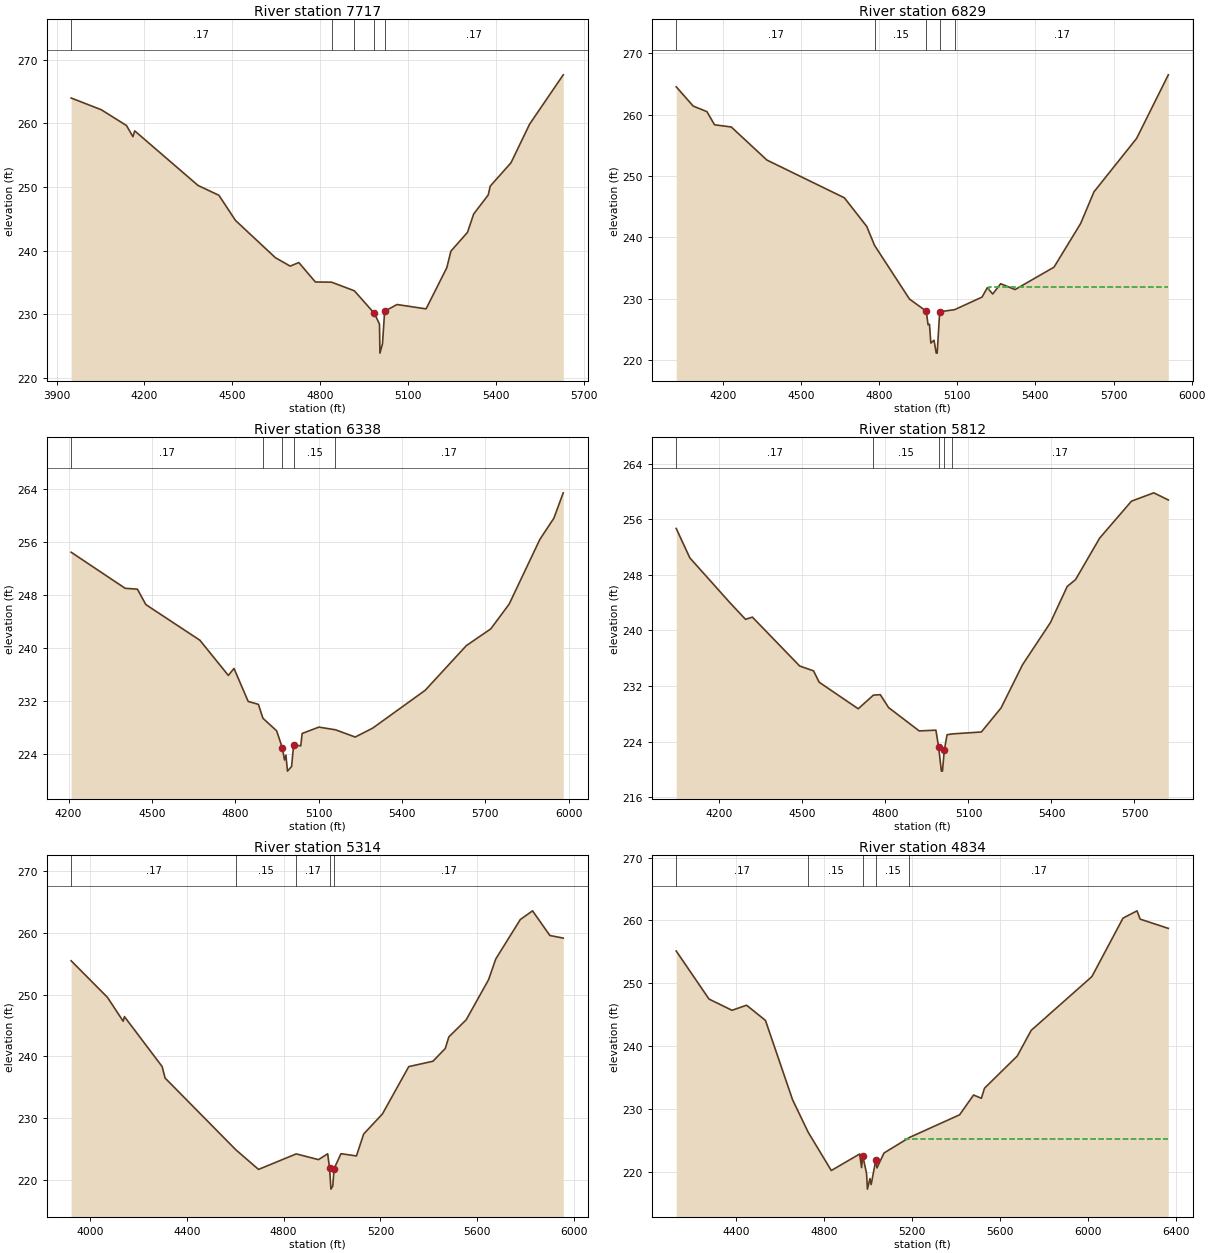
Type RM Length L Ch R = 1 ,7717    ,888,888,888
BEGIN DESCRIPTION:
LITTLE LAKE CREEK TRIB NO 3 15.0
END DESCRIPTION:
XS GIS Cut Line= 3
       3763131.5      10159580.9      3762277.53     10158969.62
       3761839.1     10158517.49
#Sta/Elev= 30
  3949.8  263.96  4052.7  262.12  4138.8  259.64  4160.7  257.89  4166.9   258.8
  4383.1  250.23  4454.3  248.69  4510.9  244.74  4647.2  238.89  4697.6  237.57
  4727.1  238.13  4783.6  235.08  4838.8  235.05  4916.6   233.7    4985  230.15
  5002.5  228.46    5004  223.91  5012.8   225.4    5020  230.48  5062.4  231.54
  5161.5  230.86  5232.2  237.31  5246.3  239.92  5302.9  242.87    5324  245.75
  5373.7  248.74  5380.6  250.13  5451.4  253.79  5514.9  259.85  5629.8   267.6
#Mann= 5 ,-1 , 0
  3949.8     .17       0  4838.8     .15       0  4916.6     .17       0
    4985     .09       0    5020     .17       0
#XS Ineff= 2 , 0
       0  4838.8  235.05               0
Permanent Ineff=
       F       F
Bank Sta=4985,5020
XS Rating Curve= 0 ,0
Exp/Cntr=0.3,0.1

Type RM Length L Ch R = 1 ,6829    ,491,491,491
BEGIN DESCRIPTION:
LITTLE LAKE CREEK TRIB NO 3 13.0
END DESCRIPTION:
XS GIS Cut Line= 3
      3763178.05     10159545.96      3762798.74     10158643.97
      3761908.92     10158451.49
#Sta/Elev= 30
  4021.5  264.54  4086.5   261.4  4139.4  260.48  4168.6  258.34  4232.9  257.98
  4369.4  252.59  4666.9  246.43  4752.7  241.77  4782.9  238.66  4916.9  229.91
  4981.5  227.92  4988.1  225.72  4993.6   225.8  4998.9  222.73  5011.1  223.19
  5019.5  221.09  5023.2  221.09  5031.6  226.99 5034.98  227.85  5090.2  228.18
  5195.3  230.23  5215.8  231.77  5236.2  230.73  5266.9  232.41  5322.2  231.46
  5471.5  235.11  5573.9  242.24    5625   247.4  5788.7  256.12  5910.4  266.49
#Mann= 5 ,-1 , 0
  4021.5     .17       0  4782.9     .15       0  4981.5     .09       0
 5034.98     .15       0  5090.2     .17       0
#XS Ineff= 2 , 0
       0                  5223.7       0  231.85
Permanent Ineff=
       F       F
Bank Sta=4981.5,5034.98
XS Rating Curve= 0 ,0
Exp/Cntr=0.3,0.1

Type RM Length L Ch R = 1 ,6338    ,526,526,526
BEGIN DESCRIPTION:
LITTLE LAKE CREEK TRIB NO 3 12.0
END DESCRIPTION:
XS GIS Cut Line= 3
      3763670.94     10158397.16      3762897.92     10158231.85
      3761924.47     10158346.71
#Sta/Elev= 30
  4209.5  254.47  4403.9  249.01  4447.9  248.88  4478.5  246.54  4672.8  241.15
  4775.1  235.83  4795.5  236.88  4846.7  231.88  4883.3  231.45  4899.6  229.34
  4948.9  227.44  4969.4  224.86  4977.2  223.02  4982.3  223.77  4987.9  221.34
  5002.6  222.04  5010.1  225.29  5035.7  225.17  5040.7  227.04  5100.8     228
  5160.5   227.6  5231.7   226.5  5294.6  227.85  5483.4  233.57  5631.4  240.33
  5719.4  242.87  5785.5  246.61  5896.2  256.42  5946.6  259.63  5980.2  263.46
#Mann= 5 ,-1 , 0
  4209.5     .17       0  4899.6     .15       0  4969.4     .09       0
  5010.1     .15       0  5160.5     .17       0
Bank Sta=4969.4,5010.1
XS Rating Curve= 0 ,0
Exp/Cntr=0.3,0.1

Type RM Length L Ch R = 1 ,5812    ,498,498,498
BEGIN DESCRIPTION:
LITTLE LAKE CREEK TRIB NO 3 11.0
END DESCRIPTION:
XS GIS Cut Line= 3
       3763771.8     10157880.98      3762820.23     10157785.99
      3762005.93     10157900.39
#Sta/Elev= 30
  4043.7  254.69    4093  250.45  4238.6  243.96  4294.2   241.6    4319  241.92
  4489.9  234.88  4540.1  234.18  4560.2  232.55  4701.5  228.72  4756.2  230.68
  4781.3  230.75  4811.4  228.89    4922  225.53  4982.3  225.64  4992.3  223.18
  5002.1  219.74    5006  219.74  5012.5  222.73  5022.6  224.98  5041.3   225.1
  5146.6  225.38  5217.9  228.85  5295.3  235.06  5396.2  241.13  5456.8  246.33
  5487.1  247.33  5574.3  253.31  5689.1  258.62  5769.9  259.82  5822.3  258.79
#Mann= 5 ,-1 , 0
  4043.7     .17       0  4756.2     .15       0  4992.3     .09       0
  5012.5     .15       0  5041.3     .17       0
Bank Sta=4992.3,5012.5
XS Rating Curve= 0 ,0
Exp/Cntr=0.3,0.1

Type RM Length L Ch R = 1 ,5314    ,480,480,480
BEGIN DESCRIPTION:
LITTLE LAKE CREEK TRIB NO 3 10.0
END DESCRIPTION:
XS GIS Cut Line= 3
      3763806.76     10157640.35      3762778.28     10157320.06
      3761993.94     10157865.06
#Sta/Elev= 30
  3922.8  255.47  4072.6  249.56  4137.7  245.69  4142.9  246.44  4298.7  238.35
  4310.8   236.5  4603.1  224.89  4696.7  221.72  4852.4  224.23  4944.5   223.3
  4982.3  224.25    4990  221.96  4995.7  218.53  5003.3  219.03  5008.6  221.83
  5037.1  224.26  5101.1   223.9  5130.8  227.44  5208.5   230.7  5317.1  238.35
  5417.1  239.22  5467.8  241.28  5482.6  243.15  5554.2  245.92  5646.7  252.41
  5676.4  255.76  5777.7  262.14  5828.3  263.55  5899.9  259.56  5955.1  259.14
#Mann= 5 ,-1 , 0
  3922.8     .17       0  4603.1     .15       0  4852.4     .17       0
    4990     .09       0  5008.6     .17       0
Bank Sta=4990,5008.6
XS Rating Curve= 0 ,0
Exp/Cntr=0.3,0.1

Type RM Length L Ch R = 1 ,4834    ,475,475,475
BEGIN DESCRIPTION:
LITTLE LAKE CREEK TRIB NO 3 9.0
END DESCRIPTION:
XS GIS Cut Line= 4
      3763846.36      10156733.6      3763011.64     10156983.41
      3762780.35     10157059.07      3761977.04      10157841.3
#Sta/Elev= 30
  4128.7  255.14  4277.7   247.5  4382.2  245.71  4448.4  246.52  4534.2   244.1
  4657.4  231.48  4728.6   226.3  4833.3  220.23  4962.2  222.86  4970.9  220.69
  4976.1   222.6  4993.5  219.77  4997.4  217.27  5008.9  218.95  5014.5     218
  5035.5  221.91  5040.8  220.64  5072.6  223.01    5188  225.48  5416.2  229.09
  5479.9  232.24  5515.2  231.72  5529.4  233.32    5678  238.43  5741.5  242.52
  6017.3  251.07  6158.8  260.37  6222.5  261.53  6236.6  260.21  6364.6  258.74
#Mann= 5 ,-1 , 0
  4128.7     .17       0  4728.6     .15       0  4976.1     .09       0
  5035.5     .15       0    5188     .17       0
#XS Ineff= 2 , 0
       0                  5168.2       0  225.25
Permanent Ineff=
       F       F
Bank Sta=4976.1,5035.5
XS Rating Curve= 0 ,0
Exp/Cntr=0.3,0.1

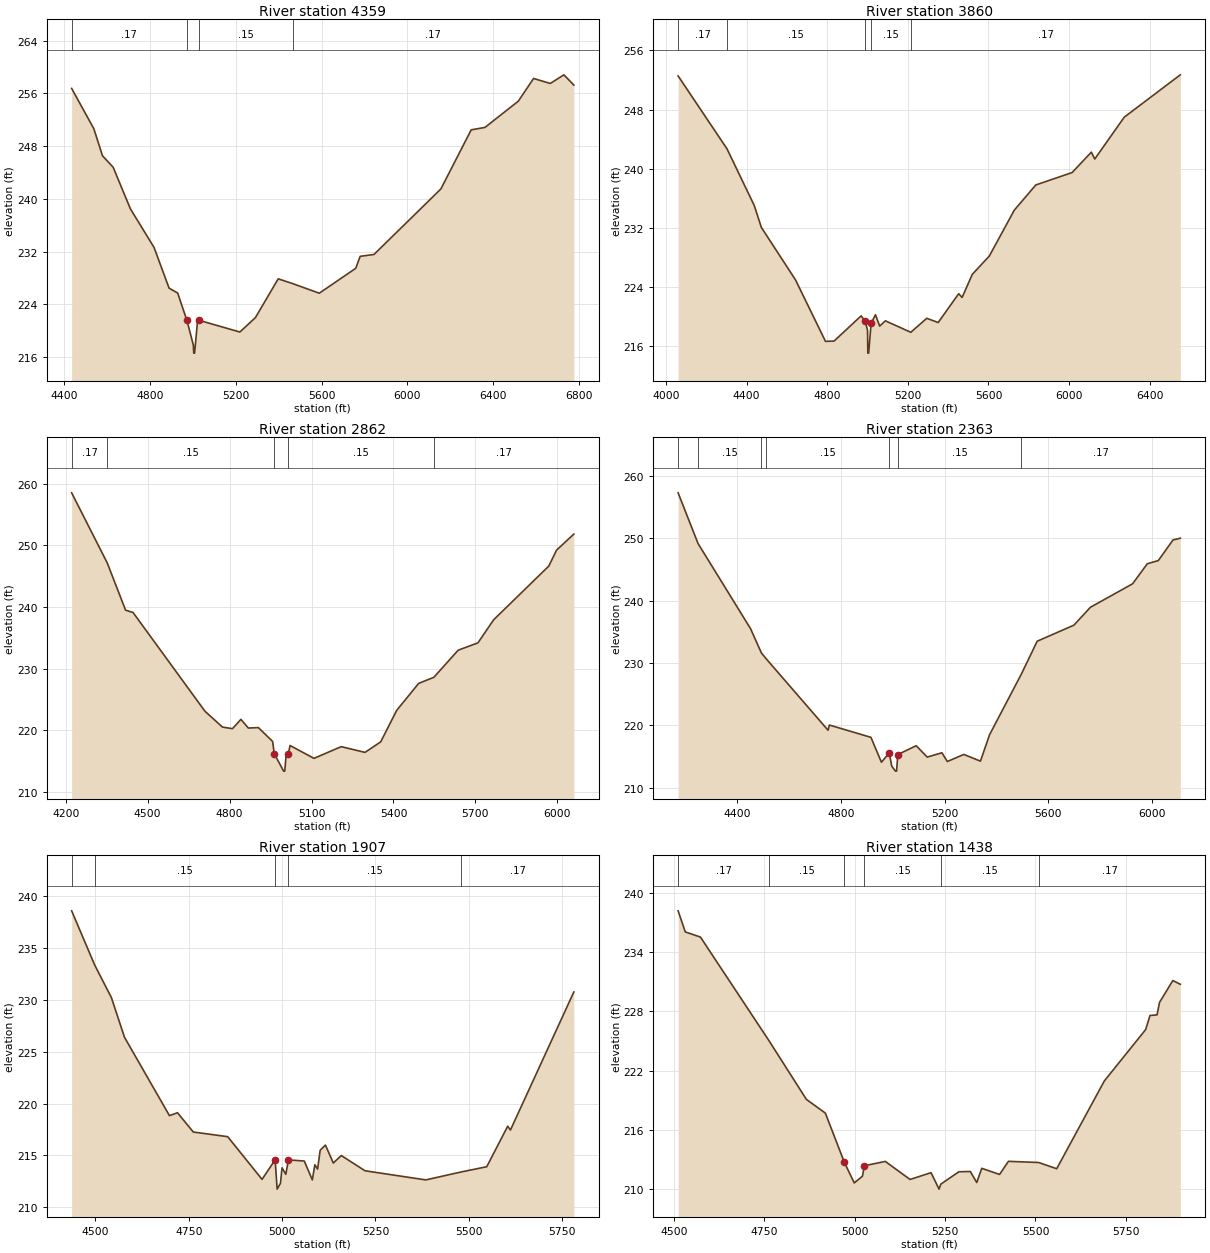
Type RM Length L Ch R = 1 ,4359    ,499,499,499
BEGIN DESCRIPTION:
LITTLE LAKE CREEK TRIB NO 3 8.0
END DESCRIPTION:
XS GIS Cut Line= 4
      3763781.28     10156573.01      3763217.73     10156592.86
      3762973.94     10156703.22      3761958.55     10157816.78
#Sta/Elev= 30
  4436.1  256.74  4539.6  250.62  4579.6  246.54  4629.6  244.78  4709.7  238.49
  4819.8  232.64  4889.8  226.47  4929.8  225.73  4972.7  221.59  5002.7  217.86
  5004.6  216.62  5008.6  216.62  5021.8  221.26  5029.7  221.59  5219.4  219.82
  5291.8     222    5398  227.88  5465.9  227.15  5589.2   225.7  5758.8  229.47
  5779.8  231.29  5843.9  231.57  6155.4   241.5  6296.6  250.46  6360.8  250.83
  6516.2  254.81  6587.1  258.25  6664.8  257.49  6728.4   258.8  6774.6  257.25
#Mann= 4 ,-1 , 0
  4436.1     .17       0  4972.7     .09       0  5029.7     .15       0
  5465.9     .17       0
Bank Sta=4972.7,5029.7
XS Rating Curve= 0 ,0
Exp/Cntr=0.3,0.1

Type RM Length L Ch R = 1 ,3860    ,998,998,998
BEGIN DESCRIPTION:
LITTLE LAKE CREEK TRIB NO 3 7.0
END DESCRIPTION:
XS GIS Cut Line= 4
      3763559.26     10155578.62      3762904.11     10156252.28
      3762639.35     10156539.18       3762128.7     10157582.07
#Sta/Elev= 30
  4060.3  252.55    4303  242.68  4437.9  235.03  4473.2  232.06  4642.9  224.95
  4791.4  216.64  4833.8  216.68  4968.3  220.09  4989.4  219.33    5000  218.12
  5001.5  215.05  5005.5  215.05  5017.7  219.08  5039.2  220.24  5060.2  218.71
  5088.6  219.42  5214.6  217.87  5293.8  219.76  5350.5  219.19  5452.2  223.09
  5469.1  222.58  5519.7  225.71  5604.1  228.18  5727.8  234.38  5834.8   237.8
  6014.8  239.48  6110.4  242.24  6127.3  241.31  6273.5  246.97  6551.6   252.7
#Mann= 5 ,-1 , 0
  4060.3     .17       0    4303     .15       0  4989.4     .09       0
  5017.7     .15       0  5214.6     .17       0
Bank Sta=4989.4,5017.7
XS Rating Curve= 0 ,0
Exp/Cntr=0.3,0.1

Type RM Length L Ch R = 1 ,2862    ,499,499,499
BEGIN DESCRIPTION:
LITTLE LAKE CREEK TRIB NO 3 6.0
END DESCRIPTION:
XS GIS Cut Line= 3
      3763427.27     10155130.74       3762762.6     10155535.67
      3761874.68     10156115.17
#Sta/Elev= 30
  4221.7  258.52  4352.1  247.14  4419.2  239.48  4446.4  239.11  4709.7  223.09
  4773.7  220.52  4810.5  220.26  4841.4  221.77  4868.6  220.36  4905.4  220.43
  4957.6  218.18  4963.5   216.2  4997.8  213.37    5002  213.37  5006.2  215.64
  5015.3   216.2  5021.3  217.53  5108.8  215.44  5208.7  217.34  5295.9  216.41
  5353.2  218.12  5411.7  223.22    5492   227.6  5547.8  228.59  5636.9  232.99
  5709.3  234.18  5766.6  237.92  5968.7  246.64  5996.8  249.21  6060.3  251.83
#Mann= 5 ,-1 , 0
  4221.7     .17       0  4352.1     .15       0  4963.5     .09       0
  5015.3     .15       0  5547.8     .17       0
Bank Sta=4963.5,5015.3
XS Rating Curve= 0 ,0
Exp/Cntr=0.3,0.1

Type RM Length L Ch R = 1 ,2363    ,456,456,456
BEGIN DESCRIPTION:
LITTLE LAKE CREEK TRIB NO 3 5.0
END DESCRIPTION:
XS GIS Cut Line= 3
       3763384.9     10155016.26      3762564.19     10155130.34
      3761816.87     10155949.99
#Sta/Elev= 30
  4171.4  257.26  4248.3  249.14  4451.1  235.49  4492.3  231.65  4512.1  230.64
    4750  219.24  4755.1  220.07  4915.5   218.1  4955.9  214.11  4986.2  215.61
  4995.6  213.51  5010.1  212.69  5014.4  212.69  5019.1  215.34    5090  216.76
  5132.6  214.94  5189.3  215.63  5210.3  214.23  5273.8  215.36    5338  214.29
  5373.1  218.51  5496.1  228.25  5556.9  233.49  5698.7  236.07  5762.3  238.93
  5925.1  242.69  5981.8   245.9  6024.4  246.41  6081.2  249.72  6109.2  249.99
#Mann= 7 ,-1 , 0
  4171.4     .17       0  4248.3     .15       0  4492.3     .11       0
  4512.1     .15       0  4986.2     .09       0  5019.1     .15       0
  5496.1     .17       0
Bank Sta=4986.2,5019.1
XS Rating Curve= 0 ,0
Exp/Cntr=0.3,0.1

Type RM Length L Ch R = 1 ,1907    ,469,469,469
BEGIN DESCRIPTION:
LITTLE LAKE CREEK TRIB NO 3 4.0
END DESCRIPTION:
XS GIS Cut Line= 3
      3763017.87     10154361.06      3762602.56     10154741.77
      3762067.88     10155311.04
#Sta/Elev= 30
  4436.6  238.59  4498.3  233.36    4543  230.22  4578.1  226.39  4698.4  218.83
    4720  219.11  4762.2  217.25  4854.4   216.8  4946.3  212.68  4981.4  214.57
  4986.7  211.74  4995.6   212.3  4999.8   213.8    5010  213.17  5016.9  214.56
  5059.4  214.45  5080.9  212.63  5087.7  214.09    5095  213.67  5101.9  215.49
    5116  215.99  5137.1  214.26  5158.5  214.98    5222  213.51  5384.7  212.63
    5480   213.4  5547.8   213.9    5604  217.81  5611.3  217.44    5781  230.76
#Mann= 5 ,-1 , 0
  4436.6     .17       0  4498.3     .15       0  4981.4     .09       0
  5016.9     .15       0    5480     .17       0
#XS Ineff= 2 , 0
       0                    5116       0  215.99
Permanent Ineff=
       F       T
Bank Sta=4981.4,5016.9
XS Rating Curve= 0 ,0
Exp/Cntr=0.3,0.1

Type RM Length L Ch R = 1 ,1438    ,431,431,431
BEGIN DESCRIPTION:
LITTLE LAKE CREEK TRIB NO 3 3.0
END DESCRIPTION:
XS GIS Cut Line= 3
      3762766.77     10154252.64      3762300.33     10154397.79
      3762015.12     10155252.03
#Sta/Elev= 30
  4511.5  238.21  4531.3  236.07  4573.2  235.55  4763.5     225  4866.4  219.08
  4918.8  217.69  4971.2  212.71  4998.7  210.61  5021.4  211.29  5026.7  212.35
  5084.6  212.79  5153.1  210.96  5211.1  211.65  5233.3  209.98    5238  210.48
  5288.1  211.74  5319.7  211.77  5337.5  210.65  5351.4  212.09  5400.7  211.47
  5425.2   212.8  5508.7  212.68  5558.7  212.05  5690.4  220.95  5804.7  226.16
  5816.8  227.59  5836.3  227.66  5843.1  228.92    5880  231.14  5900.6  230.76
#Mann= 6 ,-1 , 0
  4511.5     .17       0  4763.5     .15       0  4971.2     .09       0
  5026.7     .15       0    5238     .15       0  5508.7     .17       0
Bank Sta=4971.2,5026.7
XS Rating Curve= 0 ,0
Exp/Cntr=0.3,0.1