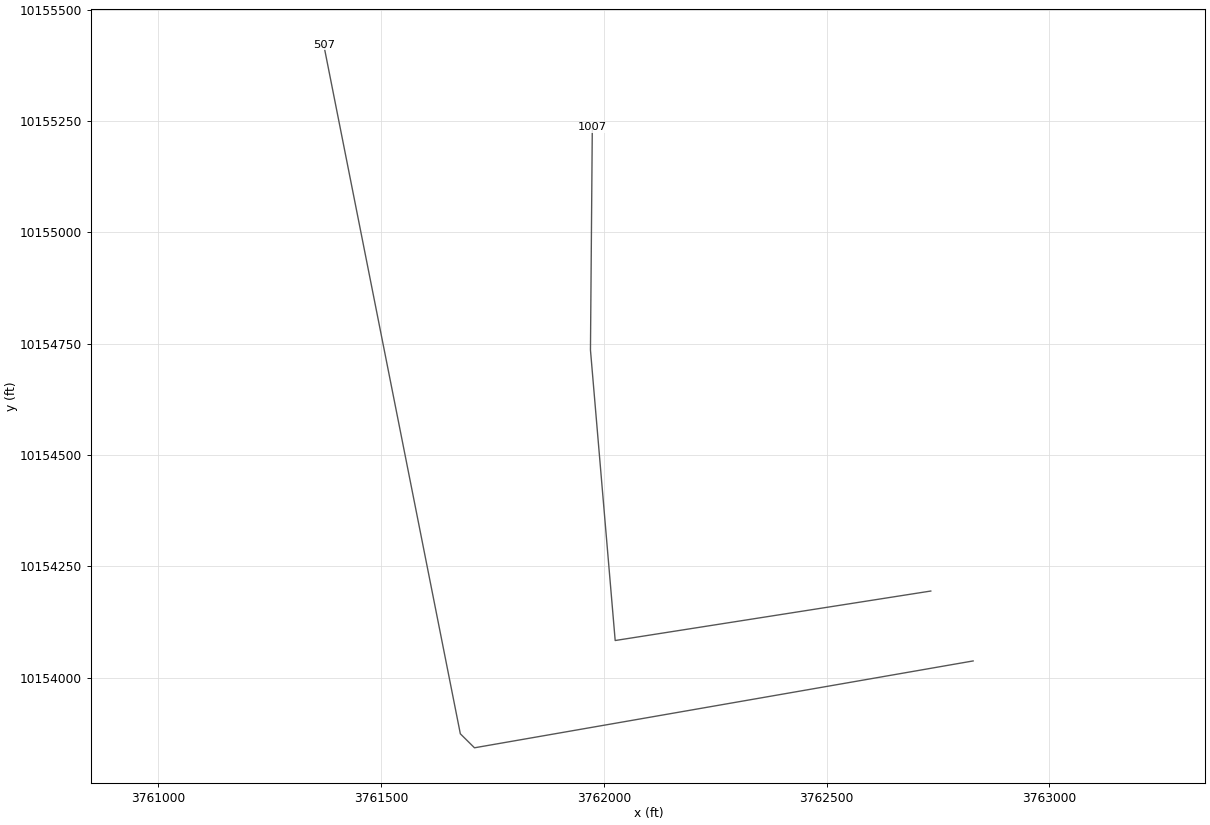
HEC-RAS study LITTLE LAKE CREEK TRIB NO 3.prj: LITTLE LAKE CREEK TRIB NO 3 Base Level Engineering

--- LITTLE LAKE CREEK TRIB NO 3.g01 (geometry) --- (continued)

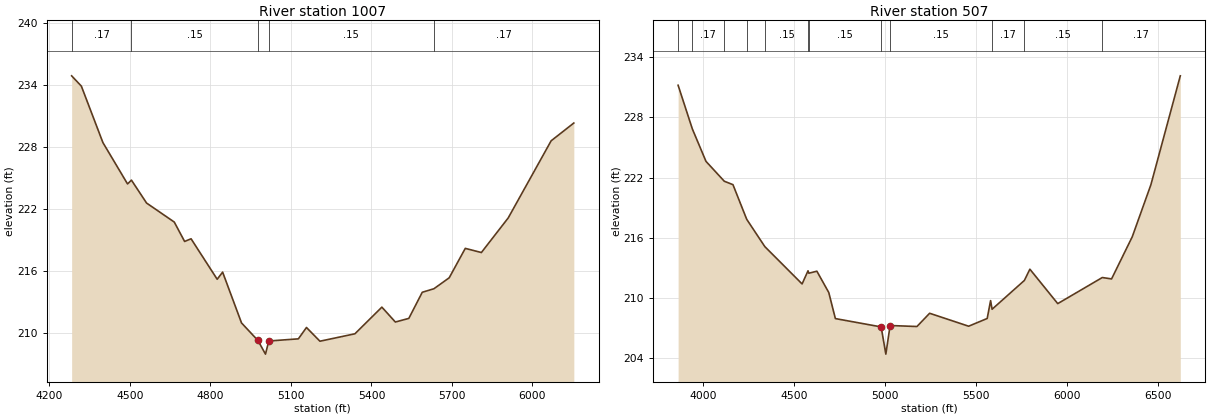
Type RM Length L Ch R = 1 ,1007    ,500,500,500
BEGIN DESCRIPTION:
LITTLE LAKE CREEK TRIB NO 3 2.0
END DESCRIPTION:
XS GIS Cut Line= 4
      3762733.64     10154194.82      3762025.19     10154083.75
      3761969.69     10154735.83      3761973.82     10155235.57
#Sta/Elev= 30
  4282.9  234.91  4319.1  233.91  4399.5  228.44  4491.2  224.44  4505.7  224.81
  4562.1  222.59  4665.3  220.75  4703.8  218.87  4727.9  219.13  4825.2  215.21
  4845.5   215.9  4915.9  210.98  4977.1  209.28  5005.2  207.96  5017.4  209.23
  5127.8  209.44  5157.9  210.54  5208.1  209.21  5338.5  209.93  5438.9  212.51
  5489.1  211.07  5539.3  211.42  5589.4  213.95  5632.7  214.29  5689.7  215.35
  5749.7   218.2  5809.7   217.8  5909.7  221.15  6069.7  228.62  6154.2  230.34
#Mann= 5 ,-1 , 0
  4282.9     .17       0  4505.7     .15       0  4977.1     .09       0
  5017.4     .15       0  5632.7     .17       0
#XS Ineff= 2 , 0
       0                  5438.9       0  212.51
Permanent Ineff=
       F       F
Bank Sta=4977.1,5017.4
XS Rating Curve= 0 ,0
Exp/Cntr=0.3,0.1

Type RM Length L Ch R = 1 ,507     ,0,0,0
BEGIN DESCRIPTION:
LITTLE LAKE CREEK TRIB NO 3 1.0
END DESCRIPTION:
XS GIS Cut Line= 4
      3762828.69     10154037.91      3761709.35     10153842.93
      3761677.59     10153874.35      3761370.88     10155421.37
#Sta/Elev= 30
  3863.8  231.19    3942  226.84  4016.9  223.61  4117.4  221.63    4165  221.29
  4240.5  217.84    4340  215.12  4544.7   211.4  4577.3  212.71  4581.7  212.47
  4625.9  212.67  4691.1  210.55  4727.5  207.95  4978.9  207.12  5004.6  204.41
  5028.1  207.26  5175.4  207.16  5245.2  208.48  5459.3  207.19  5561.3  207.96
  5579.9  209.74  5588.1  208.88  5765.5  211.75  5795.7  212.87  5948.7  209.44
  6193.5  212.04  6244.3   211.9    6358   216.1  6460.4  221.29  6621.8  232.13
#Mann= 12 ,-1 , 0
  3863.8     .11       0    3942     .17       0  4117.4     .15       0
  4240.5     .17       0    4340     .15       0  4577.3     .17       0
  4581.7     .15       0  4978.9     .09       0  5028.1     .15       0
  5588.1     .17       0  5765.5     .15       0  6193.5     .17       0
#XS Ineff= 2 , 0
       0                  5579.9       0  209.74
Permanent Ineff=
       F       F
Bank Sta=4978.9,5028.1
XS Rating Curve= 0 ,0
Exp/Cntr=0.3,0.1

Chan Stop Cuts=-1
Use User Specified Reach Order=0
Composite Channel Slope=5