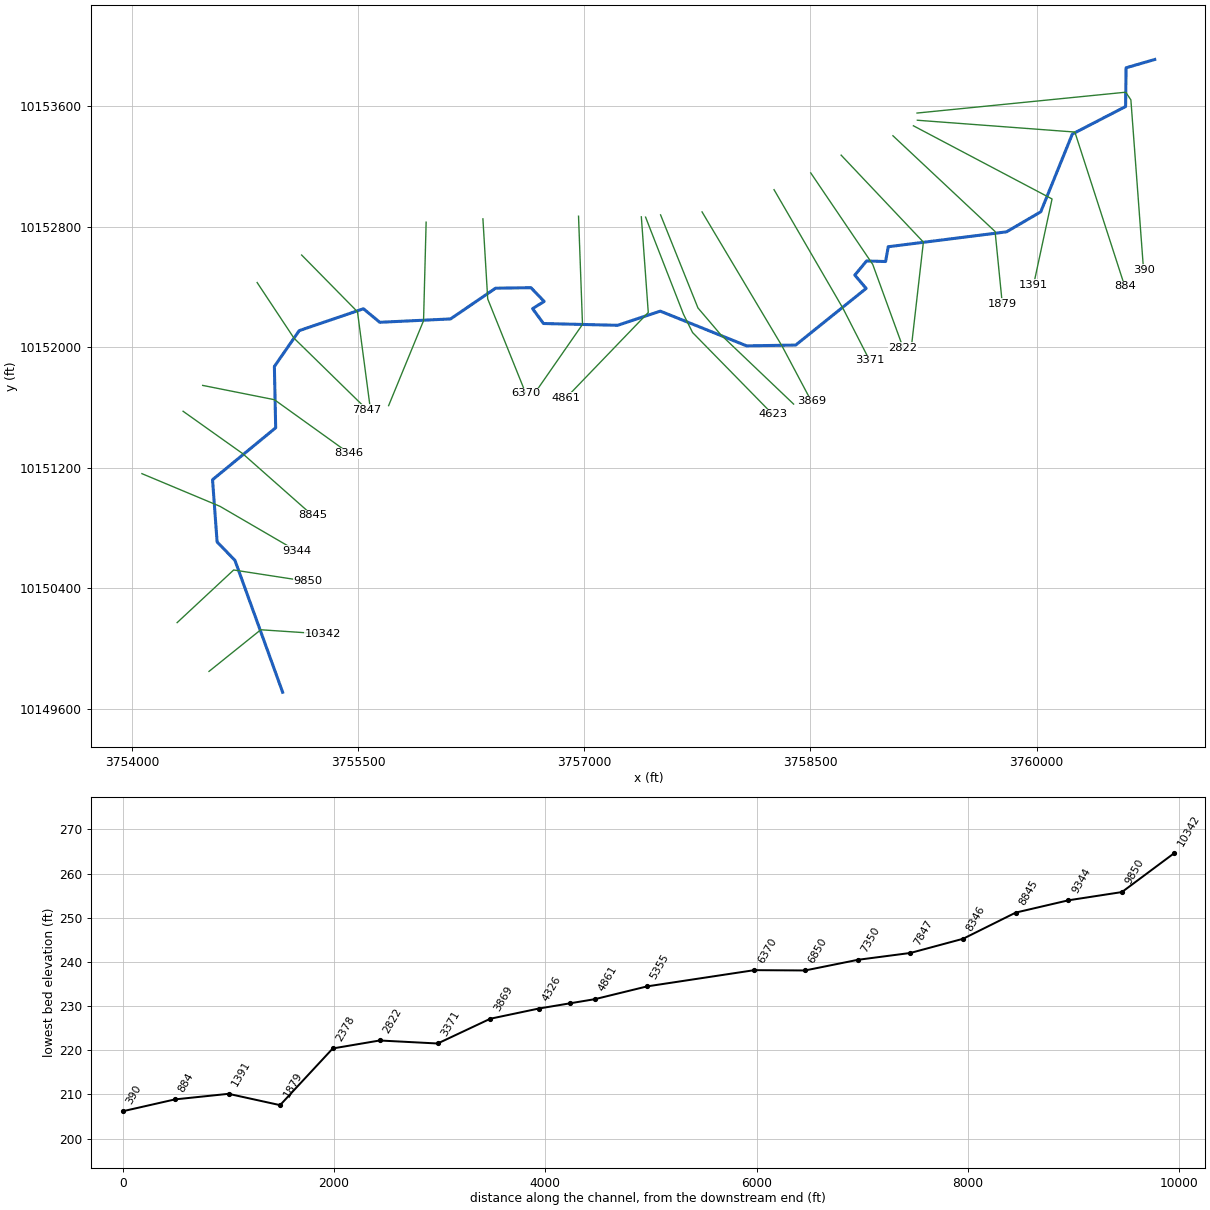
--- LITTLE LAKE CREEK TRIB NO 4.prj (project) ---

Proj Title=LITTLE LAKE CREEK TRIB NO 4 Base Level Engineering
Current Plan=p01
Default Exp/Contr=0.3,0.1
English Units
Geom File=g01
Flow File=f01
Plan File=p01
Y Axis Title=Elevation
X Axis Title(PF)=Main Channel Distance
X Axis Title(XS)=Station
BEGIN DESCRIPTION:
LITTLE LAKE CREEK TRIB NO 4
END DESCRIPTION:
DSS Export Rating Curves= 0
DSS Export Rating Curve Sorted= 0
DSS Export Volume Flow Curves= 0
DXF OffsetX= 0
DXF OffsetY= 0
DXF ScaleX= 1
DXF ScaleY= 10

--- LITTLE LAKE CREEK TRIB NO 4.p01 (plan) ---

Plan Title=Multiple Run
Short Identifier=Multiple
Geom File=g01
Flow File=f01
Subcritical Flow
K Sum by GR= 0
Std Step Tol= 0.01
Critical Tol= 0.01
Num of Std Step Trials= 20
Max Error Tol= 0.3
Flow Tol Ratio= 0.001
Split Flow NTrial= 30
Split Flow Tol= 0.02
Split Flow Ratio= 0.02
Log Output Level= 0
Friction Slope Method= 1
Unsteady Friction Slope Method= 2
Unsteady Bridges Friction Slope Method= 1
Parabolic Critical Depth
Global Vel Dist=  1 , 1 , 1
Global Log Level= 0
CheckData=True
Encroach Param= -1, 0, 0, 0
BEGIN DESCRIPTION:
Multiple Run
END DESCRIPTION:

--- LITTLE LAKE CREEK TRIB NO 4.f01 (steady flow) ---

Flow Title=Multiple
Program Version=4.10
Number of Profiles= 7
Profile Names=10-year,25-year,50-year,1pct_min,100-year,1pct_plu,500-year
River Rch & RM=LITTLE LAKE CREE,Reach-1         ,10342
     916    1271    1745     788    2379    7184    4577
River Rch & RM=LITTLE LAKE CREE,Reach-1         ,390
    4043    5791    8116    3712   11211   33857   22152
Boundary for River Rch & Prof#=LITTLE LAKE CREE,Reach-1         , 1
Up Type= 0
Dn Type= 3
Dn Slope=0.006
Boundary for River Rch & Prof#=LITTLE LAKE CREE,Reach-1         , 2
Up Type= 0
Dn Type= 3
Dn Slope=0.006
Boundary for River Rch & Prof#=LITTLE LAKE CREE,Reach-1         , 3
Up Type= 0
Dn Type= 3
Dn Slope=0.006
Boundary for River Rch & Prof#=LITTLE LAKE CREE,Reach-1         , 4
Up Type= 0
Dn Type= 3
Dn Slope=0.006
Boundary for River Rch & Prof#=LITTLE LAKE CREE,Reach-1         , 5
Up Type= 0
Dn Type= 3
Dn Slope=0.006
Boundary for River Rch & Prof#=LITTLE LAKE CREE,Reach-1         , 6
Up Type= 0
Dn Type= 3
Dn Slope=0.006
Boundary for River Rch & Prof#=LITTLE LAKE CREE,Reach-1         , 7
Up Type= 0
Dn Type= 3
Dn Slope=0.006
DSS Import GetInterval= 0
DSS Import GetPeak= 0
DSS Import FillOption= 0

--- LITTLE LAKE CREEK TRIB NO 4.g01 (geometry) ---

Geom Title=Existing Conditions
Program Version=4.10

River Reach=LITTLE LAKE CREE,Reach-1
Reach XY= 30
        3755000.       10149710.      3754683.86     10150584.75
      3754565.26     10150707.65      3754535.03     10151120.29
      3754953.79     10151465.04      3754945.16     10151871.87
       3755109.9     10152109.88      3755535.86     10152254.91
      3755644.29     10152165.21      3756113.69     10152187.57
      3756412.34     10152391.56      3756646.92     10152394.93
      3756734.38     10152303.51      3756657.58     10152255.94
       3756729.8     10152157.17      3757221.79     10152145.16
      3757504.66     10152239.27      3758077.25     10152008.82
      3758402.65     10152014.04      3758869.98     10152389.97
      3758794.86     10152478.37      3758872.84     10152572.24
      3758999.06     10152568.48      3759016.58     10152666.72
      3759800.83      10152765.5       3760028.2     10152898.44
      3760237.59     10153414.58      3760590.98     10153597.28
      3760593.88      10153854.3      3760784.34     10153909.46

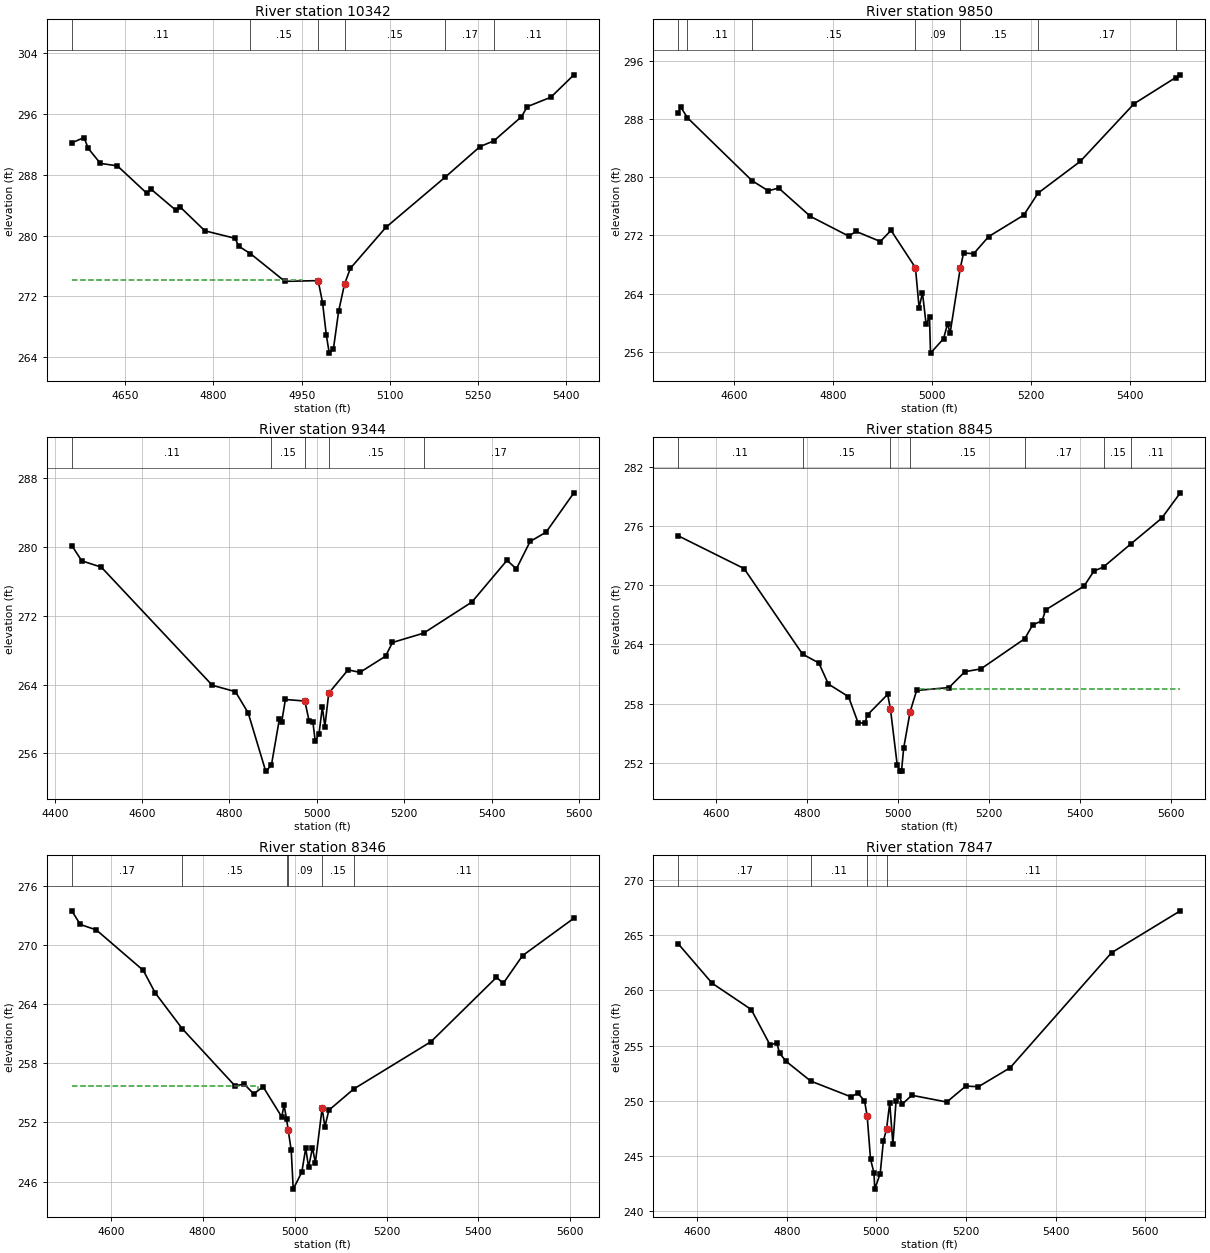
Type RM Length L Ch R = 1 ,10342   ,492,492,492
BEGIN DESCRIPTION:
LITTLE LAKE CREEK TRIB NO 4 1.0
END DESCRIPTION:
XS GIS Cut Line= 3
      3754511.56     10149848.18      3754854.99     10150124.51
      3755266.87     10150097.02
#Sta/Elev= 30
  4559.2  292.18  4580.1  292.88  4587.1  291.46  4607.9  289.48  4636.7  289.16
  4686.3  285.59  4694.3  286.07  4735.9  283.34  4743.9  283.72  4785.5  280.62
  4836.7  279.64  4843.1  278.59    4863  277.62  4921.5  273.98    4978  274.08
  4985.5   271.2  4991.9  266.93  4996.9  264.55  5003.9  265.05  5012.9  270.08
  5022.9  273.63  5032.9   275.7  5093.1  281.07  5194.1  287.68  5253.4   291.7
  5276.7  292.44  5323.6  295.61  5333.6  296.94  5373.7  298.18  5412.8  301.12
#Mann= 6 ,-1 , 0
  4559.2     .11       0    4863     .15       0    4978     .09       0
  5022.9     .15       0  5194.1     .17       0  5276.7     .11       0
#XS Ineff= 2 , 0
       0  4950.3  274.19               0
Permanent Ineff=
       F       F
Bank Sta=4978,5022.9
XS Rating Curve= 0 ,0
Exp/Cntr=0.3,0.1

Type RM Length L Ch R = 1 ,9850    ,506,506,506
BEGIN DESCRIPTION:
LITTLE LAKE CREEK TRIB NO 4 2.0
END DESCRIPTION:
XS GIS Cut Line= 3
      3754300.15     10150171.87      3754675.08     10150521.29
      3755170.02     10150444.94
#Sta/Elev= 30
  4487.5  288.81  4492.4  289.71  4506.3   288.2  4636.6  279.54  4669.3  278.15
  4690.3  278.53  4754.3  274.63    4832   271.9  4846.1  272.57  4895.5  271.17
    4917   272.7  4966.3  267.56  4973.7  262.06  4980.5  264.09  4987.8   259.8
  4994.7  260.74  4996.7   255.8    5023  257.78  5031.2  259.86  5036.2  258.53
 5056.86  267.55  5063.5  269.59  5083.8  269.49  5114.1  271.85  5184.9   274.8
  5213.7  277.83  5298.9   282.2  5407.5  290.14  5491.3  293.74  5500.8  294.12
#Mann= 7 ,-1 , 0
  4487.5     .17       0  4506.3     .11       0  4636.6     .15       0
  4966.3     .09       0 5056.86     .15       0  5213.7     .17       0
  5491.3     .11       0
Bank Sta=4966.3,5056.86
XS Rating Curve= 0 ,0
Exp/Cntr=0.3,0.1

Type RM Length L Ch R = 1 ,9344    ,499,499,499
BEGIN DESCRIPTION:
LITTLE LAKE CREEK TRIB NO 4 3.0
END DESCRIPTION:
XS GIS Cut Line= 3
      3754066.74     10151160.61      3754584.25      10150943.8
      3755092.87     10150647.55
#Sta/Elev= 30
  4438.9  280.14  4461.8  278.36  4506.5  277.63  4760.6  263.91  4813.6  263.17
  4842.8   260.7  4882.9  253.94  4895.9   254.6  4914.1  259.94  4919.5  259.63
    4928  262.26  4972.5  262.08  4982.2   259.8  4990.9  259.68  4996.3  257.41
    5005  258.27  5012.6  261.38  5018.4  259.12  5027.3  262.99  5071.4   265.7
  5098.7  265.41  5157.4  267.29  5173.1  268.88  5244.4  269.96  5355.1  273.58
  5435.4  278.42  5456.9  277.43  5488.3  280.61  5524.9  281.69  5588.6  286.26
#Mann= 5 ,-1 , 0
  4438.9     .11       0  4895.9     .15       0  4972.5     .09       0
  5027.3     .15       0  5244.4     .17       0
Bank Sta=4972.5,5027.3
XS Rating Curve= 0 ,0
Exp/Cntr=0.3,0.1

Type RM Length L Ch R = 1 ,8845    ,499,499,499
BEGIN DESCRIPTION:
LITTLE LAKE CREEK TRIB NO 4 4.0
END DESCRIPTION:
XS GIS Cut Line= 3
      3754339.78     10151574.61      3754733.57     10151294.59
      3755198.59     10150883.16
#Sta/Elev= 30
  4516.8  274.99  4661.7  271.67  4790.2  263.01  4826.1  262.11    4847  259.98
  4891.3   258.7  4912.2  256.08    4927     256  4933.1  256.86  4977.4  258.93
  4983.5  257.46  4998.3  251.83  5004.4  251.16  5007.9  251.16  5012.6  253.48
  5026.8  257.17  5041.1  259.33  5112.2  259.62  5147.3  261.23  5182.4  261.51
  5278.9  264.57  5296.2  265.96  5317.1  266.39  5324.6  267.48  5409.1  269.89
  5430.9  271.41  5452.1  271.84    5513   274.2  5579.8  276.76  5620.9  279.34
#Mann= 7 ,-1 , 0
  4516.8     .11       0  4790.2     .15       0  4983.5     .09       0
  5026.8     .15       0  5278.9     .17       0  5452.1     .15       0
    5513     .11       0
#XS Ineff= 2 , 0
       0                  5047.7       0  259.45
Permanent Ineff=
       F       F
Bank Sta=4983.5,5026.8
XS Rating Curve= 0 ,0
Exp/Cntr=0.3,0.1

Type RM Length L Ch R = 1 ,8346    ,499,499,499
BEGIN DESCRIPTION:
LITTLE LAKE CREEK TRIB NO 4 5.0
END DESCRIPTION:
XS GIS Cut Line= 3
      3754469.68     10151746.36      3754945.02     10151651.58
      3755438.64     10151297.13
#Sta/Elev= 30
  4515.3  273.47  4533.8  272.09  4568.7  271.53  4670.8  267.43    4697  265.13
  4755.8   261.5    4870  255.73  4890.7  255.88  4911.1  254.89  4931.5  255.62
  4972.1  252.56  4977.2  253.77  4982.5  252.35 4986.28  251.18  4992.7  249.17
  4997.1  245.23  5015.8  246.96  5024.3   249.4  5030.4  247.45    5039  249.43
  5045.2  247.89  5059.9  253.43    5066  251.56  5074.6  253.24    5129   255.4
  5296.8  260.19  5439.3  266.72    5454  266.11  5495.9  268.92  5607.7  272.72
#Mann= 6 ,-1 , 0
  4515.3     .17       0  4755.8     .15       0  4982.5     .12       0
 4986.28     .09       0  5059.9     .15       0    5129     .11       0
#XS Ineff= 2 , 0
       0  4921.1   255.7               0
Permanent Ineff=
       F       F
Bank Sta=4986.28,5059.9
XS Rating Curve= 0 ,0
Exp/Cntr=0.3,0.1

Type RM Length L Ch R = 1 ,7847    ,497,497,497
BEGIN DESCRIPTION:
LITTLE LAKE CREEK TRIB NO 4 6.0
END DESCRIPTION:
XS GIS Cut Line= 3
      3754830.87     10152428.98      3755075.01     10152060.16
      3755559.49     10151585.85
#Sta/Elev= 30
  4557.7  264.22  4633.4  260.65  4720.7  258.27  4762.8  255.06  4777.9  255.26
  4783.9  254.31  4798.9  253.57  4853.3   251.8  4943.3  250.37  4958.4   250.7
  4973.4  250.02  4979.4  248.62  4986.9  244.71  4994.5  243.52  4996.3  242.02
  5008.4  243.42  5015.6   246.4  5022.6  247.45  5029.7  249.82  5036.7  246.11
  5043.8  249.99  5050.8  250.41    5058  249.73  5079.1  250.51    5157   249.9
  5199.4  251.34  5227.7  251.29  5298.3     253  5524.6  263.41    5678   267.2
#Mann= 4 ,-1 , 0
  4557.7     .17       0  4853.3     .11       0  4979.4     .06       0
  5022.6     .11       0
Bank Sta=4979.4,5022.6
XS Rating Curve= 0 ,0
Exp/Cntr=0.3,0.1

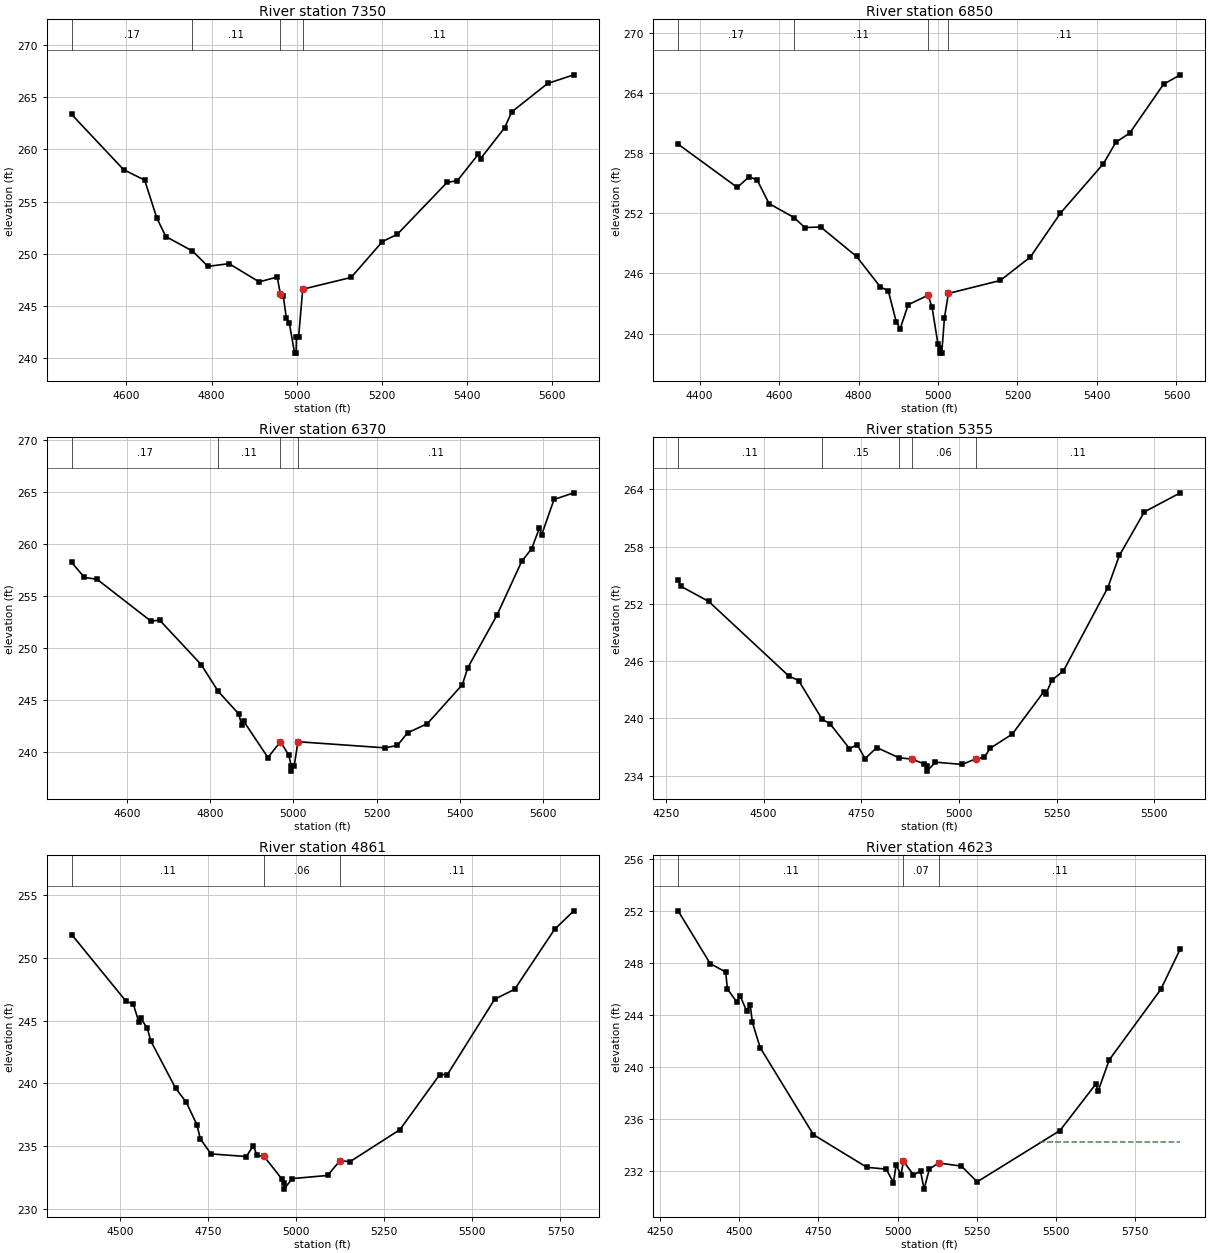
Type RM Length L Ch R = 1 ,7350    ,500,500,500
BEGIN DESCRIPTION:
LITTLE LAKE CREEK TRIB NO 4 7.0
END DESCRIPTION:
XS GIS Cut Line= 3
      3755125.92     10152611.78      3755496.39     10152235.02
      3755581.76     10151590.04
#Sta/Elev= 30
  4471.6  263.36  4593.7  258.06  4643.1  257.06  4671.4  253.44  4692.7  251.65
  4755.3  250.26  4791.7  248.79  4841.2  249.05  4911.9   247.3  4954.3  247.77
  4961.4  246.17  4968.4  245.96  4975.6  243.84  4982.6  243.36    4995  240.47
  4998.5  240.47  4999.3  242.05  5004.5  242.05  5014.1   246.6  5127.8  247.73
  5201.2  251.17    5236  251.86    5353  256.84  5377.2  257.01  5426.4  259.55
  5431.5  259.11  5488.2  262.09  5504.9  263.61    5589  266.33  5650.6  267.16
#Mann= 4 ,-1 , 0
  4471.6     .17       0  4755.3     .11       0  4961.4     .06       0
  5014.1     .11       0
#XS Ineff= 2 , 0
       0  4841.2  249.05               0
Permanent Ineff=
       F       F
Bank Sta=4961.4,5014.1
XS Rating Curve= 0 ,0
Exp/Cntr=0.3,0.1

Type RM Length L Ch R = 1 ,6850    ,480,480,480
BEGIN DESCRIPTION:
LITTLE LAKE CREEK TRIB NO 4 8.0
END DESCRIPTION:
XS GIS Cut Line= 3
      3755951.71     10152829.79      3755934.55     10152176.02
      3755702.88     10151612.05
#Sta/Elev= 30
    4346  258.89  4494.8  254.58  4524.8  255.64  4544.8  255.32  4574.8  252.97
  4637.9  251.57  4664.8  250.58  4704.8  250.63  4794.9   247.7  4854.9  244.66
  4874.9  244.27  4894.9  241.17  4904.9   240.5  4924.9  242.88  4974.9  243.83
  4984.9  242.66    5000  238.93  5005.6  238.56  5005.9  238.06  5009.4  238.06
  5016.2  241.59  5026.2  244.01  5156.7   245.3  5232.4  247.64    5308  252.01
  5416.2  256.94  5447.5  259.08  5482.3  259.99  5567.5  264.86  5609.7   265.8
#Mann= 4 ,-1 , 0
    4346     .17       0  4637.9     .11       0  4974.9     .06       0
  5026.2     .11       0
Bank Sta=4974.9,5026.2
XS Rating Curve= 0 ,0
Exp/Cntr=0.3,0.1

Type RM Length L Ch R = 1 ,6370    ,1015,1015,1015
BEGIN DESCRIPTION:
LITTLE LAKE CREEK TRIB NO 4 9.0
END DESCRIPTION:
XS GIS Cut Line= 3
      3756328.26     10152851.83      3756360.17     10152320.19
       3756611.8     10151694.81
#Sta/Elev= 30
  4467.4  258.22  4498.2  256.77  4528.3   256.6  4658.5  252.55  4678.5  252.68
  4778.7  248.38  4819.5  245.81  4868.9  243.64  4875.9  242.55  4880.9  242.93
    4939  239.44  4969.1  240.96  4989.1  239.67  4995.1  238.63  4995.3  238.13
  5002.2  238.63  5011.2  240.96  5220.8  240.37  5250.3  240.61  5274.5  241.81
  5322.4  242.71  5406.1  246.45  5419.4  248.09  5489.4  253.15  5548.8  258.32
  5572.7  259.54  5591.5  261.54  5596.9  260.89  5626.5  264.28  5674.1  264.92
#Mann= 4 ,-1 , 0
  4467.4     .17       0  4819.5     .11       0  4969.1     .06       0
  5011.2     .11       0
#XS Ineff= 2 , 0
       0  4880.9  242.93               0
Permanent Ineff=
       F       F
Bank Sta=4969.1,5011.2
XS Rating Curve= 0 ,0
Exp/Cntr=0.3,0.1

Type RM Length L Ch R = 1 ,5355    ,494,494,494
BEGIN DESCRIPTION:
LITTLE LAKE CREEK TRIB NO 4 10.0
END DESCRIPTION:
XS GIS Cut Line= 3
      3756962.45     10152869.38      3756988.78     10152151.06
      3756665.65     10151685.39
#Sta/Elev= 30
  4281.2  254.53  4288.3  253.84  4359.6  252.25  4564.9  244.42  4589.7  243.96
  4650.1  239.88  4669.8  239.44  4719.8  236.83  4739.8  237.21  4759.8  235.78
  4789.9  236.93  4846.5  235.86  4879.9  235.72  4909.9  235.23  4917.9  234.96
  4918.2  234.46    4940   235.4  5008.2  235.16    5044  235.76    5065  235.89
  5079.8  236.85  5136.6  238.34  5216.9  242.76    5223  242.56  5237.9  243.99
  5267.6  244.97  5381.1  253.69  5410.8  257.07  5474.7  261.64  5566.8  263.64
#Mann= 5 ,-1 , 0
  4281.2     .11       0  4650.1     .15       0  4846.5     .11       0
  4879.9     .06       0    5044     .11       0
Bank Sta=4879.9,5044
XS Rating Curve= 0 ,0
Exp/Cntr=0.3,0.1

Type RM Length L Ch R = 1 ,4861    ,238,238,238
BEGIN DESCRIPTION:
LITTLE LAKE CREEK TRIB NO 4 11.0
END DESCRIPTION:
XS GIS Cut Line= 3
        3757379.     10152865.09      3757424.98     10152230.46
      3756878.74     10151662.64
#Sta/Elev= 30
  4363.7  251.88  4518.1  246.55  4538.2  246.35  4554.3   244.9  4559.3  245.23
  4578.3  244.39  4588.3  243.38  4658.5  239.62  4688.6  238.51  4718.7  236.72
  4728.7  235.58  4758.8  234.38    4859  234.17  4879.1  235.04  4889.1  234.26
  4909.1  234.19  4959.3   232.4  4965.4  232.07  4965.7  231.57  4989.4  232.41
  5089.5  232.66  5124.7  233.84    5153  233.76  5294.5  236.31  5407.7  240.71
  5429.1   240.7  5563.4  246.72    5620  247.51  5733.2  252.29  5787.9  253.77
#Mann= 3 ,-1 , 0
  4363.7     .11       0  4909.1     .06       0  5124.7     .11       0
#XS Ineff= 2 , 0
       0  4879.1  235.04               0
Permanent Ineff=
       F       F
Bank Sta=4909.1,5124.7
XS Rating Curve= 0 ,0
Exp/Cntr=0.3,0.1

Type RM Length L Ch R = 1 ,4623    ,297,297,297
BEGIN DESCRIPTION:
LITTLE LAKE CREEK TRIB NO 4 11.5
END DESCRIPTION:
XS GIS Cut Line= 4
      3757407.17     10152863.15      3757658.96     10152217.52
      3757718.76     10152097.31       3758249.4     10151555.41
#Sta/Elev= 30
    4307  252.04  4408.2  247.98  4457.2  247.33  4462.6  246.03  4492.4  245.01
  4502.4  245.52  4523.9   244.3  4534.6  244.81  4541.4  243.46  4565.9  241.52
  4734.3  234.81  4902.8   232.3    4964  232.16    4987  231.12  4995.4   232.5
  5010.8   231.7  5018.4  232.77    5050  231.72  5072.4     232  5083.6  230.62
  5100.3  232.17  5129.4  232.63  5201.6  232.39  5251.2  231.18  5512.8  235.13
    5626  238.71    5633  238.16  5668.4  240.57    5831  245.99  5892.7  249.11
#Mann= 3 ,-1 , 0
    4307     .11       0  5018.4     .07       0  5129.4     .11       0
#XS Ineff= 2 , 0
       0                  5449.2       0  234.22
Permanent Ineff=
       F       F
Bank Sta=5018.4,5129.4
XS Rating Curve= 0 ,0
Exp/Cntr=0.3,0.1

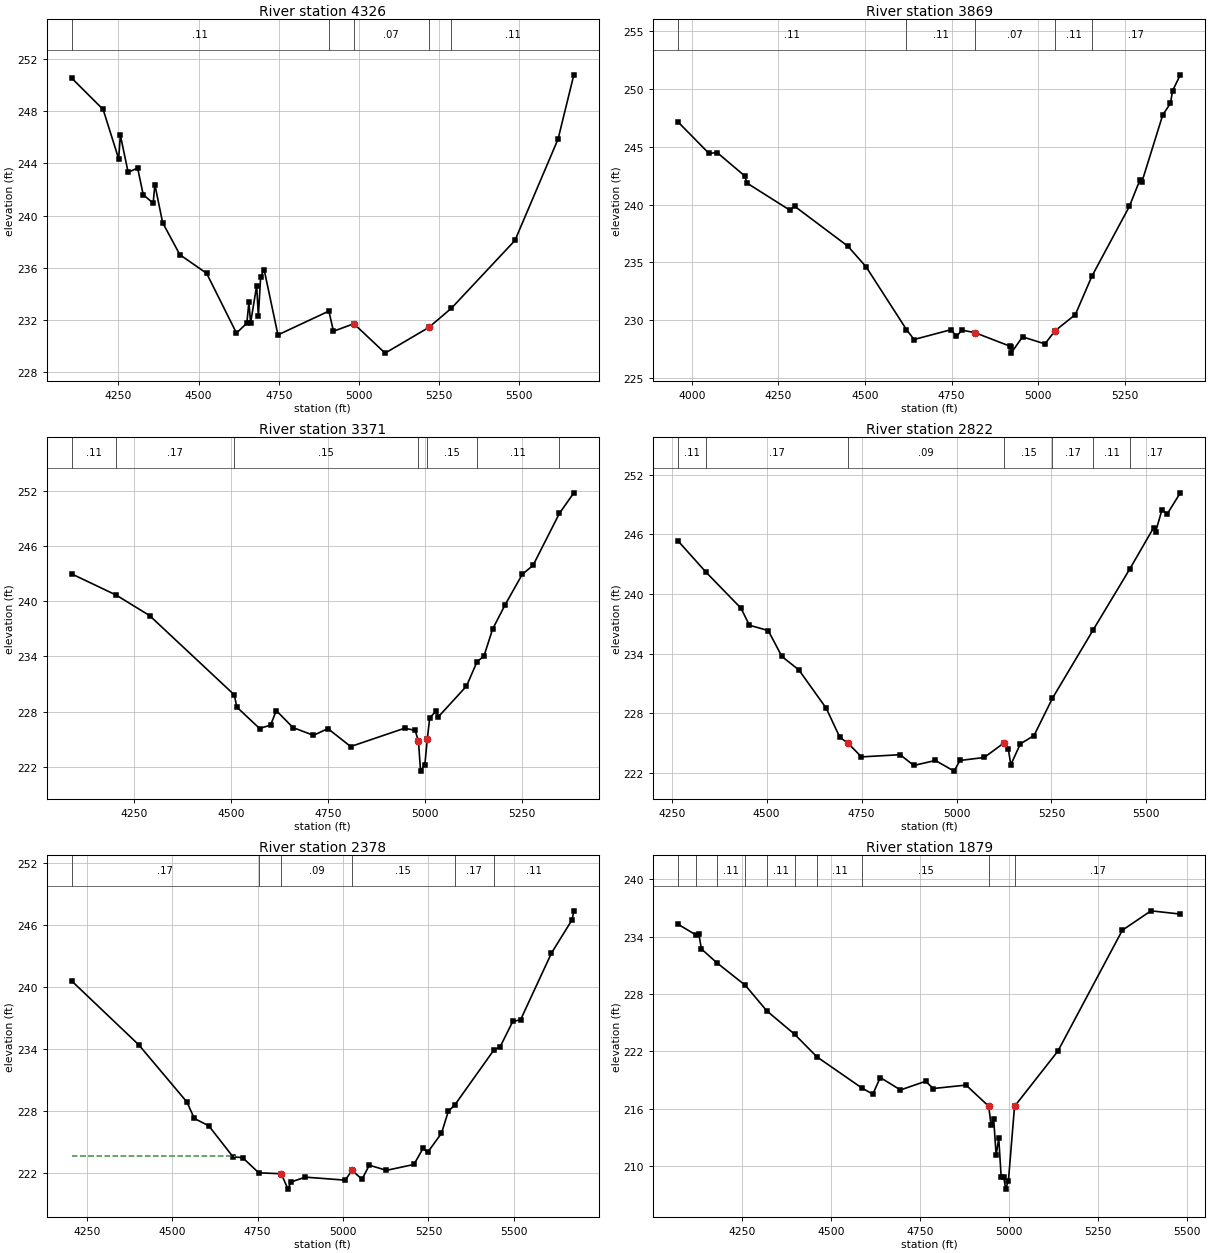
Type RM Length L Ch R = 1 ,4326    ,457,457,457
BEGIN DESCRIPTION:
LITTLE LAKE CREEK TRIB NO 4 12.0
END DESCRIPTION:
XS GIS Cut Line= 4
      3757506.65     10152878.19      3757754.43     10152260.62
      3757903.91     10152085.07      3758388.91     10151622.38
#Sta/Elev= 30
    4104  250.56  4202.2  248.15  4250.6  244.36    4256  246.17  4280.2  243.32
  4309.8  243.65  4327.2   241.6  4358.2  240.95  4363.6  242.37  4387.8  239.45
  4441.6  236.99    4525  235.56  4618.1  230.97  4650.4  231.73  4656.8  233.33
  4662.2  231.76    4681   234.6  4686.4  232.28  4693.5  235.29  4704.3  235.85
  4747.4  230.83  4906.3  232.66  4920.6  231.11  4984.2  231.69  5081.7  229.43
  5217.8   231.4  5288.5  232.88  5486.7  238.09    5621  245.87  5670.3  250.81
#Mann= 5 ,-1 , 0
    4104     .11       0  4906.3     .11       0  4984.2     .07       0
  5217.8     .11       0  5288.5     .11       0
#XS Ineff= 2 , 0
       0  4704.3  235.85               0
Permanent Ineff=
       F       F
Bank Sta=4984.2,5217.8
XS Rating Curve= 0 ,0
Exp/Cntr=0.3,0.1

Type RM Length L Ch R = 1 ,3869    ,498,498,498
BEGIN DESCRIPTION:
LITTLE LAKE CREEK TRIB NO 4 13.0
END DESCRIPTION:
XS GIS Cut Line= 3
      3757781.68     10152897.89      3758313.95     10152004.42
      3758506.54     10151641.33
#Sta/Elev= 30
    3960  247.14  4049.4  244.42  4072.7   244.5    4153  242.46  4158.8  241.86
  4282.2  239.52  4297.1  239.84  4450.9  236.38  4503.4  234.59  4619.8  229.17
  4641.7  228.31  4748.7  229.16  4764.3  228.57  4779.9  229.12  4816.9  228.91
  4918.1  227.74    4922  227.63  4922.2  227.13  4955.1  228.54  5019.9  227.93
  5049.1  229.06  5107.8  230.47  5155.5  233.79  5264.1  239.85  5294.4  242.14
  5300.1  241.96  5360.4  247.77  5382.4  248.75  5388.7  249.85    5411  251.23
#Mann= 5 ,-1 , 0
    3960     .11       0  4619.8     .11       0  4816.9     .07       0
  5049.1     .11       0  5155.5     .17       0
Bank Sta=4816.9,5049.1
XS Rating Curve= 0 ,0
Exp/Cntr=0.3,0.1

Type RM Length L Ch R = 1 ,3371    ,549,549,549
BEGIN DESCRIPTION:
LITTLE LAKE CREEK TRIB NO 4 14.0
END DESCRIPTION:
XS GIS Cut Line= 3
      3758259.15      10153045.4      3758716.81     10152256.78
      3758891.92     10151914.36
#Sta/Elev= 30
  4088.2  242.96  4203.6  240.65  4289.4  238.43    4508  229.82  4514.6  228.49
  4573.4  226.16  4601.9  226.54  4616.4  228.11  4659.7  226.26  4712.5  225.42
  4749.7  226.15  4808.5   224.2  4947.6  226.19  4974.9  225.96  4983.5  224.78
  4988.9  221.53    5000  222.23  5006.4  225.07  5012.6  227.32  5028.9  228.05
  5034.9  227.43  5107.5  230.77  5134.9  233.44  5152.4  234.01  5174.9  236.96
  5206.9  239.58  5251.4  242.91  5279.2  243.88  5347.4  249.54  5384.6  251.77
#Mann= 7 ,-1 , 0
  4088.2     .11       0  4203.6     .17       0    4508     .15       0
  4983.5     .09       0  5006.4     .15       0  5134.9     .11       0
  5347.4     .17       0
#XS Ineff= 2 , 0
       0  4616.4  228.11  5028.9       0  228.05
Permanent Ineff=
       F       F
Bank Sta=4983.5,5006.4
XS Rating Curve= 0 ,0
Exp/Cntr=0.3,0.1

Type RM Length L Ch R = 1 ,2822    ,444,444,444
BEGIN DESCRIPTION:
LITTLE LAKE CREEK TRIB NO 4 15.0
END DESCRIPTION:
XS GIS Cut Line= 3
      3758502.62     10153156.68      3758913.66     10152549.54
      3759115.27     10151995.69
#Sta/Elev= 30
  4266.8  245.32  4340.5  242.18  4432.2  238.58  4454.7  236.86  4504.1  236.33
    4540  233.73  4584.9  232.37  4656.8  228.53  4692.8   225.6  4713.8  225.03
  4749.7  223.64  4851.5  223.86  4887.5  222.78  4944.4  223.28  4993.6  222.21
    5009  223.28  5072.9  223.58  5126.1  225.07  5136.7   224.4  5142.9  222.84
  5168.2  224.95  5204.1  225.78  5252.7  229.53  5360.5  236.43  5455.7  242.47
  5519.2  246.66  5524.5  246.25  5541.1  248.46  5555.1  248.04  5589.4  250.16
#Mann= 7 ,-1 , 0
  4266.8     .11       0  4340.5     .17       0  4713.8     .09       0
  5126.1     .15       0  5252.7     .17       0  5360.5     .11       0
  5455.7     .17       0
Bank Sta=4713.8,5126.1
XS Rating Curve= 0 ,0
Exp/Cntr=0.3,0.1

Type RM Length L Ch R = 1 ,2378    ,499,499,499
BEGIN DESCRIPTION:
LITTLE LAKE CREEK TRIB NO 4 16.0
END DESCRIPTION:
XS GIS Cut Line= 3
      3758704.04     10153274.71      3759249.65     10152697.44
      3759172.84     10152026.12
#Sta/Elev= 30
  4205.7  240.58  4402.1  234.39  4543.3  228.84  4564.7  227.26  4607.2  226.54
    4678  223.54  4706.1  223.46  4753.4  221.99  4819.2   221.9  4838.9  220.41
  4847.5   221.1    4890  221.57  5006.4  221.28  5026.5  222.23  5055.7  221.36
  5076.9  222.73  5127.2  222.23  5207.7   222.8  5234.3  224.36    5248  223.98
  5288.2  225.82  5308.4  227.96  5326.7  228.54  5442.3  233.92  5459.3  234.16
  5497.1  236.66  5519.7  236.81  5610.3  243.28  5670.7  246.51  5675.7  247.37
#Mann= 6 ,-1 , 0
  4205.7     .17       0  4753.4     .11       0  4819.2     .09       0
  5026.5     .15       0  5326.7     .17       0  5442.3     .11       0
#XS Ineff= 2 , 0
       0  4684.9  223.65               0
Permanent Ineff=
       F       F
Bank Sta=4819.2,5026.5
XS Rating Curve= 0 ,0
Exp/Cntr=0.3,0.1

Type RM Length L Ch R = 1 ,1879    ,488,488,488
BEGIN DESCRIPTION:
LITTLE LAKE CREEK TRIB NO 4 17.0
END DESCRIPTION:
XS GIS Cut Line= 3
      3759047.75     10153403.22      3759725.24     10152767.71
      3759772.94     10152289.18
#Sta/Elev= 30
  4071.1   235.3    4122  234.17  4129.2   234.3  4136.5  232.72  4179.9  231.27
  4260.1   228.9  4320.3  226.23  4398.1  223.79  4460.6  221.43  4587.6  218.15
  4617.6  217.52  4638.6  219.26  4695.3  217.96  4766.1  218.87  4787.1  218.11
  4879.4  218.47  4942.9  216.26  4949.8  214.28  4957.1  214.87  4963.9  211.14
  4971.2  212.91  4978.1  208.81  4985.4  208.85  4990.5  207.58  4998.4  208.47
 5015.52  216.24  5137.3  222.03  5318.2  234.68  5398.6  236.71  5480.9  236.37
#Mann= 10 ,-1 , 0
  4071.1     .11       0    4122     .17       0  4179.9     .11       0
  4260.1     .17       0  4320.3     .11       0  4398.1     .17       0
  4460.6     .11       0  4587.6     .15       0  4942.9     .09       0
 5015.52     .17       0
#XS Ineff= 2 , 0
       0  4638.6  219.26               0
Permanent Ineff=
       F       F
Bank Sta=4942.9,5015.52
XS Rating Curve= 0 ,0
Exp/Cntr=0.3,0.1

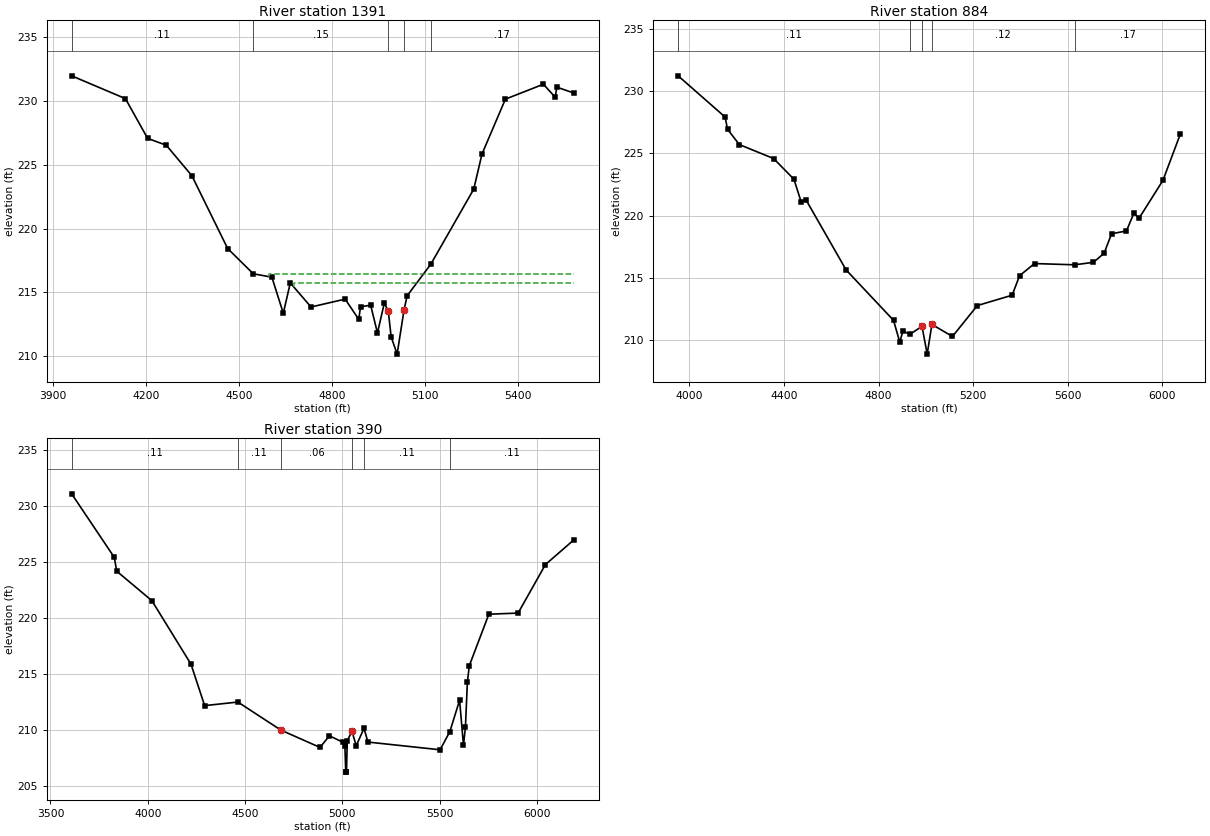
Type RM Length L Ch R = 1 ,1391    ,507,507,507
BEGIN DESCRIPTION:
LITTLE LAKE CREEK TRIB NO 4 18.0
END DESCRIPTION:
XS GIS Cut Line= 3
      3759183.59     10153469.34      3760103.05     10152983.77
      3759980.73     10152414.97
#Sta/Elev= 30
  3960.2  231.99  4133.8   230.2  4205.5  227.08  4265.8  226.54  4348.3  224.15
    4464  218.43  4546.5  216.45  4606.8  216.18  4643.6  213.35  4666.2  215.73
  4733.2  213.84  4843.3  214.46  4887.3  212.87    4893  213.86  4925.7  213.98
  4947.7   211.8  4969.8  214.15  4982.8   213.5  4991.8   211.5  5011.2  210.14
  5033.4   213.6  5043.5  214.72  5119.9   217.2  5258.5  223.09  5285.2  225.85
  5360.8  230.16  5483.5  231.33  5521.7  230.31  5526.8   231.1  5581.8  230.64
#Mann= 5 ,-1 , 0
  3960.2     .11       0  4546.5     .15       0  4982.8     .09       0
  5033.4     .15       0  5119.9     .17       0
#XS Ineff= 2 ,-1
  4678.5  4598.3   215.7  4598.3  4518.7  216.43
Permanent Ineff=
       F       F
Bank Sta=4982.8,5033.4
XS Rating Curve= 0 ,0
Exp/Cntr=0.3,0.1

Type RM Length L Ch R = 1 ,884     ,494,494,494
BEGIN DESCRIPTION:
LITTLE LAKE CREEK TRIB NO 4 19.0
END DESCRIPTION:
XS GIS Cut Line= 3
      3759209.61     10153506.22      3760254.38     10153427.86
        3760585.     10152404.54
#Sta/Elev= 30
  3952.3  231.22  4151.1  227.91  4161.1  226.93  4211.3   225.7    4356  224.58
  4441.9  222.92    4472  221.13  4493.1  221.26  4662.5  215.64  4863.1  211.59
  4889.2  209.85  4903.2  210.76  4931.4  210.46  4983.4  211.11  5005.3  208.88
  5025.2  211.26  5112.2   210.3  5217.3  212.78  5364.4  213.61    5396  215.18
    5459  216.15  5628.9  216.05  5708.3  216.25  5753.3  216.98  5784.8  218.54
  5847.8  218.77  5879.4  220.21  5900.4  219.77  6001.8  222.82  6075.4  226.54
#Mann= 5 ,-1 , 0
  3952.3     .11       0  4931.4     .12       0  4983.4     .08       0
  5025.2     .12       0  5628.9     .17       0
Bank Sta=4983.4,5025.2
XS Rating Curve= 0 ,0
Exp/Cntr=0.3,0.1

Type RM Length L Ch R = 1 ,390     ,0,0,0
BEGIN DESCRIPTION:
LITTLE LAKE CREEK TRIB NO 4 20.0
END DESCRIPTION:
XS GIS Cut Line= 4
      3759207.52     10153553.96      3760591.82     10153692.33
      3760625.89     10153641.29      3760709.73     10152515.37
#Sta/Elev= 30
  3608.8   231.1  3828.2  225.41  3840.3  224.18  4021.2  221.54  4222.2  215.86
  4292.5  212.15  4463.4  212.47  4684.5  209.96  4885.5  208.41  4933.9  209.45
  5004.7  208.86  5013.5  208.53  5017.9   206.2  5021.6   206.2  5025.7  209.01
  5049.6  209.86  5071.6  208.56  5111.7  210.12  5131.8  208.89  5502.8   208.2
  5552.9  209.82  5603.1  212.63  5623.1  208.59  5633.2  210.28  5643.2  214.28
  5653.2  215.73  5753.5  220.33  5903.9  220.43  6044.3  224.77  6190.4  226.98
#Mann= 6 ,-1 , 0
  3608.8     .11       0  4463.4     .11       0  4684.5     .06       0
  5049.6     .11       0  5111.7     .11       0  5552.9     .11       0
Bank Sta=4684.5,5049.6
XS Rating Curve= 0 ,0
Exp/Cntr=0.3,0.1

Chan Stop Cuts=-1
Use User Specified Reach Order=0
Composite Channel Slope=5