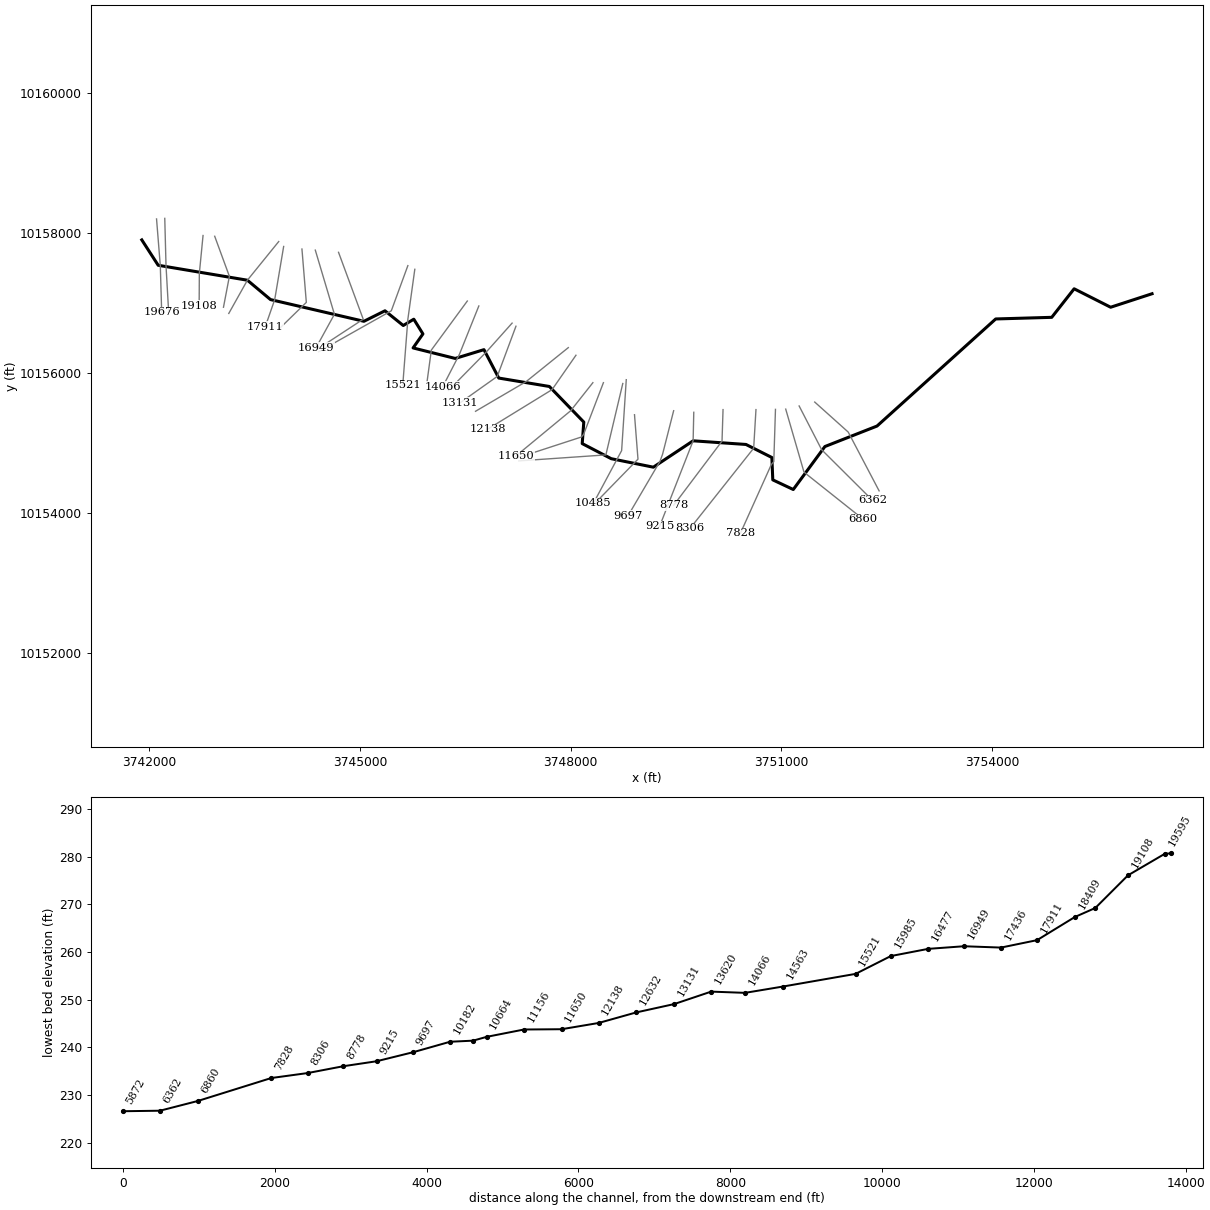
--- LITTLE LAKE CREEK TRIB NO 5.prj (project) ---

Proj Title=LITTLE LAKE CREEK TRIB NO 5 Base Level Engineering
Current Plan=p01
Default Exp/Contr=0.3,0.1
English Units
Geom File=g01
Flow File=f01
Plan File=p01
Y Axis Title=Elevation
X Axis Title(PF)=Main Channel Distance
X Axis Title(XS)=Station
BEGIN DESCRIPTION:
44LITTLE LAKE CREEK TRIB NO 5
END DESCRIPTION:
DSS Export Rating Curves= 0
DSS Export Rating Curve Sorted= 0
DSS Export Volume Flow Curves= 0
DXF OffsetX= 0
DXF OffsetY= 0
DXF ScaleX= 1
DXF ScaleY= 10

--- LITTLE LAKE CREEK TRIB NO 5.p01 (plan) ---

Plan Title=Multiple Run
Short Identifier=Multiple
Geom File=g01
Flow File=f01
Subcritical Flow
K Sum by GR= 0
Std Step Tol= 0.01
Critical Tol= 0.01
Num of Std Step Trials= 20
Max Error Tol= 0.3
Flow Tol Ratio= 0.001
Split Flow NTrial= 30
Split Flow Tol= 0.02
Split Flow Ratio= 0.02
Log Output Level= 0
Friction Slope Method= 1
Unsteady Friction Slope Method= 2
Unsteady Bridges Friction Slope Method= 1
Parabolic Critical Depth
Global Vel Dist=  1 , 1 , 1
Global Log Level= 0
CheckData=True
Encroach Param= -1, 0, 0, 0
BEGIN DESCRIPTION:
Multiple Run
END DESCRIPTION:

--- LITTLE LAKE CREEK TRIB NO 5.f01 (steady flow) ---

Flow Title=Multiple
Program Version=4.10
Number of Profiles= 7
Profile Names=10-year,25-year,50-year,1pct_min,100-year,1pct_plu,500-year
River Rch & RM=LITTLE LAKE CREE,Reach-1         ,19676
     338     443     584     255     770    2325    1376
River Rch & RM=LITTLE LAKE CREE,Reach-1         ,19108
     833    1151    1577     711    2146    6481    4109
River Rch & RM=LITTLE LAKE CREE,Reach-1         ,14563
     874    1201    1638     733    2215    6689    4193
River Rch & RM=LITTLE LAKE CREE,Reach-1         ,10664
    1673    2376    3311    1513    4568   13795    9006
River Rch & RM=LITTLE LAKE CREE,Reach-1         ,4402
    1881    2679    3741    1712    5170   15613   10224
River Rch & RM=LITTLE LAKE CREE,Reach-1         ,2469
    2076    2968    4157    1907    5759   17392   11441
Boundary for River Rch & Prof#=LITTLE LAKE CREE,Reach-1         , 1
Up Type= 0
Dn Type= 3
Dn Slope=0.002
Boundary for River Rch & Prof#=LITTLE LAKE CREE,Reach-1         , 2
Up Type= 0
Dn Type= 3
Dn Slope=0.002
Boundary for River Rch & Prof#=LITTLE LAKE CREE,Reach-1         , 3
Up Type= 0
Dn Type= 3
Dn Slope=0.002
Boundary for River Rch & Prof#=LITTLE LAKE CREE,Reach-1         , 4
Up Type= 0
Dn Type= 3
Dn Slope=0.002
Boundary for River Rch & Prof#=LITTLE LAKE CREE,Reach-1         , 5
Up Type= 0
Dn Type= 3
Dn Slope=0.002
Boundary for River Rch & Prof#=LITTLE LAKE CREE,Reach-1         , 6
Up Type= 0
Dn Type= 3
Dn Slope=0.002
Boundary for River Rch & Prof#=LITTLE LAKE CREE,Reach-1         , 7
Up Type= 0
Dn Type= 3
Dn Slope=0.002
DSS Import GetInterval= 0
DSS Import GetPeak= 0
DSS Import FillOption= 0

--- LITTLE LAKE CREEK TRIB NO 5.g01 (geometry) ---

Geom Title=Existing Conditions
Program Version=4.10

River Reach=LITTLE LAKE CREE,Reach-1
Reach XY= 30
      3741895.96      10157898.4      3742128.99     10157536.49
      3743399.13     10157323.23      3743728.23     10157046.84
      3745058.23     10156736.84      3745358.23     10156886.84
      3745618.23     10156676.84      3745768.23     10156766.84
      3745898.23     10156556.84      3745758.23     10156356.84
      3746358.23     10156206.84      3746767.19     10156332.25
      3746978.23     10155926.84      3747698.23     10155806.84
      3748188.49     10155298.72      3748166.04     10154991.83
       3748579.2     10154776.27      3749178.69     10154655.18
       3749745.1     10155031.48       3750497.7      10154979.4
      3750866.19      10154793.2      3750879.21     10154474.19
      3751170.84     10154336.58      3751620.91     10154949.58
      3752363.37     10155242.27      3754052.96      10156770.3
      3754850.61     10156793.49      3755169.61     10157200.73
      3755689.33     10156937.55      3756278.84     10157130.21

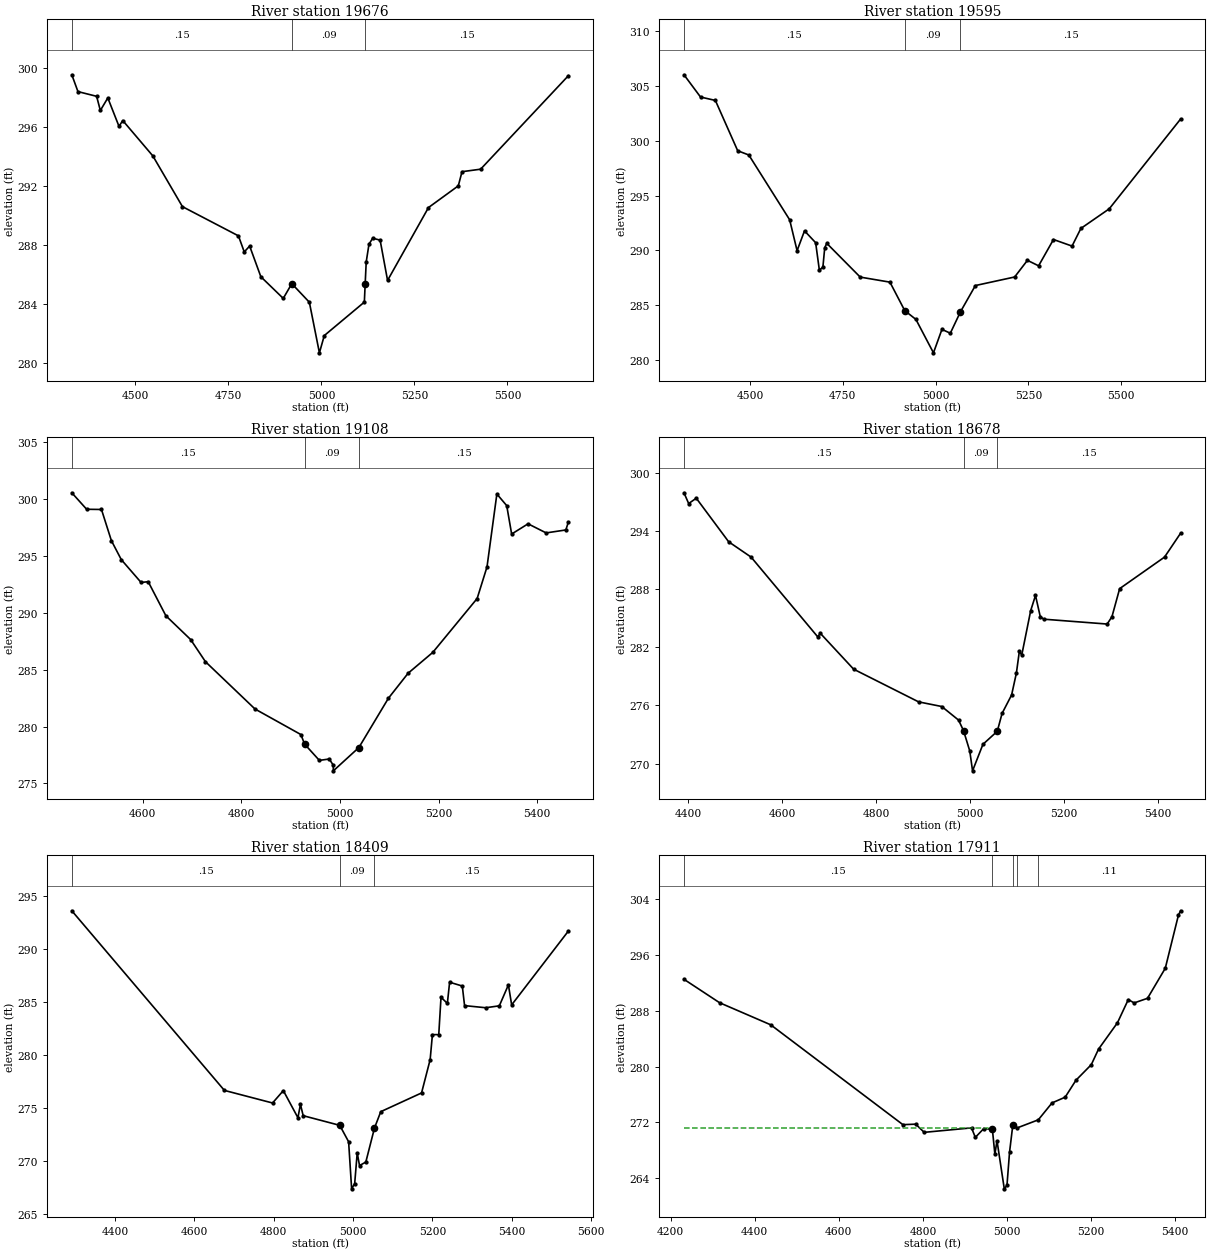
Type RM Length L Ch R = 1 ,19676   ,81,81,81
BEGIN DESCRIPTION:
LITTLE LAKE CREEK TRIB NO 5 39.0
END DESCRIPTION:
XS GIS Cut Line= 3
      3742105.81     10158197.53      3742159.37     10157528.67
      3742178.95     10156865.16
#Sta/Elev= 30
    4329  299.56  4345.5  298.42  4395.7   298.1  4405.7  297.14  4425.8  297.99
  4455.9  296.06  4465.9  296.46  4546.8  294.06  4626.4  290.62  4776.9  288.64
  4792.5  287.55    4807  287.95  4837.1  285.87  4897.3   284.4  4920.3   285.4
  4967.5  284.14  4994.5  280.71  5007.6  281.88  5115.3  284.15 5117.52  285.39
  5120.3  286.87  5127.7  288.07  5137.7  288.48  5157.7  288.35  5177.7  285.62
  5287.7  290.56  5367.8  292.03  5377.8  292.99  5427.8  293.16  5663.8   299.5
#Mann= 3 , 0 , 0
    4329     .15       0  4920.3     .09       0 5117.52     .15       0
#XS Ineff= 2 , 0
       0  4920.3   285.4               0
Permanent Ineff=
       F       F
Bank Sta=4920.3,5117.52
XS Rating Curve= 0 ,0
Exp/Cntr=0.3,0.1

Type RM Length L Ch R = 1 ,19595   ,487,487,487
BEGIN DESCRIPTION:
LITTLE LAKE CREEK TRIB NO 5 38.0
END DESCRIPTION:
XS GIS Cut Line= 3
      3742222.87     10158205.68      3742240.74     10157528.01
      3742278.15     10156869.17
#Sta/Elev= 30
  4322.1  306.02  4366.7  303.99  4406.7  303.68  4466.8  299.09  4496.8   298.7
  4606.8  292.79  4626.8  289.97  4646.8  291.78  4676.8   290.7  4686.8   288.2
  4696.3  288.46  4701.3  290.25  4706.8  290.64  4796.9  287.56  4876.9   287.1
  4916.9   284.5  4946.9   283.7  4994.2  280.65    5017  282.79  5039.6  282.44
    5067   284.4  5107.1  286.79  5212.9  287.57  5247.3  289.09  5277.4  288.59
  5317.5  290.99  5367.5  290.39  5391.3     292  5467.7  293.79  5659.9  301.98
#Mann= 3 , 0 , 0
  4322.1     .15       0  4916.9     .09       0    5067     .15       0
Bank Sta=4916.9,5067
XS Rating Curve= 0 ,0
Exp/Cntr=0.3,0.1

Type RM Length L Ch R = 1 ,19108   ,430,430,430
BEGIN DESCRIPTION:
LITTLE LAKE CREEK TRIB NO 5 37.0
END DESCRIPTION:
XS GIS Cut Line= 3
      3742767.85     10157961.03      3742714.93     10157419.41
      3742712.39     10156955.91
#Sta/Elev= 30
  4455.8  300.57  4485.9  299.12    4516   299.1  4536.1  296.36  4556.2  294.69
  4596.4  292.68  4610.8  292.75  4646.7  289.75  4696.9  287.66    4727  285.71
  4827.5  281.55  4920.7   279.3    4928  278.47  4958.1  277.03  4978.2  277.15
  4986.3  276.61  4986.5  276.11  5038.3  278.16  5098.3   282.5  5138.3   284.7
  5188.3  286.53  5278.3  291.27  5298.3  294.05  5318.3  300.46  5338.3  299.44
  5348.3  296.94  5381.6  297.84  5418.3  297.04  5458.3   297.3  5463.5  298.01
#Mann= 3 , 0 , 0
  4455.8     .15       0    4928     .09       0  5038.3     .15       0
Bank Sta=4928,5038.3
XS Rating Curve= 0 ,0
Exp/Cntr=0.3,0.1

Type RM Length L Ch R = 1 ,18678   ,269,269,269
BEGIN DESCRIPTION:
LITTLE LAKE CREEK TRIB NO 5 36.0
END DESCRIPTION:
XS GIS Cut Line= 3
      3742933.75     10157950.47      3743142.88     10157378.61
      3743058.75     10156937.46
#Sta/Elev= 30
  4391.1  297.92  4401.1  296.81  4417.3  297.36  4486.3  292.87  4534.1  291.29
  4676.1  283.07  4681.5  283.44  4752.5  279.74  4890.9  276.37  4940.3  275.89
  4976.1  274.49  4986.7   273.4    5000   271.3  5005.9  269.26    5028  271.99
  5058.6  273.34  5068.8  275.18  5089.1  277.08  5099.3  279.34  5105.7  281.61
  5110.7  281.19  5129.8  285.78    5140  287.34  5150.2  285.14  5157.8  284.89
  5292.7  284.39  5302.9  285.15  5319.3  288.04  5414.9  291.29  5449.1  293.75
#Mann= 3 , 0 , 0
  4391.1     .15       0  4986.7     .09       0  5058.6     .15       0
Bank Sta=4986.7,5058.6
XS Rating Curve= 0 ,0
Exp/Cntr=0.3,0.1

Type RM Length L Ch R = 1 ,18409   ,498,498,498
BEGIN DESCRIPTION:
LITTLE LAKE CREEK TRIB NO 5 35.0
END DESCRIPTION:
XS GIS Cut Line= 3
      3743845.21     10157874.95      3743399.13     10157323.23
      3743134.25     10156848.87
#Sta/Elev= 30
  4290.5  293.64  4675.4  276.67  4796.9  275.48  4824.1  276.65  4860.9  274.09
  4867.3  275.35  4874.2  274.28  4966.4  273.37  4988.8  271.82  4996.4  267.37
  5004.1  267.87  5010.5  270.77  5016.3  269.57  5032.2   269.9    5054  273.11
  5069.9  274.66  5172.8  276.43  5194.5  279.58  5200.2  281.94  5216.2  281.94
  5221.9  285.47  5237.9  284.89  5243.6  286.89  5275.6  286.53  5281.3  284.68
  5334.6  284.48    5369  284.66  5391.9  286.64  5400.1  284.75  5543.3  291.73
#Mann= 3 , 0 , 0
  4290.5     .15       0  4966.4     .09       0    5054     .15       0
#XS Ineff= 2 , 0
       0  4867.3  275.35               0
Permanent Ineff=
       F       F
Bank Sta=4966.4,5054
XS Rating Curve= 0 ,0
Exp/Cntr=0.3,0.1

Type RM Length L Ch R = 1 ,17911   ,475,475,475
BEGIN DESCRIPTION:
LITTLE LAKE CREEK TRIB NO 5 34.0
END DESCRIPTION:
XS GIS Cut Line= 3
      3743915.52     10157804.63      3743788.23     10157046.84
      3743652.68     10156656.72
#Sta/Elev= 30
  4231.6  292.48  4316.3  289.13    4438  285.97  4752.4  271.69  4782.8  271.76
  4803.1  270.59  4915.7  271.23  4924.7  269.87    4945  271.14  4965.3  271.01
  4971.2  267.47  4976.3  269.39  4993.6  262.51    5000  263.01  5006.1  267.75
  5013.9  271.65    5024  271.22  5074.5  272.38  5107.2   274.8  5138.4  275.62
  5164.2  278.05  5200.6  280.27  5217.8  282.49  5262.8  286.26  5288.6  289.58
  5302.5   289.1  5334.3  289.76  5376.6  294.06  5407.8  301.64    5413  302.28
#Mann= 5 ,-1 , 0
  4231.6     .15       0  4965.3     .09       0  5013.9     .15       0
    5024     .17       0  5074.5     .11       0
#XS Ineff= 2 , 0
       0  4955.2  271.15               0
Permanent Ineff=
       F       F
Bank Sta=4965.3,5013.9
XS Rating Curve= 0 ,0
Exp/Cntr=0.3,0.1

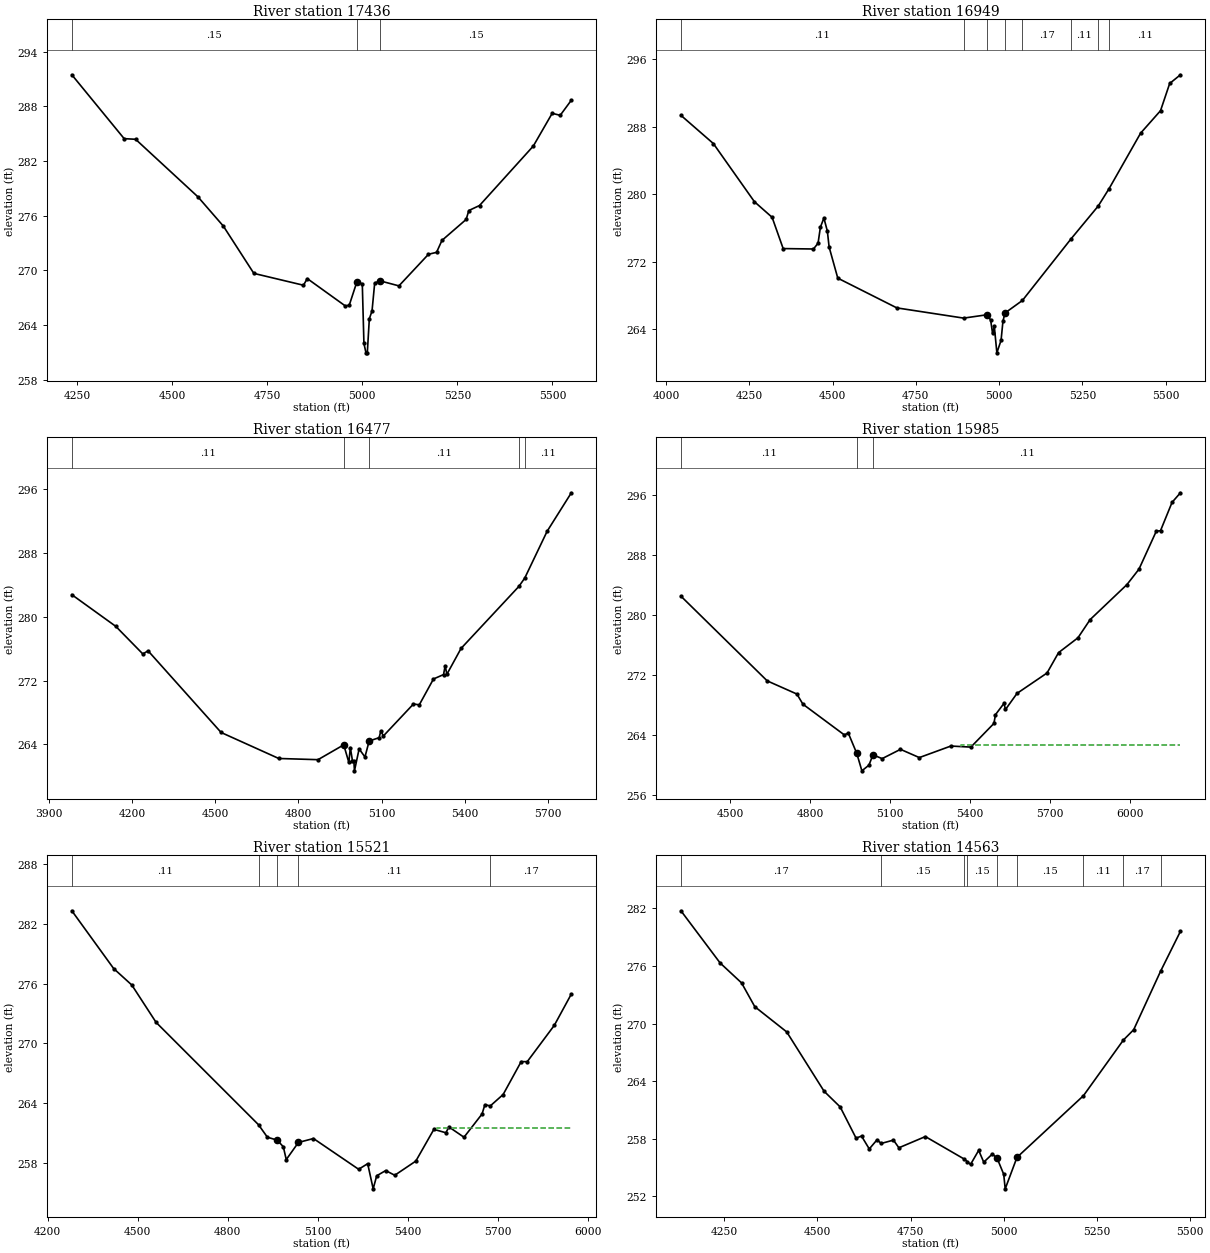
Type RM Length L Ch R = 1 ,17436   ,487,487,487
BEGIN DESCRIPTION:
LITTLE LAKE CREEK TRIB NO 5 33.0
END DESCRIPTION:
XS GIS Cut Line= 3
      3744175.93      10157768.2      3744238.23     10157006.84
      3743845.23     10156622.36
#Sta/Elev= 30
  4236.1  291.47  4373.7  284.46  4403.8  284.39  4567.8  278.07  4634.6  274.86
  4714.8  269.67  4845.3  268.37  4855.3   269.1  4955.6  266.09  4965.7  266.18
  4985.7  268.73    5000  268.53  5004.3  261.98  5009.7  260.95  5013.2  260.95
  5018.5  264.69  5025.6  265.55  5032.6  268.61  5046.7  268.85  5096.3   268.3
  5174.1  271.77  5195.3  271.98  5209.5  273.29  5273.1  275.59  5280.2  276.57
  5308.3  277.12  5449.8  283.65  5499.4  287.24  5520.5  287.02  5549.8  288.68
#Mann= 3 , 0 , 0
  4236.1     .15       0  4985.7     .09       0  5046.7     .15       0
Bank Sta=4985.7,5046.7
XS Rating Curve= 0 ,0
Exp/Cntr=0.3,0.1

Type RM Length L Ch R = 1 ,16949   ,472,472,472
BEGIN DESCRIPTION:
LITTLE LAKE CREEK TRIB NO 5 32.0
END DESCRIPTION:
XS GIS Cut Line= 3
      3744366.04     10157752.55      3744638.23     10156836.84
      3744376.44     10156359.29
#Sta/Elev= 30
  4044.7  289.34  4142.1     286  4265.3  279.12  4318.5  277.27  4351.7  273.57
  4442.7  273.52  4456.5  274.21  4463.5   276.1    4474  277.18  4484.4  275.64
  4489.7  273.75  4515.7  270.07    4693  266.55  4893.7  265.34  4964.3  265.74
  4974.7  265.11  4980.5  263.52  4985.7  264.38  4993.4  261.23    5006  262.71
  5011.7  264.99    5018  265.95  5070.1  267.43  5215.1  274.67  5297.6   278.6
  5330.3  280.66    5425  287.23  5484.8  289.89  5512.3  293.11  5544.6  294.14
#Mann= 8 ,-1 , 0
  4044.7     .11       0  4893.7     .17       0  4964.3     .09       0
    5018     .11       0  5070.1     .17       0  5215.1     .11       0
  5297.6     .17       0  5330.3     .11       0
Bank Sta=4964.3,5018
XS Rating Curve= 0 ,0
Exp/Cntr=0.3,0.1

Type RM Length L Ch R = 1 ,16477   ,492,492,492
BEGIN DESCRIPTION:
LITTLE LAKE CREEK TRIB NO 5 31.0
END DESCRIPTION:
XS GIS Cut Line= 3
      3744696.77     10157721.29      3745048.23     10156766.84
       3744392.6     10156336.22
#Sta/Elev= 30
  3982.9  282.77  4141.4   278.8  4238.9  275.34  4257.9  275.73  4521.3  265.49
  4729.2  262.23  4870.8  262.08  4963.5  263.94    4982  261.73  4987.3   263.6
  4995.1  261.92    5000  261.92  5002.2  260.68    5019  263.43  5040.1  262.42
  5055.2  264.42  5091.3  264.84  5097.3   265.7  5106.4  265.05  5214.9  269.06
    5236  268.96  5287.2   272.2  5323.4  272.75  5329.4  273.87  5335.4  272.78
  5386.6  276.03    5595   283.8  5616.3  284.85    5697  290.72  5784.4  295.55
#Mann= 5 ,-1 , 0
  3982.9     .11       0  4963.5     .07       0  5055.2     .11       0
    5595     .17       0  5616.3     .11       0
#XS Ineff= 2 , 0
       0                  5097.3       0   265.7
Permanent Ineff=
       F       F
Bank Sta=4963.5,5055.2
XS Rating Curve= 0 ,0
Exp/Cntr=0.3,0.1

Type RM Length L Ch R = 1 ,15985   ,464,464,464
BEGIN DESCRIPTION:
LITTLE LAKE CREEK TRIB NO 5 30.0
END DESCRIPTION:
XS GIS Cut Line= 3
      3745683.73     10157531.15      3745448.23     10156886.84
      3744412.89     10156302.01
#Sta/Elev= 30
    4314  282.49  4637.9  271.18  4749.4  269.42  4771.9  268.07  4927.3  263.97
  4942.3  264.21  4974.2  261.49  4993.3  259.17  5019.8  259.93  5034.9  261.31
  5069.3   260.8  5138.2  262.04  5208.9  260.94  5327.3  262.48  5402.4  262.34
    5489   265.5  5494.8  266.67  5526.6  268.17  5532.4  267.36  5575.7  269.51
  5688.3  272.23  5731.6  274.95  5804.4  276.93  5850.1  279.36  5988.2  284.03
  6033.4  286.09  6098.4  291.16  6114.3  291.23  6157.6  295.01  6189.1  296.29
#Mann= 3 , 0 , 0
    4314     .11       0  4974.2     .07       0  5034.9     .11       0
#XS Ineff= 2 , 0
       0                  5364.9       0  262.66
Permanent Ineff=
       F       F
Bank Sta=4974.2,5034.9
XS Rating Curve= 0 ,0
Exp/Cntr=0.3,0.1

Type RM Length L Ch R = 1 ,15521   ,958,958,958
BEGIN DESCRIPTION:
LITTLE LAKE CREEK TRIB NO 5 29.0
END DESCRIPTION:
XS GIS Cut Line= 3
      3745782.71     10157479.12       3745683.9     10156766.84
      3745610.95     10155824.46
#Sta/Elev= 30
  4280.9  283.29  4420.3   277.5  4480.8  275.85  4561.6  272.11    4903  261.85
  4932.5   260.6  4965.4  260.31  4985.6  259.64  4995.3  258.36  5035.9  260.08
    5086  260.47  5236.5  257.39  5266.6  257.95  5284.9  255.43  5296.7  256.74
  5326.7  257.26  5356.8  256.79    5427  258.21  5487.2  261.39  5527.1  261.05
  5537.4  261.63  5587.5   260.6  5647.7  262.93  5657.1  263.86  5675.2  263.74
  5717.9  264.88  5778.1  268.18  5798.2  268.17  5888.4  271.81  5945.2  274.95
#Mann= 5 ,-1 , 0
  4280.9     .11       0    4903     .15       0  4965.4     .09       0
  5035.9     .11       0  5675.2     .17       0
#XS Ineff= 2 , 0
       0                  5497.3       0  261.57
Permanent Ineff=
       F       F
Bank Sta=4965.4,5035.9
XS Rating Curve= 0 ,0
Exp/Cntr=0.3,0.1

Type RM Length L Ch R = 1 ,14563   ,497,497,497
BEGIN DESCRIPTION:
LITTLE LAKE CREEK TRIB NO 5 28.0
END DESCRIPTION:
XS GIS Cut Line= 3
      3746530.11     10157025.99      3746018.23     10156326.84
      3745954.58     10155856.73
#Sta/Elev= 30
  4133.5  281.76  4238.7  276.32  4296.3  274.24  4331.8  271.76  4417.5  269.13
  4517.9  262.94    4561  261.31  4603.6  258.06  4618.3  258.27  4639.1  256.93
  4660.1  257.89  4670.9   257.5    4704  257.85  4718.6  257.05  4789.7  258.22
  4894.6  255.86  4902.3  255.61  4910.9  255.31  4932.8  256.78  4946.4  255.55
  4969.5   256.4  4982.4  255.95    5000  254.29    5004  252.77  5035.6  256.05
    5214  262.48  5321.2  268.28  5348.9  269.36  5420.9  275.44  5474.4  279.62
#Mann= 9 ,-1 , 0
  4133.5     .17       0  4670.9     .15       0  4894.6     .11       0
  4902.3     .15       0  4982.4     .09       0  5035.6     .15       0
    5214     .11       0  5321.2     .17       0  5420.9     .11       0
Bank Sta=4982.4,5035.6
XS Rating Curve= 0 ,0
Exp/Cntr=0.3,0.1

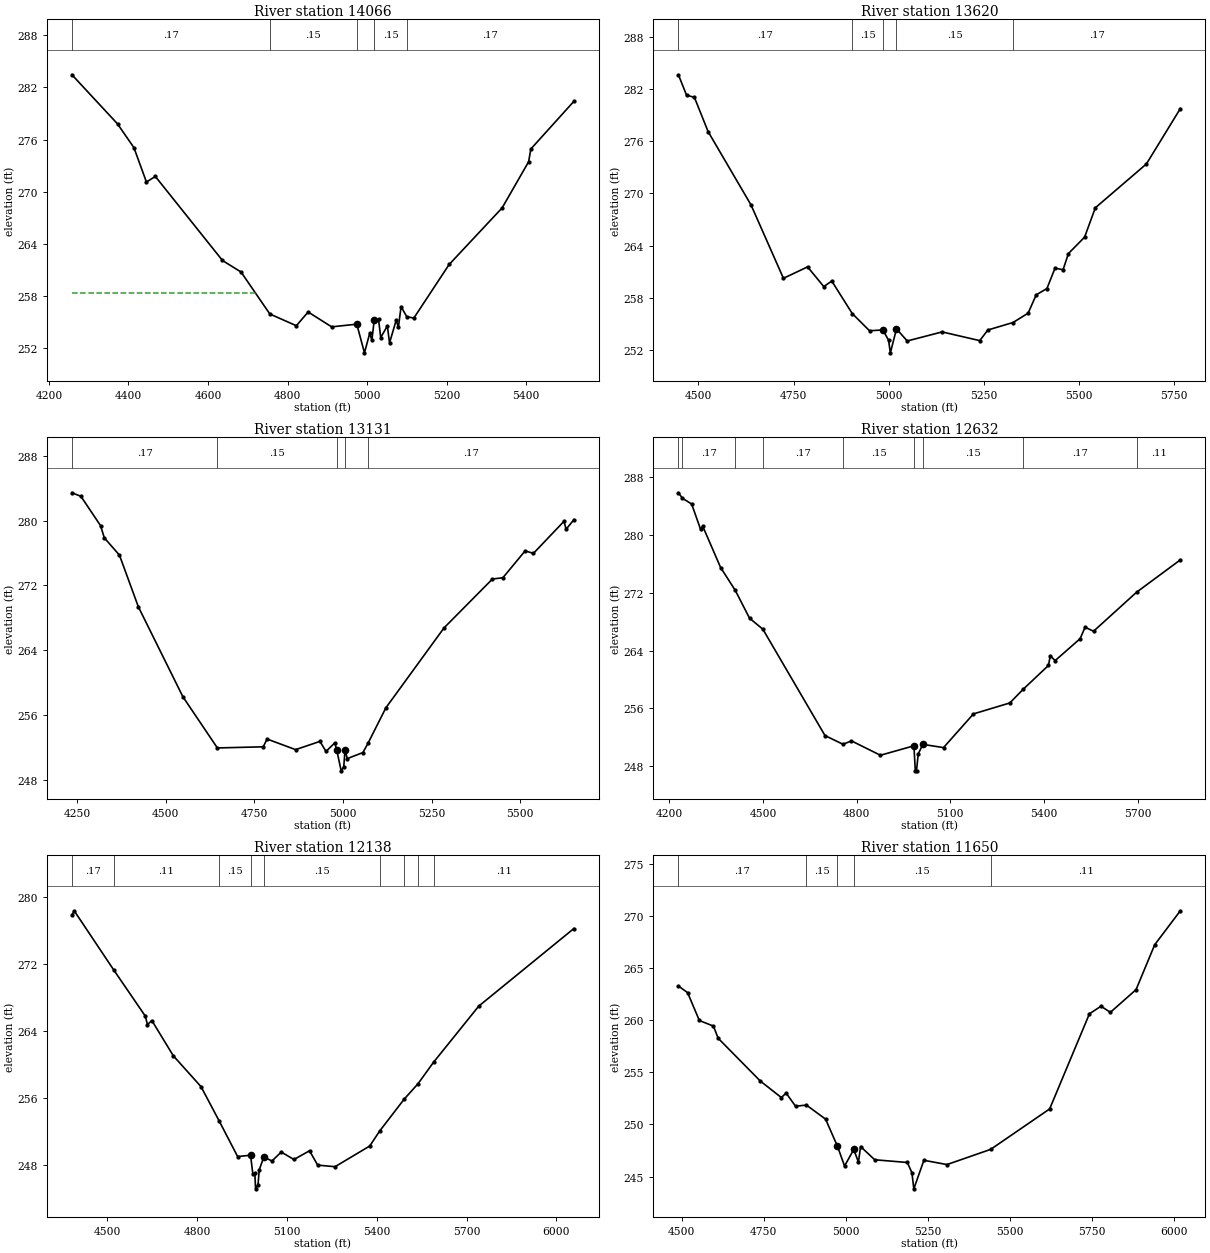
Type RM Length L Ch R = 1 ,14066   ,446,446,446
BEGIN DESCRIPTION:
LITTLE LAKE CREEK TRIB NO 5 27.0
END DESCRIPTION:
XS GIS Cut Line= 3
      3746694.15     10156955.63      3746418.23     10156266.84
      3746181.13     10155804.61
#Sta/Elev= 30
    4258  283.45  4372.5   277.8  4413.7  275.07  4445.2  271.11  4467.6  271.75
  4636.3  262.08    4683  260.75  4755.4  255.92    4822  254.57  4851.6  256.15
  4910.8  254.44  4973.9  254.75  4993.2  251.45  5006.3  253.68  5011.9  252.92
  5017.7  255.21  5028.5  255.32  5034.1  253.21  5050.7  254.54  5056.3   252.6
  5072.9   255.2  5078.5  254.39  5085.2  256.77  5099.5  255.61  5117.3  255.45
  5206.1  261.62  5339.2  268.13  5405.8  273.44  5411.4  274.91  5519.5  280.39
#Mann= 5 ,-1 , 0
    4258     .17       0  4755.4     .15       0  4973.9     .09       0
  5017.7     .15       0  5099.5     .17       0
#XS Ineff= 2 , 0
       0  4719.7  258.39               0
Permanent Ineff=
       F       F
Bank Sta=4973.9,5017.7
XS Rating Curve= 0 ,0
Exp/Cntr=0.3,0.1

Type RM Length L Ch R = 1 ,13620   ,489,489,489
BEGIN DESCRIPTION:
LITTLE LAKE CREEK TRIB NO 5 26.0
END DESCRIPTION:
XS GIS Cut Line= 3
      3747167.83     10156711.05      3746799.99      10156298.4
      3746262.33     10155750.41
#Sta/Elev= 30
  4447.2  283.61  4468.5  281.28  4489.4  281.01  4525.3  277.09  4638.2  268.68
  4723.5  260.26    4787  261.57  4829.7  259.31  4850.6  259.95  4904.5  256.22
  4950.1  254.24  4985.2  254.34    5000  253.16  5004.9  251.71  5020.9  254.46
  5049.2  253.07    5141  254.11    5240  253.11  5261.3  254.33  5327.6  255.19
  5367.3  256.26  5388.5  258.36  5416.8  259.09  5438.1  261.43  5459.2  261.24
  5473.3   263.1  5515.8  264.98  5544.1  268.35  5678.5  273.38  5767.7  279.73
#Mann= 5 ,-1 , 0
  4447.2     .17       0  4904.5     .15       0  4985.2     .09       0
  5020.9     .15       0  5327.6     .17       0
Bank Sta=4985.2,5020.9
XS Rating Curve= 0 ,0
Exp/Cntr=0.3,0.1

Type RM Length L Ch R = 1 ,13131   ,499,499,499
BEGIN DESCRIPTION:
LITTLE LAKE CREEK TRIB NO 5 25.0
END DESCRIPTION:
XS GIS Cut Line= 3
      3747222.82     10156666.65      3746956.57     10155950.33
      3746425.93     10155572.86
#Sta/Elev= 30
  4235.8  283.46  4261.1  283.02  4316.4   279.4  4327.1  277.89  4369.8  275.75
  4423.1  269.36  4548.6  258.25  4645.9  251.92  4775.2  252.06  4786.1  253.02
  4866.5  251.71  4935.2  252.73  4952.2  251.49  4977.2  252.55  4982.6  251.64
    4995  249.09  5002.3  249.59    5006  251.71  5012.1   250.6  5056.4  251.35
  5071.1  252.53  5121.1  256.88  5285.1  266.76  5421.6   272.8  5451.1  272.96
  5513.8  276.28  5537.2  275.97  5623.3  279.93  5629.4  278.95  5651.2  280.13
#Mann= 5 ,-1 , 0
  4235.8     .17       0  4645.9     .15       0  4982.6     .09       0
    5006     .15       0  5071.1     .17       0
Bank Sta=4982.6,5006
XS Rating Curve= 0 ,0
Exp/Cntr=0.3,0.1

Type RM Length L Ch R = 1 ,12632   ,494,494,494
BEGIN DESCRIPTION:
LITTLE LAKE CREEK TRIB NO 5 24.0
END DESCRIPTION:
XS GIS Cut Line= 3
      3747967.83     10156361.05      3747368.23     10155876.84
      3746647.26     10155453.05
#Sta/Elev= 30
  4229.3  285.88  4242.2  285.12  4271.7  284.32  4300.4   280.8  4306.9  281.27
  4364.4  275.52  4411.4  272.35  4457.1  268.49  4499.7  266.97  4698.6  252.23
  4756.3  251.02  4783.4  251.49  4876.1   249.5  4983.3  250.81  4987.8  247.34
  4991.6  247.34    4997  249.67    5012  251.01  5078.1  250.56  5173.9  255.23
  5290.4  256.75  5332.6  258.62  5414.1  261.95  5419.9  263.29  5435.5  262.62
  5515.6  265.66  5531.3  267.25  5558.5  266.69  5696.6  272.11  5836.3  276.58
#Mann= 9 ,-1 , 0
  4229.3     .11       0  4242.2     .17       0  4411.4     .11       0
  4499.7     .17       0  4756.3     .15       0  4983.3     .09       0
    5012     .15       0  5332.6     .17       0  5696.6     .11       0
Bank Sta=4983.3,5012
XS Rating Curve= 0 ,0
Exp/Cntr=0.3,0.1

Type RM Length L Ch R = 1 ,12138   ,488,488,488
BEGIN DESCRIPTION:
LITTLE LAKE CREEK TRIB NO 5 23.0
END DESCRIPTION:
XS GIS Cut Line= 4
      3748076.96     10156252.53      3747743.66     10155771.65
      3747718.23      10155750.3      3746817.25     10155195.68
#Sta/Elev= 30
  4381.7  277.77  4389.2   278.3  4521.1  271.25  4626.8  265.73  4633.8  264.73
  4648.7   265.2  4720.3     261  4812.8  257.32  4873.2  253.24  4935.1  248.98
  4978.2  249.14    4986  246.87  4992.5  246.98    4995  245.13  5003.2  245.63
  5007.2   247.4  5022.6  248.93  5049.8  248.45  5080.6  249.52  5123.1  248.63
  5175.2  249.67  5202.4  247.96  5260.4  247.77  5376.3  250.24  5409.7  252.04
  5490.9  255.81  5537.8  257.68  5589.4  260.23  5740.2  266.92    6058  276.18
#Mann= 9 ,-1 , 0
  4381.7     .17       0  4521.1     .11       0  4873.2     .15       0
  4978.2     .09       0  5022.6     .15       0  5409.7     .17       0
  5490.9     .15       0  5537.8     .17       0  5589.4     .11       0
Bank Sta=4978.2,5022.6
XS Rating Curve= 0 ,0
Exp/Cntr=0.3,0.1

Type RM Length L Ch R = 1 ,11650   ,494,494,494
BEGIN DESCRIPTION:
LITTLE LAKE CREEK TRIB NO 5 22.0
END DESCRIPTION:
XS GIS Cut Line= 3
      3748317.86     10155861.08       3748002.2     10155460.89
      3747217.82     10154811.05
#Sta/Elev= 30
  4490.3  263.29  4518.3  262.65    4554  259.98  4596.9  259.44  4611.4  258.27
  4739.6  254.17  4803.8  252.58  4818.2  253.02  4846.9  251.75  4880.1  251.86
  4938.4  250.51  4974.3  247.93  4996.2  246.01  5024.2   247.6  5038.5  246.38
    5045  247.88    5088  246.61  5187.4  246.35  5201.3  245.37  5207.1  243.82
  5237.8  246.56  5308.1  246.15  5441.2  247.61  5620.7  251.49  5741.8  260.62
    5777  261.35  5805.6  260.76  5883.8  262.94  5940.6  267.25  6018.6  270.51
#Mann= 5 ,-1 , 0
  4490.3     .17       0  4880.1     .15       0  4974.3     .09       0
  5024.2     .15       0  5441.2     .11       0
#XS Ineff= 2 , 0
       0                  5550.4       0  249.89
Permanent Ineff=
       F       F
Bank Sta=4974.3,5024.2
XS Rating Curve= 0 ,0
Exp/Cntr=0.3,0.1

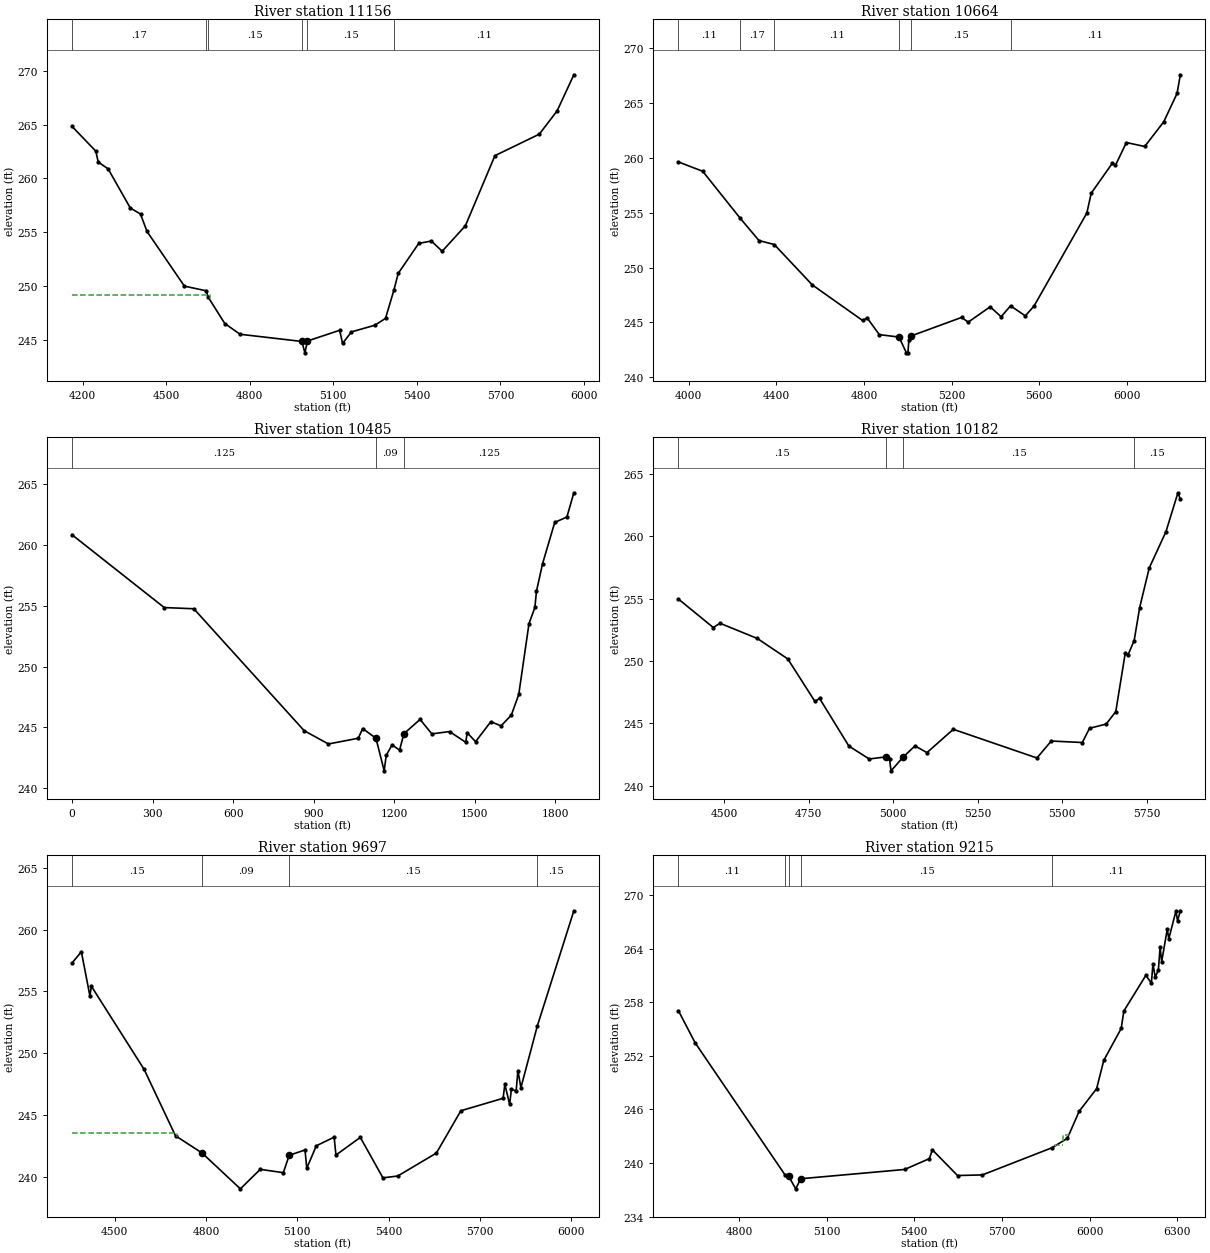
Type RM Length L Ch R = 1 ,11156   ,492,492,492
BEGIN DESCRIPTION:
LITTLE LAKE CREEK TRIB NO 5 21.0
END DESCRIPTION:
XS GIS Cut Line= 4
      3748467.84     10155861.05      3748186.26     10155123.68
      3748154.39     10155085.81      3747238.39     10154786.39
#Sta/Elev= 30
  4161.2  264.85  4246.8  262.54  4255.7  261.52  4291.1  260.89  4370.7  257.25
  4407.4  256.68  4430.8  255.06  4565.1  249.97  4642.9  249.54  4650.3  248.95
  4710.1  246.49  4764.9  245.49  4986.7  244.82  4997.8  243.76  5006.9  244.86
  5122.6  245.86  5133.1  244.64    5165  245.71  5248.9  246.33  5287.3  246.97
  5317.7  249.62    5333  251.16  5406.7  253.95  5451.9  254.17  5490.8  253.22
  5574.1  255.59  5680.3  262.12  5839.6  264.12  5903.4  266.28  5963.7  269.65
#Mann= 6 ,-1 , 0
  4161.2     .17       0  4642.9     .11       0  4650.3     .15       0
  4986.7     .09       0  5006.9     .15       0  5317.7     .11       0
#XS Ineff= 2 , 0
       0  4655.3  249.14               0
Permanent Ineff=
       F       F
Bank Sta=4986.7,5006.9
XS Rating Curve= 0 ,0
Exp/Cntr=0.3,0.1

Type RM Length L Ch R = 1 ,10664   ,179,179,179
BEGIN DESCRIPTION:
LITTLE LAKE CREEK TRIB NO 5 20.0
END DESCRIPTION:
XS GIS Cut Line= 3
      3748743.65     10155848.91      3748502.86     10154830.49
      3747262.32     10154744.76
#Sta/Elev= 30
  3953.5  259.63  4064.3  258.78    4236  254.48  4321.2  252.46  4390.8   252.1
  4564.1  248.42  4793.9  245.17  4814.4  245.41  4870.3  243.88    4960  243.66
  4993.6  242.22  5000.6  242.22    5005   243.4    5015  243.76  5245.6  245.45
  5275.7  245.02  5375.9  246.42    5426  245.51  5468.8  246.51  5536.3  245.59
  5576.4   246.5    5817  254.97    5837  256.78  5933.3  259.51  5947.3  259.31
  5997.4   261.4    6081  261.04  6167.8  263.29  6228.7  265.88  6243.5  267.58
#Mann= 6 ,-1 , 0
  3953.5     .11       0    4236     .17       0  4390.8     .11       0
    4960     .09       0    5015     .15       0  5468.8     .11       0
Bank Sta=4960,5015
XS Rating Curve= 0 ,0
Exp/Cntr=0.3,0.1

Type RM Length L Ch R = 1 ,10485   ,303,303,303
XS GIS Cut Line= 3
       3748793.2     10155903.91      3748727.23     10154891.76
      3748324.45     10154138.29
#Sta/Elev= 30
       0  260.84   343.6  254.85   453.8  254.75   864.7  244.72   954.9  243.63
  1066.1   244.1  1082.3   244.9  1131.9   244.1  1162.5  241.42  1170.1   242.7
  1192.1  243.56  1219.7  243.12  1235.9  244.47  1296.1  245.65    1340  244.46
  1405.8  244.65    1466  243.77  1471.7  244.55  1502.7  243.82  1559.5  245.46
  1597.7  245.12  1635.9     246  1663.5   247.7  1701.7  253.53  1723.7  254.86
  1729.4  256.18  1752.1  258.45  1797.5  261.85  1842.8   262.3  1868.7  264.29
#Mann= 3 , 0 , 0
       0    .125       0  1131.9     .09       0  1235.9    .125       0
Bank Sta=1131.9,1235.9
XS Rating Curve= 0 ,0
Exp/Cntr=0.3,0.1

Type RM Length L Ch R = 1 ,10182   ,485,485,485
BEGIN DESCRIPTION:
LITTLE LAKE CREEK TRIB NO 5 19.0
END DESCRIPTION:
XS GIS Cut Line= 3
      3748910.52     10155403.84      3748959.94     10154769.76
      3748367.82     10154161.04
#Sta/Elev= 30
    4364  254.96  4467.1  252.68  4487.1  253.02  4597.5   251.8  4687.7  250.16
    4768  246.75  4781.6     247  4868.3  243.18  4928.5  242.14  4978.6  242.31
  4988.7  242.11  4993.3  241.19  5028.8  242.29  5064.2  243.19  5099.5  242.65
  5177.4  244.52  5424.9  242.22  5467.3  243.58  5559.2  243.46  5580.5   244.6
  5629.9  244.94  5658.2  245.94  5686.5  250.67  5693.7  250.44  5712.6  251.63
  5728.9  254.28  5757.2  257.45  5806.8  260.37  5842.1  263.48  5849.2  262.96
#Mann= 4 ,-1 , 0
    4364     .15       0  4978.6     .09       0  5028.8     .15       0
  5712.6     .15       0
Bank Sta=4978.6,5028.8
XS Rating Curve= 0 ,0
Exp/Cntr=0.3,0.1

Type RM Length L Ch R = 1 ,9697    ,482,482,482
BEGIN DESCRIPTION:
LITTLE LAKE CREEK TRIB NO 5 18.0
END DESCRIPTION:
XS GIS Cut Line= 4
      3749467.85     10155461.08       3749310.2     10154840.07
      3749274.02      10154740.3      3748817.83     10153961.04
#Sta/Elev= 30
  4359.3   257.3  4390.3  258.22  4418.2  254.65  4423.3  255.42  4596.6  248.68
  4699.7   243.3  4786.7  241.91  4912.9     239  4978.3  240.58  5054.2  240.31
  5073.4  241.72  5125.4  242.15  5131.2  240.67  5162.6  242.49  5221.1  243.19
  5227.1  241.74  5307.2  243.17  5381.5  239.89  5430.3  240.04  5557.2   241.9
  5637.7  245.33  5776.5  246.34  5782.3  247.47    5798  245.85  5803.8  247.07
  5819.4  246.93  5825.2  248.59  5835.1   247.2    5889   252.2  6009.1  261.54
#Mann= 4 ,-1 , 0
  4359.3     .15       0  4786.7     .09       0  5073.4     .15       0
    5889     .15       0
#XS Ineff= 2 , 0
       0  4704.8  243.51               0
Permanent Ineff=
       F       F
Bank Sta=4786.7,5073.4
XS Rating Curve= 0 ,0
Exp/Cntr=0.3,0.1

Type RM Length L Ch R = 1 ,9215    ,437,437,437
BEGIN DESCRIPTION:
LITTLE LAKE CREEK TRIB NO 5 17.0
END DESCRIPTION:
XS GIS Cut Line= 3
      3749754.27     10155438.58       3749745.1     10155031.48
      3749267.85     10153811.08
#Sta/Elev= 30
  4592.8  257.05  4650.3  253.44  4958.7  238.61  4970.4  238.49  4994.2   237.1
  5011.4  238.23    5367  239.27  5451.4  240.48  5462.1  241.46    5548  238.59
  5633.1  238.66  5871.8  241.71  5923.9  242.76  5964.3  245.79    6024  248.32
  6048.4  251.48  6108.1  255.06  6117.1  257.01  6192.3     261  6211.4  260.15
  6216.7  262.28  6224.5  260.82  6235.2  261.59  6241.2  264.13  6246.6  262.55
  6265.7  266.17    6271  265.11  6295.5  268.22  6300.9  267.08  6310.4  268.24
#Mann= 5 ,-1 , 0
  4592.8     .11       0  4958.7     .15       0  4970.4     .09       0
  5011.4     .15       0  5871.8     .11       0
#XS Ineff= 2 ,-1
  5880.2    5910  242.03    5910  5934.5  243.15
Permanent Ineff=
       F       F
Bank Sta=4970.4,5011.4
XS Rating Curve= 0 ,0
Exp/Cntr=0.3,0.1

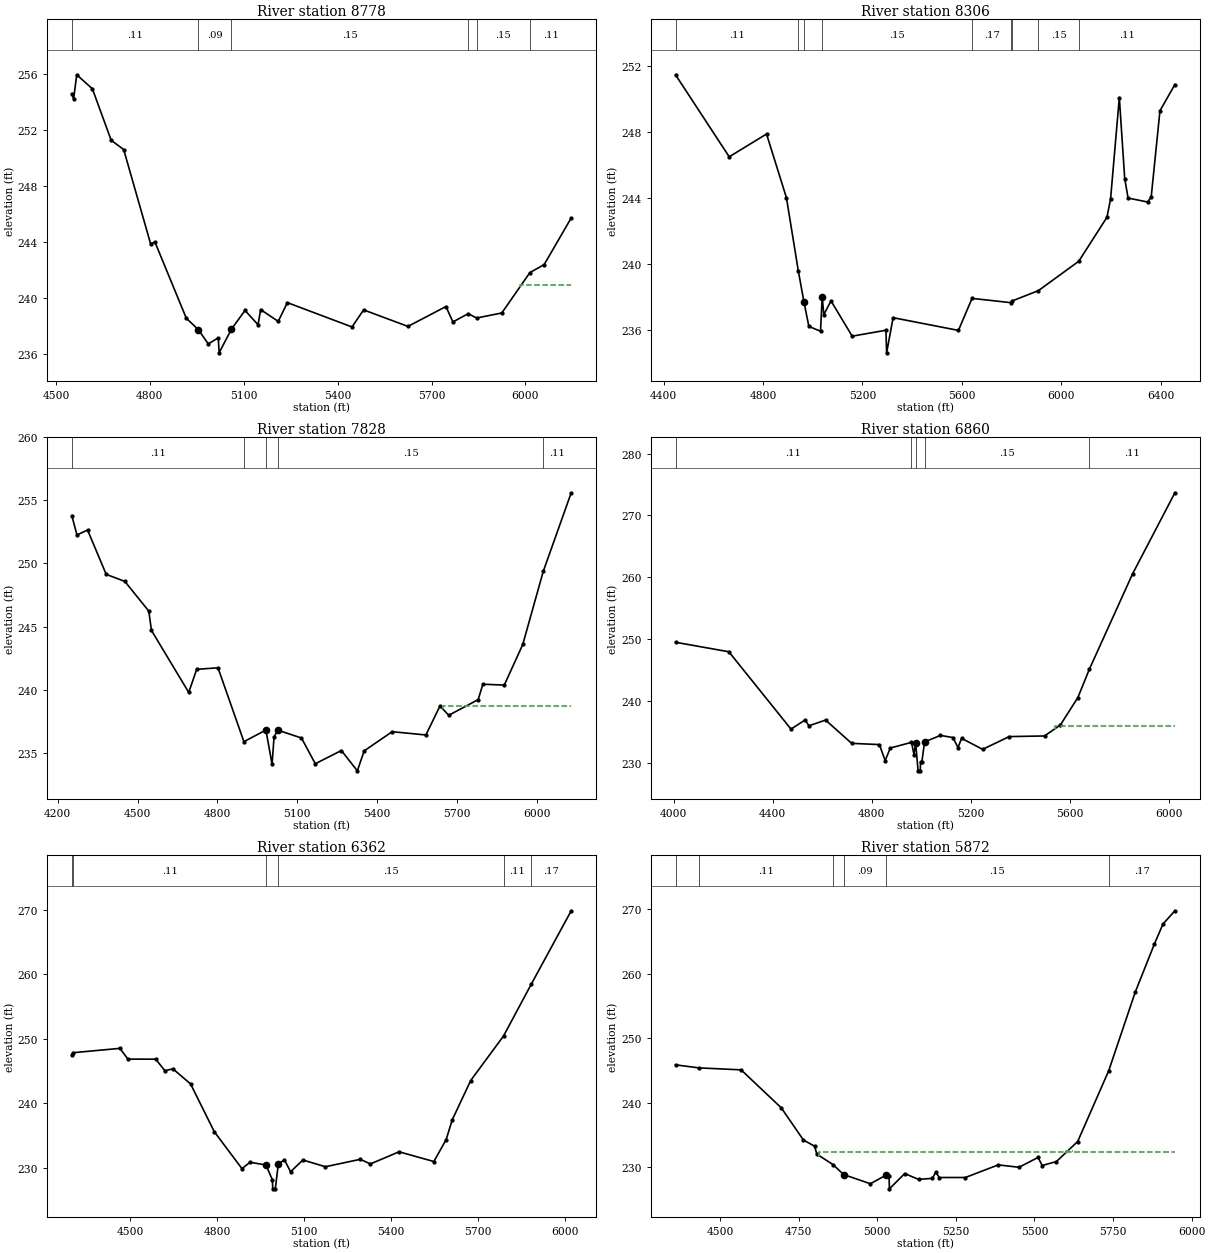
Type RM Length L Ch R = 1 ,8778    ,472,472,472
BEGIN DESCRIPTION:
LITTLE LAKE CREEK TRIB NO 5 16.0
END DESCRIPTION:
XS GIS Cut Line= 3
      3750170.94     10155476.74      3750156.56     10155027.57
      3749467.87     10154111.09
#Sta/Elev= 30
  4550.6  254.59  4556.3  254.21  4566.3  255.94  4616.3  254.94  4676.3  251.26
  4716.4  250.59  4802.3  243.86  4816.4  243.97  4916.5  238.53  4954.9  237.72
  4986.5   236.7  5018.6  237.13  5021.3  236.06  5060.3  237.74    5104  239.09
  5145.7  238.07    5154  239.15  5210.2  238.31  5239.4  239.65  5445.9  237.91
  5483.1  239.13  5624.7  237.95  5746.1  239.37  5768.4  238.27  5817.3  238.86
    5844  238.55  5924.6  238.91  6014.5   241.8    6060  242.37  6146.4   245.7
#Mann= 6 ,-1 , 0
  4550.6     .11       0  4954.9     .09       0  5060.3     .15       0
  5817.3     .11       0    5844     .15       0  6014.5     .11       0
#XS Ineff= 2 , 0
       0                  5982.9       0  240.92
Permanent Ineff=
       F       F
Bank Sta=4954.9,5060.3
XS Rating Curve= 0 ,0
Exp/Cntr=0.3,0.1

Type RM Length L Ch R = 1 ,8306    ,478,478,478
BEGIN DESCRIPTION:
LITTLE LAKE CREEK TRIB NO 5 15.0
END DESCRIPTION:
XS GIS Cut Line= 3
      3750639.69     10155476.75      3750607.08     10154926.01
      3749702.54     10153782.77
#Sta/Elev= 30
  4448.3  251.47  4664.4   246.5  4814.6  247.88  4894.8  244.01  4942.5  239.58
  4964.9  237.73  4984.9  236.22  5031.8  235.93  5038.6  238.03    5045  236.93
  5073.9  237.77  5159.3  235.63  5295.1  235.99  5297.8  234.62  5323.9  236.75
  5586.7  235.98  5641.6  237.92  5798.3  237.66  5804.1  237.77  5908.6  238.39
    6071  240.17  6184.6  242.84    6199  243.95  6234.2  250.09  6255.9  245.18
  6269.5     244    6348  243.76  6362.5  244.07  6397.7  249.29  6457.8  250.88
#Mann= 9 ,-1 , 0
  4448.3     .11       0  4942.5     .15       0  4964.9     .09       0
  5038.6     .15       0  5641.6     .17       0  5798.3     .15       0
  5804.1     .17       0  5908.6     .15       0    6071     .11       0
Bank Sta=4964.9,5038.6
XS Rating Curve= 0 ,0
Exp/Cntr=0.3,0.1

Type RM Length L Ch R = 1 ,7828    ,968,968,968
BEGIN DESCRIPTION:
LITTLE LAKE CREEK TRIB NO 5 14.0
END DESCRIPTION:
XS GIS Cut Line= 4
      3750917.46     10155480.22      3750893.53      10154733.3
      3750858.65     10154693.43      3750417.85     10153711.07
#Sta/Elev= 30
  4252.7  253.79  4271.9  252.26  4311.9  252.65  4381.9  249.14    4452  248.58
    4542  246.23    4552   244.7  4692.1  239.79  4722.1  241.62  4802.1  241.74
  4899.5  235.89  4982.2  236.81  5005.3   234.1  5012.9  236.28  5027.2   236.8
  5115.9  236.18  5167.8  234.14  5265.9  235.19  5325.9  233.58  5351.5  235.16
  5456.8  236.68  5583.6  236.42  5636.5  238.72  5669.4  237.98    5780  239.22
  5797.7  240.44  5878.2  240.37  5947.7  243.59  6024.6  249.37  6129.7   255.6
#Mann= 5 ,-1 , 0
  4252.7     .11       0  4899.5     .15       0  4982.2     .09       0
  5027.2     .15       0  6024.6     .11       0
#XS Ineff= 2 , 0
       0                  5647.4       0  238.74
Permanent Ineff=
       F       F
Bank Sta=4982.2,5027.2
XS Rating Curve= 0 ,0
Exp/Cntr=0.3,0.1

Type RM Length L Ch R = 1 ,6860    ,498,498,498
BEGIN DESCRIPTION:
LITTLE LAKE CREEK TRIB NO 5 13.0
END DESCRIPTION:
XS GIS Cut Line= 4
       3751063.3     10155483.73       3751322.2     10154589.26
      3751367.82     10154548.74      3752167.87     10153911.05
#Sta/Elev= 30
  4007.8  249.52    4223  247.99  4473.8   235.5  4531.1  236.98  4546.2  236.03
  4613.4  236.96  4718.5   233.2  4830.6     233  4853.8  230.41  4874.6  232.44
    4960  233.36  4970.3  231.39  4976.9  233.24  4986.8  228.76  4995.5  228.76
  4996.7  230.23  5002.1  230.23  5012.8  233.43  5076.8  234.48  5127.1  234.14
  5147.9  232.52  5162.3  234.01  5247.2  232.23  5354.5  234.29    5497  234.39
  5561.1  236.17  5631.5  240.59  5677.7  245.15  5852.5  260.58  6023.1  273.66
#Mann= 5 ,-1 , 0
  4007.8     .11       0    4960     .15       0  4976.9     .09       0
  5012.8     .15       0  5677.7     .11       0
#XS Ineff= 2 , 0
       0                  5538.6       0  236.01
Permanent Ineff=
       F       F
Bank Sta=4976.9,5012.8
XS Rating Curve= 0 ,0
Exp/Cntr=0.3,0.1

Type RM Length L Ch R = 1 ,6362    ,490,490,490
BEGIN DESCRIPTION:
LITTLE LAKE CREEK TRIB NO 5 12.0
END DESCRIPTION:
XS GIS Cut Line= 3
      3751254.29     10155528.83      3751575.42      10154903.8
      3752299.42     10154181.62
#Sta/Elev= 30
  4297.3  247.56  4302.5  247.86  4463.4  248.53  4491.3  246.86  4587.1  246.85
  4618.8  245.06  4646.6  245.35  4707.5  243.01  4789.5  235.59    4885  229.86
  4913.1  230.85  4968.1  230.42  4990.3   228.1  4991.5  226.72  5000.3  226.72
  5010.7  230.59  5031.9  231.22  5053.1  229.37  5095.6   231.2  5173.3  230.15
  5293.6   231.3  5328.9  230.59  5427.9  232.47  5548.1  230.96  5590.5  234.36
  5611.8  237.45  5675.4  243.54  5788.8  250.45  5885.3  258.55  6022.6  269.89
#Mann= 6 ,-1 , 0
  4297.3     .17       0  4302.5     .11       0  4968.1     .09       0
  5010.7     .15       0  5788.8     .11       0  5885.3     .17       0
Bank Sta=4968.1,5010.7
XS Rating Curve= 0 ,0
Exp/Cntr=0.3,0.1

Type RM Length L Ch R = 1 ,5872    ,506,506,506
BEGIN DESCRIPTION:
LITTLE LAKE CREEK TRIB NO 5 11.0
END DESCRIPTION:
XS GIS Cut Line= 3
      3751476.51      10155584.4      3751953.41      10155155.8
        3752393.     10154317.35
#Sta/Elev= 30
  4358.8  245.87  4433.1   245.4  4567.4  245.09  4695.2  239.19  4765.5  234.19
  4801.3  233.23  4808.1     232  4859.8  230.37  4893.3  228.83  4978.5   227.4
  5027.9  228.73  5037.7  228.53    5039  226.61  5087.5  228.98  5131.6  228.08
  5175.7  228.24    5186  229.18  5197.8  228.37  5280.4  228.37    5385  230.33
  5451.2  229.96  5511.7  231.49  5524.7  230.23  5569.9  230.85  5637.6  233.96
  5736.3  244.96  5820.6  257.16  5881.1  264.59  5908.8  267.74  5946.7   269.8
#Mann= 6 ,-1 , 0
  4358.8     .17       0  4433.1     .11       0  4859.8     .15       0
  4893.3     .09       0  5027.9     .15       0  5736.3     .17       0
#XS Ineff= 3 ,-1
  4801.3  4787.1  233.23  4815.5  4801.3  232.29    5600    5622  232.52
Permanent Ineff=
       F       F       F
Bank Sta=4893.3,5027.9
XS Rating Curve= 0 ,0
Exp/Cntr=0.3,0.1