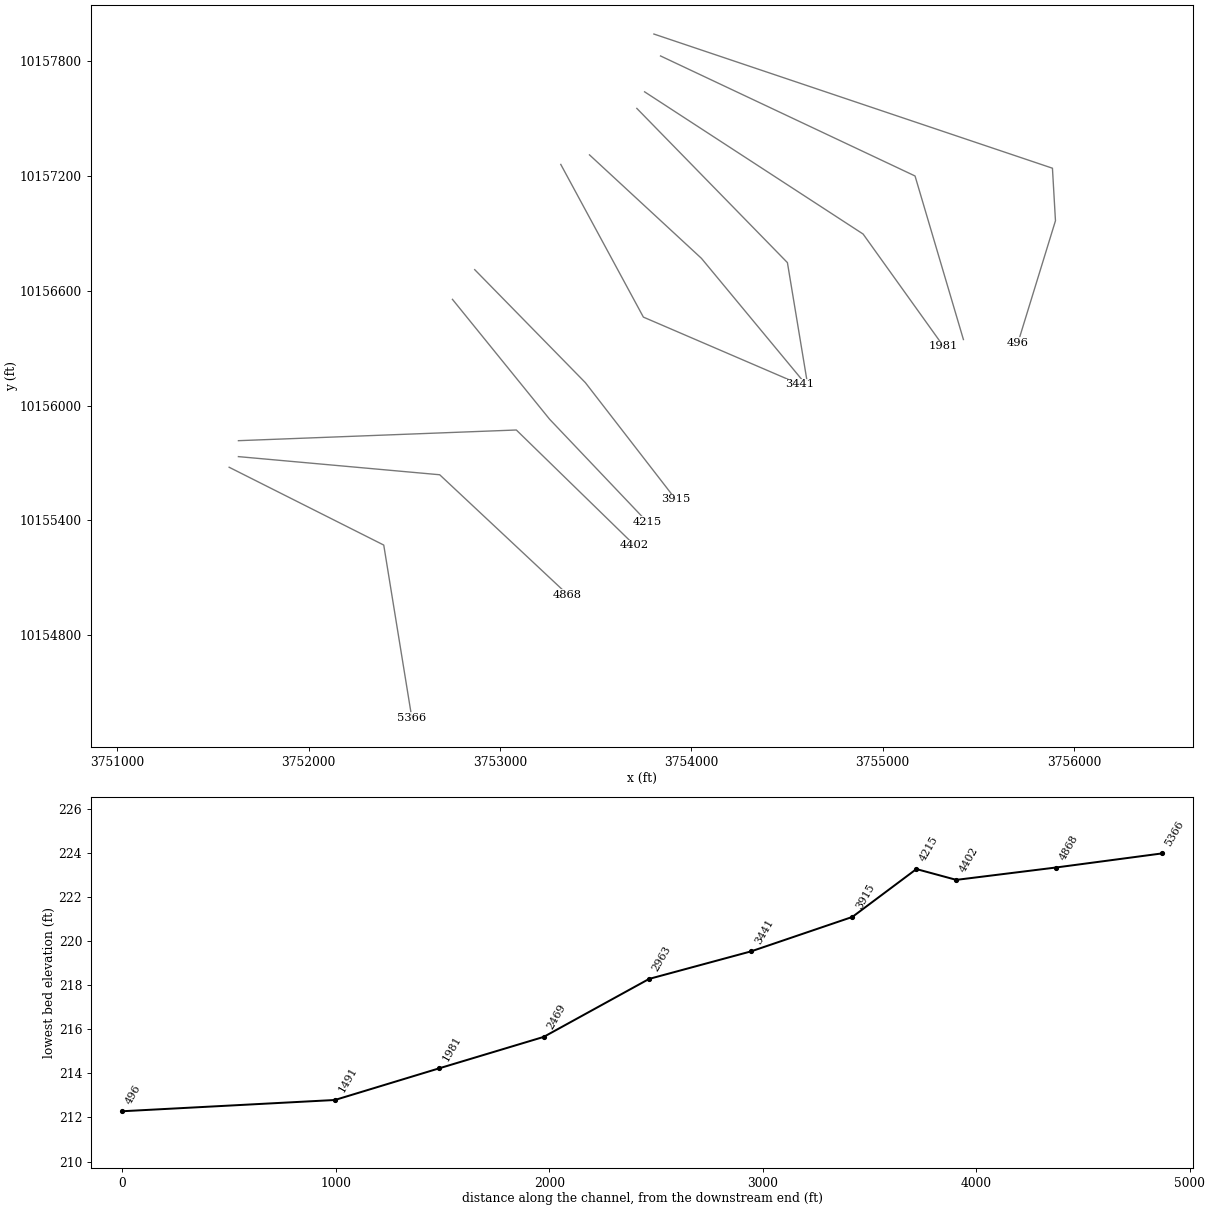
HEC-RAS study LITTLE LAKE CREEK TRIB NO 5.prj: LITTLE LAKE CREEK TRIB NO 5 Base Level Engineering

--- LITTLE LAKE CREEK TRIB NO 5.g01 (geometry) --- (continued)

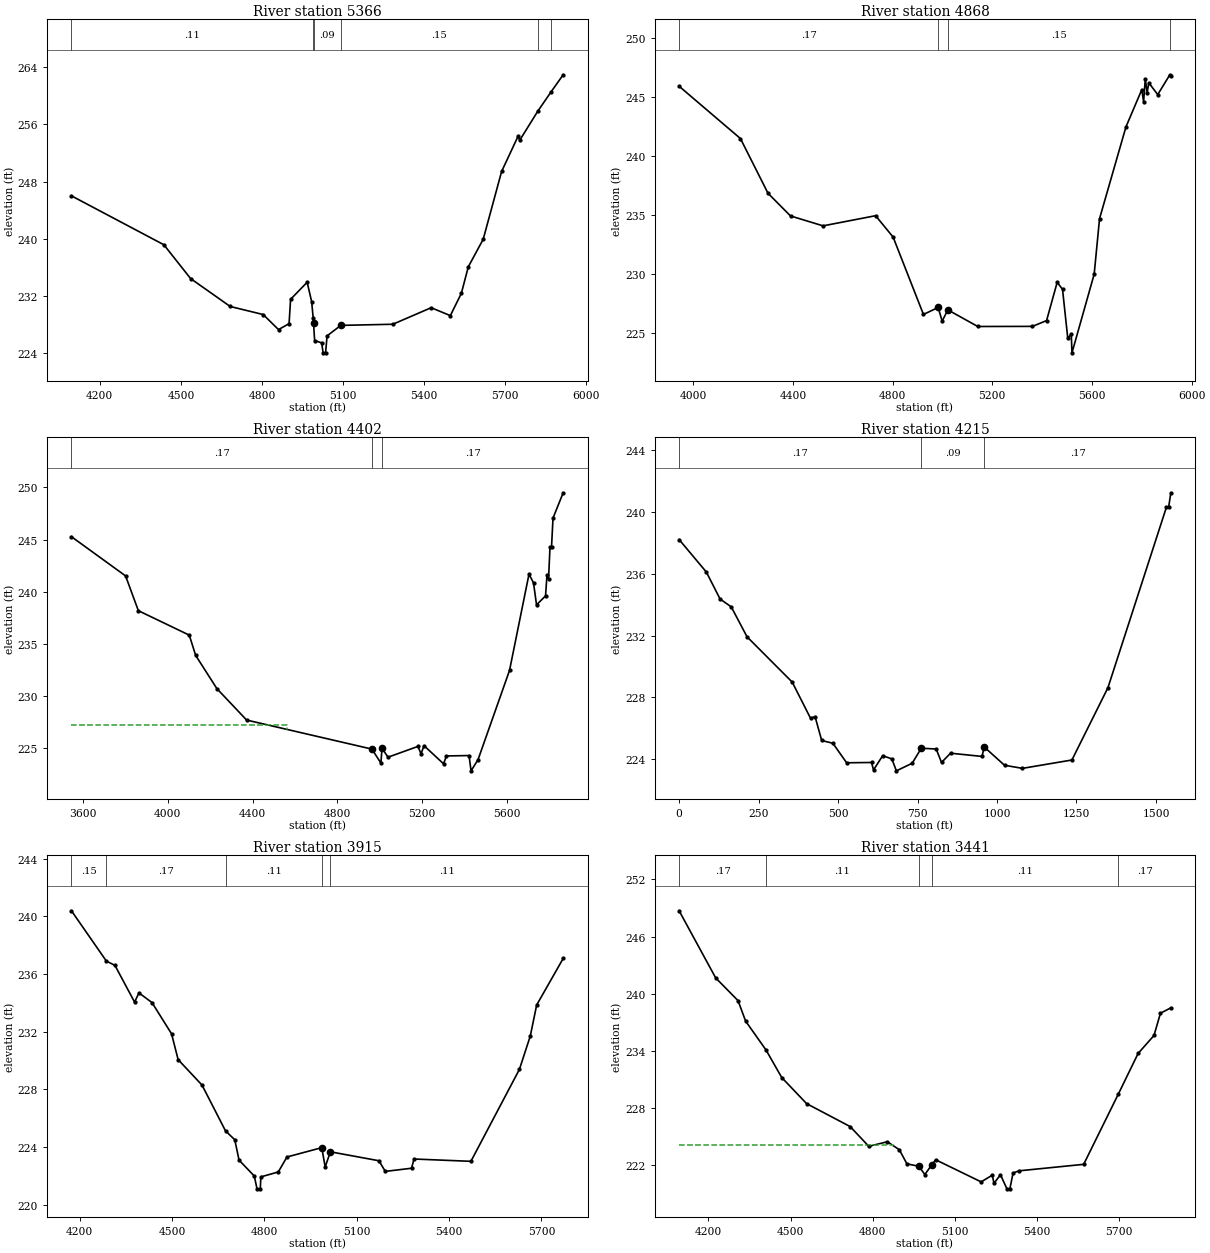
Type RM Length L Ch R = 1 ,5366    ,498,498,498
BEGIN DESCRIPTION:
LITTLE LAKE CREEK TRIB NO 5 10.0
END DESCRIPTION:
XS GIS Cut Line= 3
      3751584.18     10155678.14      3752392.38     10155271.37
        3752539.      10154369.1
#Sta/Elev= 30
  4095.2  245.99  4437.1  239.13  4535.9  234.39  4682.6  230.47  4804.6  229.34
  4861.1  227.23  4900.2  228.06  4905.8  231.48  4967.1  233.87  4983.7  231.15
  4989.4  228.87 4990.71   228.1  4994.8   225.7  5020.6  225.37  5026.2  223.97
  5035.2  223.97  5040.8  226.35  5091.5  227.82    5284  227.98  5425.8   230.3
  5496.7  229.19  5537.3   232.3  5563.3  236.05  5618.3   239.9  5686.4  249.41
    5748  254.41  5753.1  253.77  5820.3  257.87    5870  260.61  5914.1  262.97
#Mann= 6 ,-1 , 0
  4095.2     .11       0  4989.4     .12       0 4990.71     .09       0
  5091.5     .15       0  5820.3     .17       0    5870     .15       0
#XS Ineff= 2 , 0
       0  4967.1  233.87               0
Permanent Ineff=
       F       F
Bank Sta=4990.71,5091.5
XS Rating Curve= 0 ,0
Exp/Cntr=0.3,0.1

Type RM Length L Ch R = 1 ,4868    ,466,466,466
BEGIN DESCRIPTION:
LITTLE LAKE CREEK TRIB NO 5 9.0
END DESCRIPTION:
XS GIS Cut Line= 3
      3751632.72     10155733.72      3752684.85     10155638.91
      3753353.88     10155012.51
#Sta/Elev= 30
  3943.6   245.9  4189.7  241.47  4300.2  236.84  4390.5  234.92  4521.1  234.08
  4731.9  234.94  4802.2  233.13  4923.9  226.58  4982.9  227.17    4999  226.01
  5021.7  226.97  5141.9  225.56  5361.2  225.57  5417.9  226.06  5460.4   229.3
  5481.9  228.71  5502.9  224.57    5517  224.91  5519.8  223.33  5608.9  229.99
  5630.4  234.69  5736.4  242.46  5799.9  245.61  5807.2  244.59    5814  246.54
  5821.3  245.36  5828.2  246.19  5863.8  245.19  5912.4  246.87  5916.5  246.76
#Mann= 4 ,-1 , 0
  3943.6     .17       0  4982.9     .09       0  5021.7     .15       0
  5912.4     .17       0
#XS Ineff= 2 , 0
       0                  5460.4       0   229.3
Permanent Ineff=
       F       F
Bank Sta=4982.9,5021.7
XS Rating Curve= 0 ,0
Exp/Cntr=0.3,0.1

Type RM Length L Ch R = 1 ,4402    ,187,187,187
BEGIN DESCRIPTION:
LITTLE LAKE CREEK TRIB NO 5 8.0
END DESCRIPTION:
XS GIS Cut Line= 3
      3751632.72     10155817.05      3753085.45      10155872.9
      3753704.27      10155269.8
#Sta/Elev= 30
  3546.2  245.27  3801.5   241.5  3861.6  238.16  4101.7  235.81  4131.8  233.86
  4231.8  230.67  4371.9  227.65  4962.4  224.86  5004.9  223.52  5010.1  224.94
  5038.4  224.08  5179.8  225.12    5194   224.4  5208.1  225.19    5300  223.45
  5314.1   224.2  5420.3  224.24  5429.9  222.77  5462.7  223.84  5611.2  232.42
    5703  241.67  5724.3  240.83  5738.5  238.72  5780.9  239.58  5787.9   241.6
  5795.1  241.23    5802  244.27  5809.2  244.29  5816.2  247.06  5864.1  249.49
#Mann= 3 , 0 , 0
  3546.2     .17       0  4962.4     .09       0  5010.1     .17       0
#XS Ineff= 2 , 0
       0  4564.5  227.13               0
Permanent Ineff=
       F       F
Bank Sta=4962.4,5010.1
XS Rating Curve= 0 ,0
Exp/Cntr=0.3,0.1

Type RM Length L Ch R = 1 ,4215    ,300,300,300
XS GIS Cut Line= 3
      3752751.49     10156555.82      3753259.35     10155929.18
      3753769.28     10155392.63
#Sta/Elev= 30
       0   238.2    85.7   236.1   128.8  234.36     164  233.85   213.6  231.92
   355.8  228.99   413.3  226.66   427.7  226.76   448.5  225.22   483.7  225.04
   526.9  223.78   605.2   223.8   611.6  223.32   640.4  224.24   669.1  224.03
   683.5  223.26   733.1  223.75   761.8  224.72   808.7  224.67   825.4   223.8
   853.8   224.4   952.8  224.19   959.7   224.8  1023.6  223.62  1079.9  223.42
  1235.6  223.96  1348.9  228.63  1532.9  240.29  1539.8  240.29  1546.8  241.22
#Mann= 3 , 0 , 0
       0     .17       0   761.8     .09       0   959.7     .17       0
Bank Sta=761.8,959.7
XS Rating Curve= 0 ,0
Exp/Cntr=0.3,0.1

Type RM Length L Ch R = 1 ,3915    ,474,474,474
BEGIN DESCRIPTION:
LITTLE LAKE CREEK TRIB NO 5 7.0
END DESCRIPTION:
XS GIS Cut Line= 3
      3752867.88     10156711.04      3753446.19     10156120.56
      3753917.87     10155511.05
#Sta/Elev= 30
  4173.5  240.39  4286.9   236.9  4314.8   236.6  4378.6  234.05  4392.7  234.69
  4435.1  234.02  4498.7  231.85    4520  230.06  4597.7  228.29    4674  225.11
  4703.9   224.5    4718  223.08  4767.4  221.98  4776.3  221.09  4786.9  221.09
  4788.7  221.92  4845.3  222.26  4873.5   223.3  4986.6  223.95  4997.6  222.61
  5014.6  223.66  5172.2  223.04    5193   222.3  5278.1  222.52  5286.3  223.16
    5471     223  5628.5  229.38  5663.8  231.69  5684.6  233.85  5770.7  237.08
#Mann= 5 ,-1 , 0
  4173.5     .15       0  4286.9     .17       0    4674     .11       0
  4986.6     .09       0  5014.6     .11       0
Bank Sta=4986.6,5014.6
XS Rating Curve= 0 ,0
Exp/Cntr=0.3,0.1

Type RM Length L Ch R = 1 ,3441    ,478,478,478
BEGIN DESCRIPTION:
LITTLE LAKE CREEK TRIB NO 5 6.0
END DESCRIPTION:
XS GIS Cut Line= 3
      3753317.83     10157261.11      3753749.57     10156463.01
      3754567.89     10156111.05
#Sta/Elev= 30
  4092.6   248.7  4226.3  241.66  4308.2  239.27  4335.7  237.13  4410.3   234.1
  4467.8  231.21  4558.8  228.47  4718.2  226.06  4786.2  223.99  4854.2  224.47
    4898  223.63  4925.6  222.15  4969.3   221.9  4991.2  221.03    5016  222.03
  5030.8  222.58  5197.1  220.26  5237.6  220.96  5244.2  220.11  5267.7  221.01
  5291.4  219.53  5302.1  219.53  5313.8  221.19  5335.6  221.42    5572   222.1
  5698.4  229.45    5771  233.73  5829.2  235.62  5852.7  237.95  5890.8  238.52
#Mann= 5 ,-1 , 0
  4092.6     .17       0  4410.3     .11       0  4969.3     .09       0
    5016     .11       0  5698.4     .17       0
#XS Ineff= 2 , 0
       0  4876.1  224.14               0
Permanent Ineff=
       F       F
Bank Sta=4969.3,5016
XS Rating Curve= 0 ,0
Exp/Cntr=0.3,0.1

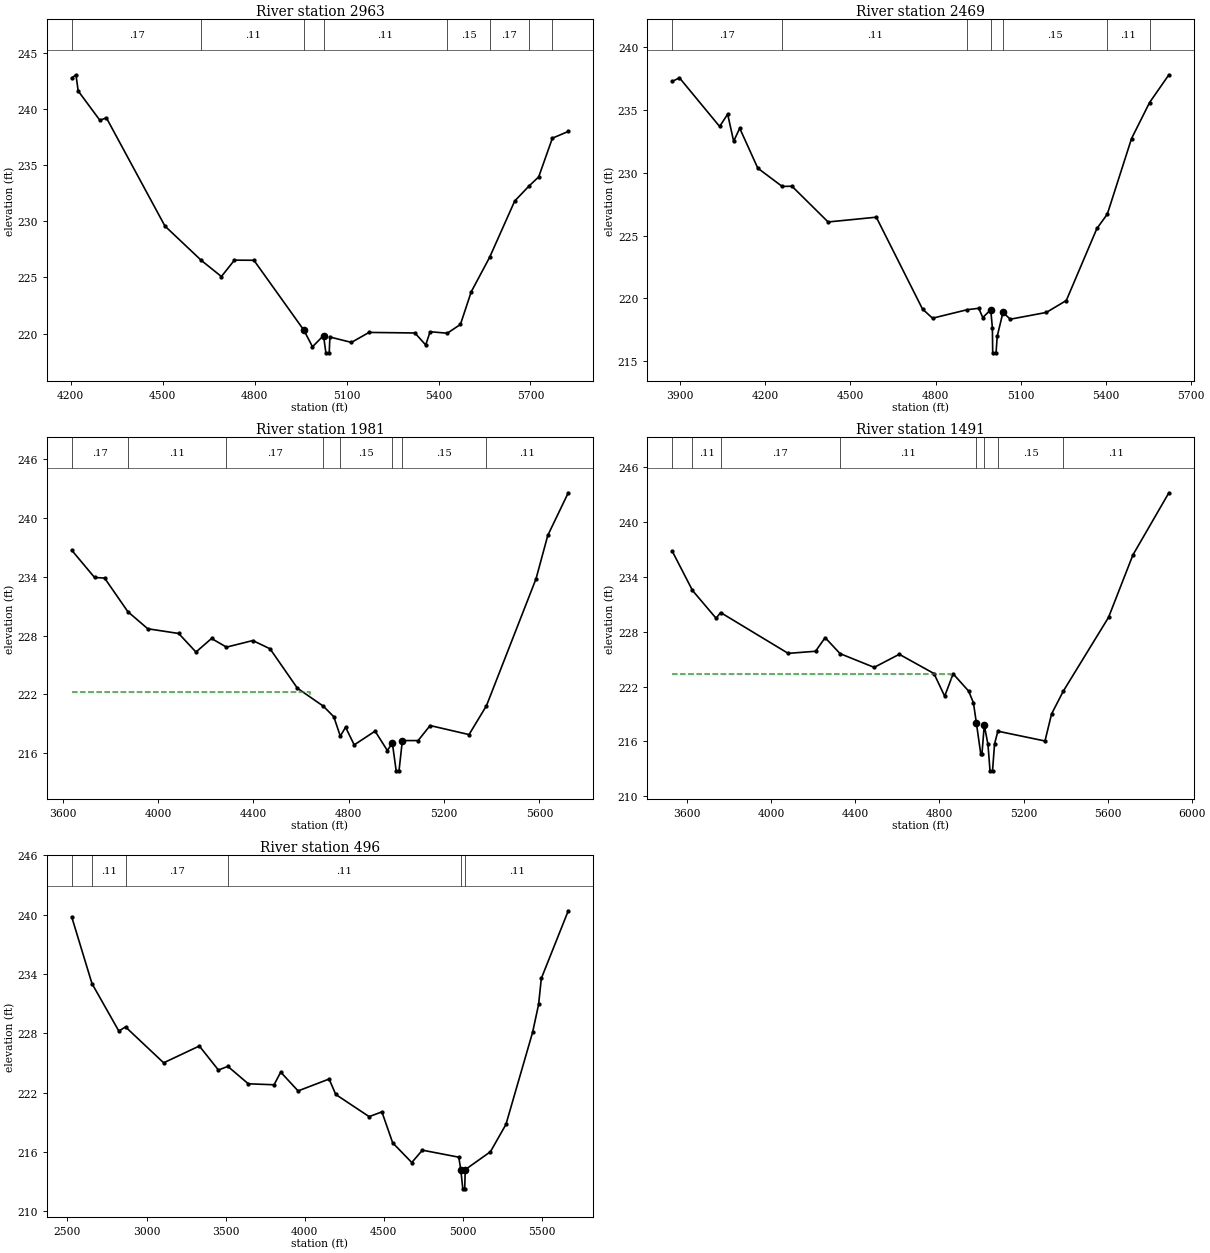
Type RM Length L Ch R = 1 ,2963    ,494,494,494
BEGIN DESCRIPTION:
LITTLE LAKE CREEK TRIB NO 5 5.0
END DESCRIPTION:
XS GIS Cut Line= 3
      3753467.88     10157311.05      3754052.96      10156770.3
       3754578.2     10156136.31
#Sta/Elev= 30
  4203.3  242.77  4217.2  243.06  4224.5  241.62  4295.4     239  4316.4  239.23
  4507.5  229.58  4626.5  226.51  4691.7  225.08  4734.3  226.54  4797.8  226.53
  4960.5  220.31  4988.9  218.82  5024.8  219.82  5032.6  218.28  5043.4  218.28
  5045.7  219.69    5116  219.21  5173.3   220.1  5323.1  220.05  5358.2  218.98
  5372.6  220.16  5428.8  220.03  5471.5  220.81  5506.7  223.72  5566.7  226.79
  5648.6  231.81    5695  233.14  5726.8  233.96  5771.5  237.41  5823.3  238.01
#Mann= 8 ,-1 , 0
  4203.3     .17       0  4626.5     .11       0  4960.5     .06       0
  5024.8     .11       0  5428.8     .15       0  5566.7     .17       0
    5695     .11       0  5771.5     .17       0
Bank Sta=4960.5,5024.8
XS Rating Curve= 0 ,0
Exp/Cntr=0.3,0.1

Type RM Length L Ch R = 1 ,2469    ,488,488,488
BEGIN DESCRIPTION:
LITTLE LAKE CREEK TRIB NO 5 4.0
END DESCRIPTION:
XS GIS Cut Line= 3
      3753715.29     10157554.03       3754502.5     10156747.81
      3754604.07     10156134.87
#Sta/Elev= 30
  3873.2  237.28  3898.3  237.57  4039.8  233.69  4068.1  234.67  4089.2  232.51
  4110.5  233.55  4174.1  230.37  4260.1  228.91  4294.4  228.93  4421.7  226.08
  4591.3  226.46    4754  219.14  4789.3  218.41  4911.8  219.09    4952   219.2
  4966.2  218.46  4994.2  219.09    5000  217.64  5001.1  215.65  5012.9  215.65
    5017  216.97  5037.2  218.87    5063  218.33    5190  218.87  5260.2  219.82
  5367.9  225.56  5404.5   226.7  5489.9  232.73  5553.4   235.6  5621.3  237.81
#Mann= 7 ,-1 , 0
  3873.2     .17       0  4260.1     .11       0  4911.8     .15       0
  4994.2     .09       0  5037.2     .15       0  5404.5     .11       0
  5553.4     .17       0
Bank Sta=4994.2,5037.2
XS Rating Curve= 0 ,0
Exp/Cntr=0.3,0.1

Type RM Length L Ch R = 1 ,1981    ,490,490,490
BEGIN DESCRIPTION:
LITTLE LAKE CREEK TRIB NO 5 3.0
END DESCRIPTION:
XS GIS Cut Line= 3
      3753755.93     10157640.63      3754898.12     10156897.24
      3755317.82     10156311.11
#Sta/Elev= 30
  3637.2  236.69  3733.1  233.91  3775.3  233.85  3872.8  230.43  3956.4  228.69
  4086.2  228.21  4158.7  226.32  4224.1   227.7  4286.7  226.82  4397.2  227.49
  4469.6  226.65  4584.3  222.64  4693.3  220.81  4737.2  219.73  4764.3  217.76
  4786.5  218.67  4822.7  216.87  4910.3  218.27  4961.7   216.3  4982.8  217.05
  4998.8  214.23  5010.7  214.23 5024.71  217.31  5090.8  217.31  5141.1  218.84
  5304.5  217.92  5377.7  220.86  5585.7  233.78  5634.9  238.19  5720.9  242.53
#Mann= 8 ,-1 , 0
  3637.2     .17       0  3872.8     .11       0  4286.7     .17       0
  4693.3     .11       0  4764.3     .15       0  4982.8     .09       0
 5024.71     .15       0  5377.7     .11       0
#XS Ineff= 2 , 0
       0  4635.6   222.3               0
Permanent Ineff=
       F       F
Bank Sta=4982.8,5024.71
XS Rating Curve= 0 ,0
Exp/Cntr=0.3,0.1

Type RM Length L Ch R = 1 ,1491    ,995,995,995
BEGIN DESCRIPTION:
LITTLE LAKE CREEK TRIB NO 5 2.0
END DESCRIPTION:
XS GIS Cut Line= 3
      3753839.24     10157828.15      3755169.61     10157200.73
      3755422.51     10156345.75
#Sta/Elev= 30
  3529.1  236.77  3625.2  232.49  3737.6  229.45  3758.9  230.08  4080.4  225.62
  4210.7  225.85  4256.2  227.34  4327.3  225.59  4489.5  224.09    4609  225.52
  4773.9  223.42    4825  220.94  4865.1  223.39  4938.9   221.5  4961.7  220.23
  4975.9     218  4996.3  214.68  5002.4  214.68  5013.4  217.78  5030.9  215.67
  5040.7  212.79  5052.6  212.79  5062.2  215.72  5077.9  217.12  5302.1  216.05
  5333.6  219.01  5389.7  221.51  5604.5  229.55  5720.5  236.37  5891.6  243.16
#Mann= 8 ,-1 , 0
  3529.1     .17       0  3625.2     .11       0  3758.9     .17       0
  4327.3     .11       0  4975.9     .09       0  5013.4     .11       0
  5077.9     .15       0  5389.7     .11       0
#XS Ineff= 2 , 0
       0  4854.3  223.42               0
Permanent Ineff=
       F       F
Bank Sta=4975.9,5013.4
XS Rating Curve= 0 ,0
Exp/Cntr=0.3,0.1

Type RM Length L Ch R = 1 ,496     ,0,0,0
BEGIN DESCRIPTION:
LITTLE LAKE CREEK TRIB NO 5 1.0
END DESCRIPTION:
XS GIS Cut Line= 4
      3753804.55     10157942.72      3755887.86     10157241.34
      3755903.67      10156966.7      3755707.29     10156328.11
#Sta/Elev= 30
  2526.7  239.78  2655.1  233.03    2825  228.23  2867.2  228.65  3108.5  225.02
  3334.2  226.72  3454.9  224.29  3514.6  224.66  3643.9   222.9  3806.9   222.8
  3849.1  224.08  3958.9  222.18  4155.1  223.38  4197.3  221.82  4408.4  219.58
  4489.1  220.06  4557.4  216.93  4678.1  214.94  4745.2  216.19  4975.6  215.48
  4988.2   214.2    5001  212.28    5013  212.28  5016.3  214.22  5175.7  216.03
  5273.8  218.79  5442.6  228.11  5480.5  230.93  5497.6  233.55  5668.1  240.39
#Mann= 6 ,-1 , 0
  2526.7     .17       0  2655.1     .11       0  2867.2     .17       0
  3514.6     .11       0  4988.2     .09       0  5016.3     .11       0
Bank Sta=4988.2,5016.3
XS Rating Curve= 0 ,0
Exp/Cntr=0.3,0.1

Chan Stop Cuts=-1
Use User Specified Reach Order=0
Composite Channel Slope=5