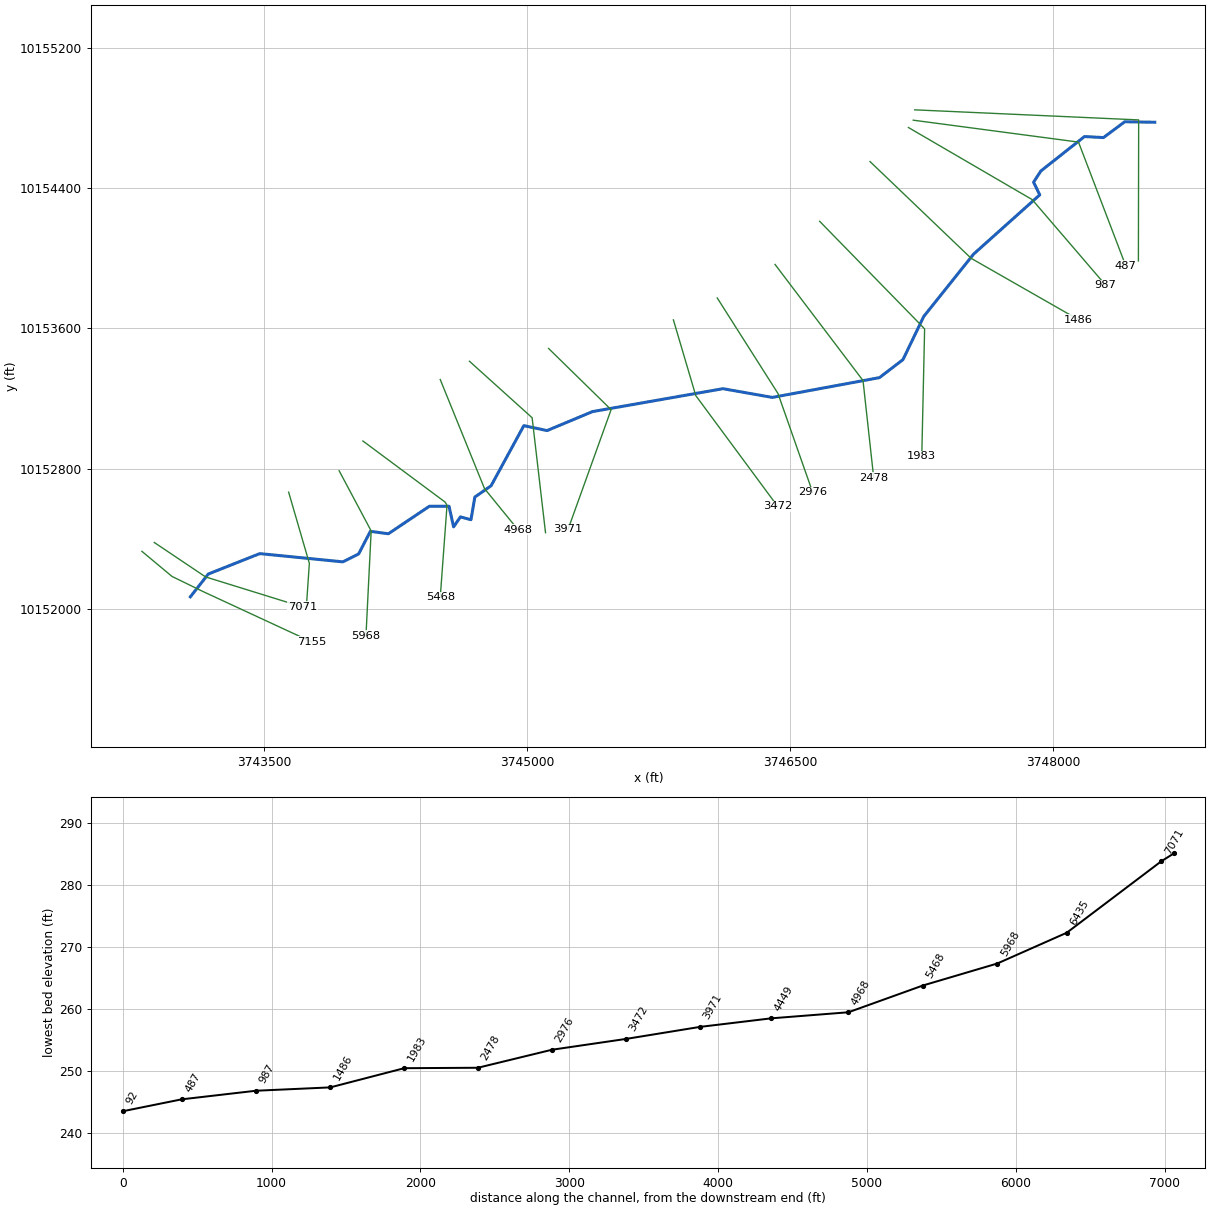
--- LITTLE LAKE CREEK TRIB NO 5_1.prj (project) ---

Proj Title=LITTLE LAKE CREEK TRIB NO 5_1 Base Level Engineering
Current Plan=p01
Default Exp/Contr=0.3,0.1
English Units
Geom File=g01
Flow File=f01
Plan File=p01
Y Axis Title=Elevation
X Axis Title(PF)=Main Channel Distance
X Axis Title(XS)=Station
BEGIN DESCRIPTION:
LITTLE LAKE CREEK TRIB NO 5_1
END DESCRIPTION:
DSS Export Rating Curves= 0
DSS Export Rating Curve Sorted= 0
DSS Export Volume Flow Curves= 0
DXF OffsetX= 0
DXF OffsetY= 0
DXF ScaleX= 1
DXF ScaleY= 10

--- LITTLE LAKE CREEK TRIB NO 5_1.p01 (plan) ---

Plan Title=Multiple Run
Short Identifier=Multiple
Geom File=g01
Flow File=f01
Subcritical Flow
K Sum by GR= 0
Std Step Tol= 0.01
Critical Tol= 0.01
Num of Std Step Trials= 20
Max Error Tol= 0.3
Flow Tol Ratio= 0.001
Split Flow NTrial= 30
Split Flow Tol= 0.02
Split Flow Ratio= 0.02
Log Output Level= 0
Friction Slope Method= 1
Unsteady Friction Slope Method= 2
Unsteady Bridges Friction Slope Method= 1
Parabolic Critical Depth
Global Vel Dist=  1 , 1 , 1
Global Log Level= 0
CheckData=True
Encroach Param= -1, 0, 0, 0
BEGIN DESCRIPTION:
Multiple Run
END DESCRIPTION:

--- LITTLE LAKE CREEK TRIB NO 5_1.f01 (steady flow) ---

Flow Title=Multiple
Program Version=4.10
Number of Profiles= 7
Profile Names=10-year,25-year,50-year,1pct_min,100-year,1pct_plu,500-year
River Rch & RM=LITTLE LAKE CREE,Reach-1         ,7155
     392     523     703     312     943    2848    1746
River Rch & RM=LITTLE LAKE CREE,Reach-1         ,6435
     915    1269    1742     786    2375    7172    4568
Boundary for River Rch & Prof#=LITTLE LAKE CREE,Reach-1         , 1
Up Type= 0
Dn Type= 3
Dn Slope=0.01
Boundary for River Rch & Prof#=LITTLE LAKE CREE,Reach-1         , 2
Up Type= 0
Dn Type= 3
Dn Slope=0.01
Boundary for River Rch & Prof#=LITTLE LAKE CREE,Reach-1         , 3
Up Type= 0
Dn Type= 3
Dn Slope=0.01
Boundary for River Rch & Prof#=LITTLE LAKE CREE,Reach-1         , 4
Up Type= 0
Dn Type= 3
Dn Slope=0.01
Boundary for River Rch & Prof#=LITTLE LAKE CREE,Reach-1         , 5
Up Type= 0
Dn Type= 3
Dn Slope=0.01
Boundary for River Rch & Prof#=LITTLE LAKE CREE,Reach-1         , 6
Up Type= 0
Dn Type= 3
Dn Slope=0.01
Boundary for River Rch & Prof#=LITTLE LAKE CREE,Reach-1         , 7
Up Type= 0
Dn Type= 3
Dn Slope=0.01
DSS Import GetInterval= 0
DSS Import GetPeak= 0
DSS Import FillOption= 0

--- LITTLE LAKE CREEK TRIB NO 5_1.g01 (geometry) ---

Geom Title=Existing Conditions
Program Version=4.10

River Reach=LITTLE LAKE CREE,Reach-1
Reach XY= 30
      3743078.43     10152069.24      3743180.86     10152199.45
      3743474.26     10152315.77      3743948.22     10152268.89
       3744038.5     10152314.03      3744105.08     10152442.75
      3744208.06     10152429.15      3744441.55     10152585.73
      3744553.96     10152585.73      3744579.99     10152468.38
      3744618.94     10152525.22      3744679.02     10152509.24
      3744701.22     10152638.42      3744793.83     10152702.79
      3744980.61      10153045.7      3745113.09     10153017.61
      3745372.47     10153125.87      3746116.32     10153256.44
       3746397.9     10153206.71      3747009.02     10153319.57
      3747142.97     10153422.15      3747261.46      10153668.2
      3747545.45      10154023.8      3747923.39     10154362.19
      3747887.81     10154434.13      3747929.71     10154498.35
      3748178.23     10154694.58      3748286.54      10154688.7
      3748407.86     10154778.88       3748579.2     10154776.27

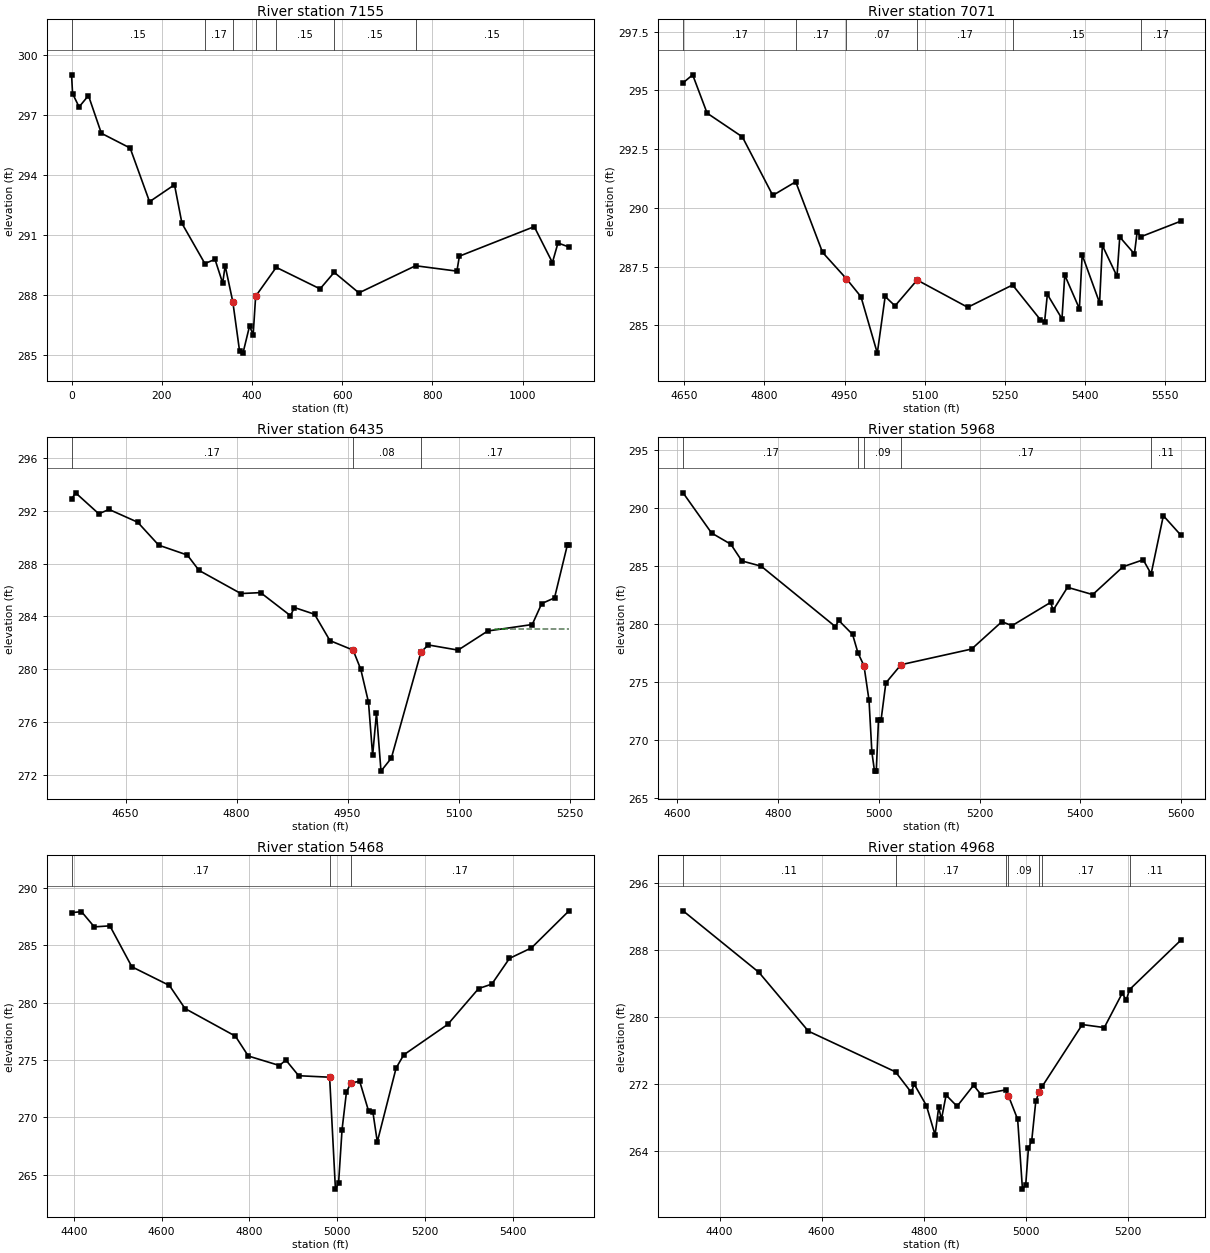
Type RM Length L Ch R = 1 ,7155    ,84,84,84
XS GIS Cut Line= 4
      3742802.36     10152328.65      3742973.82     10152185.76
       3743147.4     10152101.09      3743770.12     10151812.42
#Sta/Elev= 30
       0  299.03     2.3  298.09    16.7  297.42    37.5  297.99    66.1   296.1
   129.9  295.36   172.9  292.67   228.2  293.52   244.8  291.58   295.5  289.57
     318  289.78     335  288.59   340.5  289.46   357.5  287.65   372.3  285.21
     380  285.08   394.6  286.44   402.6     286   408.1  287.93   453.7  289.38
   550.9   288.3   582.2  289.13     637   288.1   762.6  289.46   854.2  289.19
   859.7  289.94  1025.6  291.42  1065.9  289.62  1078.2   290.6  1102.7   290.4
#Mann= 7 ,-1 , 0
       0     .15       0   295.5     .17       0   357.5     .04       0
   408.1     .17       0   453.7     .15       0   582.2     .15       0
   762.6     .15       0
Bank Sta=357.5,408.1
XS Rating Curve= 0 ,0
Exp/Cntr=0.3,0.1

Type RM Length L Ch R = 1 ,7071    ,636,636,636
BEGIN DESCRIPTION:
LITTLE LAKE CREEK TRIB NO 5_1 14.0
END DESCRIPTION:
XS GIS Cut Line= 3
       3742872.8     10152379.36      3743165.37     10152182.92
       3743718.5     10152011.45
#Sta/Elev= 30
  4647.6  295.32  4665.6  295.66  4692.6  294.03  4758.6  293.02  4815.6  290.53
  4858.5  291.11  4908.7  288.11  4953.6  286.98  4980.7  286.22  5011.3  283.82
    5026  286.23  5044.5  285.83  5085.9  286.93  5180.6  285.77  5264.6  286.72
  5316.7  285.24  5324.5  285.14  5329.7  286.32  5357.1  285.28  5362.3  287.14
  5389.7  285.71  5394.9     288  5427.5  285.96  5432.7   288.4  5460.1  287.09
  5465.3  288.76  5492.7  288.04  5497.9  288.98  5504.6  288.77  5579.1  289.43
#Mann= 6 ,-1 , 0
  4647.6     .17       0  4858.5     .17       0  4953.6     .07       0
  5085.9     .17       0  5264.6     .15       0  5504.6     .17       0
Bank Sta=4953.6,5085.9
XS Rating Curve= 0 ,0
Exp/Cntr=0.3,0.1

Type RM Length L Ch R = 1 ,6435    ,467,467,467
BEGIN DESCRIPTION:
LITTLE LAKE CREEK TRIB NO 5_1 13.0
END DESCRIPTION:
XS GIS Cut Line= 3
      3743639.17      10152666.4      3743757.25     10152260.21
      3743740.16      10152011.5
#Sta/Elev= 30
    4577   292.9  4582.5  293.38  4613.8  291.79  4627.7  292.12  4666.4  291.15
  4694.8  289.41  4733.5  288.66  4749.2   287.5  4805.8  285.74  4832.5  285.81
  4872.9  284.06  4878.1  284.68  4905.4  284.17  4926.2  282.17  4957.5  281.45
  4967.9  279.99  4978.3   277.5  4983.9  273.46  4989.1  276.68  4995.2  272.27
  5009.2  273.26  5049.3  281.31  5059.2  281.84  5099.4  281.45  5139.5   282.9
  5199.6  283.39  5212.4  284.98  5229.7  285.41    5247  289.41  5249.3  289.41
#Mann= 3 , 0 , 0
    4577     .17       0  4957.5     .08       0  5049.3     .17       0
#XS Ineff= 2 , 0
       0                  5149.5       0  283.05
Permanent Ineff=
       F       F
Bank Sta=4957.5,5049.3
XS Rating Curve= 0 ,0
Exp/Cntr=0.3,0.1

Type RM Length L Ch R = 1 ,5968    ,500,500,500
BEGIN DESCRIPTION:
LITTLE LAKE CREEK TRIB NO 5_1 12.0
END DESCRIPTION:
XS GIS Cut Line= 3
      3743927.37     10152787.93      3744109.85     10152445.18
      3744080.14     10151847.02
#Sta/Elev= 30
  4611.7  291.28  4668.2  287.82  4706.5  286.85  4728.4  285.41  4766.7  284.96
    4914  279.75  4920.5  280.29  4948.1  279.08  4958.8  277.48  4970.7  276.38
  4980.7  273.41  4986.4  268.93  4991.6   267.3  4995.1   267.3  4999.5   271.7
  5004.6   271.7  5014.1   274.9  5044.2  276.47  5184.3  277.82  5244.4  280.18
  5264.4  279.83  5341.1  281.84  5346.1  281.17  5374.6  283.14  5424.6  282.51
  5484.7  284.91  5524.8  285.51  5540.5  284.29  5564.8  289.31  5598.9  287.66
#Mann= 5 ,-1 , 0
  4611.7     .17       0  4958.8     .12       0  4970.7     .09       0
  5044.2     .17       0  5540.5     .11       0
Bank Sta=4970.7,5044.2
XS Rating Curve= 0 ,0
Exp/Cntr=0.3,0.1

Type RM Length L Ch R = 1 ,5468    ,500,500,500
BEGIN DESCRIPTION:
LITTLE LAKE CREEK TRIB NO 5_1 11.0
END DESCRIPTION:
XS GIS Cut Line= 4
      3744062.78     10152958.08      3744531.21     10152610.01
      3744542.51     10152591.95      3744503.76     10152065.87
#Sta/Elev= 30
  4395.1  287.86  4417.7  287.95  4446.9  286.62  4482.4  286.71  4532.4  283.14
  4617.9  281.51  4653.4   279.5  4768.1  277.09  4797.4  275.36  4868.3  274.53
  4882.9  275.01  4912.1  273.64  4982.6  273.51  4995.8  263.75  5002.9  264.25
  5010.9  268.95  5020.9  272.22    5031     273    5051  273.16  5071.1  270.58
  5081.1  270.46  5091.1  267.87  5133.9  274.31  5151.3  275.46  5251.6  278.12
  5321.7  281.24  5351.8  281.63  5391.9  283.87  5442.1  284.79  5527.5  288.02
#Mann= 3 , 0 , 0
  4395.1     .17       0  4982.6     .09       0    5031     .17       0
Bank Sta=4982.6,5031
XS Rating Curve= 0 ,0
Exp/Cntr=0.3,0.1

Type RM Length L Ch R = 1 ,4968    ,519,519,519
BEGIN DESCRIPTION:
LITTLE LAKE CREEK TRIB NO 5_1 10.0
END DESCRIPTION:
XS GIS Cut Line= 3
      3744503.75     10153308.78      3744756.37     10152686.39
      3744948.17     10152451.17
#Sta/Elev= 30
  4328.3  292.66  4476.9  285.32    4574  278.29  4744.8  273.43  4775.8  270.97
  4781.2  271.98  4805.3  269.41  4822.3   265.9  4829.4  269.19  4834.8  267.77
  4843.9  270.66  4865.4  269.32  4897.8  271.83  4912.4  270.72  4960.6  271.28
    4966  270.59  4984.2  267.76  4993.6  259.43    5000  259.93  5005.3  264.29
  5011.8  265.23  5019.7   269.9  5026.1  271.03  5032.7  271.73  5110.9  279.08
    5154  278.72  5189.1  282.81  5197.1  282.01  5203.6  283.26  5303.5  289.12
#Mann= 7 ,-1 , 0
  4328.3     .11       0  4744.8     .17       0  4960.6     .12       0
    4966     .09       0  5026.1     .12       0  5032.7     .17       0
  5203.6     .11       0
#XS Ineff= 2 , 0
       0  4897.8  271.83               0
Permanent Ineff=
       F       F
Bank Sta=4966,5026.1
XS Rating Curve= 0 ,0
Exp/Cntr=0.3,0.1

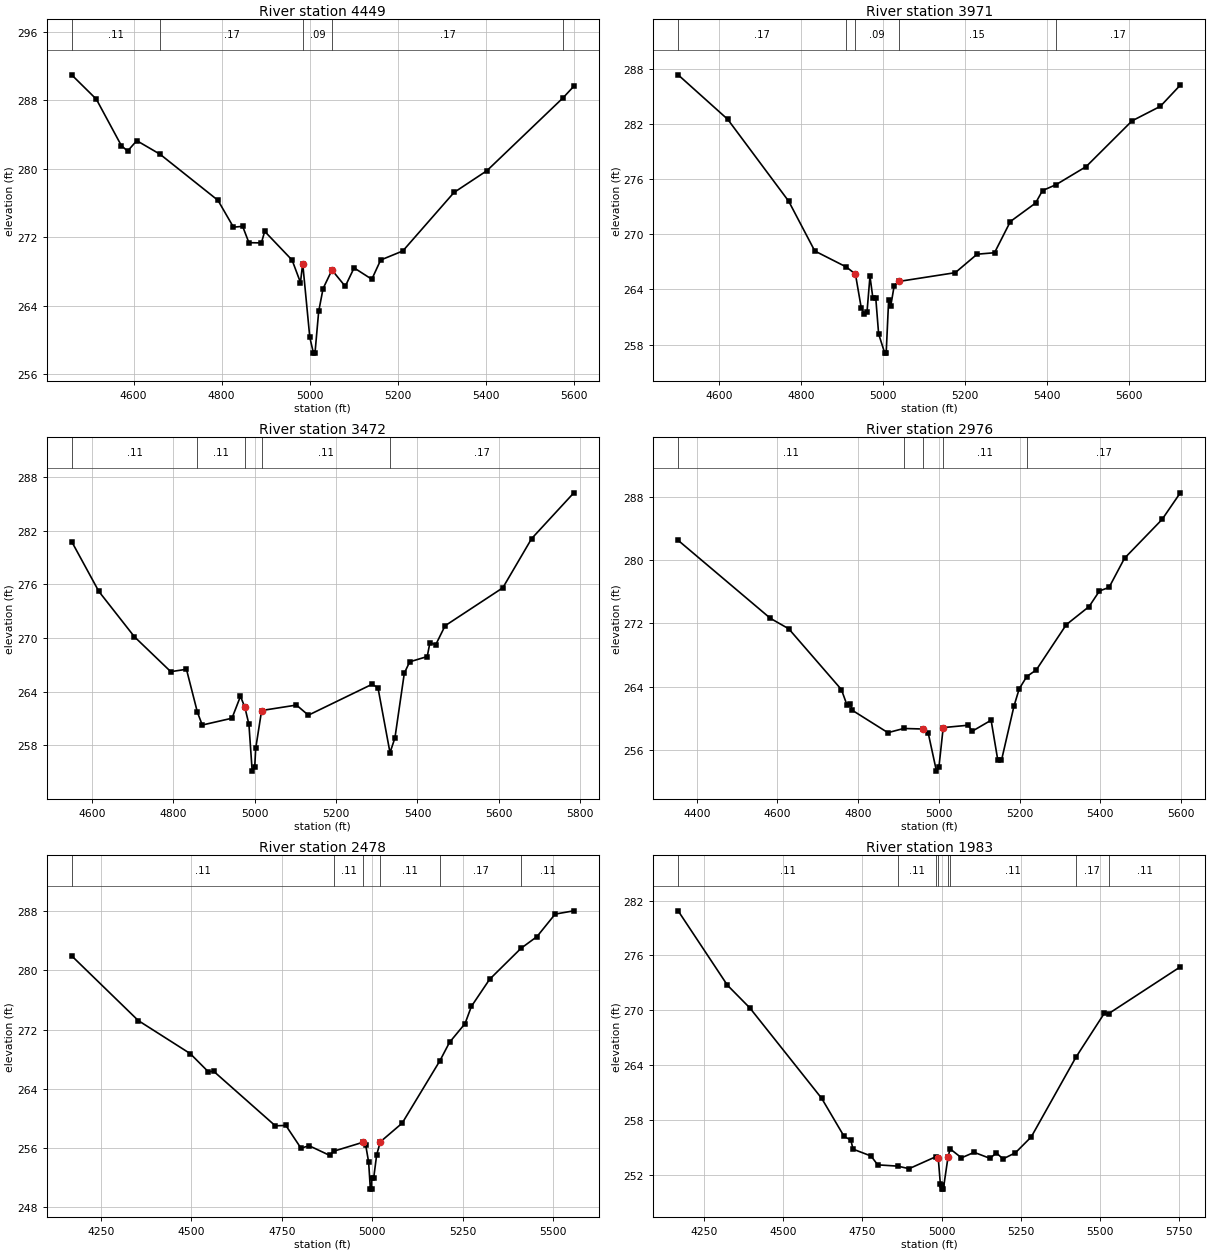
Type RM Length L Ch R = 1 ,4449    ,478,478,478
BEGIN DESCRIPTION:
LITTLE LAKE CREEK TRIB NO 5_1 9.0
END DESCRIPTION:
XS GIS Cut Line= 3
      3744670.42     10153412.95      3745027.89     10153090.75
      3745104.31     10152434.94
#Sta/Elev= 30
  4459.1     291  4515.2  288.15    4572  282.73  4586.2  282.08  4607.1   283.3
  4660.1  281.71  4791.7  276.32  4826.9  273.18  4847.8  273.28    4862  271.37
  4890.4  271.34  4897.9  272.69  4960.2  269.33  4979.2  266.71  4984.3  268.93
  5000.4  260.31  5008.7  258.45  5012.2  258.45  5020.6  263.32  5030.6     266
  5050.8  268.17    5081  266.26  5101.1  268.42  5141.4  267.09  5161.5  269.34
  5211.9   270.4  5328.2  277.24  5403.1  279.79  5576.5  288.33  5600.6  289.67
#Mann= 5 ,-1 , 0
  4459.1     .11       0  4660.1     .17       0  4984.3     .09       0
  5050.8     .17       0  5576.5     .11       0
Bank Sta=4984.3,5050.8
XS Rating Curve= 0 ,0
Exp/Cntr=0.3,0.1

Type RM Length L Ch R = 1 ,3971    ,499,499,499
BEGIN DESCRIPTION:
LITTLE LAKE CREEK TRIB NO 5_1 8.0
END DESCRIPTION:
XS GIS Cut Line= 3
      3745121.84     10153485.83      3745478.37     10153136.85
      3745233.17     10152455.31
#Sta/Elev= 30
  4501.1  287.37  4621.8  282.53  4770.4  273.61    4834  268.19  4911.2  266.44
    4933  265.67  4947.1  262.01  4954.3  261.35  4961.3   261.6  4968.4  265.44
  4975.4  263.09  4982.6  263.03  4989.5  259.16  5004.4  257.07  5007.9  257.07
  5013.9  262.87  5019.2  262.25  5027.4  264.41    5038  264.87  5176.2  265.83
  5229.3  267.84  5271.8     268  5310.4   271.4  5371.8  273.41  5388.7  274.77
  5421.6  275.41    5495  277.38  5606.8  282.36  5675.7  283.94  5724.3  286.25
#Mann= 5 ,-1 , 0
  4501.1     .17       0  4911.2     .15       0    4933     .09       0
    5038     .15       0  5421.6     .17       0
Bank Sta=4933,5038
XS Rating Curve= 0 ,0
Exp/Cntr=0.3,0.1

Type RM Length L Ch R = 1 ,3472    ,496,496,496
BEGIN DESCRIPTION:
LITTLE LAKE CREEK TRIB NO 5_1 7.0
END DESCRIPTION:
XS GIS Cut Line= 3
      3745833.62     10153649.04      3745961.09     10153217.37
      3746427.34     10152586.58
#Sta/Elev= 30
  4549.9  280.77  4616.7   275.2  4704.2  270.13  4793.6  266.23  4832.1   266.5
  4859.1  261.69    4871  260.27    4944  261.03  4964.9  263.48  4975.7  262.25
  4985.7  260.34  4993.7  255.12    5000  255.62  5002.3  257.65  5016.9  261.89
  5102.5   262.5  5131.8  261.37  5288.3  264.82  5302.9  264.44  5332.5  257.18
  5344.6  258.83  5367.7  266.07  5380.9  267.33    5424  267.92  5430.6  269.47
  5444.8  269.23  5467.9  271.36  5609.8   275.6  5680.7   281.1  5784.4  286.21
#Mann= 5 ,-1 , 0
  4549.9     .11       0  4859.1     .11       0  4975.7     .07       0
  5016.9     .11       0  5332.5     .17       0
#XS Ineff= 2 , 0
       0                  5288.3       0  264.82
Permanent Ineff=
       F       F
Bank Sta=4975.7,5016.9
XS Rating Curve= 0 ,0
Exp/Cntr=0.3,0.1

Type RM Length L Ch R = 1 ,2976    ,498,498,498
BEGIN DESCRIPTION:
LITTLE LAKE CREEK TRIB NO 5_1 6.0
END DESCRIPTION:
XS GIS Cut Line= 3
      3746083.64     10153774.02      3746430.27     10153228.77
      3746628.21     10152664.48
#Sta/Elev= 30
  4353.9  282.49  4582.5  272.65    4628  271.33  4758.4  263.67  4772.1  261.74
  4779.6   261.9  4785.5  261.05  4873.6  258.23  4912.9  258.76  4961.7  258.69
  4973.6  258.16  4993.9  253.38    5000  253.88  5010.6  258.87  5072.6  259.17
  5082.3  258.41  5129.3   259.8  5145.9  254.76    5155  254.74    5186  261.59
  5198.9  263.76  5217.7  265.31  5241.3  266.15  5315.5  271.85  5372.1  274.14
  5397.8  276.11  5421.5  276.55  5459.8  280.23  5552.8  285.12    5598  288.48
#Mann= 5 ,-1 , 0
  4353.9     .11       0  4912.9     .11       0  4961.7     .07       0
  5010.6     .11       0  5217.7     .17       0
Bank Sta=4961.7,5010.6
XS Rating Curve= 0 ,0
Exp/Cntr=0.3,0.1

Type RM Length L Ch R = 1 ,2478    ,495,495,495
BEGIN DESCRIPTION:
LITTLE LAKE CREEK TRIB NO 5_1 5.0
END DESCRIPTION:
XS GIS Cut Line= 3
      3746413.47     10153965.03      3746915.16     10153302.81
      3746975.97     10152749.74
#Sta/Elev= 30
  4169.2  281.94  4353.2  273.21  4496.7  268.75  4546.7   266.3  4561.2  266.38
  4731.8  259.01  4760.9  259.06  4802.6     256  4825.4  256.32  4881.6  255.03
  4892.7  255.58  4975.2  256.81  4981.5  256.39  4989.6  254.11  4994.3  250.47
  4997.8  250.47  4998.1  251.93  5003.4  251.93  5011.8  255.11  5021.9  256.85
  5082.2  259.37  5186.6   267.8    5213  270.27  5255.8  272.79  5273.4  275.12
  5323.7  278.77  5410.6  282.96  5454.5  284.53  5504.8  287.57  5556.4  288.01
#Mann= 6 ,-1 , 0
  4169.2     .11       0  4892.7     .11       0  4975.2     .07       0
  5021.9     .11       0  5186.6     .17       0  5410.6     .11       0
#XS Ineff= 2 , 0
       0  4760.9  259.06               0
Permanent Ineff=
       F       F
Bank Sta=4975.2,5021.9
XS Rating Curve= 0 ,0
Exp/Cntr=0.3,0.1

Type RM Length L Ch R = 1 ,1983    ,497,497,497
BEGIN DESCRIPTION:
LITTLE LAKE CREEK TRIB NO 5_1 4.0
END DESCRIPTION:
XS GIS Cut Line= 4
      3746667.86     10154211.07      3747248.21     10153616.72
      3747266.48      10153596.9      3747250.28     10152871.24
#Sta/Elev= 30
  4169.3  280.89  4324.8  272.74  4395.5  270.25  4621.9  260.35  4692.6  256.18
  4713.9  255.77  4720.9  254.78  4777.5  254.03  4798.6  253.06  4861.4  252.92
  4897.6  252.64  4982.5  253.96  4989.6  253.78  4996.2  250.95  5001.9   250.9
  5002.1   250.4  5005.6   250.4 5020.43  253.94    5027  254.81  5062.8  253.83
  5102.8  254.43  5152.8  253.77  5172.8  254.37  5193.7  253.71  5232.8  254.38
  5282.8  256.12  5423.5  264.84  5512.9  269.65  5527.4  269.64  5752.8  274.75
#Mann= 8 ,-1 , 0
  4169.3     .11       0  4861.4     .11       0  4982.5     .11       0
  4989.6     .07       0 5020.43     .11       0    5027     .11       0
  5423.5     .17       0  5527.4     .11       0
Bank Sta=4989.6,5020.43
XS Rating Curve= 0 ,0
Exp/Cntr=0.3,0.1

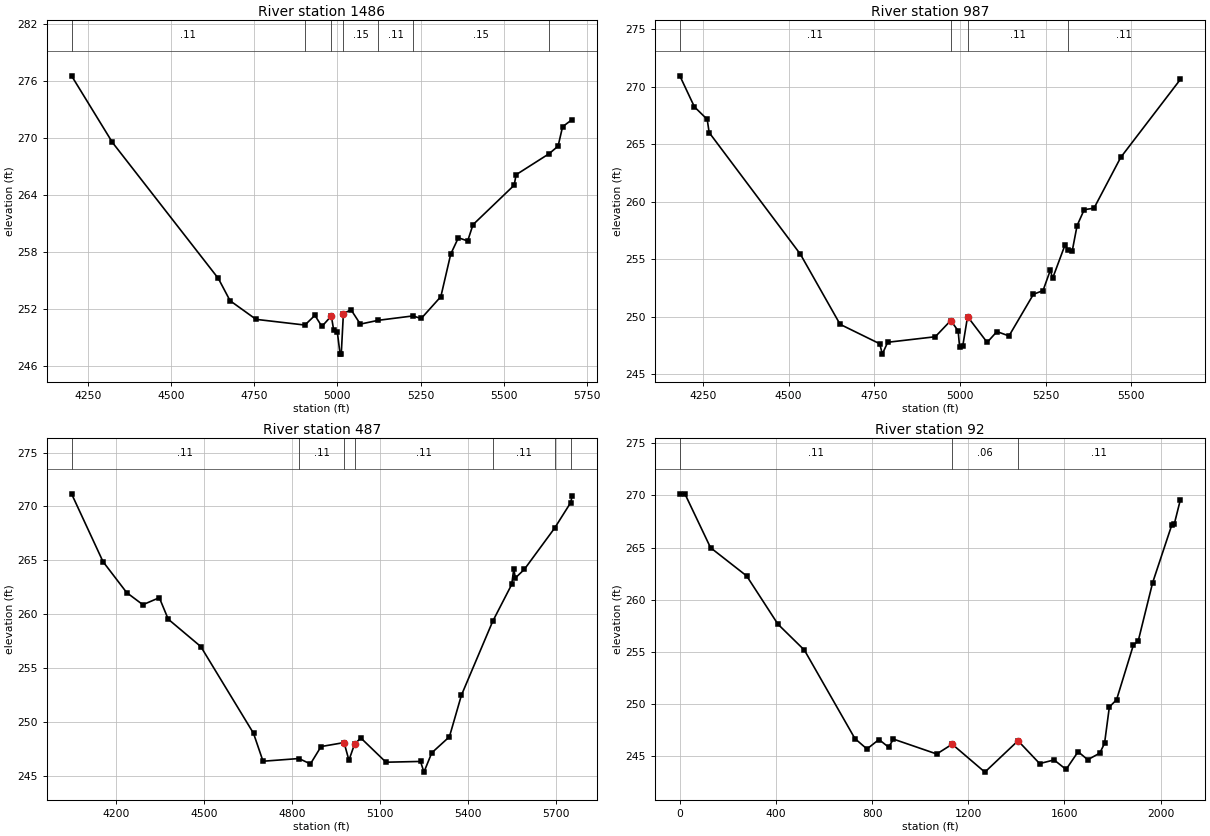
Type RM Length L Ch R = 1 ,1486    ,499,499,499
BEGIN DESCRIPTION:
LITTLE LAKE CREEK TRIB NO 5_1 3.0
END DESCRIPTION:
XS GIS Cut Line= 3
      3746955.14     10154551.84      3747532.05     10153999.92
      3748144.52     10153649.97
#Sta/Elev= 30
  4201.6  276.59  4324.3  269.58  4642.6  255.26  4677.8  252.92  4755.8  250.96
  4902.6  250.36  4932.6  251.38  4953.6  250.21    4982  251.32  4989.2  249.79
    5000  249.61  5008.3   247.3  5011.8   247.3  5018.2  251.56  5041.2  251.97
  5069.1  250.46  5123.1  250.86    5227  251.32    5252  251.05    5311  253.35
  5340.7  257.83  5363.7  259.55  5391.6  259.21  5407.5  260.92  5531.3  265.08
    5537  266.18  5636.1  268.39  5663.2  269.19  5676.7  271.23  5705.4  271.99
#Mann= 7 ,-1 , 0
  4201.6     .11       0  4902.6     .15       0    4982     .07       0
  5018.2     .15       0  5123.1     .11       0    5227     .15       0
  5636.1     .17       0
Bank Sta=4982,5018.2
XS Rating Curve= 0 ,0
Exp/Cntr=0.3,0.1

Type RM Length L Ch R = 1 ,987     ,500,500,500
BEGIN DESCRIPTION:
LITTLE LAKE CREEK TRIB NO 5_1 2.0
END DESCRIPTION:
XS GIS Cut Line= 3
      3747173.93     10154746.26      3747879.97     10154334.97
      3748298.86     10153847.01
#Sta/Elev= 30
  4182.9  270.94  4225.5  268.24  4262.7  267.16  4268.5  266.01  4534.6  255.44
  4650.4  249.35  4766.1  247.66  4773.6  246.76  4789.2  247.79  4928.1  248.27
  4973.3  249.68  4994.8  248.78  4998.9  247.42  5008.1  247.44  5022.3  250.02
  5079.4  247.78  5107.9  248.72  5143.1  248.34  5214.4  251.96  5242.4  252.28
  5263.8  254.06  5270.4  253.35  5306.6  256.25  5314.9   255.8  5327.4  255.69
  5341.7  257.92  5362.5  259.31  5391.1  259.44    5469  263.85  5643.1  270.63
#Mann= 4 ,-1 , 0
  4182.9     .11       0  4973.3     .07       0  5022.3     .11       0
  5314.9     .11       0
Bank Sta=4973.3,5022.3
XS Rating Curve= 0 ,0
Exp/Cntr=0.3,0.1

Type RM Length L Ch R = 1 ,487     ,395,395,395
BEGIN DESCRIPTION:
LITTLE LAKE CREEK TRIB NO 5_1 1.0
END DESCRIPTION:
XS GIS Cut Line= 3
      3747201.66     10154787.95      3748144.19     10154662.88
      3748413.16     10153958.91
#Sta/Elev= 30
  4049.2  271.17  4156.3  264.88    4237  262.01    4292  260.89    4348  261.54
  4378.3  259.55  4489.2  257.01  4668.7  248.97  4701.1  246.38  4823.3  246.63
  4862.5  246.13  4898.7  247.74  4977.1  248.11  4993.6  246.47  5012.6  247.95
    5034  248.54  5119.7  246.29  5237.4  246.36    5249  245.37  5275.7  247.16
  5335.8  248.65  5376.6   252.5    5483  259.34  5547.9  262.77  5554.9   264.2
  5560.3  263.37  5590.7  264.16  5693.7  267.98  5748.8  270.36  5753.6  270.97
#Mann= 7 ,-1 , 0
  4049.2     .11       0  4823.3     .11       0  4977.1     .07       0
  5012.6     .11       0    5483     .11       0  5693.7     .17       0
  5748.8     .11       0
Bank Sta=4977.1,5012.6
XS Rating Curve= 0 ,0
Exp/Cntr=0.3,0.1

Type RM Length L Ch R = 1 ,92      ,0,0,0
XS GIS Cut Line= 3
      3747210.15     10154846.94      3748487.35      10154789.5
      3748485.83     10153985.04
#Sta/Elev= 30
       0  270.16    21.1  270.16   127.8  264.99     278  262.28   408.1  257.65
   518.2  255.16   728.4  246.67   778.5  245.67   828.5  246.58   868.6  245.84
   888.6  246.62  1068.8  245.19    1133  246.13    1269  243.45  1406.9  246.46
  1496.9  244.27  1556.9  244.62  1606.9  243.71  1656.9  245.41  1696.9  244.64
  1746.9  245.27  1766.9  246.21  1786.9   249.7  1816.9   250.4  1886.9  255.65
  1906.9  256.03  1966.9  261.63  2046.9  267.19  2056.9  267.25  2082.4   269.6
#Mann= 3 , 0 , 0
       0     .11       0    1133     .06       0  1406.9     .11       0
Bank Sta=1133,1406.9
XS Rating Curve= 0 ,0
Exp/Cntr=0.3,0.1
Stream Node=LITTLE LAKE CREE,Reach-1         , 0 , 0 ,Upstream end
Stream Node=LITTLE LAKE CREE,Reach-1         , 0 , 1 ,Downstream end

Chan Stop Cuts=-1
Use User Specified Reach Order=0
Composite Channel Slope=5