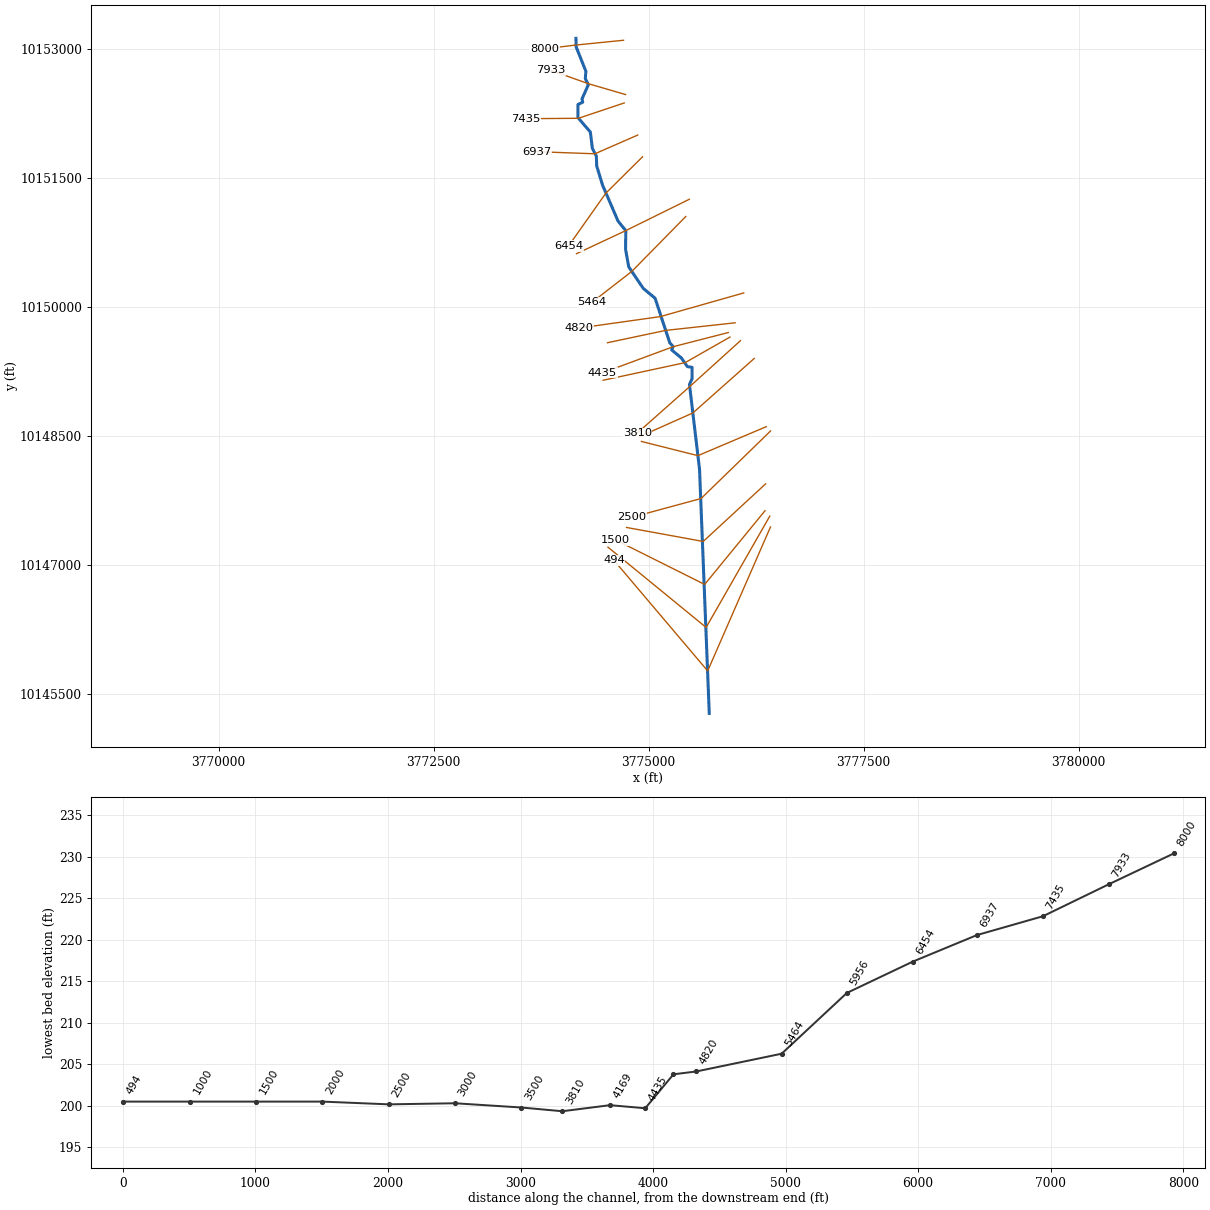
--- LITTLE LAKE CREEK TRIB NO 6.prj (project) ---

Proj Title=LITTLE LAKE CREEK TRIB NO 6 Base Level Engineering
Current Plan=p01
Default Exp/Contr=0.3,0.1
English Units
Geom File=g01
Flow File=f01
Plan File=p01
Y Axis Title=Elevation
X Axis Title(PF)=Main Channel Distance
X Axis Title(XS)=Station
BEGIN DESCRIPTION:
LITTLE LAKE CREEK TRIB NO 6
END DESCRIPTION:
DSS Export Rating Curves= 0
DSS Export Rating Curve Sorted= 0
DSS Export Volume Flow Curves= 0
DXF OffsetX= 0
DXF OffsetY= 0
DXF ScaleX= 1
DXF ScaleY= 10

--- LITTLE LAKE CREEK TRIB NO 6.p01 (plan) ---

Plan Title=Multiple Run
Short Identifier=Multiple
Geom File=g01
Flow File=f01
Subcritical Flow
K Sum by GR= 0
Std Step Tol= 0.01
Critical Tol= 0.01
Num of Std Step Trials= 20
Max Error Tol= 0.3
Flow Tol Ratio= 0.001
Split Flow NTrial= 30
Split Flow Tol= 0.02
Split Flow Ratio= 0.02
Log Output Level= 0
Friction Slope Method= 1
Unsteady Friction Slope Method= 2
Unsteady Bridges Friction Slope Method= 1
Parabolic Critical Depth
Global Vel Dist=  1 , 1 , 1
Global Log Level= 0
CheckData=True
Encroach Param= -1, 0, 0, 0
BEGIN DESCRIPTION:
Multiple Run
END DESCRIPTION:

--- LITTLE LAKE CREEK TRIB NO 6.f01 (steady flow) ---

Flow Title=Multiple
Program Version=4.10
Number of Profiles= 7
Profile Names=10-year,25-year,50-year,1pct_min,100-year,1pct_plu,500-year
River Rch & RM=LITTLE LAKE CREE,Reach-1         ,8000
     829    1140    1557     699    2110    6372    4006
River Rch & RM=LITTLE LAKE CREE,Reach-1         ,7933
     829    1140    1557     699    2110    6372    4006
Boundary for River Rch & Prof#=LITTLE LAKE CREE,Reach-1         , 1
Up Type= 0
Dn Type= 3
Dn Slope=0.0001
Boundary for River Rch & Prof#=LITTLE LAKE CREE,Reach-1         , 2
Up Type= 0
Dn Type= 3
Dn Slope=0.0001
Boundary for River Rch & Prof#=LITTLE LAKE CREE,Reach-1         , 3
Up Type= 0
Dn Type= 3
Dn Slope=0.0001
Boundary for River Rch & Prof#=LITTLE LAKE CREE,Reach-1         , 4
Up Type= 0
Dn Type= 3
Dn Slope=0.0001
Boundary for River Rch & Prof#=LITTLE LAKE CREE,Reach-1         , 5
Up Type= 0
Dn Type= 3
Dn Slope=0.0001
Boundary for River Rch & Prof#=LITTLE LAKE CREE,Reach-1         , 6
Up Type= 0
Dn Type= 3
Dn Slope=0.0001
Boundary for River Rch & Prof#=LITTLE LAKE CREE,Reach-1         , 7
Up Type= 0
Dn Type= 3
Dn Slope=0.0001
DSS Import GetInterval= 0
DSS Import GetPeak= 0
DSS Import FillOption= 0

--- LITTLE LAKE CREEK TRIB NO 6.g01 (geometry) ---

Geom Title=Existing Conditions
Program Version=4.10

River Reach=LITTLE LAKE CREE,Reach-1
Reach XY= 30
      3774155.01     10153126.32      3774156.17     10153028.58
      3774270.31     10152743.01      3774263.46     10152658.73
      3774298.61     10152585.81      3774225.54     10152423.27
      3774233.08     10152383.74       3774177.7     10152356.51
      3774177.56     10152204.38      3774322.23     10152036.63
      3774345.46     10151847.04      3774391.63     10151756.47
      3774396.08     10151641.09      3774464.97     10151416.93
      3774643.84     10151001.47      3774734.08      10150890.5
      3774731.81     10150672.37      3774768.18     10150469.04
      3774937.62     10150218.34      3775074.43     10150104.45
      3775246.12     10149585.24      3775284.62     10149542.69
      3775266.74     10149504.04      3775380.29     10149409.73
      3775450.79     10149309.28      3775504.98     10149300.95
      3775504.74      10149167.6      3775474.37     10149102.67
      3775591.59     10148114.94      3775704.73     10145277.12

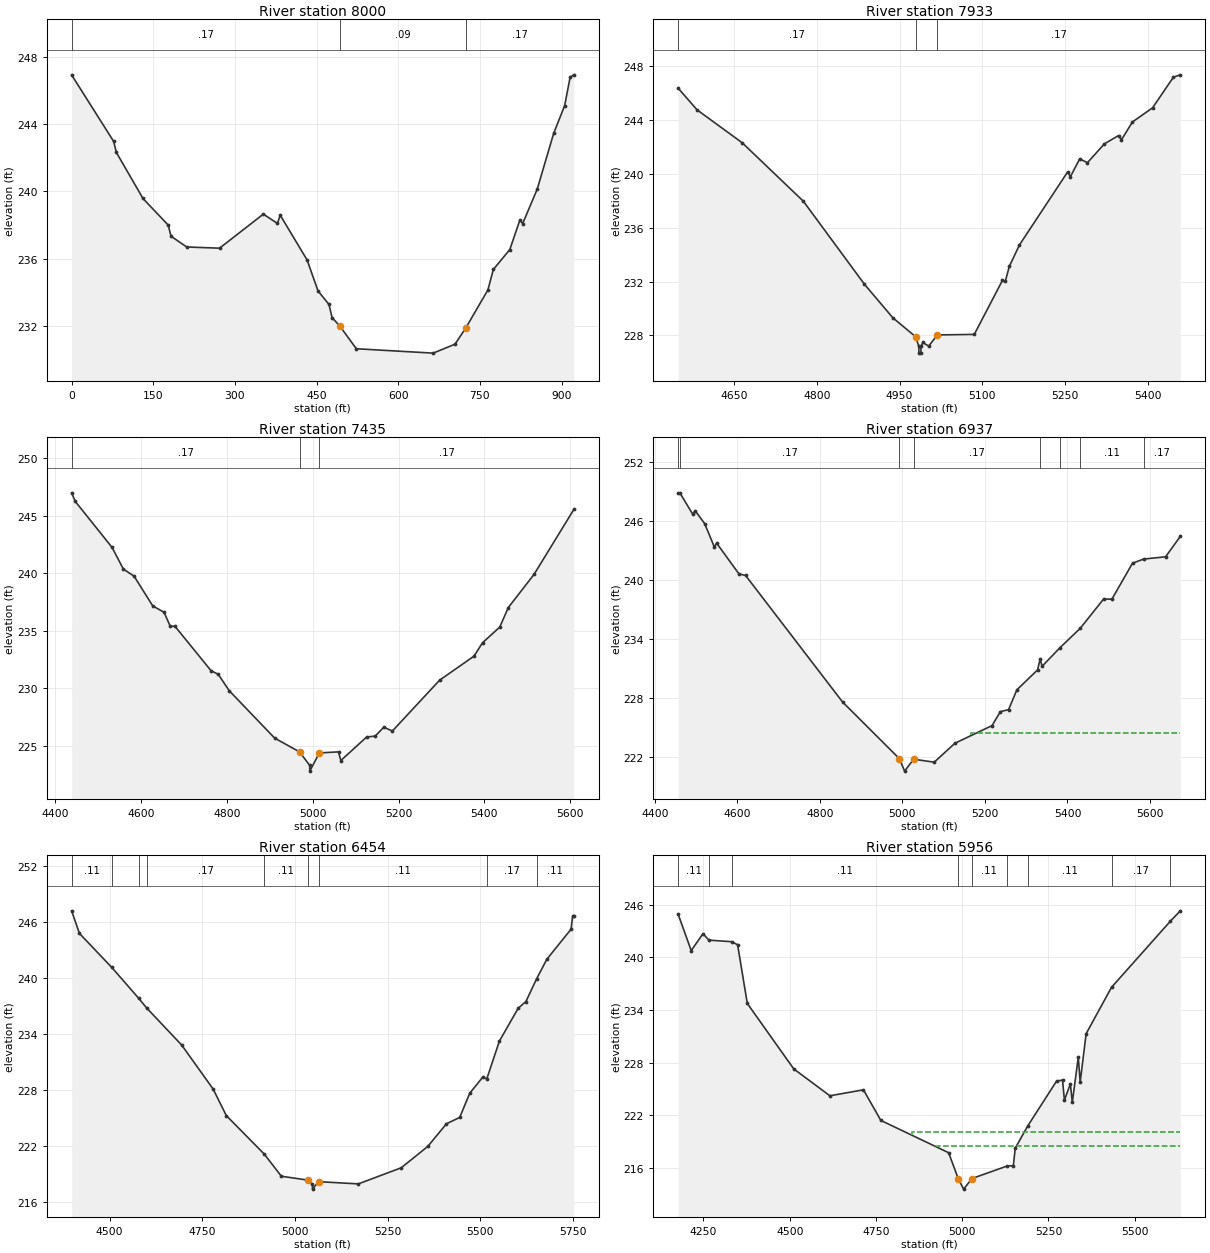
Type RM Length L Ch R = 1 ,8000    ,490,490,490
XS GIS Cut Line= 3
      3774708.18     10153103.92      3774154.78     10153048.37
       3773789.3     10153004.44
#Sta/Elev= 30
       0  246.91    77.1  242.97    82.2  242.31     131  239.58   177.4     238
   182.5  237.34   211.4   236.7   271.7  236.63   352.1  238.65   378.1   238.1
   383.1  238.59   432.5  235.93   452.6  234.09   472.7  233.29   478.4  232.51
   492.8     232   522.9  230.66   664.1   230.4   704.2  230.93   724.3  231.91
   764.6  234.15   774.7  235.37   804.9  236.55   823.4   238.3   828.5  238.09
   855.2  240.13   885.5  243.45   905.6  245.09   915.7  246.78   922.5  246.92
#Mann= 3 , 0 , 0
       0     .17       0   492.8     .09       0   724.3     .17       0
Bank Sta=492.8,724.3
XS Rating Curve= 0 ,0
Exp/Cntr=0.3,0.1

Type RM Length L Ch R = 1 ,7933    ,498,498,498
BEGIN DESCRIPTION:
LITTLE LAKE CREEK TRIB NO 6 1.0
END DESCRIPTION:
XS GIS Cut Line= 3
      3774731.11     10152472.66      3774298.09     10152599.09
      3773866.18     10152753.25
#Sta/Elev= 30
  4548.9  246.36  4583.5  244.74  4664.9  242.31  4775.7  237.97  4886.5   231.8
  4937.7  229.32  4979.4   227.9  4984.9  227.19  4985.2  226.69  4988.7  226.69
  4988.9  227.19  4992.1  227.48  5002.8  227.21  5018.5  228.04  5085.4  228.08
  5136.4  232.09  5141.7  232.04  5148.9  233.13  5167.2  234.72  5254.3  240.13
  5259.6  239.79  5276.3  241.11  5290.4  240.83  5321.2  242.23  5346.7  242.84
    5352  242.53  5371.9  243.85  5408.3   244.9  5446.2  247.18  5458.6  247.35
#Mann= 3 ,-1 , 0
  4548.9     .17       0  4979.4     .09       0  5018.5     .17       0
Bank Sta=4979.4,5018.5
XS Rating Curve= 0 ,0
Exp/Cntr=0.3,0.1

Type RM Length L Ch R = 1 ,7435    ,498,498,498
BEGIN DESCRIPTION:
LITTLE LAKE CREEK TRIB NO 6 2.0
END DESCRIPTION:
XS GIS Cut Line= 3
      3774715.72     10152374.83       3774183.5     10152196.51
      3773575.21     10152192.04
#Sta/Elev= 30
  4438.7  246.97    4447  246.23  4532.9  242.23  4559.2  240.35  4584.1  239.74
  4627.6  237.16  4653.9  236.61  4668.5  235.38    4679  235.41  4763.4  231.54
  4780.1  231.23  4805.6  229.81  4911.6  225.69  4969.5   224.5  4993.1  223.33
  4993.3  222.83  5015.6  224.41  5060.2   224.5  5065.6  223.75  5125.7  225.79
  5145.7  225.87  5165.7  226.64  5185.7  226.31  5295.7  230.72  5375.7   232.8
  5395.7  233.97  5435.7  235.32  5455.7  237.02  5515.7   239.9  5608.3  245.53
#Mann= 3 ,-1 , 0
  4438.7     .17       0  4969.5     .09       0  5015.6     .17       0
Bank Sta=4969.5,5015.6
XS Rating Curve= 0 ,0
Exp/Cntr=0.3,0.1

Type RM Length L Ch R = 1 ,6937    ,483,483,483
BEGIN DESCRIPTION:
LITTLE LAKE CREEK TRIB NO 6 3.0
END DESCRIPTION:
XS GIS Cut Line= 3
      3774872.76     10152001.55      3774374.98     10151783.84
      3773702.13     10151808.43
#Sta/Elev= 30
  4456.7  248.84  4460.9  248.84  4492.3  246.65  4497.8  247.03  4521.2   245.7
  4544.6  243.32    4550  243.73  4603.9  240.61  4620.2  240.44    4855  227.59
  4992.9  221.82  5005.4  220.56  5027.2  221.77  5077.2  221.47  5127.2  223.39
  5217.3  225.19  5237.3   226.6  5257.3  226.81  5277.3  228.82  5327.4  230.84
  5333.8  231.94  5338.6  231.22  5381.5  233.09    5431  235.08  5487.5  238.05
  5507.5  238.03  5557.5  241.69  5584.5  242.11  5637.6  242.34  5673.3  244.41
#Mann= 8 ,-1 , 0
  4456.7     .11       0  4460.9     .17       0  4992.9     .09       0
  5027.2     .17       0  5333.8     .11       0  5381.5     .17       0
    5431     .11       0  5584.5     .17       0
#XS Ineff= 2 , 0
       0                  5167.2       0  224.39
Permanent Ineff=
       F       F
Bank Sta=4992.9,5027.2
XS Rating Curve= 0 ,0
Exp/Cntr=0.3,0.1

Type RM Length L Ch R = 1 ,6454    ,498,498,498
BEGIN DESCRIPTION:
LITTLE LAKE CREEK TRIB NO 6 4.0
END DESCRIPTION:
XS GIS Cut Line= 3
      3774929.38     10151749.25      3774501.68     10151325.18
      3774067.84     10150711.06
#Sta/Elev= 30
  4397.7  247.18  4418.7  244.76  4506.1  241.11  4578.1  237.83  4600.5  236.75
  4694.5   232.8  4779.4  228.08  4814.7  225.25  4917.4  221.11  4963.2  218.75
  5034.1  218.34  5046.9  217.87  5047.2  217.37  5063.7  218.17  5170.8  217.93
  5286.6  219.66  5357.9  221.94  5408.4  224.37  5444.1  225.05  5471.2  227.64
    5507   229.4  5517.1  229.17  5551.2  233.23  5601.7  236.74  5622.6  237.46
  5651.4  239.89  5679.2     242  5744.5  245.22  5748.8  246.65  5751.9  246.65
#Mann= 9 ,-1 , 0
  4397.7     .11       0  4506.1     .17       0  4578.1     .11       0
  4600.5     .17       0  4917.4     .11       0  5034.1     .06       0
  5063.7     .11       0  5517.1     .17       0  5651.4     .11       0
Bank Sta=5034.1,5063.7
XS Rating Curve= 0 ,0
Exp/Cntr=0.3,0.1

Type RM Length L Ch R = 1 ,5956    ,492,492,492
BEGIN DESCRIPTION:
LITTLE LAKE CREEK TRIB NO 6 5.0
END DESCRIPTION:
XS GIS Cut Line= 3
      3775472.54     10151254.96      3774734.08      10150890.5
      3774161.21     10150622.41
#Sta/Elev= 30
  4176.5  244.94  4214.4  240.78  4248.6   242.7  4265.8  241.97  4332.1  241.79
    4349  241.44  4377.1  234.75  4511.8  227.29  4616.6  224.23  4713.8  224.91
  4764.3  221.42  4960.8  217.74  4988.8  214.77  5004.2  213.59  5028.7   214.8
  5128.6   216.2  5148.4  216.27    5154  218.26  5189.5  220.75  5273.7   225.9
    5291  226.02  5296.5  223.73  5313.8  225.58  5319.3  223.47  5336.7  228.62
  5342.2  225.79  5359.5  231.31  5433.2   236.6  5603.9  244.14  5632.5  245.31
#Mann= 9 ,-1 , 0
  4176.5     .11       0  4265.8     .17       0  4332.1     .11       0
  4988.8     .06       0  5028.7     .11       0  5128.6     .17       0
  5189.5     .11       0  5433.2     .17       0  5603.9     .11       0
#XS Ineff= 3 ,-1
  4960.8  4921.5  217.74  4921.5  4884.3  218.51  4854.1  4817.4  220.11
Permanent Ineff=
       F       F       F
Bank Sta=4988.8,5028.7
XS Rating Curve= 0 ,0
Exp/Cntr=0.3,0.1

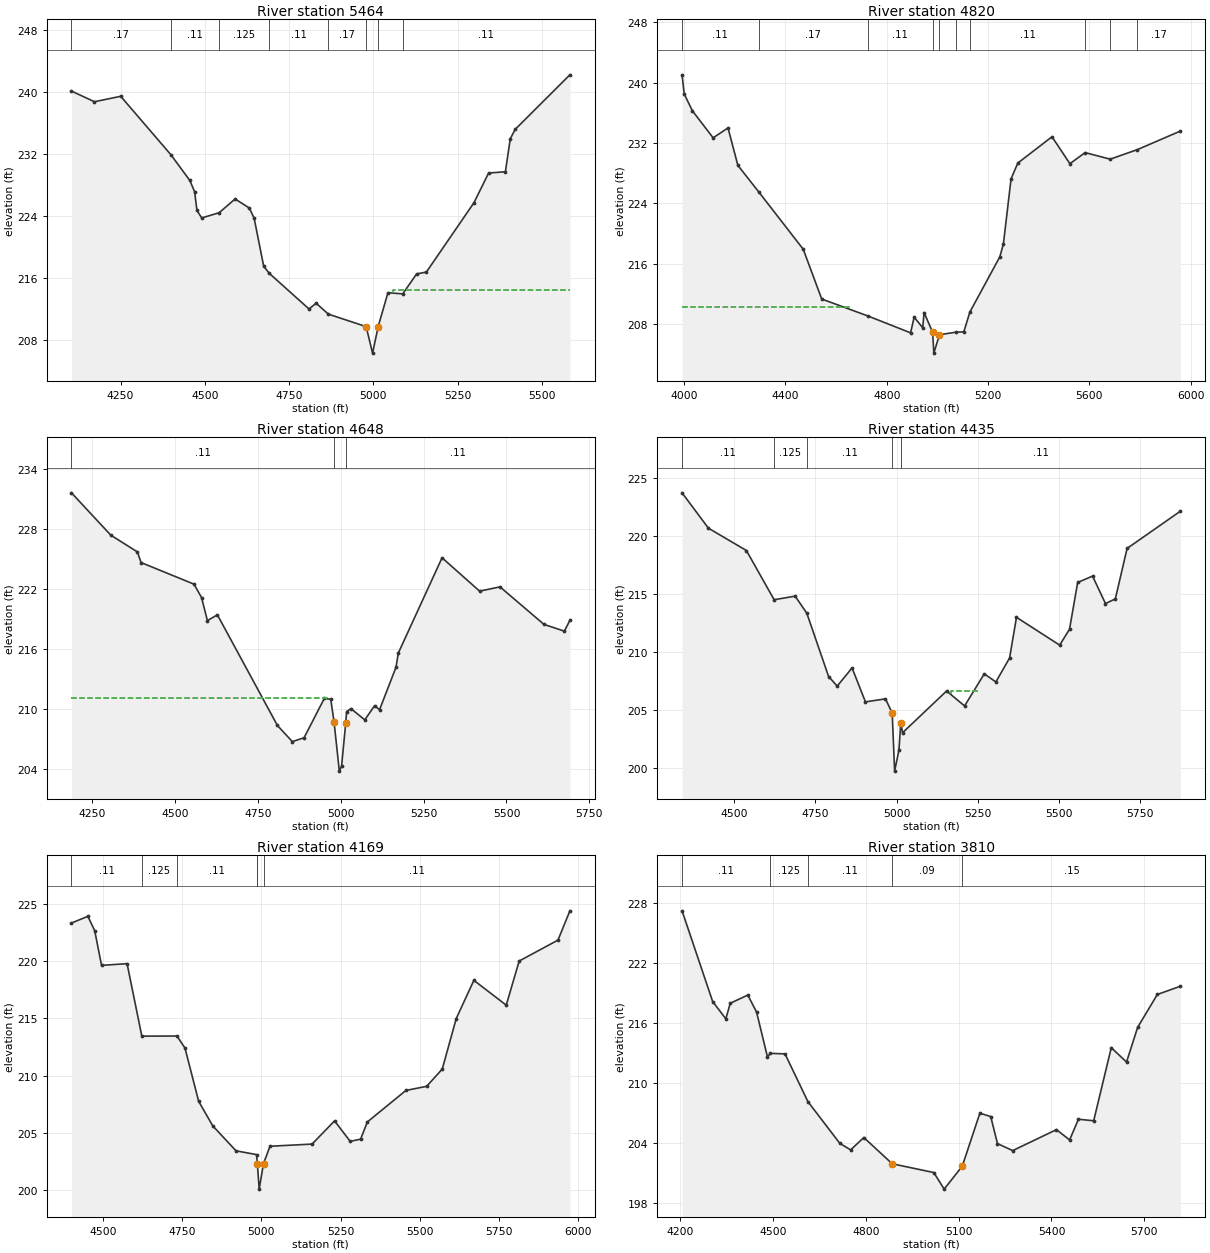
Type RM Length L Ch R = 1 ,5464    ,644,644,644
BEGIN DESCRIPTION:
LITTLE LAKE CREEK TRIB NO 6 6.0
END DESCRIPTION:
XS GIS Cut Line= 3
      3775431.38     10151054.17       3774803.6     10150415.57
       3774342.6     10150058.02
#Sta/Elev= 30
  4104.5  240.08  4172.8  238.71  4250.6  239.41  4399.5  231.87  4455.7  228.55
  4469.8  227.11  4476.9  224.68    4491  223.71  4542.8  224.39    4590  226.16
  4632.4  224.99  4646.6  223.66  4674.9  217.48  4691.3  216.57  4809.3  211.97
  4830.5  212.71  4866.8   211.3  4978.9  209.69  4997.9  206.27  5014.5  209.69
  5043.5  214.06  5087.5  213.92  5128.6  216.49  5157.6  216.73  5298.8  225.68
  5342.2  229.51    5392  229.67  5406.5  233.93    5421  235.14  5583.4  242.18
#Mann= 8 ,-1 , 0
  4104.5     .17       0  4399.5     .11       0  4542.8    .125       0
  4691.3     .11       0  4866.8     .17       0  4978.9     .07       0
  5014.5     .17       0  5087.5     .11       0
#XS Ineff= 2 , 0
       0  4830.5  212.71  5057.9       0  214.48
Permanent Ineff=
       F       F
Bank Sta=4978.9,5014.5
XS Rating Curve= 0 ,0
Exp/Cntr=0.3,0.1

Type RM Length L Ch R = 1 ,4820    ,172,172,172
BEGIN DESCRIPTION:
LITTLE LAKE CREEK TRIB NO 6 7.0
END DESCRIPTION:
XS GIS Cut Line= 3
       3776105.9     10150166.02      3775136.14     10149890.65
      3774185.43     10149756.69
#Sta/Elev= 30
  3991.9  241.02  4000.3   238.5  4032.5  236.26  4114.6  232.67  4173.3  233.98
  4212.4  229.01  4294.7   225.5  4470.4   217.9  4543.4   211.3  4724.6  209.07
  4894.3  206.82  4908.4   208.9  4942.3  207.49  4947.5  209.51  4981.4  206.89
  4986.1  204.13  5008.4  206.57  5074.9  206.91  5104.4  206.95  5128.6  209.59
  5246.8   216.9  5260.8   218.6  5291.1  227.25  5317.9  229.33  5452.7  232.81
  5523.4  229.24  5583.5  230.71  5682.6  229.84  5790.1  231.11  5960.1  233.57
#Mann= 10 ,-1 , 0
  3991.9     .11       0  4294.7     .17       0  4724.6     .11       0
  4981.4     .06       0  5008.4     .11       0  5074.9     .17       0
  5128.6     .11       0  5583.5    .125       0  5682.6     .11       0
  5790.1     .17       0
#XS Ineff= 2 , 0
       0  4655.5   210.3               0
Permanent Ineff=
       F       F
Bank Sta=4981.4,5008.4
XS Rating Curve= 0 ,0
Exp/Cntr=0.3,0.1

Type RM Length L Ch R = 1 ,4648    ,213,213,213
BEGIN DESCRIPTION:
LITTLE LAKE CREEK TRIB NO 6 8.0
END DESCRIPTION:
XS GIS Cut Line= 3
       3776005.5     10149818.47      3775197.91     10149730.21
      3774521.48     10149587.08
#Sta/Elev= 30
  4187.6  231.64  4306.4   227.4  4386.4  225.73  4397.7  224.66  4557.4   222.5
  4580.2  221.15  4597.7  218.85  4627.9  219.43  4808.9  208.36  4854.1  206.74
  4889.4  207.13  4950.4  211.06  4969.9  210.98  4979.9  208.71  4995.8  203.79
  5002.6  204.29  5015.1 208.623  5017.7  209.74  5030.7  210.05  5072.5  208.92
  5102.3  210.34  5117.1  209.93  5166.8  214.19  5173.8  215.61  5305.7  225.14
  5419.1   221.8  5480.5  222.23  5613.3  218.47  5674.7   217.8  5691.4  218.88
#Mann= 3 ,-1 , 0
  4187.6     .11       0  4979.9     .07       0  5015.1     .11       0
#XS Ineff= 2 , 0
       0  4959.8   211.1  5030.7       0  210.05
Permanent Ineff=
       T       T
Bank Sta=4979.9,5015.1
XS Rating Curve= 0 ,0
Exp/Cntr=0.3,0.1

Type RM Length L Ch R = 1 ,4435    ,266,266,266
BEGIN DESCRIPTION:
LITTLE LAKE CREEK TRIB NO 6 9.0
END DESCRIPTION:
XS GIS Cut Line= 3
      3775925.69     10149705.21      3775284.96     10149540.75
      3774463.43     10149236.67
#Sta/Elev= 30
  4338.5  223.73  4419.7  220.68  4536.9  218.75  4622.5   214.5  4687.3  214.81
  4723.4  213.33  4790.5  207.87    4817  207.04  4862.9  208.61  4904.1  205.68
    4966  205.94  4986.7  204.71  4994.2   199.7  5007.6  201.53  5013.2  203.89
  5018.5  203.01  5154.5  206.62    5210  205.33  5270.8   208.1  5306.5   207.4
  5348.8  209.47  5370.1  212.98  5503.3  210.58  5533.7  211.95  5558.8  215.99
  5604.7  216.54  5644.6  214.17    5675  214.57  5711.3  218.93    5876  222.15
#Mann= 5 ,-1 , 0
  4338.5     .11       0  4622.5    .125       0  4723.4     .11       0
  4986.7     .05       0  5013.2     .11       0
#XS Ineff= 3 ,-1
  4862.9  4781.4  208.61  5167.5  5252.8  206.66  5270.8  5326.3   208.1
Permanent Ineff=
       F       F       F
Bank Sta=4986.7,5013.2
XS Rating Curve= 0 ,0
Exp/Cntr=0.3,0.1

Type RM Length L Ch R = 1 ,4169    ,359,359,359
BEGIN DESCRIPTION:
Mapping XS 222ab995
END DESCRIPTION:
XS GIS Cut Line= 3
      3775945.99     10149652.91      3775424.35     10149355.64
      3774471.14     10149150.68
#Sta/Elev= 30
  4399.6  223.34  4451.5  223.93  4473.1  222.67  4494.7  219.64  4575.4  219.79
    4622  213.45  4733.1  213.46  4758.4  212.41  4801.6  207.75  4846.3   205.6
  4919.7  203.42  4984.6  203.09 4987.24  202.27  4992.9  200.07  5006.6   202.3
  5027.1  203.82  5160.1  204.01  5231.2  206.04  5280.5  204.25  5313.5  204.44
    5335  205.95  5456.7   208.7  5522.2  209.06  5571.6  210.57  5615.8  214.99
  5671.5  218.33  5773.8  216.16  5814.7  220.02  5937.4  221.85    5975  224.41
#Mann= 6 ,-1 , 0
  4399.6     .11       0    4622    .125       0  4733.1     .11       0
  4984.6     .11       0 4987.24     .07       0  5006.6     .11       0
#XS Ineff= 2 , 0
       0                  5231.2       0  206.04
Permanent Ineff=
       F       F
Bank Sta=4987.24,5006.6
XS Rating Curve= 0 ,0
Exp/Cntr=0.3,0.1

Type RM Length L Ch R = 1 ,3810    ,310,310,310
BEGIN DESCRIPTION:
LITTLE LAKE CREEK TRIB NO 6 10.0
END DESCRIPTION:
XS GIS Cut Line= 3
      3776067.87     10149611.09      3775478.75     10149078.02
      3774866.97     10148536.23
#Sta/Elev= 30
  4205.5  227.22  4304.5  218.13  4347.1   216.4  4361.3  217.96  4418.1  218.78
  4446.5  217.07  4481.6  212.59    4491  212.94  4538.4  212.89  4612.3  208.11
  4715.5  203.93  4750.6  203.27  4793.2  204.51  4885.1  201.88  5019.6     201
    5053  199.34  5111.6  201.64  5168.5  206.95  5203.6  206.61  5225.4   203.9
  5274.7   203.2  5416.1   205.3  5458.7  204.27  5487.2  206.34  5536.5  206.19
  5593.4  213.51  5642.7  212.07  5678.7  215.55  5742.3  218.84  5817.2  219.67
#Mann= 5 ,-1 , 0
  4205.5     .11       0    4491    .125       0  4612.3     .11       0
  4885.1     .09       0  5111.6     .15       0
#XS Ineff= 2 , 0
       0  4793.2  204.51  5168.5       0  206.95
Permanent Ineff=
       F       T
Bank Sta=4885.1,5111.6
XS Rating Curve= 0 ,0
Exp/Cntr=0.3,0.1

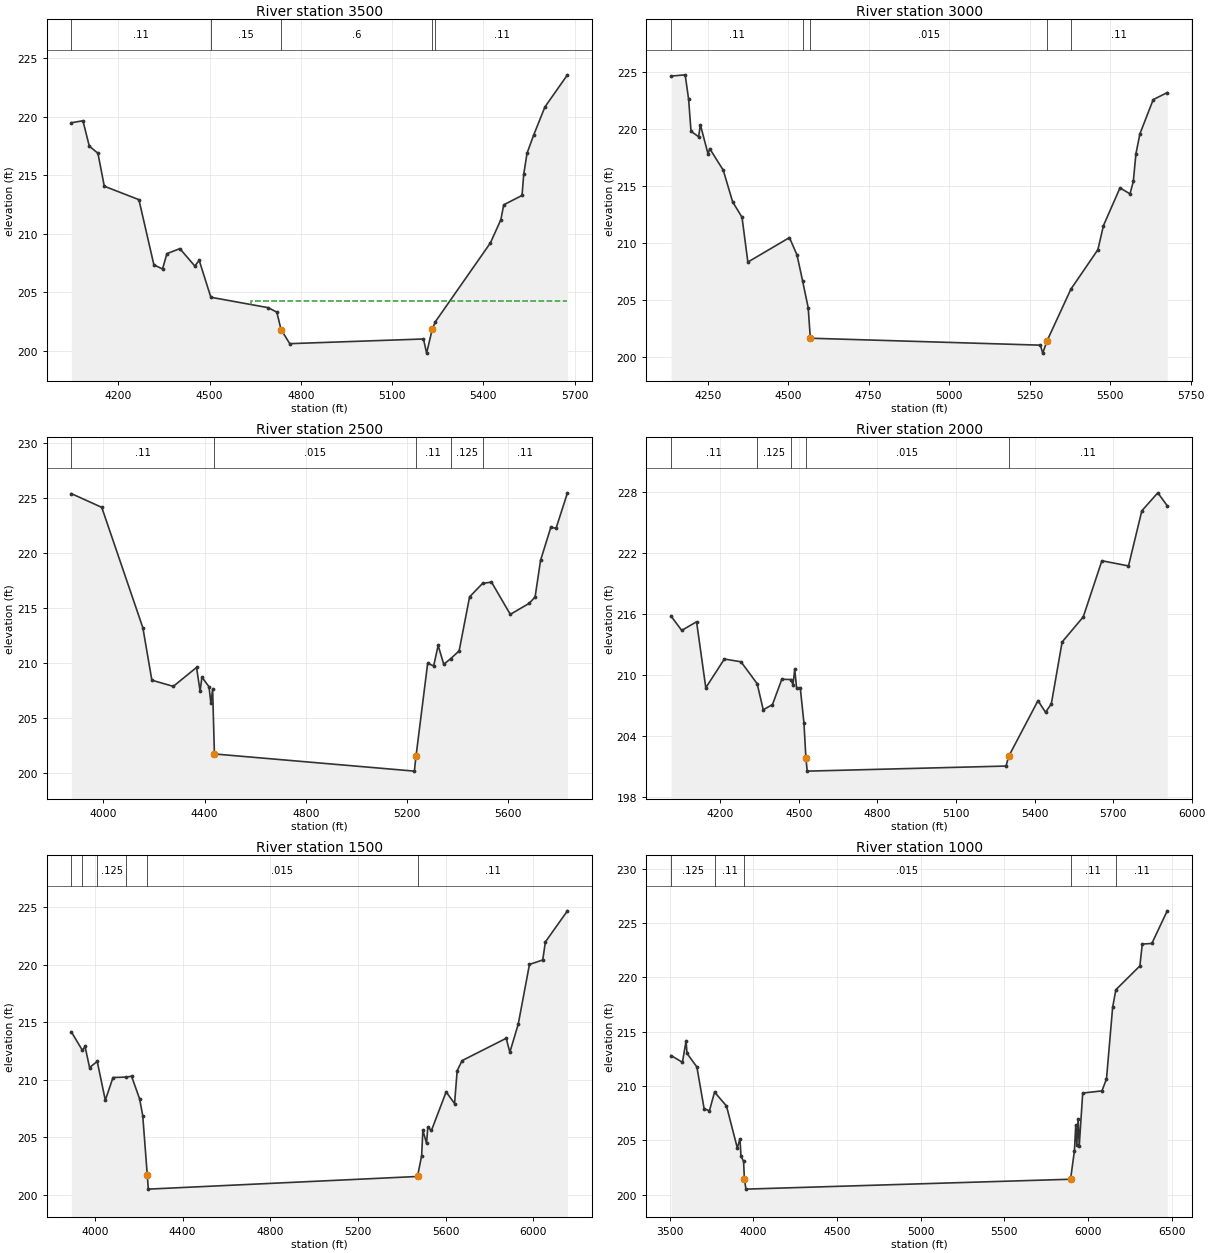
Type RM Length L Ch R = 1 ,3500    ,500,500,500
BEGIN DESCRIPTION:
LITTLE LAKE CREEK TRIB NO 6 10.5
END DESCRIPTION:
XS GIS Cut Line= 3
      3776228.06     10149404.27      3775514.28     10148770.41
      3774896.45     10148495.33
#Sta/Elev= 30
  4045.4   219.5  4083.5  219.67  4104.4   217.5  4132.8  216.89  4153.7  214.07
  4267.5  212.92  4316.8  207.34  4345.2  206.99  4359.5   208.3  4402.1  208.73
  4451.4  207.24  4465.7  207.73    4504  204.57  4692.3  203.68  4720.7   203.3
  4734.9   201.8  4763.4   200.6    5203     201  5213.3  199.79  5231.7  201.82
  5242.4  202.49    5423  209.22  5457.3   211.2  5466.8  212.48    5527  213.28
  5532.5  215.08  5543.4  216.89  5565.3  218.45  5602.2  220.85  5676.3   223.6
#Mann= 5 ,-1 , 0
  4045.4     .11       0    4504     .15       0  4734.9      .6       0
  5231.7     .11       0  5242.4     .11       0
#XS Ineff= 2 ,-1
  4692.3  4663.9  203.68  4635.4    4504  204.29
Permanent Ineff=
       F       F
Bank Sta=4734.9,5231.7
XS Rating Curve= 0 ,0
Exp/Cntr=0.3,0.1

Type RM Length L Ch R = 1 ,3000    ,500,500,500
BEGIN DESCRIPTION:
LITTLE LAKE CREEK TRIB NO 6 11.0
END DESCRIPTION:
XS GIS Cut Line= 3
      3776367.82     10148611.06      3775572.67     10148273.83
      3774915.61     10148439.01
#Sta/Elev= 30
  4136.3  224.64  4179.9  224.75  4190.6  222.62  4198.1  219.79  4221.8  219.31
  4227.2  220.36  4250.9  217.81  4256.3  218.26  4298.3  216.37  4327.4  213.59
  4356.5  212.24  4374.7   208.3  4503.9  210.45  4527.3  208.93  4544.5  206.68
  4562.1  204.29 4568.79  201.61  5283.4     201  5290.7   200.3    5304  201.37
  5378.2  205.92  5462.1  209.39  5479.3   211.5  5530.8  214.82  5561.8  214.29
  5572.1  215.38  5580.3  217.82  5592.7  219.57  5633.9  222.57  5677.5  223.19
#Mann= 5 ,-1 , 0
  4136.3     .11       0  4544.5     .15       0 4568.79    .015       0
    5304     .11       0  5378.2     .11       0
Bank Sta=4568.79,5304
XS Rating Curve= 0 ,0
Exp/Cntr=0.3,0.1

Type RM Length L Ch R = 1 ,2500    ,500,500,500
BEGIN DESCRIPTION:
LITTLE LAKE CREEK TRIB NO 6 12.0
END DESCRIPTION:
XS GIS Cut Line= 3
      3776417.83     10148561.05      3775609.78     10147775.44
      3774804.46     10147557.07
#Sta/Elev= 30
    3873  225.38  3993.2  224.13  4155.8  213.19  4191.3  208.43  4276.1  207.87
    4368  209.59  4382.1  207.42  4389.1  208.71  4417.4  207.83  4424.6  206.35
  4431.5  207.59  4438.7  201.73  5229.2  200.17 5235.57  201.51  5281.7  209.96
  5305.5  209.73  5323.2  211.59  5345.3  209.87  5372.3  210.38  5406.1  211.09
  5447.5     216  5498.7  217.22  5534.1  217.34  5608.5  214.41    5683  215.41
  5706.5  215.99    5728  219.31  5768.7  222.32  5789.4  222.23  5834.4  225.45
#Mann= 5 ,-1 , 0
    3873     .11       0  4438.7    .015       0 5235.57     .11       0
  5372.3    .125       0  5498.7     .11       0
Bank Sta=4438.7,5235.57
XS Rating Curve= 0 ,0
Exp/Cntr=0.3,0.1

Type RM Length L Ch R = 1 ,2000    ,500,500,500
BEGIN DESCRIPTION:
LITTLE LAKE CREEK TRIB NO 6 13.0
END DESCRIPTION:
XS GIS Cut Line= 3
      3776360.03     10147945.96      3775634.36     10147276.06
      3774742.41     10147438.94
#Sta/Elev= 30
  4012.4  215.76  4052.9  214.36  4109.6  215.21  4144.8  208.71  4215.7  211.54
  4279.2  211.27  4340.8  209.12  4364.2  206.54  4399.4  207.06  4435.1  209.55
  4470.5  209.52  4477.6  208.99  4484.4  210.54  4491.7  208.66  4505.4  208.73
  4519.6  205.24    4527  201.81    4532   200.5  5291.2     201  5301.4  201.96
  5413.2  207.44    5442   206.3  5464.1  207.12  5505.4  213.22    5586  215.69
  5657.2  221.22  5758.8  220.71  5809.7  226.14  5870.7  227.91  5906.7  226.64
#Mann= 5 ,-1 , 0
  4012.4     .11       0  4340.8    .125       0  4470.5     .11       0
    4527    .015       0  5301.4     .11       0
Bank Sta=4527,5301.4
XS Rating Curve= 0 ,0
Exp/Cntr=0.3,0.1

Type RM Length L Ch R = 1 ,1500    ,500,500,500
BEGIN DESCRIPTION:
LITTLE LAKE CREEK TRIB NO 6 14.0
END DESCRIPTION:
XS GIS Cut Line= 3
      3776353.08     10147633.46      3775651.24     10146776.35
      3774616.99     10147293.18
#Sta/Elev= 30
  3892.2  214.17  3942.8  212.56  3954.6   212.9  3975.4  211.07  4010.3   211.6
  4047.2  208.23  4082.3   210.2  4141.5  210.24    4167  210.31  4203.6  208.35
    4218  206.89  4238.8   201.7  4243.5   200.5 5471.95   201.6  5490.8  203.41
  5496.4  205.63  5513.2  204.47  5518.8  205.88  5535.5   205.6  5602.6  208.95
    5641  207.94  5652.9  210.79  5675.3  211.67  5876.6  213.61  5893.4   212.4
  5931.7  214.85  5982.8  220.03  6043.4  220.42  6055.5  221.99  6156.2  224.69
#Mann= 6 ,-1 , 0
  3892.2    .125       0  3942.8     .11       0  4010.3    .125       0
  4141.5     .11       0  4238.8    .015       0 5471.95     .11       0
Bank Sta=4238.8,5471.95
XS Rating Curve= 0 ,0
Exp/Cntr=0.3,0.1

Type RM Length L Ch R = 1 ,1000    ,506,506,506
BEGIN DESCRIPTION:
LITTLE LAKE CREEK TRIB NO 6 15.0
END DESCRIPTION:
XS GIS Cut Line= 3
      3776408.65     10147570.97      3775668.12     10146276.63
      3774526.67     10147209.88
#Sta/Elev= 30
  3508.8  212.79  3576.5  212.17  3598.1  214.14  3603.8  212.99  3662.8  211.74
    3706  207.91  3737.7  207.71  3768.5  209.43  3839.8  208.15  3904.6  204.28
  3920.4  205.14  3926.2  203.56    3942  203.05  3946.8   201.4  3956.1   200.5
 5896.55  201.41  5919.7  204.04  5927.6  206.39    5934  204.58  5941.9  206.98
  5948.4  204.48  5969.2  209.34  6084.1  209.54  6111.3  210.64    6148  217.22
  6167.4  218.85  6310.9  221.04  6325.3  223.05  6382.5  223.11  6474.4  226.11
#Mann= 5 ,-1 , 0
  3508.8    .125       0  3768.5     .11       0  3946.8    .015       0
 5896.55     .11       0  6167.4     .11       0
Bank Sta=3946.8,5896.55
XS Rating Curve= 0 ,0
Exp/Cntr=0.3,0.1

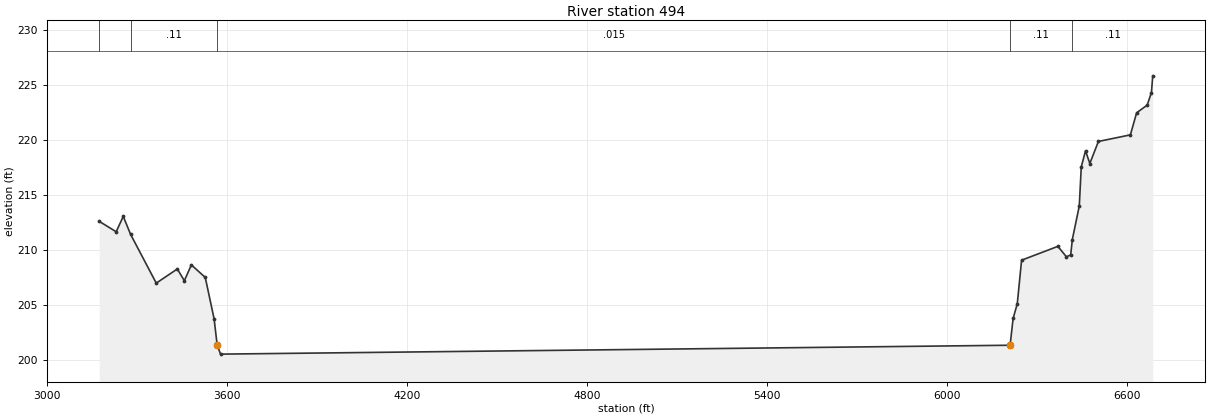
Type RM Length L Ch R = 1 ,494     ,0,0,0
BEGIN DESCRIPTION:
LITTLE LAKE CREEK TRIB NO 6 17.0
END DESCRIPTION:
XS GIS Cut Line= 3
      3776416.81     10147445.01      3775686.26     10145770.86
       3774597.4     10147056.13
#Sta/Elev= 30
  3173.4   212.6    3230  211.65  3253.5  213.05    3278  211.41  3363.5  206.97
  3433.7  208.26  3457.1  207.19  3480.5  208.63  3526.8  207.49  3556.2  203.73
 3566.48  201.34  3577.7   200.5 6209.14  201.31  6219.2  203.75  6233.1   205.1
  6247.4  209.06  6368.3  210.32  6396.8  209.37  6411.1  209.54  6416.5  210.94
  6439.7     214  6446.3  217.56  6460.5  219.03  6474.8  217.87  6503.4  219.88
    6610  220.48  6630.8  222.49    6666  223.19  6680.2  224.34  6684.5  225.86
#Mann= 5 ,-1 , 0
  3173.4    .125       0    3278     .11       0 3566.48    .015       0
 6209.14     .11       0  6416.5     .11       0
Bank Sta=3566.48,6209.14
XS Rating Curve= 0 ,0
Exp/Cntr=0.3,0.1

Chan Stop Cuts=-1
Use User Specified Reach Order=0
Composite Channel Slope=5