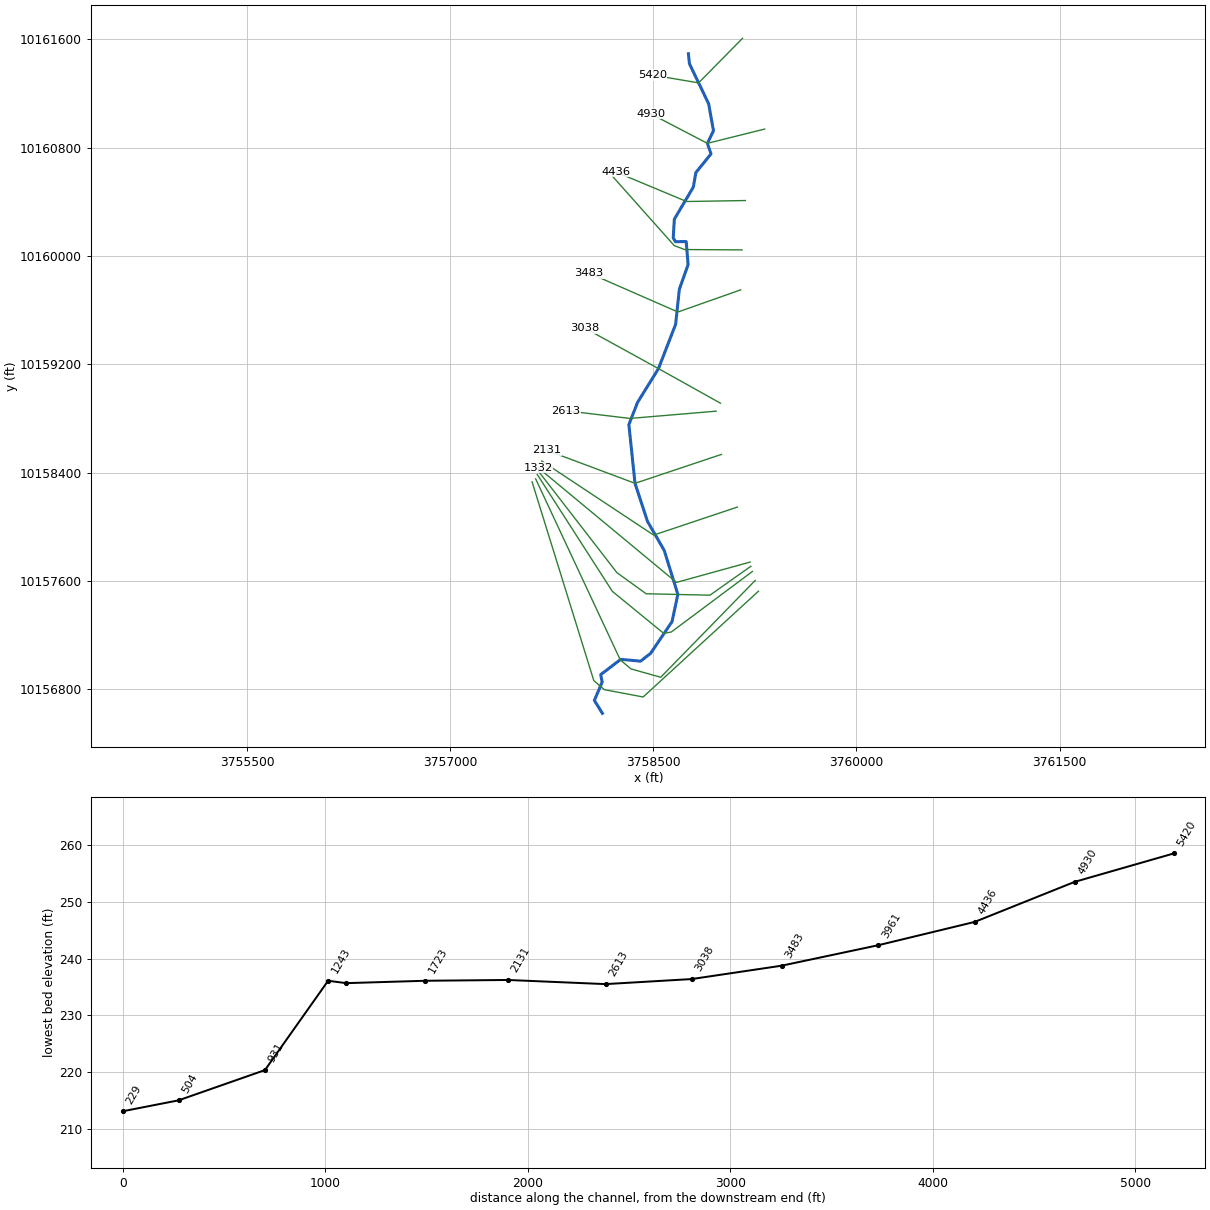
--- LITTLE LAKE CREEK TRIB NO 7.prj (project) ---

Proj Title=LITTLE LAKE CREEK TRIB NO 7 Base Level Engineering
Current Plan=p01
Default Exp/Contr=0.3,0.1
English Units
Geom File=g01
Flow File=f01
Plan File=p01
Y Axis Title=Elevation
X Axis Title(PF)=Main Channel Distance
X Axis Title(XS)=Station
BEGIN DESCRIPTION:
LITTLE LAKE CREEK TRIB NO 7
END DESCRIPTION:
DSS File=dss
DSS Export Rating Curves= 0
DSS Export Rating Curve Sorted= 0
DSS Export Volume Flow Curves= 0
DXF OffsetX= 0
DXF OffsetY= 0
DXF ScaleX= 1
DXF ScaleY= 10

--- LITTLE LAKE CREEK TRIB NO 7.p01 (plan) ---

Plan Title=Multiple Run
Program Version=4.10
Short Identifier=Multiple Run
Geom File=g01
Flow File=f01
Subcritical Flow
K Sum by GR= 0
Std Step Tol= 0.01
Critical Tol= 0.01
Num of Std Step Trials= 20
Max Error Tol= 0.3
Flow Tol Ratio= 0.001
Split Flow NTrial= 30
Split Flow Tol= 0.02
Split Flow Ratio= 0.02
Log Output Level= 0
Friction Slope Method= 1
Unsteady Friction Slope Method= 2
Unsteady Bridges Friction Slope Method= 1
Parabolic Critical Depth
Global Vel Dist= 1 , 1 , 1
Global Log Level= 0
CheckData=True
Encroach Param=-1 ,0,0, 0
BEGIN DESCRIPTION:
Multiple Run
END DESCRIPTION:
Computation Interval=1HOUR
Output Interval=1HOUR
Run HTab= 0
Run UNet= 0
Run PostProcess= 0
Run WQNet= 0
UNET Theta= 1
UNET Theta Warmup= 1
UNET ZTol= 0.02
UNET ZSATol= 0.05
UNET MxIter= 20
UNET MaxInSteps= 0
UNET DtIC= 0
UNET DtMin= 0
UNET MaxCRTS= 20
UNET WFStab= 2
UNET SFStab= 1
UNET WFX= 1
UNET SFX= 1
UNET DSS MLevel= 4
UNET DZMax Abort= 100
UNET Convert EG Bridges= 0
UNET Use Existing IB Tables=-1
UNET Froude Reduction=False
UNET Froude Limit= 1
UNET Froude Power= 10
UNET Time Slicing=0,0, 5
UNET Junction Losses=0
Instantaneous Interval=1HOUR
DSS File=dss
Write IC File= 0
Write IC File at Sim End=0
Echo Input=False
Echo Parameters=False
Echo Output=False
Write Detailed= 0
WQ AD Non Conservative
WQ ULTIMATE=-1
WQ Max Comp Step=1HOUR
WQ Output Interval=15MIN
WQ Output Selected Increments= 0
WQ Output face flow=0
WQ Output face velocity=0
WQ Output face area=0
WQ Output face dispersion=0
WQ Output cell volume=0
WQ Output cell surface area=0
WQ Output cell continuity=0
WQ Output cumulative cell continuity=0
WQ Output face conc=0
WQ Output face dconc_dx=0
WQ Output face courant=0
WQ Output face peclet=0
WQ Output face adv mass=0
WQ Output face disp mass=0
WQ Output cell mass=0
WQ Output cell source sink temp=0
WQ Output cell source sink nsm=0
WQ Output MaxMinRange=-1
WQ Daily Max Min Mean=-1
WQ Daily Range=0
WQ Daily Time=0
WQ Create Restart=0
WQ Fixed Restart=0
WQ System Summary=0
WQ Use Fixed Temperature=0
Sorting and Armoring Iterations= 10
XS Update Threshold= 0.02
Hydraulics Update Threshold= 0.02
Energy Slope Method= 1
Volume Change Method= 0
XS Weighting Method= 0
Number of US Weighted Cross Sections= 1
Number of DS Weighted Cross Sections= 1
Upstream XS Weight=0.25
Main XS Weight=0.5
Downstream XS Weight=0.25
Number of DS XS's Weighted with US Boundary= 1
Upstream Boundary Weight= 1
Weight of XSs Associated with US Boundary= 0
Number of US XS's Weighted with DS Boundary= 1
Downstream Boundary Weight= 0.5
Weight of XSs Associated with DS Boundary= 0.5
Sediment Output Level= 4
Mass or Volume Output= 0
Output Increment Type= 1
Profile and TS Output Increment= 10
XS Output Flag= 0
XS Output Increment= 10
Disregard all LS=0
Disregard all Conn=0
Disregard all Breaches=0
Disregard all Pumps=0

--- LITTLE LAKE CREEK TRIB NO 7.f01 (steady flow) ---

Flow Title=Multiple
Program Version=4.10
Number of Profiles= 7
Profile Names=10-year,25-year,50-year,1pct_min,100-year,1pct_plu,500-year
River Rch & RM=LITTLE LAKE CREE,Reach-1         ,5420
     216     275     359     155     467    1410     814
River Rch & RM=LITTLE LAKE CREE,Reach-1         ,3483
     359     472     627     274     828    2501    1495
Boundary for River Rch & Prof#=LITTLE LAKE CREE,Reach-1         , 1
Up Type= 0
Dn Type= 3
Dn Slope=0.02
Boundary for River Rch & Prof#=LITTLE LAKE CREE,Reach-1         , 2
Up Type= 0
Dn Type= 3
Dn Slope=0.02
Boundary for River Rch & Prof#=LITTLE LAKE CREE,Reach-1         , 3
Up Type= 0
Dn Type= 3
Dn Slope=0.02
Boundary for River Rch & Prof#=LITTLE LAKE CREE,Reach-1         , 4
Up Type= 0
Dn Type= 3
Dn Slope=0.02
Boundary for River Rch & Prof#=LITTLE LAKE CREE,Reach-1         , 5
Up Type= 0
Dn Type= 3
Dn Slope=0.02
Boundary for River Rch & Prof#=LITTLE LAKE CREE,Reach-1         , 6
Up Type= 0
Dn Type= 3
Dn Slope=0.02
Boundary for River Rch & Prof#=LITTLE LAKE CREE,Reach-1         , 7
Up Type= 0
Dn Type= 3
Dn Slope=0.02
DSS Import GetInterval= 0
DSS Import GetPeak= 0
DSS Import FillOption= 0

--- LITTLE LAKE CREEK TRIB NO 7.g01 (geometry) ---

Geom Title=Existing Conditions
Program Version=4.10

River Reach=LITTLE LAKE CREE,Reach-1
Reach XY= 30
      3758758.72       10161493.      3758766.69     10161418.91
       3758908.4     10161123.45      3758943.99     10160923.79
      3758898.85     10160831.35      3758925.76     10160753.66
      3758813.78      10160615.2      3758795.11       10160508.
      3758654.92     10160271.45      3758646.68     10160132.13
      3758664.04     10160105.22       3758742.6     10160105.65
      3758756.49     10159935.51      3758691.82     10159753.22
      3758664.47     10159494.97      3758537.74     10159167.72
      3758383.22     10158918.15       3758319.2     10158754.06
      3758364.42      10158320.5      3758456.91     10158038.91
      3758580.24     10157825.14      3758680.95     10157500.39
      3758637.79     10157298.95      3758479.52     10157064.64
      3758405.53     10157007.09      3758259.29      10157020.6
      3758111.17     10156907.86      3758121.94     10156852.31
       3758064.3     10156717.24      3758123.71     10156621.53

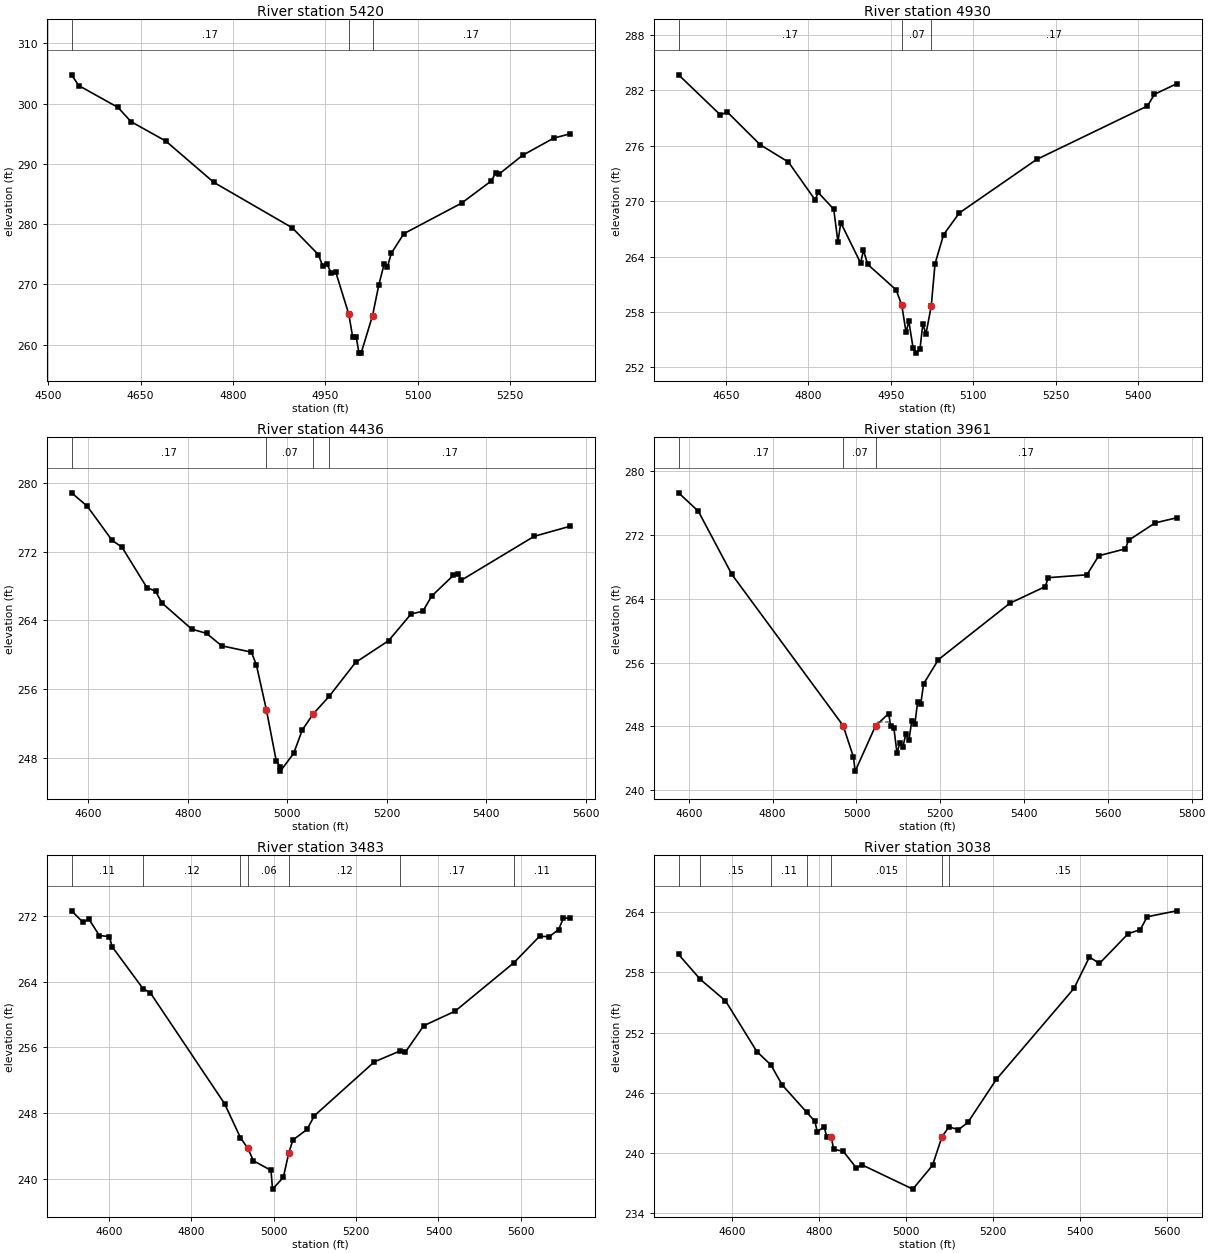
Type RM Length L Ch R = 1 ,5420    ,490,490,490
BEGIN DESCRIPTION:
LITTLE LAKE CREEK TRIB NO 7 12.0
END DESCRIPTION:
XS GIS Cut Line= 3
      3759158.46     10161606.85      3758833.96     10161277.85
      3758492.37     10161335.95
#Sta/Elev= 30
  4537.9  304.78  4549.5     303  4613.2  299.37  4634.3  297.01  4690.9  293.78
  4768.7  286.93    4896  279.39  4938.4  274.94  4945.5  273.06  4952.6  273.33
  4959.6  271.82  4966.7  272.03  4987.9  265.04  4994.2  261.24    5000  261.24
  5004.4  258.57  5007.9  258.57  5026.5  264.81  5036.6  269.89  5045.4  273.41
  5050.4  272.81  5056.9  275.14  5077.2   278.4  5170.9  283.47  5219.2  287.16
  5226.1  288.44  5231.2  288.25  5269.9  291.41  5320.6  294.27  5346.5  294.97
#Mann= 3 , 0 , 0
  4537.9     .17       0  4987.9     .07       0  5026.5     .17       0
Bank Sta=4987.9,5026.5
XS Rating Curve= 0 ,0
Exp/Cntr=0.3,0.1

Type RM Length L Ch R = 1 ,4930    ,494,494,494
BEGIN DESCRIPTION:
LITTLE LAKE CREEK TRIB NO 7 11.0
END DESCRIPTION:
XS GIS Cut Line= 3
      3759321.71     10160936.74      3758898.85     10160831.35
      3758481.91     10161048.72
#Sta/Elev= 30
  4564.2  283.67  4640.3  279.33  4652.7  279.65  4712.5  276.11    4764  274.23
  4812.7  270.12  4817.9  270.95  4846.4  269.13    4854  265.59  4859.2  267.67
  4895.3   263.3  4900.4  264.69  4908.3  263.15  4959.8   260.4  4970.1  258.76
  4977.9  255.81    4983     257  4990.7  254.11  4996.2  253.55  5003.4  254.05
  5008.5  256.73  5014.1  255.62  5023.7  258.61  5030.6  263.21  5046.2  266.37
  5074.8  268.72  5215.4  274.51    5417   280.3  5429.7  281.56  5470.2  282.71
#Mann= 3 , 0 , 0
  4564.2     .17       0  4970.1     .07       0  5023.7     .17       0
Bank Sta=4970.1,5023.7
XS Rating Curve= 0 ,0
Exp/Cntr=0.3,0.1

Type RM Length L Ch R = 1 ,4436    ,475,475,475
BEGIN DESCRIPTION:
LITTLE LAKE CREEK TRIB NO 7 10.0
END DESCRIPTION:
XS GIS Cut Line= 3
      3759179.27     10160408.96      3758745.64     10160401.66
      3758221.87     10160620.39
#Sta/Elev= 30
  4566.3  278.85  4597.7   277.3  4647.7  273.33  4667.7  272.52  4717.7  267.83
  4735.2  267.41  4747.7  266.05  4807.8     263  4837.8   262.5  4867.8  261.06
  4927.8  260.32  4937.8  258.83  4957.8  253.64  4977.8  247.65  4985.8  246.98
    4986  246.48  5012.7  248.54  5030.1  251.27  5051.8  253.12  5084.1  255.18
  5137.1  259.12  5203.5  261.65  5248.6  264.75  5272.4  265.08  5290.2  266.84
  5333.5  269.24  5343.9  269.36  5349.3  268.67  5496.1  273.79  5567.6  274.95
#Mann= 4 ,-1 , 0
  4566.3     .17       0  4957.8     .07       0  5051.8     .17       0
  5084.1     .17       0
Bank Sta=4957.8,5051.8
XS Rating Curve= 0 ,0
Exp/Cntr=0.3,0.1

Type RM Length L Ch R = 1 ,3961    ,478,478,478
BEGIN DESCRIPTION:
LITTLE LAKE CREEK TRIB NO 7 9.0
END DESCRIPTION:
XS GIS Cut Line= 4
      3759155.04     10160044.37      3758730.44     10160047.06
      3758654.33     10160076.07      3758200.12     10160586.08
#Sta/Elev= 30
  4575.4  277.28  4622.6  274.97  4702.6  267.05 4968.14  248.09  4992.6  244.18
    4997  242.38  5045.6  248.06  5076.9   249.6  5081.5  248.08  5089.3  247.78
  5096.8  244.64  5103.5  245.94    5111   245.4  5117.7  247.05  5125.2  246.26
  5131.9  248.63  5139.4  248.27  5146.1  251.11  5153.6  250.85  5160.3  253.33
  5195.5  256.36    5366  263.43  5450.5  265.52    5458  266.64    5550     267
  5578.4  269.39  5641.9  270.26  5649.5  271.33    5713  273.51  5764.4  274.15
#Mann= 3 , 0 , 0
  4575.4     .17       0 4968.14     .07       0  5045.6     .17       0
#XS Ineff= 2 ,-1
  5052.2  5076.9   248.5  5076.9  5146.1   249.6
Permanent Ineff=
       T       T
Bank Sta=4968.14,5045.6
XS Rating Curve= 0 ,0
Exp/Cntr=0.3,0.1

Type RM Length L Ch R = 1 ,3483    ,445,445,445
BEGIN DESCRIPTION:
LITTLE LAKE CREEK TRIB NO 7 8.0
END DESCRIPTION:
XS GIS Cut Line= 3
      3759144.58     10159749.23       3758681.4     10159585.69
      3758023.06     10159874.24
#Sta/Elev= 30
  4508.8  272.62  4537.1   271.2  4550.7  271.63  4576.3  269.61  4600.8  269.49
  4607.2  268.26  4682.4  263.15    4700  262.65  4880.3  249.17  4918.9  245.03
  4936.8  243.73  4950.7   242.2  4993.2  241.05  4996.9  238.76  5023.1  240.18
  5036.6   243.2  5046.4  244.74  5080.7  246.02  5098.6  247.69  5244.1  254.24
  5307.6  255.59  5319.9  255.45  5364.2  258.64  5440.6  260.42  5583.1   266.3
  5645.6  269.52    5669  269.48  5691.7  270.33  5703.3  271.71  5718.8  271.75
#Mann= 7 ,-1 , 0
  4508.8     .11       0  4682.4     .12       0  4918.9     .12       0
  4936.8     .06       0  5036.6     .12       0  5307.6     .17       0
  5583.1     .11       0
Bank Sta=4936.8,5036.6
XS Rating Curve= 0 ,0
Exp/Cntr=0.3,0.1

Type RM Length L Ch R = 1 ,3038    ,425,425,425
BEGIN DESCRIPTION:
LITTLE LAKE CREEK TRIB NO 7 7.0
END DESCRIPTION:
XS GIS Cut Line= 3
      3758995.33     10158912.41      3758537.74     10159167.72
      3757991.86     10159467.96
#Sta/Elev= 30
    4476  259.79    4526  257.31    4584  255.17  4656.3  250.11  4688.8  248.77
  4714.3   246.8    4771  244.06  4789.7  243.17  4795.4  242.13  4811.4  242.61
  4817.1  241.61  4827.4  241.64  4833.1  240.35  4854.8  240.19  4885.4  238.51
  4898.3  238.82  5015.4   236.4  5060.7  238.77  5082.5  241.62  5098.6  242.61
  5120.4  242.32  5142.2  243.05  5207.5  247.33  5386.5  256.41  5422.1  259.54
    5445  258.89  5511.5  261.87    5539  262.26  5555.1  263.55    5623  264.14
#Mann= 7 ,-1 , 0
    4476     .11       0    4526     .15       0  4688.8     .11       0
    4771     .15       0  4827.4    .015       0  5082.5     .15       0
  5098.6     .15       0
Bank Sta=4827.4,5082.5
XS Rating Curve= 0 ,0
Exp/Cntr=0.3,0.1

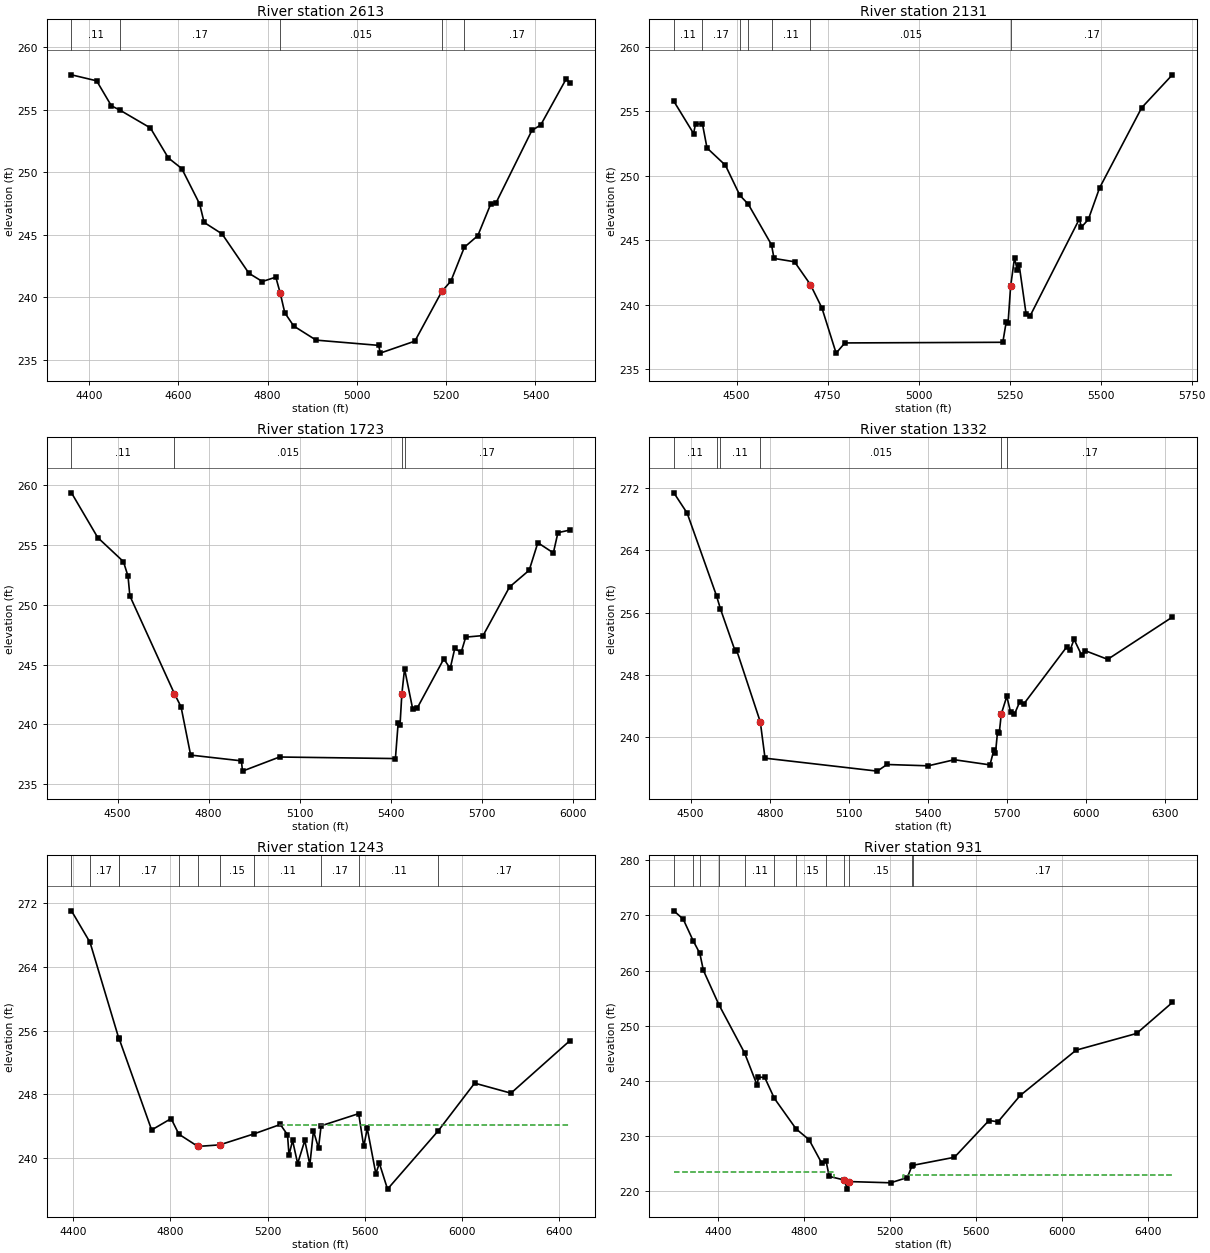
Type RM Length L Ch R = 1 ,2613    ,482,482,482
BEGIN DESCRIPTION:
LITTLE LAKE CREEK TRIB NO 7 6.0
END DESCRIPTION:
XS GIS Cut Line= 3
      3758964.04      10158853.4       3758326.8     10158799.66
      3757852.94     10158856.87
#Sta/Elev= 30
  4360.5  257.78  4416.9   257.3  4449.9   255.3  4468.9  254.96  4537.3  253.53
  4577.5  251.13  4607.6  250.28  4647.7  247.44  4657.7  245.97  4697.9  245.05
  4758.1   241.9  4788.2  241.24  4818.3  241.59  4828.3   240.3  4838.4  238.74
  4858.4  237.68  4908.6  236.55  5048.9  236.13  5052.2  235.51  5129.9  236.47
  5190.3  240.45  5210.5  241.27  5240.7  243.98  5270.9  244.91  5299.9  247.45
  5311.2   247.5    5392  253.33  5411.9  253.77    5469  257.46  5477.3  257.09
#Mann= 5 ,-1 , 0
  4360.5     .11       0  4468.9     .17       0  4828.3    .015       0
  5190.3     .17       0  5240.7     .17       0
Bank Sta=4828.3,5190.3
XS Rating Curve= 0 ,0
Exp/Cntr=0.3,0.1

Type RM Length L Ch R = 1 ,2131    ,408,408,408
BEGIN DESCRIPTION:
LITTLE LAKE CREEK TRIB NO 7 5.0
END DESCRIPTION:
XS GIS Cut Line= 3
      3759002.25     10158533.96      3758364.42      10158320.5
      3757711.73     10158564.77
#Sta/Elev= 30
  4327.4  255.76  4381.6  253.26  4386.9     254    4406     254  4418.5  252.14
  4469.1   250.8  4508.7  248.47  4531.7  247.79  4595.7  244.64  4602.6  243.58
  4658.9  243.32  4702.6  241.55  4734.2  239.74  4773.2  236.24  4797.3  237.03
  5231.2  237.08  5240.4  238.64  5245.7   238.6  5252.6  241.41  5263.3  243.61
  5270.6  242.72    5276  243.09  5295.3  239.24  5306.3  239.13  5441.6  246.64
    5447     246  5466.1   246.6  5496.9  249.04  5612.7  255.26  5696.9  257.81
#Mann= 7 ,-1 , 0
  4327.4     .11       0    4406     .17       0  4508.7     .11       0
  4531.7     .17       0  4595.7     .11       0  4702.6    .015       0
  5252.6     .17       0
#XS Ineff= 2 , 0
       0                  5263.3       0  243.61
Permanent Ineff=
       F       T
Bank Sta=4702.6,5252.6
XS Rating Curve= 0 ,0
Exp/Cntr=0.3,0.1

Type RM Length L Ch R = 1 ,1723    ,391,391,391
BEGIN DESCRIPTION:
LITTLE LAKE CREEK TRIB NO 7 4.0
END DESCRIPTION:
XS GIS Cut Line= 3
      3759120.33     10158145.08      3758502.13     10157938.19
      3757675.86     10158485.33
#Sta/Elev= 30
  4348.1  259.36  4434.7  255.62  4519.4  253.61  4534.6  252.38  4540.5  250.75
  4687.2  242.58  4709.2  241.48  4740.9  237.44  4908.2  236.96  4911.8   236.1
  5033.8  237.28  5415.8  237.15  5424.9  240.15  5430.9  239.93  5436.9  242.52
  5445.9  244.65    5473  241.26    5488  241.39  5575.3  245.48  5596.3  244.68
  5611.4  246.35  5632.4  246.02  5647.5   247.3  5704.7  247.43  5791.9  251.49
  5856.7  252.89  5885.2  255.19  5936.3  254.34  5951.4  256.03    5991  256.25
#Mann= 4 ,-1 , 0
  4348.1     .11       0  4687.2    .015       0  5436.9     .15       0
  5445.9     .17       0
#XS Ineff= 2 , 0
       0                  5445.9       0  244.65
Permanent Ineff=
       F       T
Bank Sta=4687.2,5436.9
XS Rating Curve= 0 ,0
Exp/Cntr=0.3,0.1

Type RM Length L Ch R = 1 ,1332    ,89,89,89
BEGIN DESCRIPTION:
LITTLE LAKE CREEK TRIB NO 7 3.0
END DESCRIPTION:
XS GIS Cut Line= 3
      3759214.04     10157738.82      3758670.67     10157588.77
      3757648.49     10158436.39
#Sta/Elev= 30
  4436.3  271.33  4486.8  268.73  4598.5  258.11  4612.8  256.49  4668.9  251.06
  4674.1  251.21  4764.3  241.99  4782.3  237.34  5208.3  235.68  5245.2  236.53
  5401.5  236.36  5500.5  237.14  5635.9  236.48  5650.2  238.33  5656.7  237.96
  5664.6  240.71  5671.1  240.56  5678.9  243.01  5699.7  245.25    5714  243.26
  5728.4  242.94  5749.2  244.59  5763.5  244.25  5926.3  251.55  5940.6  251.25
    5955  252.56  5983.6  250.54  5997.9   251.1  6082.6     250  6327.9  255.41
#Mann= 6 ,-1 , 0
  4436.3     .11       0  4598.5     .17       0  4612.8     .11       0
  4764.3    .015       0  5678.9     .17       0  5699.7     .17       0
#XS Ineff= 2 , 0
       0                  5699.7       0  245.25
Permanent Ineff=
       F       F
Bank Sta=4764.3,5678.9
XS Rating Curve= 0 ,0
Exp/Cntr=0.3,0.1

Type RM Length L Ch R = 1 ,1243    ,312,312,312
BEGIN DESCRIPTION:
Mapping XS 18c01569
END DESCRIPTION:
XS GIS Cut Line= 5
      3759220.12     10157707.96      3758918.05     10157494.43
       3758446.7     10157504.85      3758230.55      10157661.1
      3757653.58       10158407.
#Sta/Elev= 30
  4392.8  271.05  4469.3  267.08    4587  255.09    4590   254.9  4722.7  243.53
  4802.9  244.96 4834.73     243    4913  241.46    5003  241.66    5143  243.03
  5252.3  244.22  5281.7  242.92  5287.9  240.38  5302.6  242.21  5323.5  239.31
  5352.9  242.21  5373.7  239.15  5388.5  243.41  5409.3  241.26    5420  244.05
  5574.6  245.58  5595.4  241.47  5609.9  243.72  5645.2  238.04  5659.7  239.35
  5693.3   236.1  5902.4  243.44  6051.8  249.41  6201.2  248.15  6443.9  254.75
#Mann= 11 ,-1 , 0
  4392.8     .11       0  4469.3     .17       0    4587     .11       0
    4590     .17       0 4834.73     .11       0    4913     .07       0
    5003     .15       0    5143     .11       0    5420     .17       0
  5574.6     .11       0  5902.4     .17       0
#XS Ineff= 2 , 0
       0                  5245.1       0  244.16
Permanent Ineff=
       F       F
Bank Sta=4913,5003
XS Rating Curve= 0 ,0
Exp/Cntr=0.3,0.1

Type RM Length L Ch R = 1 ,931     ,427,427,427
BEGIN DESCRIPTION:
LITTLE LAKE CREEK TRIB NO 7 2.0
END DESCRIPTION:
XS GIS Cut Line= 5
      3759231.43     10157669.39      3758632.95     10157222.73
      3758576.13     10157212.63       3758196.7     10157523.08
      3757642.66     10158385.73
#Sta/Elev= 30
  4195.5  270.83  4239.1  269.31  4285.3  265.41  4316.5   263.1  4332.9  260.03
    4405  253.81  4524.7  245.04  4583.1   239.2  4589.3  240.66  4618.5   240.6
  4663.1  236.82  4764.1  231.28  4824.9   229.3  4883.3  225.08  4904.1  225.39
  4918.7  222.65  4988.1     222  5003.1  220.34  5011.3  221.71  5204.4  221.49
    5282  222.44  5303.4  224.52  5309.3  224.67  5501.5  226.12  5662.1  232.79
  5704.3  232.56  5807.4  237.33  6067.6  245.55  6349.1  248.58  6515.5   254.2
#Mann= 12 ,-1 , 0
  4195.5     .11       0  4285.3     .17       0  4316.5     .11       0
    4405     .17       0  4524.7     .11       0  4663.1     .17       0
  4764.1     .15       0  4904.1     .11       0  4988.1     .07       0
  5011.3     .15       0  5303.4     .15       0  5309.3     .17       0
#XS Ineff= 2 , 0
       0  4942.3   223.4  5260.4       0   222.9
Permanent Ineff=
       F       F
Bank Sta=4988.1,5011.3
XS Rating Curve= 0 ,0
Exp/Cntr=0.3,0.1

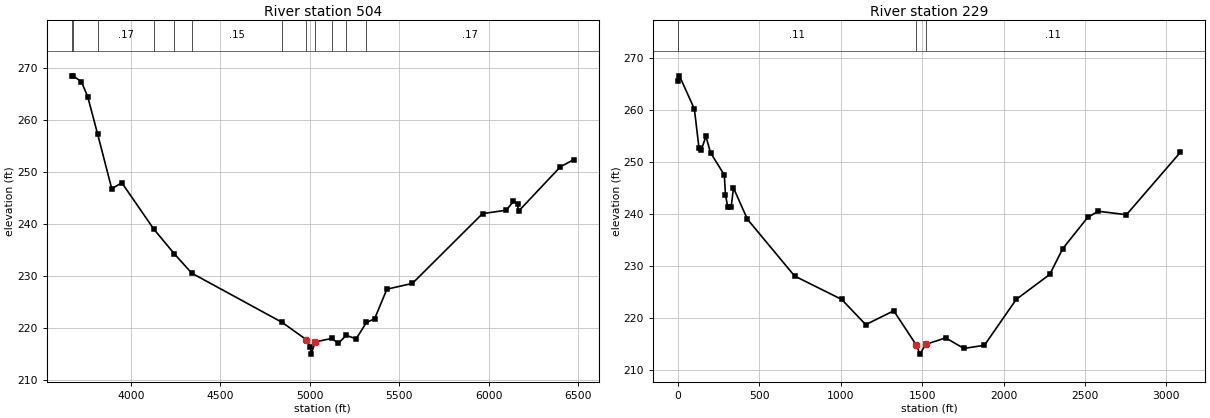
Type RM Length L Ch R = 1 ,504     ,275,275,275
BEGIN DESCRIPTION:
LITTLE LAKE CREEK TRIB NO 7 1.0
END DESCRIPTION:
XS GIS Cut Line= 5
      3759252.23      10157603.4      3758554.32     10156888.12
      3758334.02      10156950.2       3758255.5     10157016.97
      3757630.69     10158353.43
#Sta/Elev= 30
  3668.7  268.56  3676.6  268.54    3723  267.43  3758.2  264.58  3814.1  257.32
  3892.7  246.84  3949.3  247.97  4127.3  239.08  4242.2  234.32  4339.6  230.59
  4845.5   221.1  4980.2  217.78  5003.1  216.46  5006.4     215    5031  217.36
  5122.4  218.02  5159.1  217.06  5203.2  218.62  5258.4  217.94  5316.2   221.1
  5361.9  221.79  5430.4   227.5    5573  228.61  5964.9  242.04  6097.7   242.7
  6137.8  244.39  6160.7  243.92  6166.2   242.5  6400.2  251.06  6475.3  252.44
#Mann= 12 ,-1 , 0
  3668.7     .17       0  3676.6     .11       0  3814.1     .17       0
  4127.3     .15       0  4242.2     .17       0  4339.6     .15       0
  4845.5     .11       0  4980.2     .06       0    5031     .11       0
  5122.4     .11       0  5203.2     .11       0  5316.2     .17       0
Bank Sta=4980.2,5031
XS Rating Curve= 0 ,0
Exp/Cntr=0.3,0.1

Type RM Length L Ch R = 1 ,229     ,0,0,0
XS GIS Cut Line= 5
      3759276.24     10157523.88      3758424.68     10156742.63
      3758138.71     10156796.56      3758060.19     10156863.32
      3757604.36     10158331.17
#Sta/Elev= 30
       0  265.62     8.1  266.52    99.9  260.15   128.3  252.67   142.5  252.31
   170.9  254.89   199.2  251.76   283.7   247.5   291.1  243.68   305.3  241.26
   326.2  241.39   340.4     245   425.5     239   715.9  228.08  1005.7  223.58
  1153.1  218.74  1325.4   221.4  1464.4   214.8  1486.4  213.08  1521.5  214.95
  1644.4   216.2  1756.8  214.17  1882.8  214.78  2078.2  223.59  2284.1  228.38
  2364.1  233.33  2517.3  239.33  2582.4  240.52  2755.7  239.85  3086.7  251.82
#Mann= 3 , 0 , 0
       0     .11       0  1464.4     .06       0  1521.5     .11       0
Bank Sta=1464.4,1521.5
XS Rating Curve= 0 ,0
Exp/Cntr=0.3,0.1

Chan Stop Cuts=-1
Use User Specified Reach Order=0
Composite Channel Slope=5