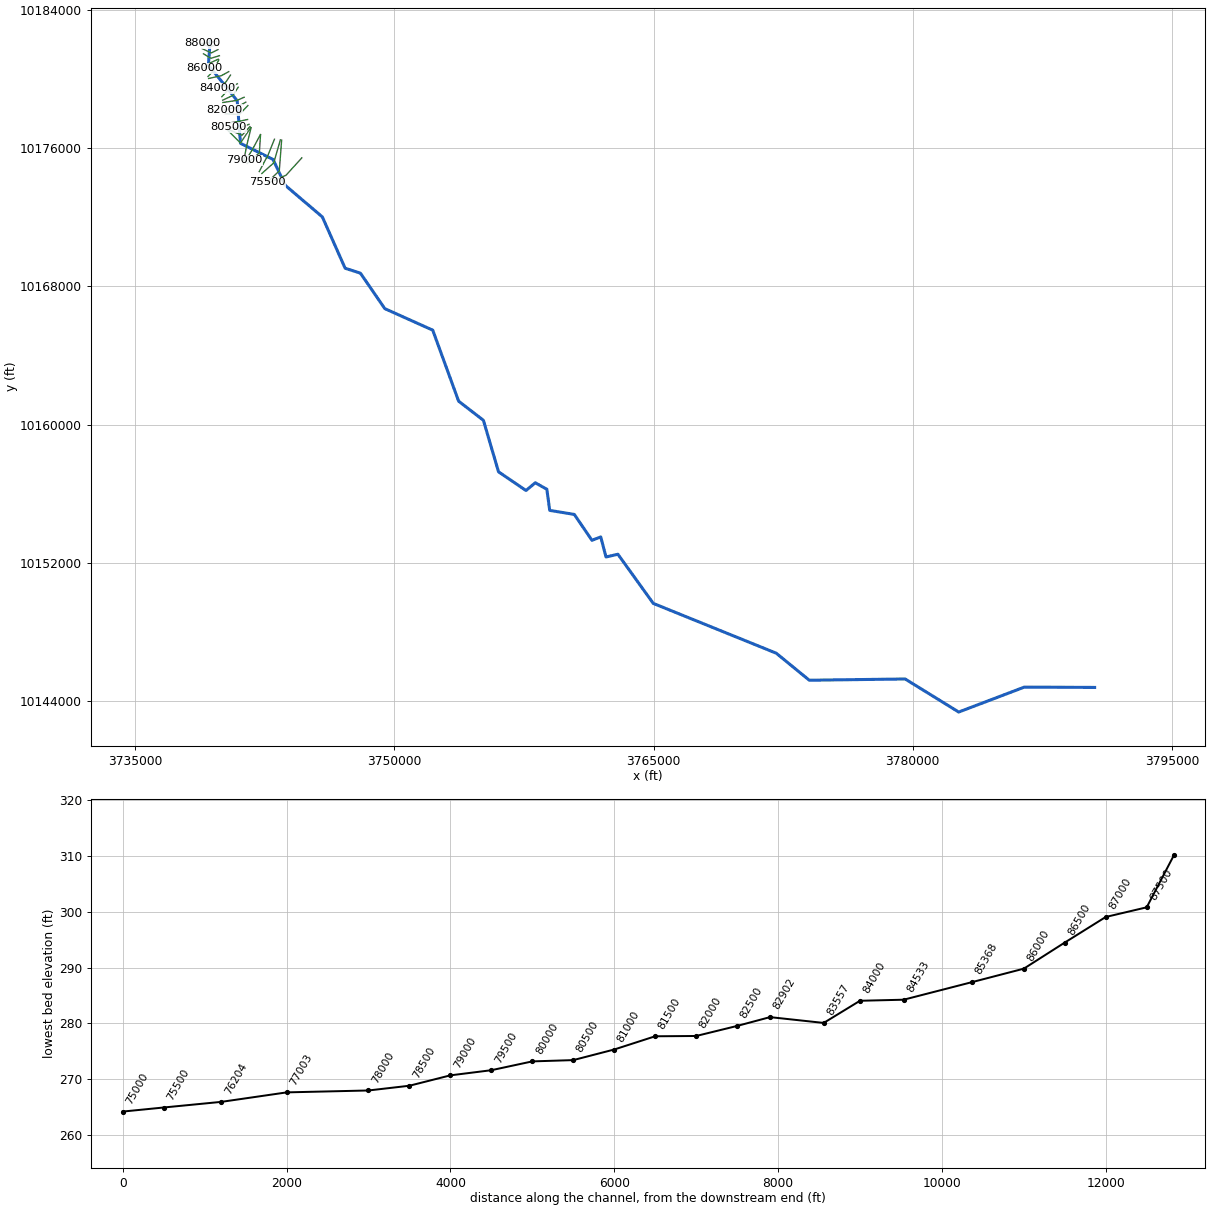
--- LITTLE LAKE CREEK.prj (project) ---

Proj Title=LITTLE LAKE CREEK Base Level Engineering
Current Plan=p01
Default Exp/Contr=0.3,0.1
English Units
Geom File=g01
Flow File=f01
Plan File=p01
Y Axis Title=Elevation
X Axis Title(PF)=Main Channel Distance
X Axis Title(XS)=Station
BEGIN DESCRIPTION:
LITTLE LAKE CREEK
END DESCRIPTION:
DSS File=dss
DSS Export Rating Curves= 0
DSS Export Rating Curve Sorted= 0
DSS Export Volume Flow Curves= 0
DXF OffsetX= 0
DXF OffsetY= 0
DXF ScaleX= 1
DXF ScaleY= 10

--- LITTLE LAKE CREEK.p01 (plan) ---

Plan Title=Multiple Run
Program Version=4.10
Geom File=g01
Flow File=f01
Subcritical Flow
K Sum by GR= 0
Std Step Tol= 0.01
Critical Tol= 0.01
Num of Std Step Trials= 20
Max Error Tol= 0.3
Flow Tol Ratio= 0.001
Split Flow NTrial= 30
Split Flow Tol= 0.02
Split Flow Ratio= 0.02
Log Output Level= 0
Friction Slope Method= 1
Unsteady Friction Slope Method= 2
Unsteady Bridges Friction Slope Method= 1
Parabolic Critical Depth
Global Vel Dist= 1 , 1 , 1
Global Log Level= 0
CheckData=True
Encroach Param=-1 ,0,0, 0
BEGIN DESCRIPTION:
Multiple Run
END DESCRIPTION:
Computation Interval=1HOUR
Output Interval=1HOUR
Run HTab= 0
Run UNet= 0
Run PostProcess= 0
Run WQNet= 0
UNET Theta= 1
UNET Theta Warmup= 1
UNET ZTol= 0.02
UNET ZSATol= 0.05
UNET MxIter= 20
UNET MaxInSteps= 0
UNET DtIC= 0
UNET DtMin= 0
UNET MaxCRTS= 20
UNET WFStab= 2
UNET SFStab= 1
UNET WFX= 1
UNET SFX= 1
UNET DSS MLevel= 4
UNET DZMax Abort= 100
UNET Convert EG Bridges= 0
UNET Use Existing IB Tables=-1
UNET Froude Reduction=False
UNET Froude Limit= 1
UNET Froude Power= 10
UNET Time Slicing=0,0, 5
UNET Junction Losses=0
Instantaneous Interval=1HOUR
DSS File=dss
Write IC File= 0
Write IC File at Sim End=0
Echo Input=False
Echo Parameters=False
Echo Output=False
Write Detailed= 0
WQ AD Non Conservative
WQ ULTIMATE=-1
WQ Max Comp Step=1HOUR
WQ Output Interval=15MIN
WQ Output Selected Increments= 0
WQ Output face flow=0
WQ Output face velocity=0
WQ Output face area=0
WQ Output face dispersion=0
WQ Output cell volume=0
WQ Output cell surface area=0
WQ Output cell continuity=0
WQ Output cumulative cell continuity=0
WQ Output face conc=0
WQ Output face dconc_dx=0
WQ Output face courant=0
WQ Output face peclet=0
WQ Output face adv mass=0
WQ Output face disp mass=0
WQ Output cell mass=0
WQ Output cell source sink temp=0
WQ Output cell source sink nsm=0
WQ Output MaxMinRange=-1
WQ Daily Max Min Mean=-1
WQ Daily Range=0
WQ Daily Time=0
WQ Create Restart=0
WQ Fixed Restart=0
WQ System Summary=0
WQ Use Fixed Temperature=0
Sorting and Armoring Iterations= 10
XS Update Threshold= 0.02
Hydraulics Update Threshold= 0.02
Energy Slope Method= 1
Volume Change Method= 0
XS Weighting Method= 0
Number of US Weighted Cross Sections= 1
Number of DS Weighted Cross Sections= 1
Upstream XS Weight=0.25
Main XS Weight=0.5
Downstream XS Weight=0.25
Number of DS XS's Weighted with US Boundary= 1
Upstream Boundary Weight= 1
Weight of XSs Associated with US Boundary= 0
Number of US XS's Weighted with DS Boundary= 1
Downstream Boundary Weight= 0.5
Weight of XSs Associated with DS Boundary= 0.5
Sediment Output Level= 4
Mass or Volume Output= 0
Output Increment Type= 1
Profile and TS Output Increment= 10
XS Output Flag= 0
XS Output Increment= 10
Disregard all LS=0
Disregard all Conn=0
Disregard all Breaches=0
Disregard all Pumps=0

--- LITTLE LAKE CREEK.f01 (steady flow) ---

Flow Title=Multiple
Program Version=4.10
Number of Profiles= 7
Profile Names=10-year,25-year,50-year,1pct_min,100-year,1pct_plu,500-year
River Rch & RM=LITTLE LAKE CREE,Reach-1         ,88000
     307     401     528     230     696    2102    1244
River Rch & RM=LITTLE LAKE CREE,Reach-1         ,87500
     307     401     528     230     696    2102    1244
River Rch & RM=LITTLE LAKE CREE,Reach-1         ,87000
     707     967    1316     589    1778    5369    3361
River Rch & RM=LITTLE LAKE CREE,Reach-1         ,82500
     809    1111    1515     679    2050    6191    3887
River Rch & RM=LITTLE LAKE CREE,Reach-1         ,79000
    1388    1951    2703    1227    3705   11189    7212
River Rch & RM=LITTLE LAKE CREE,Reach-1         ,73000
    1577    2211    3057    1384    4180   12623    8089
River Rch & RM=LITTLE LAKE CREE,Reach-1         ,69000
    1618    2267    3131    1416    4277   12916    8265
River Rch & RM=LITTLE LAKE CREE,Reach-1         ,66519
    1879    2658    3696    1682    5080   15341    9940
River Rch & RM=LITTLE LAKE CREE,Reach-1         ,62666
    2340    3339    4671    2138    6456   19497   12766
River Rch & RM=LITTLE LAKE CREE,Reach-1         ,61983
    2486    3539    4940    2256    6812   20572   13407
River Rch & RM=LITTLE LAKE CREE,Reach-1         ,60000
    3516    5083    7171    3306    9985   30154   20043
River Rch & RM=LITTLE LAKE CREE,Reach-1         ,56500
    3514    5063    7129    3279    9901   29901   19778
River Rch & RM=LITTLE LAKE CREE,Reach-1         ,48500
    3591    5174    7283    3349   10114   30544   20198
River Rch & RM=LITTLE LAKE CREE,Reach-1         ,46500
    4587    6675    9460    4378   13222   39930   26741
River Rch & RM=LITTLE LAKE CREE,Reach-1         ,43500
    4301    6205    8740    4019   12138   36656   24235
River Rch & RM=LITTLE LAKE CREE,Reach-1         ,38500
    4043    5791    8116    3712   11211   33857   22152
River Rch & RM=LITTLE LAKE CREE,Reach-1         ,35407
    4747    6886    9738    4495   13575   40996   27308
River Rch & RM=LITTLE LAKE CREE,Reach-1         ,31500
    4403    6322    8878    4068   12285   37100   24353
River Rch & RM=LITTLE LAKE CREE,Reach-1         ,26818
    4373    6269    8793    4025   12154   36704   24035
River Rch & RM=LITTLE LAKE CREE,Reach-1         ,25000
    4397    6301    8833    4040   12202   36849   24106
River Rch & RM=LITTLE LAKE CREE,Reach-1         ,22500
    4292    6121    8555    3900   11778   35569   23112
River Rch & RM=LITTLE LAKE CREE,Reach-1         ,20500
    4565    6544    9178    4200   12683   38302   25069
River Rch & RM=LITTLE LAKE CREE,Reach-1         ,15500
    4628    6631    9298    4253   12843   38785   25367
River Rch & RM=LITTLE LAKE CREE,Reach-1         ,12500
    4429    6286    8757    3979   12017   36291   23411
River Rch & RM=LITTLE LAKE CREE,Reach-1         ,8286
    4506    6396    8913    4050   12230   36934   23834
River Rch & RM=LITTLE LAKE CREE,Reach-1         ,5500
    4580    6494    9042    4105   12397   37438   24114
River Rch & RM=LITTLE LAKE CREE,Reach-1         ,4500
    4485    6338    8803    3986   12038   36354   23296
Boundary for River Rch & Prof#=LITTLE LAKE CREE,Reach-1         , 1
Up Type= 0
Dn Type= 3
Dn Slope=0.0001
Boundary for River Rch & Prof#=LITTLE LAKE CREE,Reach-1         , 2
Up Type= 0
Dn Type= 3
Dn Slope=0.0001
Boundary for River Rch & Prof#=LITTLE LAKE CREE,Reach-1         , 3
Up Type= 0
Dn Type= 3
Dn Slope=0.0001
Boundary for River Rch & Prof#=LITTLE LAKE CREE,Reach-1         , 4
Up Type= 0
Dn Type= 3
Dn Slope=0.0001
Boundary for River Rch & Prof#=LITTLE LAKE CREE,Reach-1         , 5
Up Type= 0
Dn Type= 3
Dn Slope=0.0001
Boundary for River Rch & Prof#=LITTLE LAKE CREE,Reach-1         , 6
Up Type= 0
Dn Type= 3
Dn Slope=0.0001
Boundary for River Rch & Prof#=LITTLE LAKE CREE,Reach-1         , 7
Up Type= 0
Dn Type= 3
Dn Slope=0.0001
DSS Import GetInterval= 0
DSS Import GetPeak= 0
DSS Import FillOption= 0

--- LITTLE LAKE CREEK.g01 (geometry) ---

Geom Title=Existing Conditions
Program Version=4.10

River Reach=LITTLE LAKE CREE,Reach-1
Reach XY= 30
      3739343.38     10182180.47      3739239.34     10180796.36
      3740908.23     10178726.84      3741098.23     10176266.84
      3742983.64     10175330.48      3743686.32     10173838.99
      3745834.11     10172010.01      3747153.43     10169042.17
      3748037.45     10168758.17      3749448.16     10166706.47
      3752222.91     10165462.25      3753721.05     10161355.11
       3755155.9     10160247.04      3756029.76     10157270.06
      3757619.84     10156188.46      3758157.69     10156636.93
      3758825.83     10156259.73      3758992.86     10155040.54
      3760415.52     10154805.27      3761435.29     10153310.37
      3761945.31      10153503.6      3762250.24     10152345.23
      3762938.17     10152503.65      3764984.61     10149660.77
      3772100.02     10146781.56      3774014.32     10145217.53
      3779560.38     10145290.51      3782659.96     10143378.44
      3786459.04     10144820.49      3790525.64     10144801.45

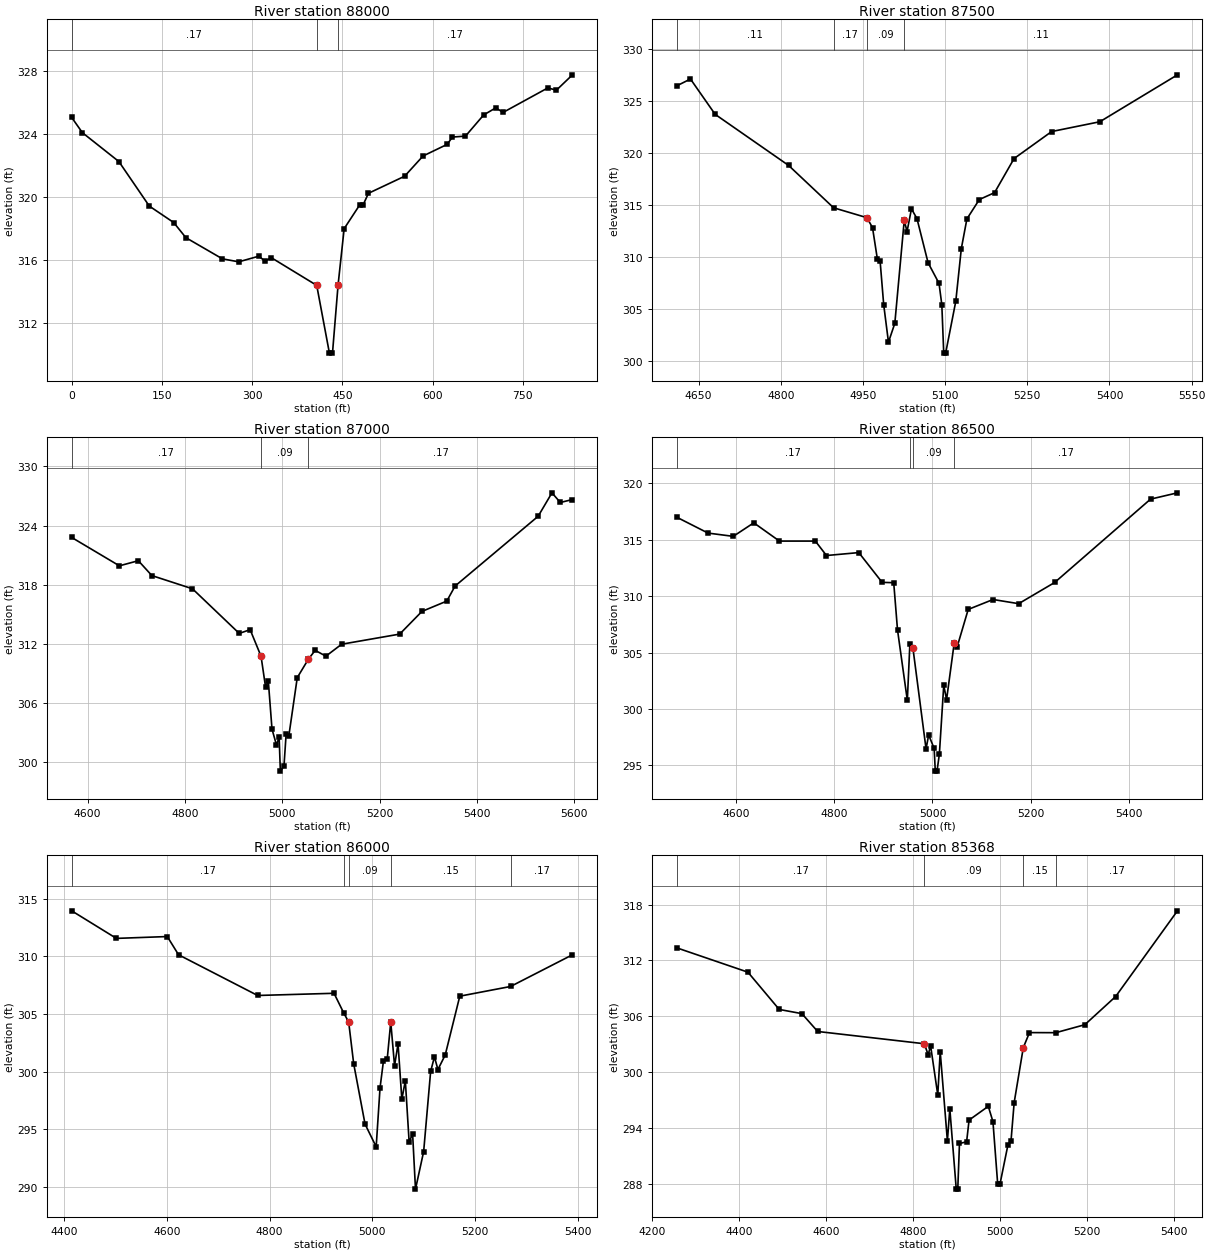
Type RM Length L Ch R = 1 ,88000   ,332,332,332
XS GIS Cut Line= 3
      3739695.29     10182159.84      3739271.46     10182092.62
      3738870.18     10182040.72
#Sta/Elev= 30
       0  325.04    17.7  324.08    78.4  322.25     129  319.43   169.5  318.39
   189.8  317.43   250.5  316.09   277.6   315.9   311.3  316.26   321.4  315.93
   331.5  316.17   407.3  314.41   428.4  310.12   433.5  310.12   442.8  314.44
   452.9     318   479.2  319.53   484.2  319.49   493.3  320.24   553.4  321.32
     584   322.6   624.3  323.34   632.8   323.8   654.6  323.86   684.8   325.2
     705  325.65   717.1  325.36   791.4  326.91   805.8  326.77   832.4  327.74
#Mann= 3 , 0 , 0
       0     .17       0   407.3     .09       0   442.8     .17       0
Bank Sta=407.3,442.8
XS Rating Curve= 0 ,0
Exp/Cntr=0.3,0.1

Type RM Length L Ch R = 1 ,87500   ,500,500,500
BEGIN DESCRIPTION:
LITTLE LAKE CREEK 168.0
END DESCRIPTION:
XS GIS Cut Line= 3
      3739767.89     10181961.08      3739385.91     10181881.94
      3738867.81     10181961.08
#Sta/Elev= 30
  4609.9  326.43    4635  327.09  4680.1   323.7  4814.2   318.8  4896.3  314.74
  4957.2  313.79  4967.4  312.83  4976.1  309.87  4981.2  309.66  4987.8  305.44
  4996.5  301.85  5008.1  303.66  5025.3  313.54  5030.4  312.46  5038.5  314.64
  5048.6  313.69  5068.8  309.47  5088.8  307.49  5093.9  305.45  5097.4   300.8
  5100.9   300.8  5119.4  305.77  5129.5  310.82  5139.7  313.67  5162.4  315.53
  5190.2  316.19  5225.8  319.46  5294.4  322.05  5382.4  322.99  5524.1  327.49
#Mann= 4 ,-1 , 0
  4609.9     .11       0  4896.3     .17       0  4957.2     .09       0
  5025.3     .11       0
#XS Ineff= 2 , 0
       0                  5025.3       0  313.54
Permanent Ineff=
       F       T
Bank Sta=4957.2,5025.3
XS Rating Curve= 0 ,0
Exp/Cntr=0.3,0.1

Type RM Length L Ch R = 1 ,87000   ,500,500,500
BEGIN DESCRIPTION:
LITTLE LAKE CREEK 167.0
END DESCRIPTION:
XS GIS Cut Line= 3
      3739794.67     10181688.17      3739408.91     10181492.15
      3738869.77     10181746.44
#Sta/Elev= 30
  4567.3  322.79  4665.3  319.91  4704.2  320.43    4732  318.92  4815.4  317.58
  4911.5  313.05  4933.9  313.43  4956.3  310.73  4965.6   307.6  4971.2  308.24
  4978.8  303.34  4987.9  301.74  4993.5  302.49    4996  299.07  5003.4  299.57
  5007.9  302.88  5013.5  302.68  5030.7  308.56  5053.5  310.43  5067.5  311.33
  5089.6  310.74  5121.8  311.95  5241.2  312.98  5286.8  315.28  5337.9  316.33
    5355  317.86  5525.6  324.94    5554  327.32  5571.2  326.34  5596.1  326.64
#Mann= 3 , 0 , 0
  4567.3     .17       0  4956.3     .09       0  5053.5     .17       0
Bank Sta=4956.3,5053.5
XS Rating Curve= 0 ,0
Exp/Cntr=0.3,0.1

Type RM Length L Ch R = 1 ,86500   ,500,500,500
BEGIN DESCRIPTION:
LITTLE LAKE CREEK 166.0
END DESCRIPTION:
XS GIS Cut Line= 3
      3739877.99     10181333.35      3739379.73     10181182.47
      3738955.47      10181444.4
#Sta/Elev= 30
  4479.4  317.01  4543.2   315.6  4594.5  315.31  4636.3  316.51  4688.5  314.89
  4761.6  314.89  4784.2  313.61    4850  313.87  4897.5  311.23  4921.1   311.2
  4928.8  307.02  4948.8  300.76    4954  305.79  4960.2   305.4  4986.9  296.46
  4992.2   297.7  5003.4   296.5  5005.7  294.49  5009.2  294.49    5014  295.99
  5022.9  302.09  5028.7  300.84  5044.1  305.81    5050  305.48  5072.7  308.83
  5123.3  309.71  5175.4  309.34  5248.7  311.22  5443.8  318.61  5498.6  319.17
#Mann= 4 ,-1 , 0
  4479.4     .17       0    4954     .12       0  4960.2     .09       0
  5044.1     .17       0
#XS Ineff= 2 , 0
       0    4954  305.79               0
Permanent Ineff=
       F       F
Bank Sta=4960.2,5044.1
XS Rating Curve= 0 ,0
Exp/Cntr=0.3,0.1

Type RM Length L Ch R = 1 ,86000   ,632,632,632
BEGIN DESCRIPTION:
LITTLE LAKE CREEK 165.0
END DESCRIPTION:
XS GIS Cut Line= 3
      3739807.02     10181129.73      3739275.01     10180885.01
      3739011.98     10180597.05
#Sta/Elev= 30
  4414.4  313.94  4501.5  311.55  4600.6  311.71  4622.6  310.13  4776.7   306.6
  4925.5  306.79  4944.2   305.1    4954   304.3  4963.8  300.68  4985.9  295.45
  5007.6  293.48  5015.1  298.58  5021.8  300.93  5029.2  301.13    5036   304.3
  5043.4  300.51  5050.2  302.41  5057.6   297.6  5064.4  299.21  5071.8  293.91
  5078.6  294.59  5084.2  289.81  5100.1  293.07  5113.7  300.01  5121.1  301.28
  5127.9  300.18  5142.1  301.44  5170.5  306.54  5269.4  307.38    5390  310.13
#Mann= 5 ,-1 , 0
  4414.4     .17       0  4944.2     .15       0    4954     .09       0
    5036     .15       0  5269.4     .17       0
#XS Ineff= 2 , 0
       0                    5036       0   304.3
Permanent Ineff=
       F       T
Bank Sta=4954,5036
XS Rating Curve= 0 ,0
Exp/Cntr=0.3,0.1

Type RM Length L Ch R = 1 ,85368   ,835,835,835
BEGIN DESCRIPTION:
LITTLE LAKE CREEK 164.0
END DESCRIPTION:
XS GIS Cut Line= 3
      3739840.94     10181086.54      3739498.23     10180426.84
      3739217.68     10180130.06
#Sta/Elev= 30
  4256.6  313.36  4420.4  310.74  4492.4  306.73  4544.5  306.28  4580.9  304.36
  4826.2  303.04    4835  301.85  4840.6  302.83  4857.1  297.53  4862.7  302.19
  4879.2  292.59  4884.8  296.04  4899.6   287.4  4903.1   287.4    4907  292.31
  4923.4  292.49  4929.1  294.83  4973.3  296.31    4984  294.66    4995   287.9
    5000   287.9  5018.6  292.19  5025.5  292.56  5032.8  296.71  5053.8  302.62
    5068  304.24  5128.5  304.23  5195.4  305.09  5266.2  308.12  5408.4  317.34
#Mann= 4 ,-1 , 0
  4256.6     .17       0  4826.2     .09       0  5053.8     .15       0
  5128.5     .17       0
#XS Ineff= 2 , 0
       0  4862.7  302.19               0
Permanent Ineff=
       F       F
Bank Sta=4826.2,5053.8
XS Rating Curve= 0 ,0
Exp/Cntr=0.3,0.1

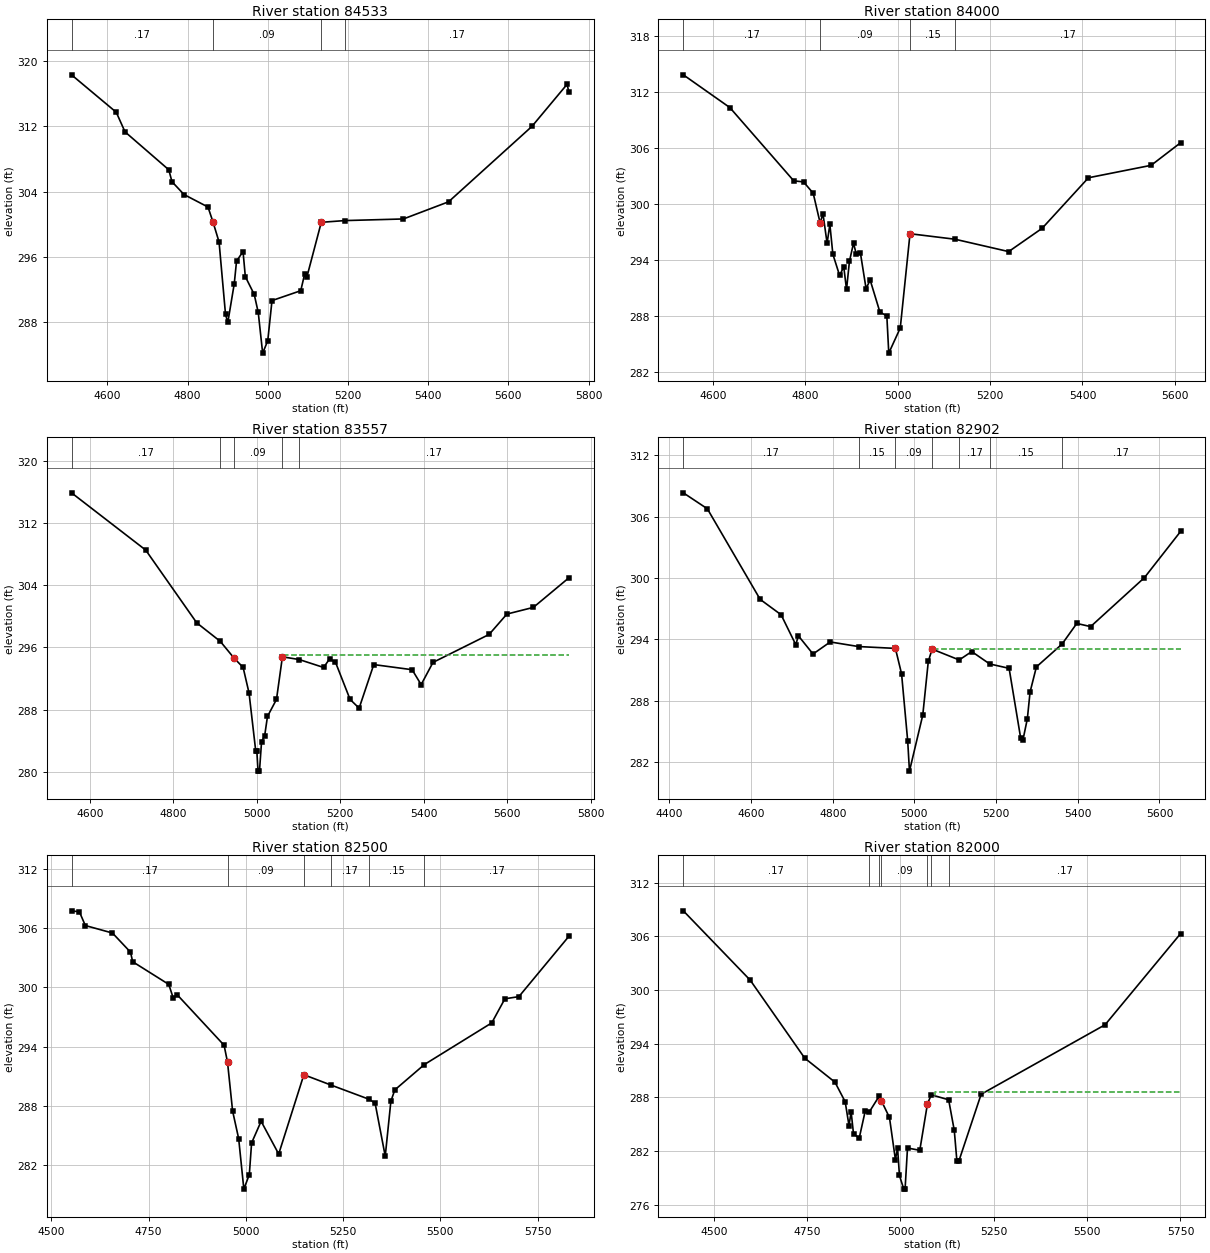
Type RM Length L Ch R = 1 ,84533   ,533,533,533
BEGIN DESCRIPTION:
LITTLE LAKE CREEK 162.0
END DESCRIPTION:
XS GIS Cut Line= 3
      3740417.83     10180411.06      3739988.23     10180176.84
      3739255.07     10180015.98
#Sta/Elev= 30
  4510.7  318.31  4622.2  313.73  4644.1  311.33  4753.2  306.69  4761.2  305.23
  4791.2  303.66    4851  302.13  4863.8  300.25  4878.6  297.85  4894.7  288.99
  4900.4     288  4916.5  292.75  4922.2  295.52  4938.4  296.68  4944.1  293.61
  4966.3  291.43  4976.3  289.23  4987.3  284.25    5000  285.76  5010.6  290.68
  5082.3  291.89  5092.2  293.97  5097.3  293.52  5133.5  300.26  5191.6  300.47
  5338.2  300.67  5450.9  302.77  5658.8     312  5746.4  317.15  5750.6  316.26
#Mann= 4 ,-1 , 0
  4510.7     .17       0  4863.8     .09       0  5133.5     .15       0
  5191.6     .17       0
#XS Ineff= 2 , 0
       0  4938.4  296.68               0
Permanent Ineff=
       F       F
Bank Sta=4863.8,5133.5
XS Rating Curve= 0 ,0
Exp/Cntr=0.3,0.1

Type RM Length L Ch R = 1 ,84000   ,443,443,443
BEGIN DESCRIPTION:
LITTLE LAKE CREEK 161.0
END DESCRIPTION:
XS GIS Cut Line= 3
      3740517.87     10180211.09      3740261.34     10179823.73
      3739767.87     10179461.08
#Sta/Elev= 30
  4535.4   313.8  4636.2   310.3  4774.6  302.47  4795.7  302.36  4816.7  301.15
  4831.8  297.95  4837.8  298.98  4846.8   295.8  4852.8  297.82  4859.3  294.63
  4873.9  292.36  4882.9  293.28  4888.9  290.86  4895.2  293.87    4904  295.81
    4910  294.65    4919  294.75  4931.2  290.96  4940.1  291.87  4961.1  288.46
  4976.2  288.03  4980.4  284.06  5005.3  286.75  5026.4  296.82    5124  296.23
  5240.1  294.91  5312.6   297.4  5412.9   302.8  5548.7  304.13  5612.4  306.54
#Mann= 4 ,-1 , 0
  4535.4     .17       0  4831.8     .09       0  5026.4     .15       0
    5124     .17       0
#XS Ineff= 2 , 0
       0    4904  295.81               0
Permanent Ineff=
       F       F
Bank Sta=4831.8,5026.4
XS Rating Curve= 0 ,0
Exp/Cntr=0.3,0.1

Type RM Length L Ch R = 1 ,83557   ,655,655,655
BEGIN DESCRIPTION:
LITTLE LAKE CREEK 160.0
END DESCRIPTION:
XS GIS Cut Line= 3
      3740917.83     10179711.06      3740518.23     10179516.84
      3740017.88      10178961.1
#Sta/Elev= 30
  4555.7   315.9  4733.6  308.53  4855.9  299.17  4912.3  296.79  4944.8  294.67
  4967.1  293.43  4981.3  290.14  4997.4  282.65    5000  282.65  5002.8  280.09
  5006.3  280.09  5011.3  283.88  5018.7  284.63  5025.5  287.13  5047.1  289.32
  5061.3   294.8  5101.5  294.45    5160  293.43  5174.2  294.51  5188.4  294.12
  5223.5  289.32  5245.2  288.19  5280.3   293.8  5372.3  293.14  5393.9  291.22
  5422.3  294.08  5556.9  297.68  5599.5   300.3    5663  301.16  5747.8  304.95
#Mann= 5 ,-1 , 0
  4555.7     .17       0  4912.3     .15       0  4944.8     .09       0
  5061.3     .15       0  5101.5     .17       0
#XS Ineff= 2 , 0
       0                  5068.1       0  294.99
Permanent Ineff=
       F       T
Bank Sta=4944.8,5061.3
XS Rating Curve= 0 ,0
Exp/Cntr=0.3,0.1

Type RM Length L Ch R = 1 ,82902   ,402,402,402
BEGIN DESCRIPTION:
LITTLE LAKE CREEK 159.0
END DESCRIPTION:
XS GIS Cut Line= 3
      3740967.87      10179511.1      3740652.28     10179033.02
      3740067.81     10178761.05
#Sta/Elev= 30
  4434.2  308.34    4493  306.78  4622.4  297.92  4673.6  296.42  4709.7  293.48
  4715.7  294.37  4751.8  292.58  4793.9  293.76  4863.2  293.31  4953.5  293.13
  4968.6  290.64  4983.6  284.08  4987.9  281.13  5020.5  286.61    5034  291.85
  5043.4  293.06  5109.7     292  5140.4  292.82  5184.3  291.61  5231.9  291.18
  5260.3  284.34  5265.8  284.18  5276.6  286.26  5283.2  288.86  5298.7  291.32
  5361.5  293.55  5397.6  295.57  5431.5  295.26  5563.3  300.05  5651.7  304.56
#Mann= 7 ,-1 , 0
  4434.2     .17       0  4863.2     .15       0  4953.5     .09       0
  5043.4     .15       0  5109.7     .17       0  5184.3     .15       0
  5361.5     .17       0
#XS Ineff= 2 , 0
       0                  5048.9       0  293.08
Permanent Ineff=
       F       T
Bank Sta=4953.5,5043.4
XS Rating Curve= 0 ,0
Exp/Cntr=0.3,0.1

Type RM Length L Ch R = 1 ,82500   ,500,500,500
BEGIN DESCRIPTION:
LITTLE LAKE CREEK 158.0
END DESCRIPTION:
XS GIS Cut Line= 3
      3741306.42     10178929.86      3740896.73     10178748.34
      3740075.37      10178627.5
#Sta/Elev= 30
  4551.9  307.77  4572.2  307.67  4587.3  306.28  4657.1  305.52  4703.5  303.58
  4709.1  302.61  4801.9  300.31  4813.2  298.95  4823.8  299.25  4944.1  294.14
  4952.9  292.43    4966  287.47  4981.6  284.67  4994.9  279.55    5009  281.03
  5014.8  284.23  5039.3  286.43  5084.5  283.11  5149.2  291.15  5218.5  290.11
  5317.7  288.65  5332.4  288.26  5358.4  282.89  5372.9  288.46    5383  289.61
  5458.9  292.18  5632.3  296.41    5666  298.85    5702  299.07  5830.2  305.17
#Mann= 6 ,-1 , 0
  4551.9     .17       0  4952.9     .09       0  5149.2     .15       0
  5218.5     .17       0  5317.7     .15       0  5458.9     .17       0
#XS Ineff= 2 , 0
       0                  5149.2       0  291.15
Permanent Ineff=
       F       F
Bank Sta=4952.9,5149.2
XS Rating Curve= 0 ,0
Exp/Cntr=0.3,0.1

Type RM Length L Ch R = 1 ,82000   ,500,500,500
BEGIN DESCRIPTION:
LITTLE LAKE CREEK 157.0
END DESCRIPTION:
XS GIS Cut Line= 3
      3741405.15       10178646.      3740898.23     10178361.09
      3740167.94     10178189.39
#Sta/Elev= 30
  4418.5  308.87  4597.6  301.12  4743.6   292.4  4824.6  289.71    4852  287.52
  4862.2  284.86  4867.9  286.39  4874.3  283.94  4889.6  283.46  4905.6  286.47
  4916.4  286.37  4943.1  288.15  4948.9  287.63  4970.6  285.76  4986.5  281.05
  4992.3  282.35  4997.3  279.28  5008.9  277.75  5012.4  277.75  5018.9  282.35
  5051.8  282.09  5072.3  287.28  5082.6   288.3  5129.1  287.74  5144.2  284.31
  5151.2  280.89  5156.3  280.87  5216.1  288.36  5548.1  296.13  5750.2  306.32
#Mann= 7 ,-1 , 0
  4418.5     .17       0  4916.4     .15       0  4943.1     .12       0
  4948.9     .09       0  5072.3     .12       0  5082.6     .15       0
  5129.1     .17       0
#XS Ineff= 2 , 0
       0  4943.1  288.15  5092.8       0  288.56
Permanent Ineff=
       F       F
Bank Sta=4948.9,5072.3
XS Rating Curve= 0 ,0
Exp/Cntr=0.3,0.1

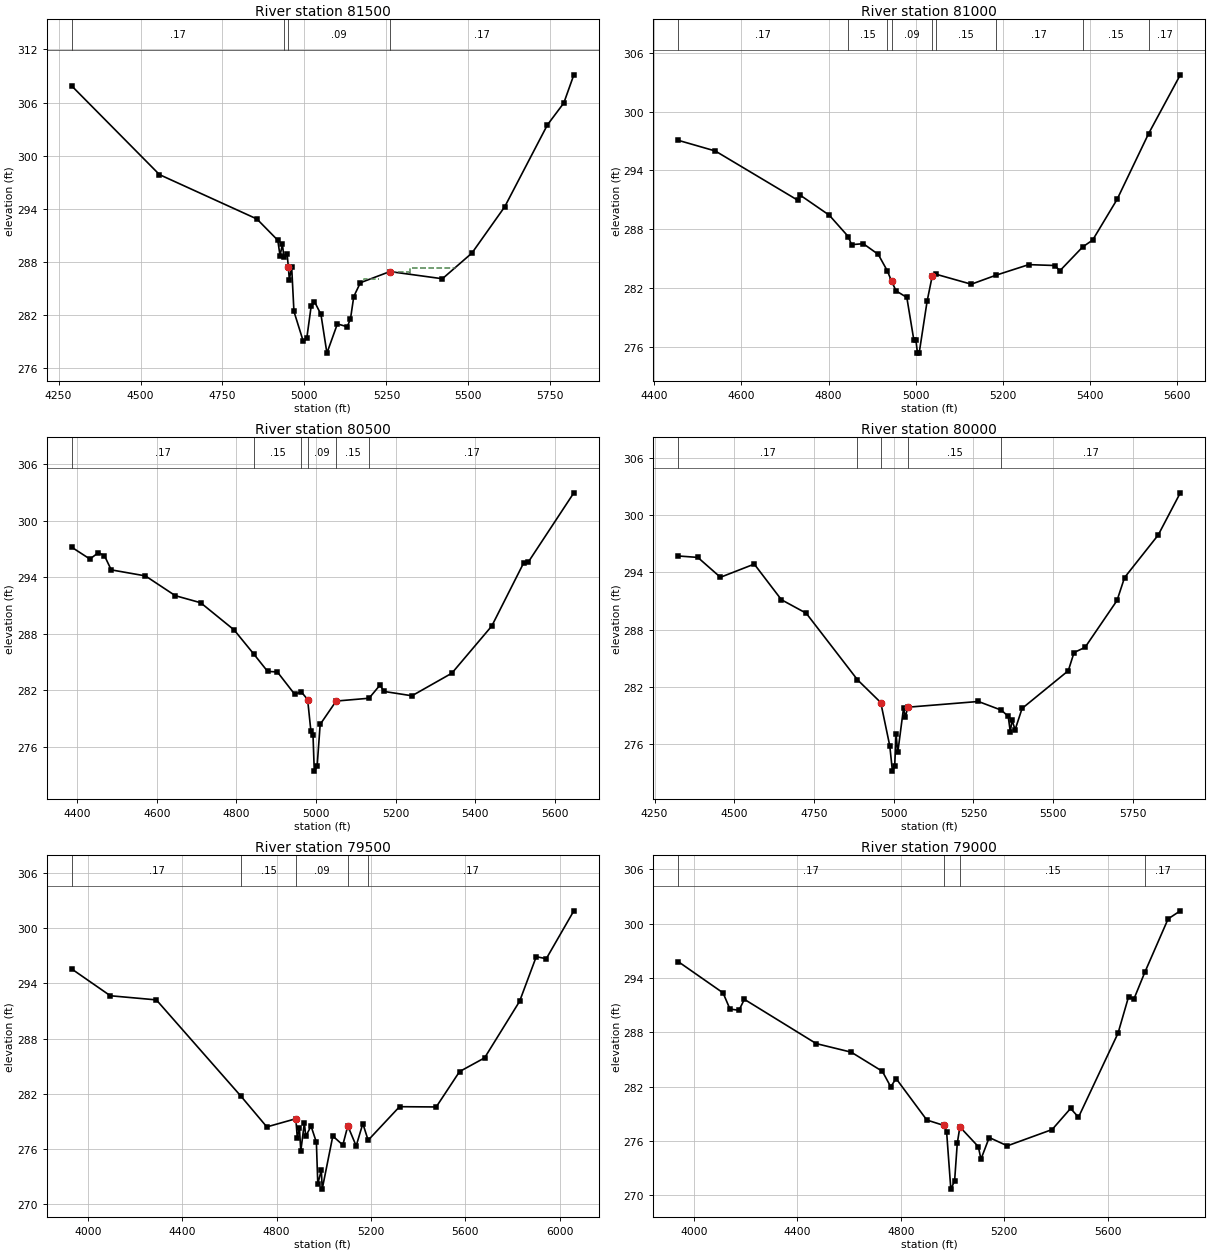
Type RM Length L Ch R = 1 ,81500   ,500,500,500
BEGIN DESCRIPTION:
LITTLE LAKE CREEK 156.0
END DESCRIPTION:
XS GIS Cut Line= 3
       3741525.5     10178451.63      3741038.23     10177935.65
       3740217.3     10177973.42
#Sta/Elev= 30
  4290.3  307.87  4557.8  297.86    4855  292.85  4918.7  290.45  4925.5  288.72
  4932.8  289.97  4937.7  288.51    4947  288.95  4950.9  287.45  4953.9     286
  4961.1   287.4    4968  282.41  4996.3  279.05  5007.3  279.42  5020.4  282.97
  5030.4  283.53  5050.4  282.07  5068.6   277.7  5100.5     281  5130.5  280.68
  5140.5  281.57  5150.5  284.09  5170.6  285.65  5260.7  286.91  5420.8   286.1
  5510.9     289    5611  294.23  5741.2  303.48  5791.2  305.95  5821.8  309.13
#Mann= 4 ,-1 , 0
  4290.3     .17       0  4937.7     .15       0  4950.9     .09       0
  5260.7     .17       0
#XS Ineff= 4 ,-1
  4961.1    4947   287.4  5180.6  5226.2  286.02  5260.7  5320.7  286.91
  5320.7  5460.9  287.33
Permanent Ineff=
       F       F       F       F
Bank Sta=4950.9,5260.7
XS Rating Curve= 0 ,0
Exp/Cntr=0.3,0.1

Type RM Length L Ch R = 1 ,81000   ,500,500,500
BEGIN DESCRIPTION:
LITTLE LAKE CREEK 155.0
END DESCRIPTION:
XS GIS Cut Line= 3
      3741506.97     10177643.28      3740973.42     10177531.65
      3740374.72     10177433.49
#Sta/Elev= 30
  4454.9  297.07  4539.9  295.98  4729.5  290.94  4734.6  291.47  4801.4  289.42
  4845.1  287.23  4852.4  286.41  4879.4  286.51  4913.7  285.42  4934.4  283.75
  4944.4  282.67  4954.6  281.69  4979.3  281.02  4995.2  276.72    5000  276.72
  5003.7  275.33  5007.6  275.33  5025.9  280.65  5037.8  283.25  5046.2  283.39
  5127.2  282.37  5183.8  283.29    5259  284.37  5319.8  284.28  5329.9  283.72
  5382.8  286.18  5405.6  286.88  5461.7  291.04  5533.9  297.75  5606.7  303.76
#Mann= 9 ,-1 , 0
  4454.9     .17       0  4845.1     .15       0  4934.4     .12       0
  4944.4     .09       0  5037.8     .12       0  5046.2     .15       0
  5183.8     .17       0  5382.8     .15       0  5533.9     .17       0
Bank Sta=4944.4,5037.8
XS Rating Curve= 0 ,0
Exp/Cntr=0.3,0.1

Type RM Length L Ch R = 1 ,80500   ,500,500,500
BEGIN DESCRIPTION:
LITTLE LAKE CREEK 154.0
END DESCRIPTION:
XS GIS Cut Line= 3
      3741590.31     10177365.61      3741018.23     10177142.34
      3740372.24     10177195.86
#Sta/Elev= 30
  4385.9   297.2  4431.5  295.95  4452.9  296.63  4468.1   296.3  4485.1   294.8
    4571  294.16  4646.2  292.06  4709.9  291.31  4794.1  288.42  4844.1  285.83
  4878.3  284.02  4902.8  283.96  4946.7  281.57  4962.5  281.87  4978.9  281.03
    4987  277.71  4992.4  277.28  4995.6  273.43  5002.7  273.93  5010.4  278.39
  5050.6  280.87  5133.3  281.17  5160.9  282.57  5171.1  281.89  5241.2  281.43
  5341.5  283.83  5441.9  288.84  5522.2  295.55  5533.4  295.61  5648.2  302.98
#Mann= 6 ,-1 , 0
  4385.9     .17       0  4844.1     .15       0  4962.5     .12       0
  4978.9     .09       0  5050.6     .15       0  5133.3     .17       0
Bank Sta=4978.9,5050.6
XS Rating Curve= 0 ,0
Exp/Cntr=0.3,0.1

Type RM Length L Ch R = 1 ,80000   ,500,500,500
BEGIN DESCRIPTION:
LITTLE LAKE CREEK 153.0
END DESCRIPTION:
XS GIS Cut Line= 3
      3741642.79     10177232.98      3741188.23     10176732.76
      3740361.05     10177084.09
#Sta/Elev= 30
  4324.1  295.72  4385.5  295.57  4456.4  293.49  4562.5  294.87  4647.7  291.14
  4725.4  289.73  4886.3  282.76  4959.2  280.38  4987.6  275.83  4995.8   273.2
  5002.9   273.7  5007.2  277.11  5012.6  275.15  5030.8  279.83  5036.2  278.83
  5043.9  279.89  5265.4  280.49  5337.5  279.58  5358.9  278.94  5365.5  277.32
  5370.9  278.52  5380.7  277.54  5402.4  279.76  5547.4  283.71  5565.4  285.61
  5600.1  286.16  5700.2  291.06  5723.8  293.46  5829.3  297.91  5898.7  302.33
#Mann= 5 ,-1 , 0
  4324.1     .17       0  4886.3     .15       0  4959.2     .09       0
  5043.9     .15       0  5337.5     .17       0
Bank Sta=4959.2,5043.9
XS Rating Curve= 0 ,0
Exp/Cntr=0.3,0.1

Type RM Length L Ch R = 1 ,79500   ,500,500,500
BEGIN DESCRIPTION:
LITTLE LAKE CREEK 152.0
END DESCRIPTION:
XS GIS Cut Line= 3
      3741692.15     10177174.36      3741098.23     10176286.61
      3740343.84     10177032.39
#Sta/Elev= 30
  3931.9  295.57  4095.4  292.66  4290.5  292.21    4650  281.71    4759  278.39
  4882.1  279.28  4888.1  277.19  4897.1  278.28  4903.1  275.77  4918.1  278.81
  4924.1  277.37  4946.5  278.48  4969.1  276.72  4975.1  272.18  4990.2   273.7
  4993.8  271.62  5038.8   277.4  5081.2  276.42  5102.4   278.5  5137.8  276.32
  5166.1  278.75  5188.6  276.94  5321.7  280.59  5477.2  280.56  5576.2  284.41
  5682.3   285.9  5830.7  292.05  5901.4  296.91  5943.9  296.69  6060.8   301.9
#Mann= 5 ,-1 , 0
  3931.9     .17       0    4650     .15       0  4882.1     .09       0
  5102.4     .15       0  5188.6     .17       0
#XS Ineff= 2 , 0
       0  4680.9  280.53  5321.7       0  280.59
Permanent Ineff=
       F       F
Bank Sta=4882.1,5102.4
XS Rating Curve= 0 ,0
Exp/Cntr=0.3,0.1

Type RM Length L Ch R = 1 ,79000   ,500,500,500
BEGIN DESCRIPTION:
LITTLE LAKE CREEK 151.0
END DESCRIPTION:
XS GIS Cut Line= 3
      3741710.38     10177169.43      3741459.38     10176138.65
      3741289.64     10175274.77
#Sta/Elev= 30
  3939.1  295.82  4112.4  292.37  4139.1  290.58  4174.1  290.45  4194.7  291.66
  4472.6  286.77  4608.2  285.82  4728.3  283.71  4760.8     282  4781.4  282.91
  4900.3  278.33  4966.6  277.73  4976.9  276.98  4993.1   270.7  5007.7   271.6
  5017.9  275.74  5028.1  277.57  5099.4  275.39  5109.6     274  5141.5   276.4
  5211.5  275.48  5384.8  277.28  5456.1  279.61  5486.7  278.64  5639.6  287.92
  5680.3  291.94  5700.7  291.67  5743.4  294.66  5833.2  300.54  5880.4  301.43
#Mann= 4 ,-1 , 0
  3939.1     .17       0  4966.6     .09       0  5028.1     .15       0
  5743.4     .17       0
#XS Ineff= 2 , 0
       0                  5456.1       0  279.61
Permanent Ineff=
       F       F
Bank Sta=4966.6,5028.1
XS Rating Curve= 0 ,0
Exp/Cntr=0.3,0.1

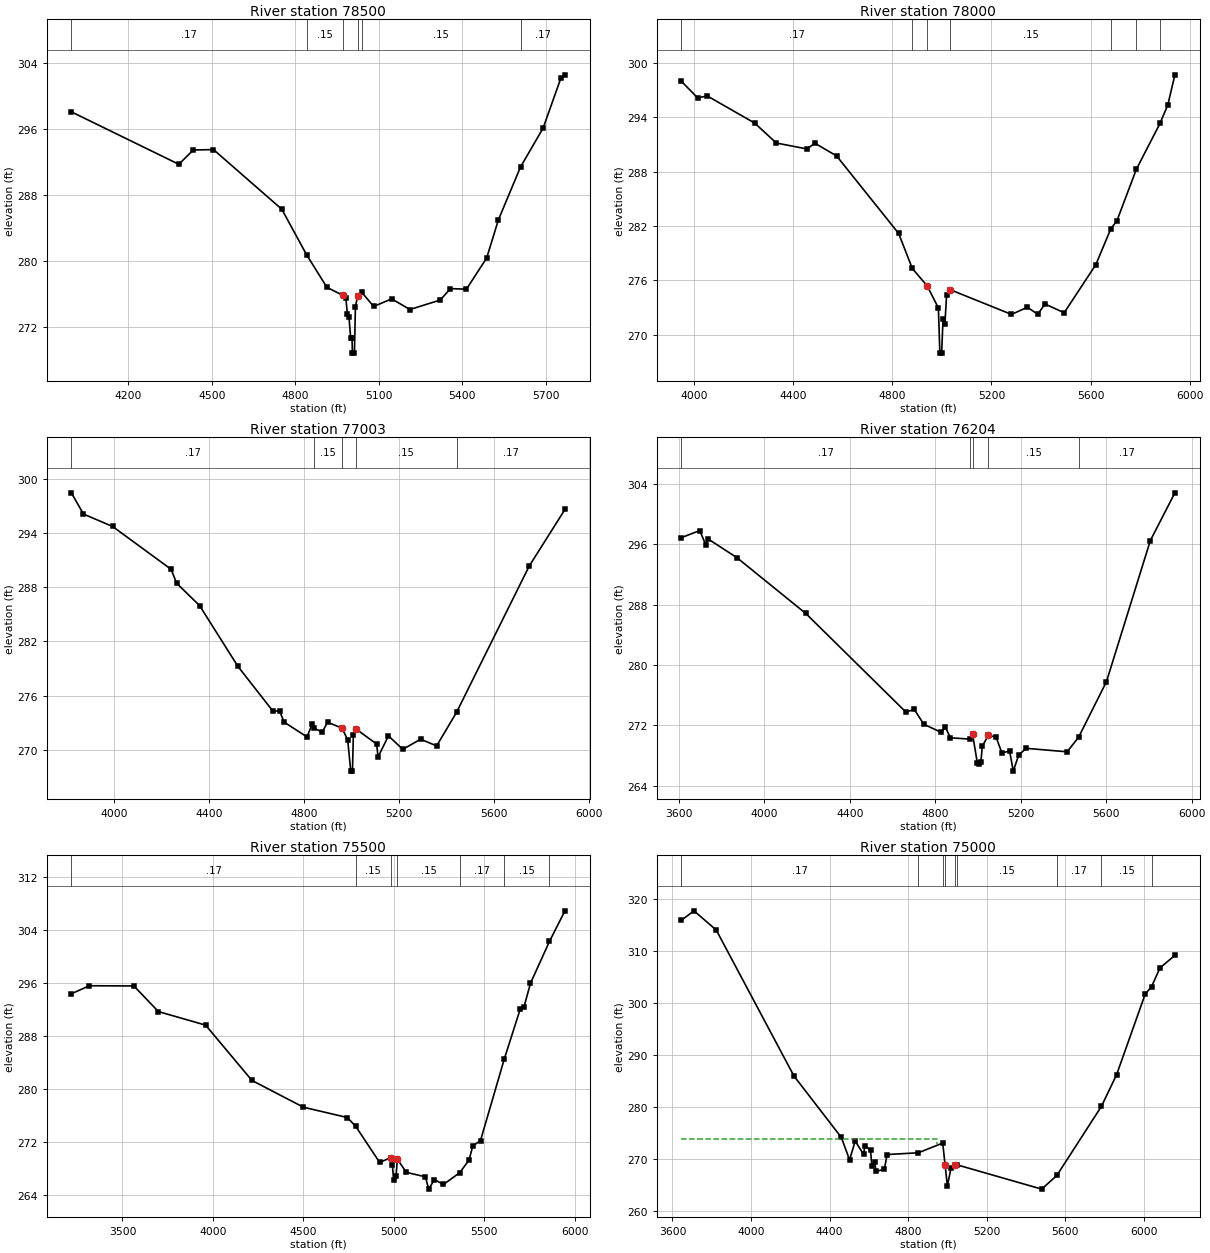
Type RM Length L Ch R = 1 ,78500   ,500,500,500
BEGIN DESCRIPTION:
LITTLE LAKE CREEK 150.0
END DESCRIPTION:
XS GIS Cut Line= 3
      3742249.32     10176772.41      3741777.05     10175884.72
      3741363.71      10175235.3
#Sta/Elev= 30
  3994.5  298.05  4381.1   291.7  4433.1  293.43  4505.7  293.48  4751.4  286.26
  4840.9  280.73  4913.5  276.81  4971.1  275.83  4981.5  275.55  4987.4   273.6
  4993.1  273.16  4999.2  270.68  5003.9  270.68  5005.5  268.84  5012.6  268.84
  5016.2  274.44  5024.3   275.8  5039.5  276.18  5081.8  274.49  5146.6  275.41
  5212.2  274.12  5321.4  275.27  5357.8  276.65  5415.4  276.58  5488.2  280.35
  5530.6  284.99  5610.2  291.39  5691.4  296.09  5754.9  302.11  5769.8  302.53
#Mann= 6 ,-1 , 0
  3994.5     .17       0  4840.9     .15       0  4971.1     .09       0
  5024.3     .12       0  5039.5     .15       0  5610.2     .17       0
Bank Sta=4971.1,5024.3
XS Rating Curve= 0 ,0
Exp/Cntr=0.3,0.1

Type RM Length L Ch R = 1 ,78000   ,997,997,997
BEGIN DESCRIPTION:
LITTLE LAKE CREEK 149.0
END DESCRIPTION:
XS GIS Cut Line= 3
      3742258.33      10176766.5      3742188.94       10175717.
      3741481.92     10175096.94
#Sta/Elev= 30
  3948.2  297.98  4013.8  296.15  4053.9  296.34  4244.3  293.36  4331.9  291.16
  4454.7  290.51  4487.9  291.13    4575  289.74  4825.5  281.19  4880.6  277.33
  4940.7   275.4  4985.9  272.97  4991.9  267.99    4999  267.99  5004.7  271.76
  5012.3  271.24    5019  274.39  5033.2  274.99  5280.9  272.26  5345.4  273.05
  5387.2  272.27  5415.7  273.41  5493.6  272.44  5621.6  277.76  5681.9  281.71
  5706.4  282.58    5785  288.27  5880.3  293.32    5912  295.37  5940.4  298.68
#Mann= 7 ,-1 , 0
  3948.2     .17       0  4880.6     .15       0  4940.7     .09       0
  5033.2     .15       0  5681.9     .17       0    5785     .15       0
  5880.3     .17       0
Bank Sta=4940.7,5033.2
XS Rating Curve= 0 ,0
Exp/Cntr=0.3,0.1

Type RM Length L Ch R = 1 ,77003   ,799,799,799
BEGIN DESCRIPTION:
LITTLE LAKE CREEK 147.0
END DESCRIPTION:
XS GIS Cut Line= 4
      3743062.68     10176502.17      3742624.42     10175422.24
      3742598.38     10175420.07      3742182.68     10174632.78
#Sta/Elev= 30
  3818.1  298.43  3869.3  296.08    3992  294.71    4239  289.97  4261.8  288.44
  4358.9  285.96  4520.8  279.23  4667.5  274.31    4697  274.29    4715  273.08
  4812.2  271.43  4833.7  272.86  4841.7   272.4  4876.4  271.96  4898.5  273.06
  4959.5  272.41  4983.6  271.12  4996.6  267.65  5003.8  267.65  5007.5  271.68
  5017.9  272.33  5105.9  270.64  5111.6  269.21  5155.6  271.55    5216  270.06
  5291.3  271.18  5358.8  270.44  5442.7  274.15  5749.5  290.34    5900  296.59
#Mann= 5 ,-1 , 0
  3818.1     .17       0  4841.7     .15       0  4959.5     .09       0
  5017.9     .15       0  5442.7     .17       0
Bank Sta=4959.5,5017.9
XS Rating Curve= 0 ,0
Exp/Cntr=0.3,0.1

Type RM Length L Ch R = 1 ,76204   ,704,704,704
BEGIN DESCRIPTION:
LITTLE LAKE CREEK 145.0
END DESCRIPTION:
XS GIS Cut Line= 3
      3743406.42     10176470.91      3743020.97     10175136.77
      3742334.73     10174521.76
#Sta/Elev= 30
  3611.3  296.88  3697.9  297.82  3725.6  295.94  3736.7  296.71  3871.3  294.24
    4194  286.84  4662.4  273.78  4701.9  274.12    4746  272.17    4829  271.07
  4846.8  271.81  4870.6  270.37  4961.7  270.19  4974.7  270.83  4996.6  267.09
    5006  266.96  5013.5  267.14  5020.2  269.26  5048.6   270.7  5084.5  270.46
  5112.1  268.35    5148  268.62  5165.2  265.95  5190.7   268.1  5225.8  268.97
  5417.2  268.51  5470.6  270.43  5601.1  277.79  5806.7   296.5  5921.5  302.82
#Mann= 5 ,-1 , 0
  3611.3     .17       0  4961.7     .15       0  4974.7     .09       0
  5048.6     .15       0  5470.6     .17       0
Bank Sta=4974.7,5048.6
XS Rating Curve= 0 ,0
Exp/Cntr=0.3,0.1

Type RM Length L Ch R = 1 ,75500   ,500,500,500
BEGIN DESCRIPTION:
LITTLE LAKE CREEK 144.0
END DESCRIPTION:
XS GIS Cut Line= 3
      3743479.34     10176450.09      3743342.91     10174672.82
       3742656.4     10174022.97
#Sta/Elev= 30
  3217.5  294.35  3316.8  295.56  3563.1  295.53  3698.6  291.67  3959.6  289.63
  4215.6   281.3  4500.3  277.27  4742.7  275.72  4789.6  274.37  4921.5  268.95
  4981.7  269.68  4991.7  268.59  4998.4   266.3  5011.8  266.88  5019.1  269.45
  5068.5  267.47  5174.5  266.79  5192.1  264.94  5224.2  266.38  5273.6  265.64
  5363.8  267.41  5415.1  269.32  5436.2  271.43  5478.7  272.26    5610  284.53
  5697.9  292.03  5719.3   292.4  5754.5  295.91  5859.6  302.23  5945.3  306.84
#Mann= 7 ,-1 , 0
  3217.5     .17       0  4789.6     .15       0  4981.7     .09       0
  5019.1     .15       0  5363.8     .17       0    5610     .15       0
  5859.6     .17       0
#XS Ineff= 2 , 0
       0                  5443.5       0  271.53
Permanent Ineff=
       F       F
Bank Sta=4981.7,5019.1
XS Rating Curve= 0 ,0
Exp/Cntr=0.3,0.1

Type RM Length L Ch R = 1 ,75000   ,1000,1000,1000
BEGIN DESCRIPTION:
LITTLE LAKE CREEK 143.0
END DESCRIPTION:
XS GIS Cut Line= 3
      3744646.01     10175424.04      3743733.88     10174421.74
       3742673.3     10173955.84
#Sta/Elev= 30
  3644.8  315.81  3709.3  317.64  3822.8  313.96  4218.8  285.92    4460  274.13
  4501.9  269.81  4530.3  273.44  4572.8   270.9  4580.3  272.52  4608.6  271.63
  4615.4  268.66  4629.6  269.46  4636.3  267.61  4678.9  268.02  4693.1  270.85
  4852.1  271.19  4976.2  273.06 4988.38  268.76    5000  264.82  5018.5   268.3
  5036.4  268.79  5050.3  268.86  5480.3  264.21  5557.4  266.84  5784.5  280.11
  5861.7  286.19  6007.3  301.66  6039.8   303.1  6082.8  306.69  6158.4  309.09
#Mann= 9 ,-1 , 0
  3644.8     .17       0  4852.1     .15       0  4976.2     .12       0
 4988.38     .09       0  5036.4     .12       0  5050.3     .15       0
  5557.4     .17       0  5784.5     .15       0  6039.8     .17       0
#XS Ineff= 2 , 0
       0  4947.8   273.8               0
Permanent Ineff=
       F       F
Bank Sta=4988.38,5036.4
XS Rating Curve= 0 ,0
Exp/Cntr=0.3,0.1