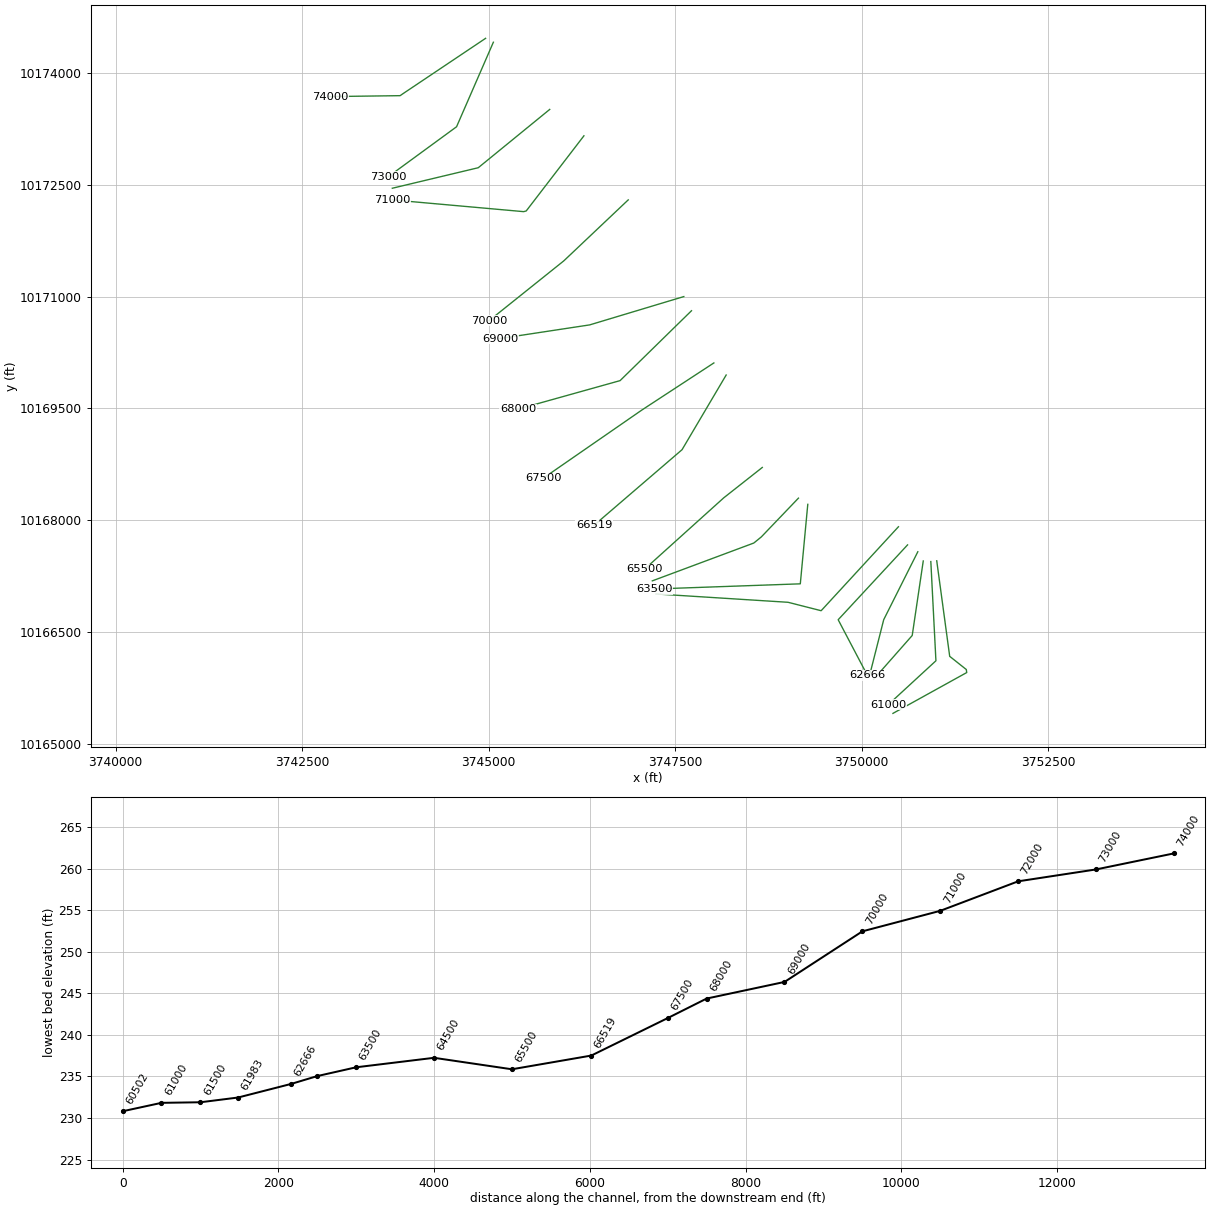
HEC-RAS study LITTLE LAKE CREEK.prj: LITTLE LAKE CREEK Base Level Engineering

--- LITTLE LAKE CREEK.g01 (geometry) --- (continued)

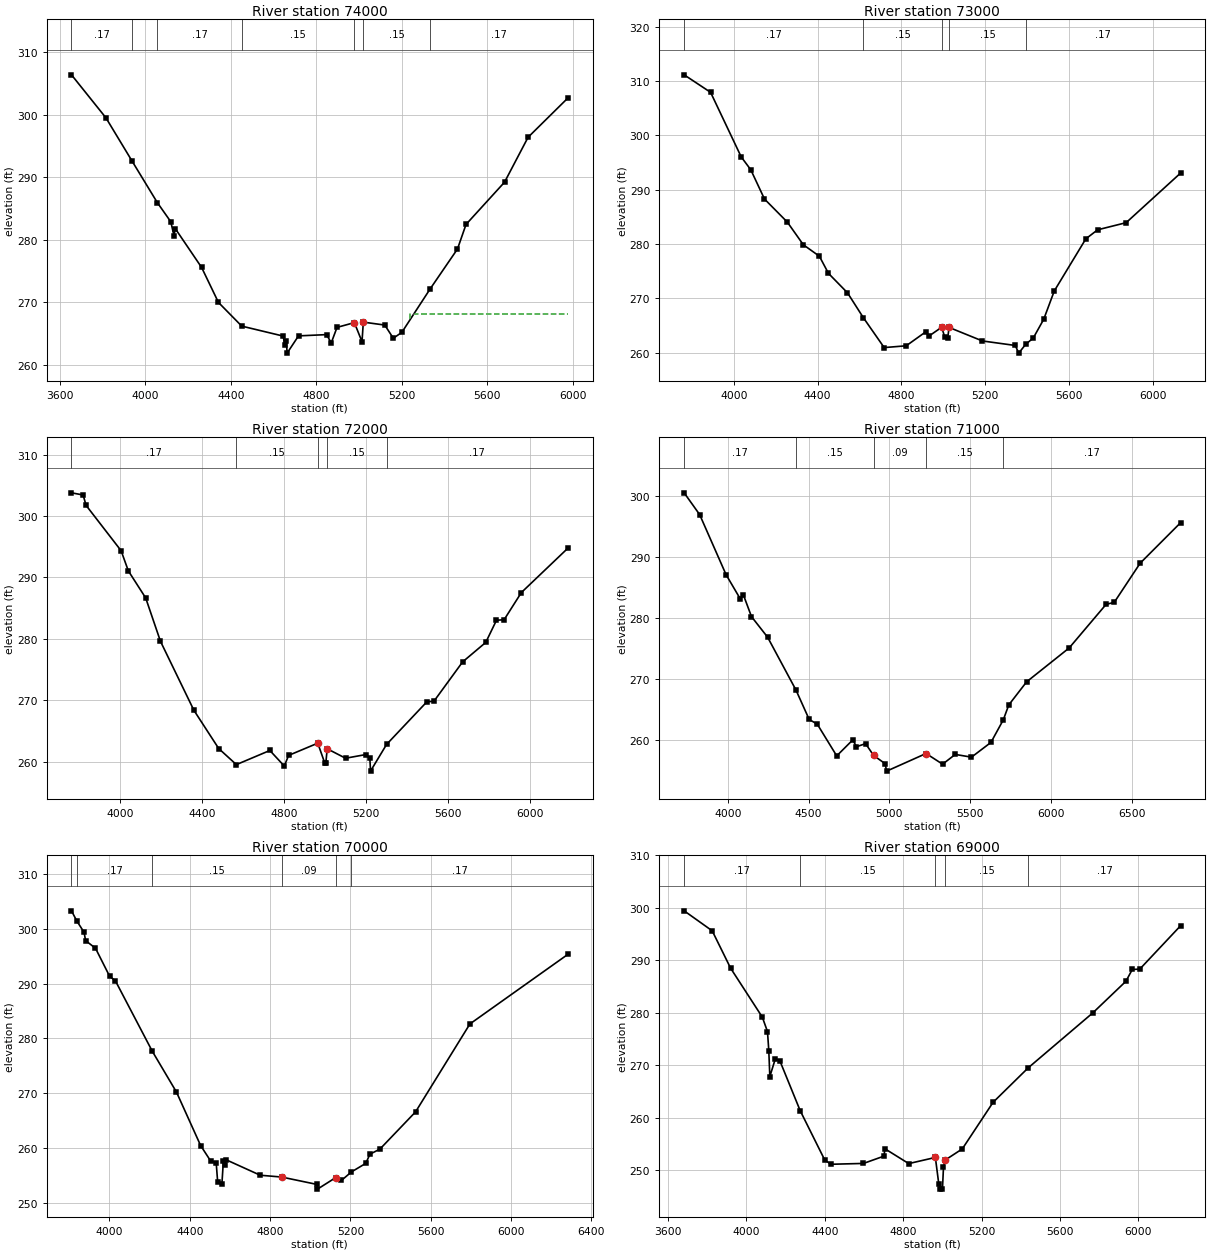
Type RM Length L Ch R = 1 ,74000   ,1000,1000,1000
BEGIN DESCRIPTION:
LITTLE LAKE CREEK 141.0
END DESCRIPTION:
XS GIS Cut Line= 4
      3744958.63     10174464.51      3743841.87     10173715.83
      3743813.22     10173695.67      3742871.43     10173683.29
#Sta/Elev= 30
  3655.5  306.36  3816.6  299.48    3939  292.55  4056.9  285.92  4119.8  282.86
  4134.8  280.63  4140.8  281.76  4263.9  275.55  4342.7  269.95  4451.6  266.16
    4645  264.57    4654   263.1    4660  263.78  4663.8  261.84  4717.1   264.6
  4848.3   264.8  4870.1  263.48  4897.2  265.96  4978.2  266.72    5014  263.67
  5020.1   266.8  5120.4  266.33  5160.4  264.22  5200.4  265.17  5331.2  272.04
  5460.4   278.5  5500.4  282.43  5680.5  289.19  5790.5  296.37  5976.9  302.66
#Mann= 7 ,-1 , 0
  3655.5     .17       0    3939     .11       0  4056.9     .17       0
  4451.6     .15       0  4978.2     .09       0  5020.1     .15       0
  5331.2     .17       0
#XS Ineff= 2 , 0
       0                  5240.4       0   268.1
Permanent Ineff=
       F       F
Bank Sta=4978.2,5020.1
XS Rating Curve= 0 ,0
Exp/Cntr=0.3,0.1

Type RM Length L Ch R = 1 ,73000   ,1000,1000,1000
BEGIN DESCRIPTION:
LITTLE LAKE CREEK 139.0
END DESCRIPTION:
XS GIS Cut Line= 3
      3745062.81     10174412.45      3744569.56      10173278.7
      3743656.55     10172610.35
#Sta/Elev= 30
  3763.6  311.13  3889.7  307.91  4035.8  296.02  4081.4  293.66  4146.8  288.27
  4255.8  284.02  4332.2  279.85  4408.5  277.75  4452.1  274.58  4542.7  271.01
  4618.2  266.44  4717.7  260.93  4822.9  261.26  4916.1  263.83    4932  263.07
  4991.9  264.67  5006.4  262.89    5021  262.78  5027.2  264.64  5186.2  262.15
    5343  261.32  5359.4  259.91    5393  261.55  5428.7  262.68  5478.9  266.16
    5529  271.35  5679.6  280.95    5736  282.61  5871.8  283.92  6131.5  293.05
#Mann= 5 ,-1 , 0
  3763.6     .17       0  4618.2     .15       0  4991.9     .09       0
  5027.2     .15       0    5393     .17       0
Bank Sta=4991.9,5027.2
XS Rating Curve= 0 ,0
Exp/Cntr=0.3,0.1

Type RM Length L Ch R = 1 ,72000   ,1000,1000,1000
BEGIN DESCRIPTION:
LITTLE LAKE CREEK 137.0
END DESCRIPTION:
XS GIS Cut Line= 3
      3745817.84     10173511.06      3744860.32     10172729.17
      3743708.61      10172454.1
#Sta/Elev= 30
  3763.8  303.77  3820.5  303.42  3834.9  301.73  4005.7  294.35  4040.9  291.07
  4125.6  286.66  4197.4  279.62  4360.4  268.39  4481.7  262.15  4567.7  259.54
  4730.9  261.84  4801.2  259.31  4822.4  261.04  4964.5  263.03  4998.4  259.81
  5003.8  259.81  5010.5  262.12  5099.8  260.58  5197.9  261.17  5218.4  260.64
  5221.6  258.48  5299.8  262.82    5496  269.75    5531  269.86  5670.8  276.26
  5783.5  279.43  5835.8  283.04  5872.8  283.11    5957  287.54  6184.1  294.77
#Mann= 5 ,-1 , 0
  3763.8     .17       0  4567.7     .15       0  4964.5     .09       0
  5010.5     .15       0  5299.8     .17       0
Bank Sta=4964.5,5010.5
XS Rating Curve= 0 ,0
Exp/Cntr=0.3,0.1

Type RM Length L Ch R = 1 ,71000   ,1000,1000,1000
BEGIN DESCRIPTION:
LITTLE LAKE CREEK 135.0
END DESCRIPTION:
XS GIS Cut Line= 4
      3746276.34     10173157.22      3745503.06      10172149.4
       3745468.6     10172140.12      3743708.64     10172297.85
#Sta/Elev= 30
  3729.7  300.58  3825.7  297.01  3989.5  287.14  4075.9  283.24  4096.8  283.81
  4146.6  280.27  4246.3   276.9  4422.1  268.22  4503.8   263.4  4553.6  262.64
  4674.1  257.43  4773.8  260.06  4796.2  258.93  4852.7  259.44  4902.6   257.5
  4973.2  256.16  4983.2  254.93  5227.2  257.82  5329.5  256.07  5407.9  257.67
  5508.3  257.22  5628.8  259.64  5705.4  263.35  5739.2  265.79  5849.7  269.58
  6113.2  275.14  6341.7  282.29  6391.9  282.61  6552.5  289.04  6802.7  295.68
#Mann= 5 ,-1 , 0
  3729.7     .17       0  4422.1     .15       0  4902.6     .09       0
  5227.2     .15       0  5705.4     .17       0
#XS Ineff= 2 , 0
       0  4773.8  260.06               0
Permanent Ineff=
       F       F
Bank Sta=4902.6,5227.2
XS Rating Curve= 0 ,0
Exp/Cntr=0.3,0.1

Type RM Length L Ch R = 1 ,70000   ,1000,1000,1000
BEGIN DESCRIPTION:
LITTLE LAKE CREEK 133.0
END DESCRIPTION:
XS GIS Cut Line= 3
      3746870.07     10172297.82      3746006.98     10171480.31
      3745005.49     10170678.04
#Sta/Elev= 30
  3811.2  303.34  3838.1  301.46  3874.1   299.4  3881.3   297.9  3930.7   296.5
  4001.5  291.35  4029.8  290.55  4213.5  277.67    4334   270.2  4454.2  260.43
  4503.5  257.64  4531.8  257.25  4539.1  253.75  4560.1  253.32  4567.4  257.57
  4574.3  256.83  4581.6  257.82  4751.1     255  4857.5  254.67  5034.8  253.31
  5036.1  252.46    5127  254.57  5154.9  254.04  5205.4  255.61  5276.5  257.17
  5297.3  258.85    5347  259.78  5524.6  266.59  5795.1  282.66  6283.2  295.39
#Mann= 6 ,-1 , 0
  3811.2     .11       0  3838.1     .17       0  4213.5     .15       0
  4857.5     .09       0    5127     .15       0  5205.4     .17       0
#XS Ineff= 2 , 0
       0  4581.6  257.82               0
Permanent Ineff=
       F       F
Bank Sta=4857.5,5127
XS Rating Curve= 0 ,0
Exp/Cntr=0.3,0.1

Type RM Length L Ch R = 1 ,69000   ,1000,1000,1000
BEGIN DESCRIPTION:
LITTLE LAKE CREEK 131.0
END DESCRIPTION:
XS GIS Cut Line= 3
      3747614.92     10171000.99      3746353.81     10170621.37
      3745152.13      10170438.6
#Sta/Elev= 30
    3683  299.43  3826.1  295.62  3920.1  288.49  4081.8  279.16  4108.1  276.41
  4114.8  272.79  4120.1  267.83  4147.9  271.19  4170.8  270.88  4274.8  261.34
  4400.5   251.9  4432.8  251.11  4597.9  251.27  4702.1  252.66  4707.4  254.06
  4828.7  251.24  4964.5  252.41  4981.9  247.38  4989.9  246.37  5000.7  246.37
    5006  250.58  5016.1  251.95  5101.9  254.04  5258.9  262.92    5438  269.49
  5768.2  279.99  5936.6     286  5969.1  288.25  6007.4  288.32  6215.5  296.59
#Mann= 5 ,-1 , 0
    3683     .17       0  4274.8     .15       0  4964.5     .09       0
  5016.1     .15       0    5438     .17       0
Bank Sta=4964.5,5016.1
XS Rating Curve= 0 ,0
Exp/Cntr=0.3,0.1

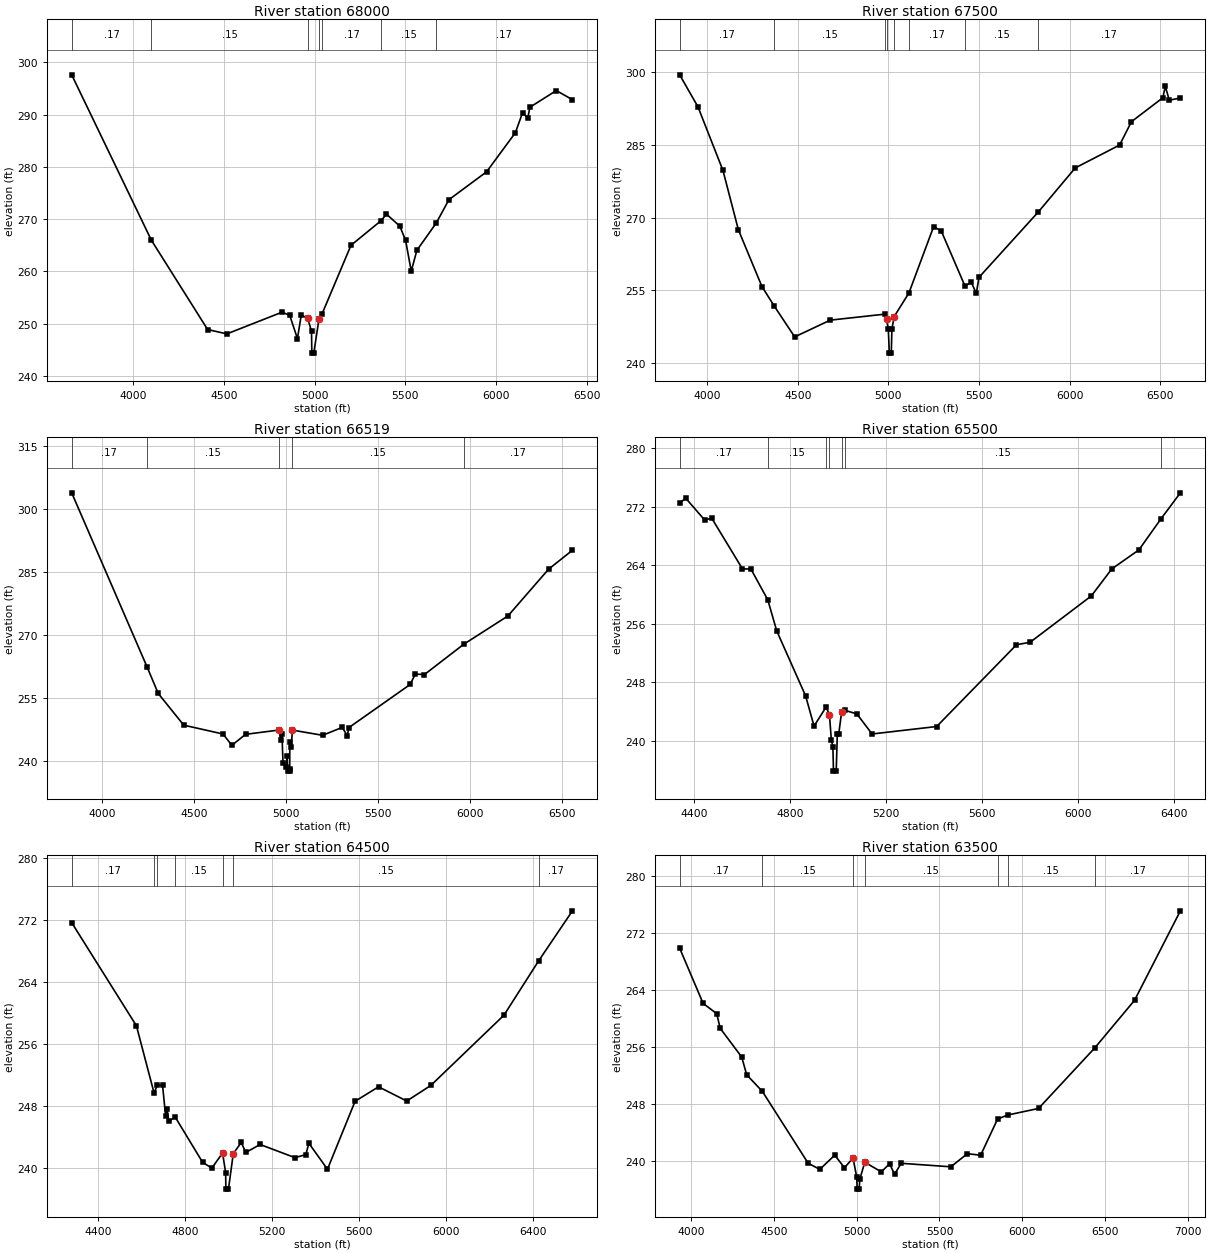
Type RM Length L Ch R = 1 ,68000   ,500,500,500
BEGIN DESCRIPTION:
LITTLE LAKE CREEK 129.0
END DESCRIPTION:
XS GIS Cut Line= 3
      3747717.88      10170811.1      3746760.94     10169873.79
      3745391.89     10169490.83
#Sta/Elev= 30
  3660.5  297.59  4099.5  265.98  4410.1  248.88  4516.1  248.05  4820.3   252.2
  4862.7   251.6  4905.2  247.14  4926.3  251.65  4961.7  251.02  4982.9  248.54
  4984.6  244.37  4995.4  244.37  5023.7  250.82  5040.5  251.83  5200.5  264.99
  5365.8  269.68  5396.2  270.95  5469.7  268.65  5501.6  265.94  5532.8  260.05
  5563.9  264.03  5670.6  269.25  5740.5  273.71  5948.1  279.04  6107.1  286.53
  6146.5  290.34  6175.4  289.31    6187  291.39  6332.7  294.58  6421.6  292.84
#Mann= 7 ,-1 , 0
  3660.5     .17       0  4099.5     .15       0  4961.7     .09       0
  5023.7     .15       0  5040.5     .17       0  5365.8     .15       0
  5670.6     .17       0
Bank Sta=4961.7,5023.7
XS Rating Curve= 0 ,0
Exp/Cntr=0.3,0.1

Type RM Length L Ch R = 1 ,67500   ,981,981,981
BEGIN DESCRIPTION:
LITTLE LAKE CREEK 128.0
END DESCRIPTION:
XS GIS Cut Line= 3
      3748017.82     10170111.05      3747054.48     10169480.59
      3745729.51      10168563.5
#Sta/Elev= 30
  3848.7  299.48  3949.7  292.88  4087.7  279.73  4172.8  267.48  4302.8  255.76
  4370.4  251.75  4483.4  245.37  4679.4  248.83    4984  250.08    4990  249.09
    5000  246.95  5005.6  242.02  5016.4  242.02  5019.8     247  5032.4  249.57
  5113.8  254.45  5249.6   268.1  5291.5   267.3  5422.8  255.88    5458  256.63
  5485.4  254.35  5500.3  257.67  5827.6  271.17  6031.4  280.26    6276  284.98
  6341.5  289.81  6514.5  294.74  6528.3  297.09  6550.3  294.24  6611.4   294.7
#Mann= 8 ,-1 , 0
  3848.7     .17       0  4370.4     .15       0    4984     .12       0
    4990     .09       0  5032.4     .15       0  5113.8     .17       0
  5422.8     .15       0  5827.6     .17       0
Bank Sta=4990,5032.4
XS Rating Curve= 0 ,0
Exp/Cntr=0.3,0.1

Type RM Length L Ch R = 1 ,66519   ,1019,1019,1019
BEGIN DESCRIPTION:
LITTLE LAKE CREEK 126.0
END DESCRIPTION:
XS GIS Cut Line= 3
      3748182.61     10169948.92      3747591.28     10168947.36
      3746412.31     10167933.74
#Sta/Elev= 30
  3836.9  303.75  4245.3  262.38  4306.6  255.99  4445.1  248.45  4657.8  246.35
  4706.5  243.66  4780.7  246.27  4962.1  247.29  4971.9  245.02  4977.8  246.42
  4984.1  239.36  4998.5   238.6  5006.5  241.01  5008.8  237.51  5019.6  237.51
  5020.1  238.01  5020.8  244.36  5028.5  243.31  5035.1  247.27  5198.6  246.04
    5305  247.91  5333.5  245.92  5340.1  247.83  5673.7  258.13  5702.2  260.61
  5751.6   260.5  5964.3  267.69  6204.8  274.45  6425.4  285.58  6554.8  290.08
#Mann= 5 ,-1 , 0
  3836.9     .17       0  4245.3     .15       0  4962.1     .09       0
  5035.1     .15       0  5964.3     .17       0
Bank Sta=4962.1,5035.1
XS Rating Curve= 0 ,0
Exp/Cntr=0.3,0.1

Type RM Length L Ch R = 1 ,65500   ,1000,1000,1000
BEGIN DESCRIPTION:
LITTLE LAKE CREEK 124.0
END DESCRIPTION:
XS GIS Cut Line= 3
      3748666.94     10168709.28      3748149.38     10168301.18
      3747089.61     10167345.41
#Sta/Elev= 30
  4340.9  272.55  4366.9  273.15  4445.5  270.18  4474.4  270.45  4602.6  263.51
  4637.9  263.49  4708.1  259.28  4745.4  255.03  4865.6  246.16  4900.8  242.02
    4951  244.61    4965   243.6    4973  240.05  4979.4   239.2  4981.8  235.86
  4993.2  235.86  4997.8  240.94  5003.8  240.94  5015.5  243.91  5029.1  244.18
  5079.2  243.68  5142.7  240.94  5411.8  241.96  5744.3  253.14  5801.1  253.48
    6056  259.81  6141.2   263.5  6254.4  266.11  6345.9  270.34  6427.1  273.91
#Mann= 7 ,-1 , 0
  4340.9     .17       0  4708.1     .15       0    4951     .12       0
    4965     .09       0  5015.5     .12       0  5029.1     .15       0
  6345.9     .17       0
Bank Sta=4965,5015.5
XS Rating Curve= 0 ,0
Exp/Cntr=0.3,0.1

Type RM Length L Ch R = 1 ,64500   ,1000,1000,1000
BEGIN DESCRIPTION:
LITTLE LAKE CREEK 122.0
END DESCRIPTION:
XS GIS Cut Line= 4
      3749151.35     10168297.86      3748653.14      10167777.1
      3748553.08     10167695.74      3747193.05     10167188.49
#Sta/Elev= 30
  4279.3  271.69  4576.7  258.36  4657.8  249.67  4672.2  250.66  4696.8  250.65
  4710.9  246.72  4717.9  247.58  4725.1  245.99  4754.6  246.57  4880.8  240.71
  4923.2  239.95  4972.6  241.91  4986.8  239.36  4987.8  237.24  4999.7  237.24
  5021.8  241.82  5058.4  243.27  5079.3  241.98  5145.2  243.01  5305.3  241.31
  5355.1   241.7  5369.3  243.17  5454.7  239.81  5581.7   248.6  5689.5  250.47
  5818.9  248.63  5929.5  250.64  6265.9  259.73  6424.9  266.74  6580.5  273.22
#Mann= 7 ,-1 , 0
  4279.3     .17       0  4657.8     .15       0  4672.2     .17       0
  4754.6     .15       0  4972.6     .09       0  5021.8     .15       0
  6424.9     .17       0
Bank Sta=4972.6,5021.8
XS Rating Curve= 0 ,0
Exp/Cntr=0.3,0.1

Type RM Length L Ch R = 1 ,63500   ,500,500,500
BEGIN DESCRIPTION:
LITTLE LAKE CREEK 120.0
END DESCRIPTION:
XS GIS Cut Line= 3
      3749276.35     10168214.55      3749176.25     10167148.54
      3747220.98     10167079.17
#Sta/Elev= 30
  3929.3  269.88    4071  262.14  4153.8  260.69  4173.9  258.66  4304.4  254.62
  4334.6  252.13  4429.3   249.8  4706.2  239.73  4776.5  238.87  4866.9  240.86
  4925.8  239.09  4977.4  240.47    5000  237.77  5002.4   236.1  5014.4   236.1
  5018.4  237.47  5048.4  239.87  5148.5  238.52  5198.5  239.66  5228.5  238.18
  5268.6  239.72  5568.8  239.23  5668.8  241.07  5748.9  240.85  5851.3  245.92
  5911.4  246.48  6099.1  247.41  6439.2   255.9  6679.5  262.57  6956.5  275.11
#Mann= 7 ,-1 , 0
  3929.3     .17       0  4429.3     .15       0  4977.4     .09       0
  5048.4     .15       0  5851.3     .17       0  5911.4     .15       0
  6439.2     .17       0
Bank Sta=4977.4,5048.4
XS Rating Curve= 0 ,0
Exp/Cntr=0.3,0.1

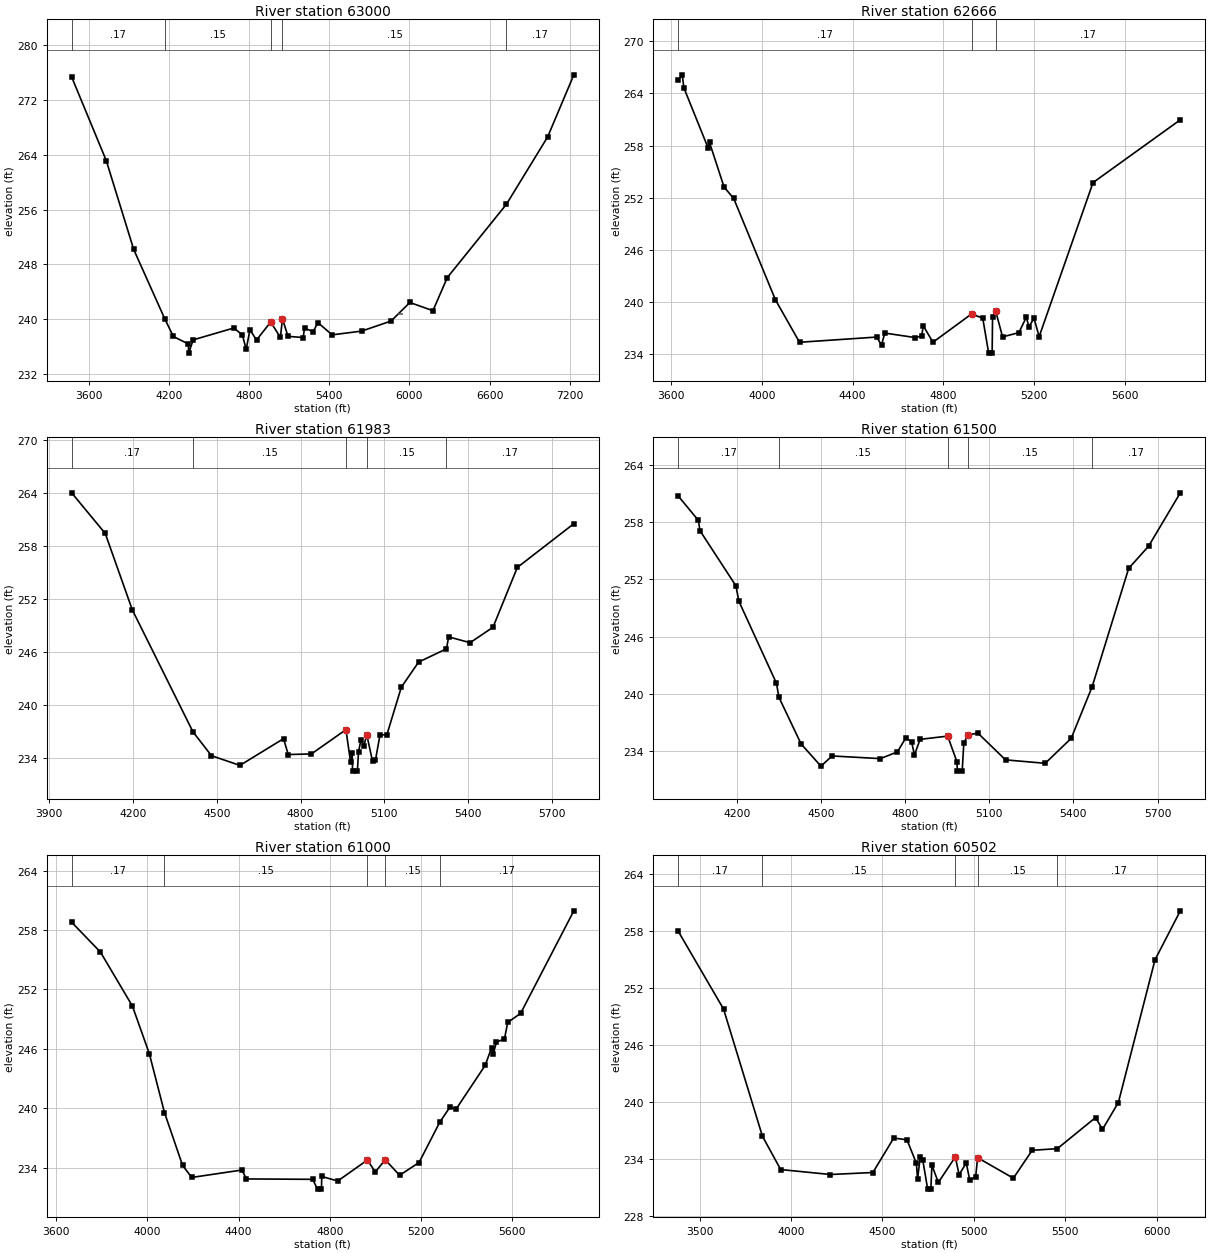
Type RM Length L Ch R = 1 ,63000   ,334,334,334
BEGIN DESCRIPTION:
LITTLE LAKE CREEK 119.0
END DESCRIPTION:
XS GIS Cut Line= 4
      3750491.32     10167913.93      3749455.56     10166787.96
      3749012.14      10166900.9      3747242.05     10167012.83
#Sta/Elev= 30
  3470.1  275.39  3729.5  263.16  3934.8  250.19  4166.6  240.09    4232  237.47
  4344.8  236.37  4346.2  235.04  4380.6  236.98  4684.5  238.71  4748.6  237.71
    4777  235.59  4805.4  238.44  4854.7  236.96  4960.7  239.58  5033.3  237.35
  5049.2  240.04  5090.5  237.49    5204  237.32  5214.3   238.7  5278.7  238.16
  5314.4   239.5  5420.7  237.71  5642.2  238.26  5862.7  239.73    6003  242.44
  6175.9  241.24  6283.5  246.08  6726.7   256.8    7035  266.63  7231.2   275.7
#Mann= 5 ,-1 , 0
  3470.1     .17       0  4166.6     .15       0  4960.7     .09       0
  5049.2     .15       0  6726.7     .17       0
#XS Ineff= 2 ,-1
  5912.8  5952.9  240.77    6003  6223.4  242.44
Permanent Ineff=
       F       F
Bank Sta=4960.7,5049.2
XS Rating Curve= 0 ,0
Exp/Cntr=0.3,0.1

Type RM Length L Ch R = 1 ,62666   ,683,683,683
BEGIN DESCRIPTION:
LITTLE LAKE CREEK 118.0
END DESCRIPTION:
XS GIS Cut Line= 3
      3750613.67     10167670.84      3749683.67     10166666.89
      3750075.49     10165920.82
#Sta/Elev= 30
  3631.5  265.52  3649.5  266.15  3656.9  264.65  3762.9  257.77  3769.7  258.36
  3833.8  253.23  3876.3  251.91    4060  240.24    4166  235.35  4505.6  235.95
  4527.2  235.03  4541.3  236.41  4675.7  235.89  4704.1  236.07  4710.9  237.26
  4753.4  235.35  4923.5  238.61  4972.8  238.13  4998.9   234.1  5014.2   234.1
    5016  238.21  5029.2     239  5060.1  235.97  5131.9  236.46  5164.7  238.24
    5176  237.13  5198.6  238.12  5221.2     236  5458.4  253.74  5842.7  260.97
#Mann= 3 , 0 , 0
  3631.5     .17       0  4923.5     .09       0  5029.2     .17       0
Bank Sta=4923.5,5029.2
XS Rating Curve= 0 ,0
Exp/Cntr=0.3,0.1

Type RM Length L Ch R = 1 ,61983   ,483,483,483
BEGIN DESCRIPTION:
LITTLE LAKE CREEK 117.0
END DESCRIPTION:
XS GIS Cut Line= 3
      3750751.09     10167578.71      3750293.82     10166667.17
      3750102.63       10165912.
#Sta/Elev= 30
  3980.2  264.01  4100.6   259.4  4197.5  250.74  4414.6  236.92    4481  234.21
  4582.9  233.11  4739.2  236.14    4756  234.34    4839  234.41  4962.6  237.16
  4979.4  233.46    4985   234.5  4986.4  232.46  5003.6  232.46  5007.7  234.65
  5016.6  236.03  5026.9  235.32  5037.2   236.6  5057.9  233.58  5068.2  233.67
  5084.6  236.56  5109.4  236.59    5161  241.97  5222.9  244.82  5322.8  246.33
  5330.6  247.68  5407.4  247.02  5489.4  248.77  5576.6  255.55    5779  260.51
#Mann= 5 ,-1 , 0
  3980.2     .17       0  4414.6     .15       0  4962.6     .09       0
  5037.2     .15       0  5322.8     .17       0
Bank Sta=4962.6,5037.2
XS Rating Curve= 0 ,0
Exp/Cntr=0.3,0.1

Type RM Length L Ch R = 1 ,61500   ,500,500,500
BEGIN DESCRIPTION:
LITTLE LAKE CREEK 116.0
END DESCRIPTION:
XS GIS Cut Line= 3
      3750823.88     10167455.07      3750676.06     10166455.74
       3750159.7      10165869.4
#Sta/Elev= 30
  3989.8  260.74  4062.4  258.16  4067.4  257.11    4196  251.31  4206.5   249.7
  4340.6   241.1  4349.4  239.63  4428.5  234.74  4499.3  232.41  4539.1  233.48
  4711.6   233.2  4772.2  233.91  4802.5   235.4  4822.8  234.94  4832.9  233.59
  4853.1  235.22  4951.4  235.56  4984.5  232.87    4986  231.89  5003.2  231.89
  5008.9   234.8  5023.1  235.67  5059.1  235.88  5157.8  233.07  5299.4  232.71
  5392.1  235.33  5466.6  240.72  5597.1  253.14  5668.2  255.47  5781.3  261.06
#Mann= 5 ,-1 , 0
  3989.8     .17       0  4349.4     .15       0  4951.4     .09       0
  5023.1     .15       0  5466.6     .17       0
Bank Sta=4951.4,5023.1
XS Rating Curve= 0 ,0
Exp/Cntr=0.3,0.1

Type RM Length L Ch R = 1 ,61000   ,498,498,498
BEGIN DESCRIPTION:
LITTLE LAKE CREEK 115.0
END DESCRIPTION:
XS GIS Cut Line= 3
      3750925.44     10167447.28      3750993.71     10166116.43
      3750352.89     10165526.08
#Sta/Elev= 30
  3667.4  258.79  3793.8  255.77    3934  250.32  4008.1  245.52  4074.7  239.56
  4154.2  234.22  4194.3     233  4414.6  233.75  4434.6  232.85    4725  232.81
  4746.4  231.82  4763.7  231.82    4765   233.1  4835.1  232.64  4965.3  234.76
    5000  233.55  5043.4  234.79  5106.9  233.22    5192  234.51  5282.4  238.56
  5326.4  240.07  5354.7  239.91  5482.3  244.33  5510.7  246.13  5517.5  245.48
  5531.6  246.68  5566.8  246.99    5581  248.66  5637.7  249.58  5871.3  259.94
#Mann= 5 ,-1 , 0
  3667.4     .17       0  4074.7     .15       0  4965.3     .09       0
  5043.4     .15       0  5282.4     .17       0
Bank Sta=4965.3,5043.4
XS Rating Curve= 0 ,0
Exp/Cntr=0.3,0.1

Type RM Length L Ch R = 1 ,60502   ,502,502,502
BEGIN DESCRIPTION:
LITTLE LAKE CREEK 114.0
END DESCRIPTION:
XS GIS Cut Line= 5
      3751004.66     10167457.39      3751178.26     10166176.15
       3751400.7     10165999.29      3751406.53     10165958.53
      3750417.88     10165411.09
#Sta/Elev= 30
  3381.7  257.98  3630.3  249.77  3843.1  236.38  3943.1  232.87  4215.6  232.35
  4447.7  232.56  4561.8  236.19  4634.3     236  4685.7  233.53  4692.1  231.85
  4706.5  234.16  4720.9  233.85  4747.4  230.81  4764.9  230.81  4770.6  233.33
  4805.8  231.51  4898.7   234.2  4919.5  232.34  4958.8  233.56  4978.1  231.72
  5010.4  232.13  5020.7  234.12  5216.4  231.96  5319.5   234.9  5457.2  235.07
  5666.4  238.35  5704.2   237.1  5791.2  239.93  5991.6  254.95  6130.1  260.11
#Mann= 5 ,-1 , 0
  3381.7     .17       0  3843.1     .15       0  4898.7     .09       0
  5020.7     .15       0  5457.2     .17       0
Bank Sta=4898.7,5020.7
XS Rating Curve= 0 ,0
Exp/Cntr=0.3,0.1