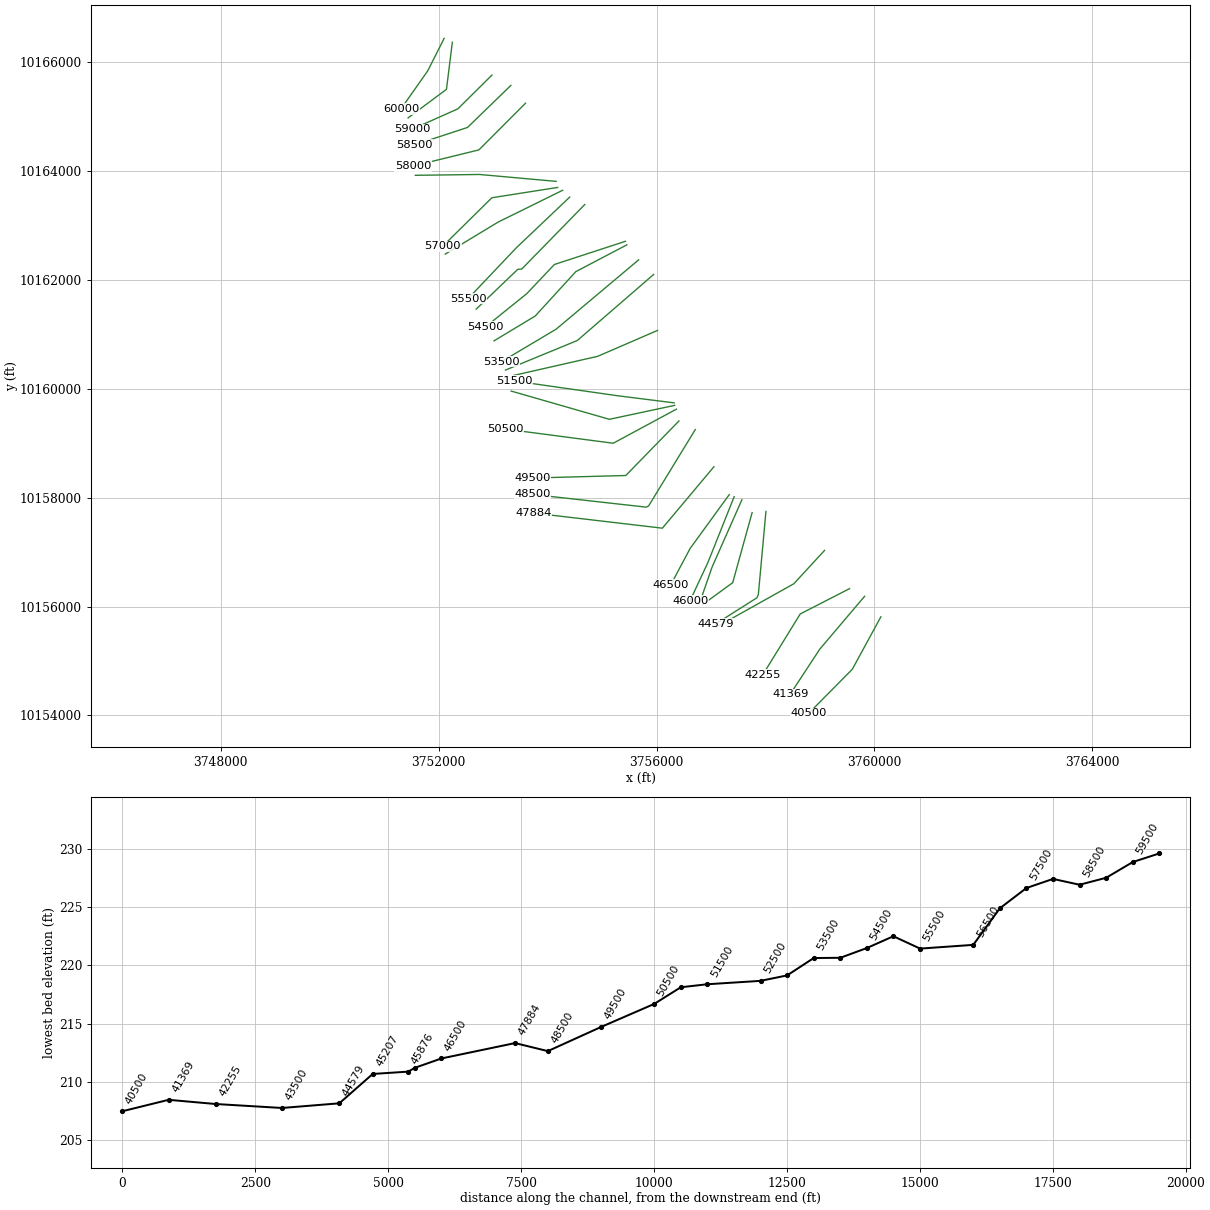
HEC-RAS study LITTLE LAKE CREEK.prj: LITTLE LAKE CREEK Base Level Engineering

--- LITTLE LAKE CREEK.g01 (geometry) --- (continued)

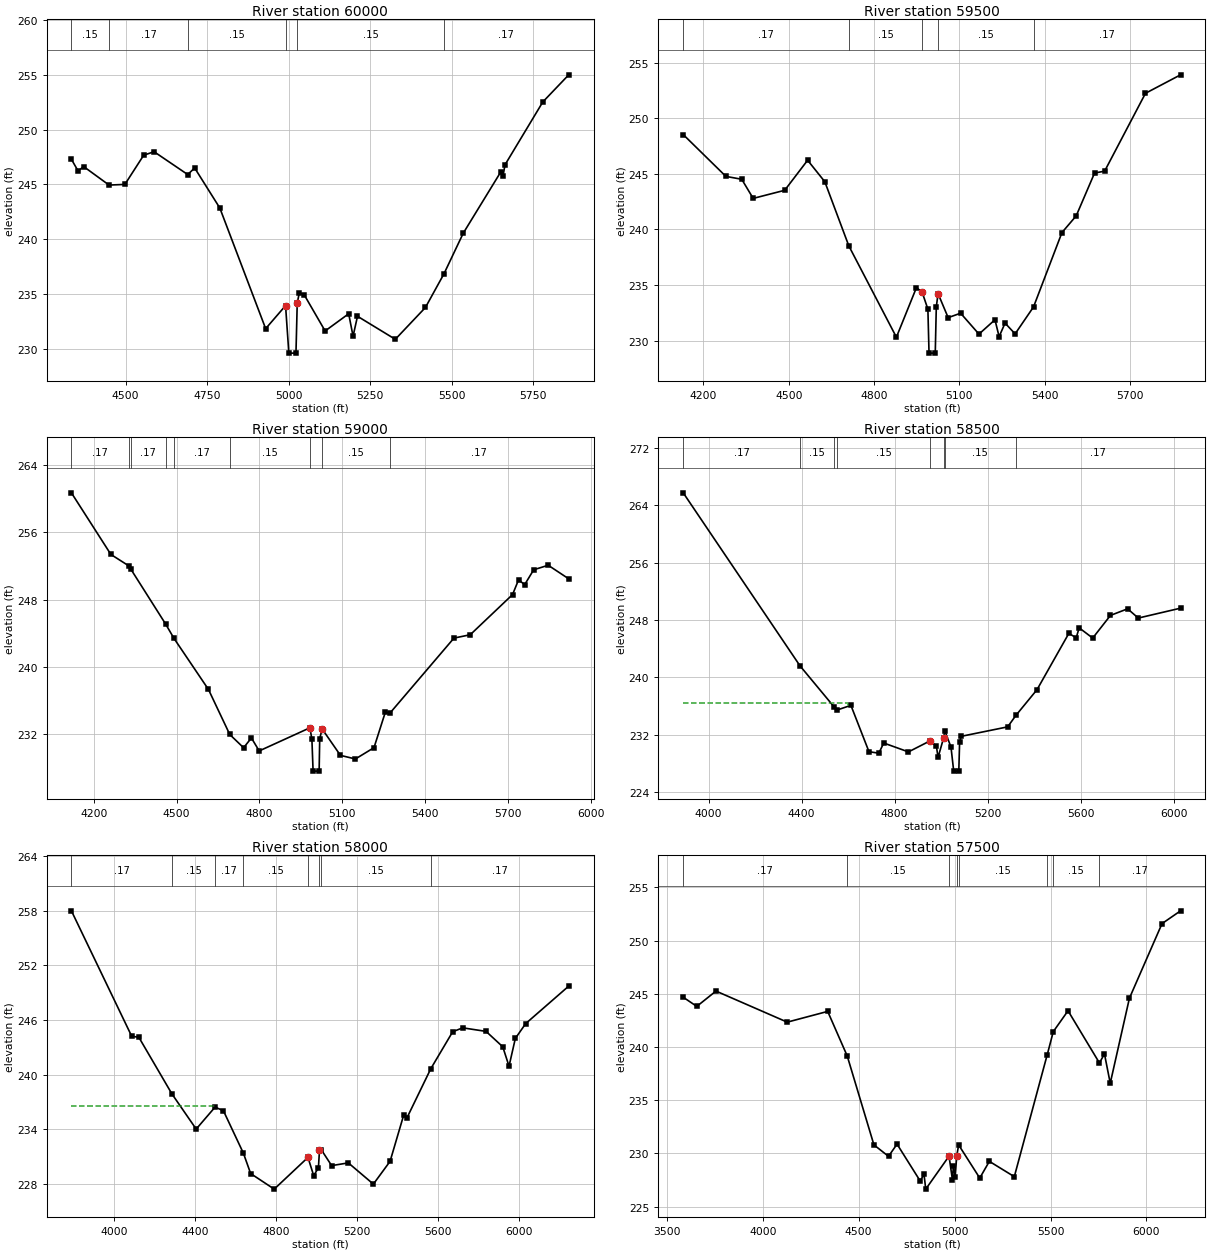
Type RM Length L Ch R = 1 ,60000   ,500,500,500
BEGIN DESCRIPTION:
LITTLE LAKE CREEK 113.0
END DESCRIPTION:
XS GIS Cut Line= 3
      3752100.61      10166437.5      3751801.46     10165842.58
      3751307.82      10165140.2
#Sta/Elev= 30
  4334.1  247.29  4354.7  246.22  4371.5  246.63  4449.5  244.94    4498     245
  4555.6  247.66  4587.5  247.98  4690.6   245.9  4711.9   246.5    4789  242.85
  4929.5  231.85  4990.5  233.95  5000.6  229.62  5022.4  229.62  5026.3  234.19
  5032.4  235.07  5047.2  234.96  5111.8  231.64    5184  233.21  5197.4  231.16
    5211  232.98  5326.9  230.88  5419.2  233.78  5475.9  236.84  5535.1  240.55
  5649.6  246.11  5657.1  245.78  5663.2  246.79  5779.1  252.52  5858.5  254.99
#Mann= 6 ,-1 , 0
  4334.1     .15       0  4449.5     .17       0  4690.6     .15       0
  4990.5     .09       0  5026.3     .15       0  5475.9     .17       0
Bank Sta=4990.5,5026.3
XS Rating Curve= 0 ,0
Exp/Cntr=0.3,0.1

Type RM Length L Ch R = 1 ,59500   ,500,500,500
BEGIN DESCRIPTION:
LITTLE LAKE CREEK 112.0
END DESCRIPTION:
XS GIS Cut Line= 3
      3752251.31     10166365.44      3752143.86     10165500.89
      3751438.86      10164976.4
#Sta/Elev= 30
  4128.8  248.53  4278.9  244.77  4334.7  244.51    4375  242.79  4485.9  243.52
  4566.5  246.22    4627  244.29  4711.5  238.52  4878.9  230.31  4949.4  234.77
  4969.6  234.35  4989.7  232.83  4993.7  228.88  5015.6  228.88  5019.3  233.04
  5025.5  234.23    5061  232.07  5104.8  232.47  5169.4  230.59  5225.7  231.88
  5240.3  230.36  5261.2  231.58  5296.6  230.61  5361.5  233.04  5461.4  239.72
  5511.5  241.22  5576.1  245.07  5611.6  245.24  5755.3  252.24  5878.7   253.9
#Mann= 5 ,-1 , 0
  4128.8     .17       0  4711.5     .15       0  4969.6     .09       0
  5025.5     .15       0  5361.5     .17       0
Bank Sta=4969.6,5025.5
XS Rating Curve= 0 ,0
Exp/Cntr=0.3,0.1

Type RM Length L Ch R = 1 ,59000   ,500,500,500
BEGIN DESCRIPTION:
LITTLE LAKE CREEK 111.0
END DESCRIPTION:
XS GIS Cut Line= 3
      3752978.58     10165762.64      3752352.99     10165142.32
      3751511.87     10164767.15
#Sta/Elev= 30
    4119  260.73    4262  253.38  4326.3  252.03    4335  251.59  4460.1  245.09
  4490.8  243.36  4615.6  237.27  4692.8   231.9  4742.9  230.32  4771.2  231.49
  4799.4  229.94  4983.3   232.7  4990.4  231.31  4994.7  227.53  5016.6  227.53
  5018.7   231.4  5027.5  232.56  5093.8  229.41    5148  228.98  5215.4  230.33
  5256.4  234.56  5272.9  234.44  5505.1   243.4  5564.1   243.8  5717.4  248.59
  5739.3  250.36  5761.2  249.77    5794  251.55  5846.6  252.09    5921  250.47
#Mann= 9 ,-1 , 0
    4119     .17       0  4326.3     .15       0    4335     .17       0
  4460.1     .15       0  4490.8     .17       0  4692.8     .15       0
  4983.3     .09       0  5027.5     .15       0  5272.9     .17       0
Bank Sta=4983.3,5027.5
XS Rating Curve= 0 ,0
Exp/Cntr=0.3,0.1

Type RM Length L Ch R = 1 ,58500   ,500,500,500
BEGIN DESCRIPTION:
LITTLE LAKE CREEK 110.0
END DESCRIPTION:
XS GIS Cut Line= 3
       3753325.8      10165572.6      3752529.83     10164800.53
      3751551.56     10164478.87
#Sta/Elev= 30
  3891.1  265.73  4393.5   241.6  4540.5  235.86  4552.8  235.45  4612.2   236.1
  4689.9  229.64  4732.3  229.43  4753.4  230.85  4859.6  229.61  4951.5  231.13
  4979.8  230.43    4987  228.84  5010.8  231.55  5016.1  232.55  5042.6  230.28
  5054.3  226.93  5076.2  226.93  5079.7  230.98  5086.3  231.78  5286.3   233.1
  5321.8   234.7  5412.6  238.29  5549.5  246.14  5581.1  245.51  5593.7  246.91
    5652  245.48  5728.4  248.64  5802.1  249.56  5848.1  248.27  6029.8  249.65
#Mann= 8 ,-1 , 0
  3891.1     .17       0  4393.5     .15       0  4540.5     .17       0
  4552.8     .15       0  4951.5     .09       0  5010.8     .12       0
  5016.1     .15       0  5321.8     .17       0
#XS Ineff= 2 , 0
       0    4598  236.46               0
Permanent Ineff=
       F       F
Bank Sta=4951.5,5010.8
XS Rating Curve= 0 ,0
Exp/Cntr=0.3,0.1

Type RM Length L Ch R = 1 ,58000   ,500,500,500
BEGIN DESCRIPTION:
LITTLE LAKE CREEK 109.0
END DESCRIPTION:
XS GIS Cut Line= 3
      3753594.48     10165245.04      3752739.03     10164388.44
      3751531.75     10164092.16
#Sta/Elev= 30
  3789.4  257.97  4086.8  244.21  4122.2  244.09    4285  237.89    4405  234.02
  4498.2  236.43  4539.4  236.03    4638  231.37  4673.7  229.14    4790  227.43
  4956.5  230.91  4984.8  228.91  5008.1  229.77  5013.3  231.68  5021.8  231.77
  5073.3  230.01  5155.7  230.31  5279.2  227.98  5361.6  230.48    5429  235.57
    5444  235.21  5562.2  240.63  5670.5   244.7    5720  245.13  5835.2  244.74
  5917.6  243.05  5948.5  240.92  5979.7  243.97  6030.9   245.6  6243.1  249.71
#Mann= 8 ,-1 , 0
  3789.4     .17       0    4285     .15       0  4498.2     .17       0
    4638     .15       0  4956.5     .09       0  5013.3     .12       0
  5021.8     .15       0  5562.2     .17       0
#XS Ineff= 2 , 0
       0  4496.9   236.5    5429       0  235.57
Permanent Ineff=
       F       F
Bank Sta=4956.5,5013.3
XS Rating Curve= 0 ,0
Exp/Cntr=0.3,0.1

Type RM Length L Ch R = 1 ,57500   ,500,500,500
BEGIN DESCRIPTION:
LITTLE LAKE CREEK 108.0
END DESCRIPTION:
XS GIS Cut Line= 3
      3754157.89     10163810.14      3752749.08     10163936.87
      3751571.38     10163921.54
#Sta/Elev= 30
  3585.5  244.68  3656.3  243.82  3756.2  245.26  4127.7  242.34  4338.6  243.35
  4440.4  239.16  4579.5  230.81  4655.6  229.73    4700  230.88  4820.5  227.42
  4840.6  228.04  4849.7  226.65  4971.1  229.75  4988.6  227.55  4993.7  228.82
  5003.1  227.83  5011.2  229.78  5021.2   230.8  5131.2  227.69  5181.2  229.26
  5311.3  227.82    5483  239.29  5514.5  241.45  5591.3  243.41  5754.8  238.51
  5781.3  239.35  5811.3   236.6  5911.3  244.59  6081.3   251.6  6177.8   252.8
#Mann= 8 ,-1 , 0
  3585.5     .17       0  4440.4     .15       0  4971.1     .09       0
  5011.2     .12       0  5021.2     .15       0    5483     .17       0
  5514.5     .15       0  5754.8     .17       0
Bank Sta=4971.1,5011.2
XS Rating Curve= 0 ,0
Exp/Cntr=0.3,0.1

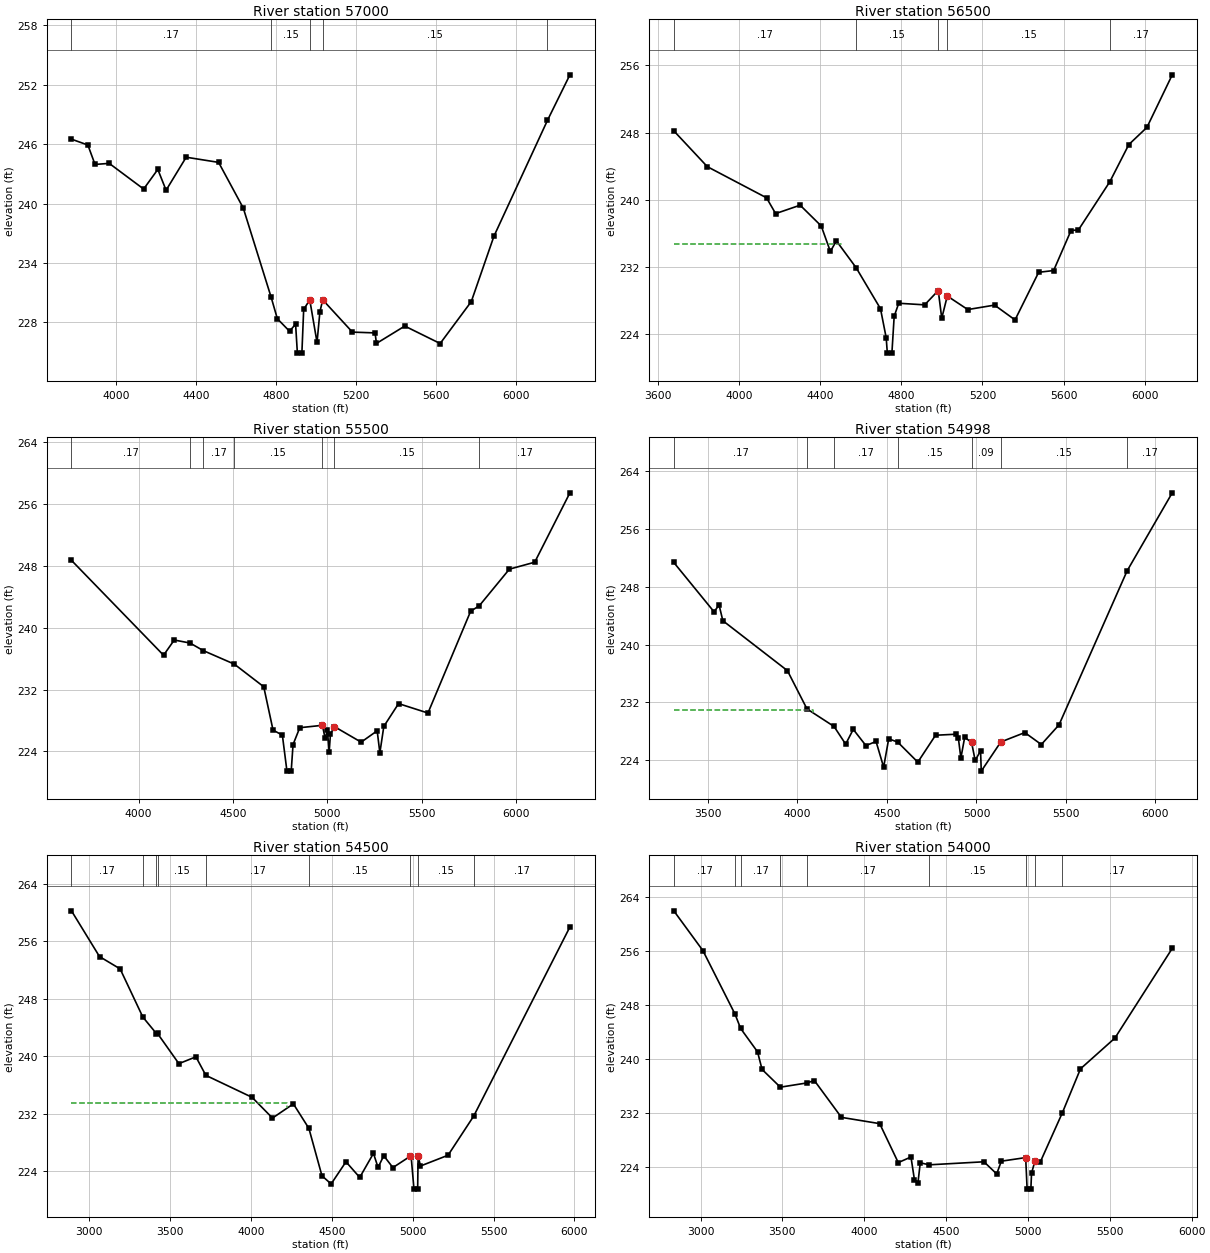
Type RM Length L Ch R = 1 ,57000   ,500,500,500
BEGIN DESCRIPTION:
LITTLE LAKE CREEK 107.0
END DESCRIPTION:
XS GIS Cut Line= 3
      3754184.14     10163698.75      3752977.24     10163509.21
      3752074.43      10162617.7
#Sta/Elev= 30
  3778.3  246.49  3860.3   245.9    3896  243.94  3966.9  244.05    4139  241.46
  4209.8  243.44  4251.1  241.34  4351.5  244.67  4513.5  244.15  4636.8  239.54
    4776  230.55    4807  228.38  4867.8  227.12  4898.2  227.83  4907.1  224.91
  4929.6  224.91  4938.6  229.32    4969  230.28  5005.3  225.99  5019.5  229.05
  5033.6  230.29  5182.1  227.03  5295.2  226.95  5302.3  225.89  5443.7  227.64
  5620.5  225.88  5776.1  230.11  5889.2   236.7  6156.5  248.38  6268.8  252.98
#Mann= 5 ,-1 , 0
  3778.3     .17       0    4776     .15       0    4969     .09       0
  5033.6     .15       0  6156.5     .17       0
Bank Sta=4969,5033.6
XS Rating Curve= 0 ,0
Exp/Cntr=0.3,0.1

Type RM Length L Ch R = 1 ,56500   ,1000,1000,1000
BEGIN DESCRIPTION:
LITTLE LAKE CREEK 106.0
END DESCRIPTION:
XS GIS Cut Line= 3
      3754275.89     10163646.34      3753092.09     10163062.37
      3752121.55      10162474.3
#Sta/Elev= 30
    3680   248.2  3845.1  243.94  4136.6  240.24  4181.5  238.36  4302.2  239.36
  4406.1  236.89    4451  233.86  4480.7  235.12  4578.1  231.92  4697.9  227.05
    4726   223.6  4731.6  221.77  4754.1  221.77  4765.3  226.14  4787.7   227.7
  4915.5  227.51  4982.4  229.21  4999.6  225.92    5027  228.56  5127.8  226.95
  5259.7  227.48  5360.5  225.72  5476.9  231.38  5550.6  231.59  5636.3  236.35
  5672.8  236.42  5827.9  242.17    5921  246.57  6010.1  248.61  6134.8  254.86
#Mann= 5 ,-1 , 0
    3680     .17       0  4578.1     .15       0  4982.4     .09       0
    5027     .15       0  5827.9     .17       0
#XS Ineff= 2 , 0
       0    4503   234.7               0
Permanent Ineff=
       F       F
Bank Sta=4982.4,5027
XS Rating Curve= 0 ,0
Exp/Cntr=0.3,0.1

Type RM Length L Ch R = 1 ,55500   ,502,502,502
BEGIN DESCRIPTION:
LITTLE LAKE CREEK 104.0
END DESCRIPTION:
XS GIS Cut Line= 3
      3754406.88     10163521.82      3753423.98     10162587.96
      3752540.32      10161655.3
#Sta/Elev= 30
  3644.2  248.73  4132.1  236.45  4188.7  238.42  4272.3  238.03  4342.4  237.05
  4506.8   235.3  4662.8  232.37  4712.1  226.76  4761.5  226.11  4785.8  221.45
  4808.3  221.45  4818.1  224.89  4853.7  227.07  4973.8  227.38    4988  225.68
    5000  226.72  5009.4  223.93  5016.3  226.25  5037.3  227.21  5178.9   225.2
  5263.8  226.67    5278  223.81    5299  227.24  5377.1  230.19  5532.8  228.97
    5759  242.15  5804.3  242.84  5964.1  247.59  6098.4  248.49  6284.8  257.47
#Mann= 7 ,-1 , 0
  3644.2     .17       0  4272.3     .15       0  4342.4     .17       0
  4506.8     .15       0  4973.8     .09       0  5037.3     .15       0
  5804.3     .17       0
Bank Sta=4973.8,5037.3
XS Rating Curve= 0 ,0
Exp/Cntr=0.3,0.1

Type RM Length L Ch R = 1 ,54998   ,498,498,498
BEGIN DESCRIPTION:
LITTLE LAKE CREEK 103.0
END DESCRIPTION:
XS GIS Cut Line= 4
      3754682.13     10163384.29      3753525.53     10162199.57
      3753452.61     10162194.36      3752690.26     10161464.49
#Sta/Elev= 30
  3309.5  251.35  3534.1  244.54  3562.4  245.46  3583.5   243.3  3944.1   236.4
  4053.4  231.11  4204.7  228.68  4269.4  226.24  4311.9  228.28  4382.6  226.04
  4439.2  226.61  4481.6  223.06  4509.9  226.98  4560.4  226.52  4672.5  223.75
  4771.5  227.47  4884.7  227.61  4898.8  227.12    4913  224.31  4934.3  227.19
  4972.9  226.47  4992.9  223.98    5023  225.32  5026.9  222.51    5136  226.54
  5270.2  227.84  5362.4  226.19  5461.1   228.9  5841.5  250.19  6093.7  260.98
#Mann= 7 ,-1 , 0
  3309.5     .17       0  4053.4     .15       0  4204.7     .17       0
  4560.4     .15       0  4972.9     .09       0    5136     .15       0
  5841.5     .17       0
#XS Ineff= 2 , 0
       0  4085.6  230.95               0
Permanent Ineff=
       F       F
Bank Sta=4972.9,5136
XS Rating Curve= 0 ,0
Exp/Cntr=0.3,0.1

Type RM Length L Ch R = 1 ,54500   ,500,500,500
BEGIN DESCRIPTION:
LITTLE LAKE CREEK 102.0
END DESCRIPTION:
XS GIS Cut Line= 4
      3755429.02      10162709.4      3754125.18     10162283.52
       3753617.9     10161748.11      3752861.76     10161137.82
#Sta/Elev= 30
  2890.8  260.27  3064.1   253.9  3191.6  252.18    3332  245.47    3416  243.17
  3422.6  243.19  3554.8  238.98    3660  239.93  3721.5  237.35  4007.1  234.29
  4133.4   231.4  4262.4  233.38  4358.4  229.96  4439.1  223.36  4495.8  222.22
  4587.6  225.31  4672.6  223.13  4757.5  226.48  4785.8  224.52    4821  226.15
  4877.7   224.5  4983.6  226.06  4990.9  225.93  5007.8   221.5  5030.6   221.5
  5033.6  226.15    5048  224.72  5218.5  226.22  5377.7   231.7  5971.7  258.02
#Mann= 9 ,-1 , 0
  2890.8     .17       0    3332     .15       0    3416     .11       0
  3422.6     .15       0  3721.5     .17       0  4358.4     .15       0
  4983.6     .09       0  5033.6     .15       0  5377.7     .17       0
#XS Ineff= 2 , 0
       0  4222.4  233.46               0
Permanent Ineff=
       F       F
Bank Sta=4983.6,5033.6
XS Rating Curve= 0 ,0
Exp/Cntr=0.3,0.1

Type RM Length L Ch R = 1 ,54000   ,500,500,500
BEGIN DESCRIPTION:
LITTLE LAKE CREEK 101.0
END DESCRIPTION:
XS GIS Cut Line= 4
      3755455.25     10162643.89       3754518.3     10162152.48
      3753772.57     10161336.78      3753017.92     10160881.41
#Sta/Elev= 30
  2836.8  261.88  3014.5  255.99  3211.1  246.56  3244.9  244.46  3348.2     241
  3375.9  238.39  3487.6  235.76    3648  236.38  3695.5  236.74  3860.7  231.29
  4094.4  230.36  4207.8  224.59  4285.5  225.42  4306.5  222.07  4328.1  221.61
  4342.3  224.56  4397.1  224.26  4731.4  224.71  4809.1  222.91  4837.5   224.8
  4986.1  225.33    4995  220.66  5017.8  220.66  5021.9  223.01  5043.2  224.86
  5074.3  224.62  5210.2  231.97  5320.9  238.48  5531.1  243.03  5881.4  256.32
#Mann= 9 ,-1 , 0
  2836.8     .17       0  3211.1     .11       0  3244.9     .17       0
  3487.6     .11       0    3648     .17       0  4397.1     .15       0
  4986.1     .09       0  5043.2     .15       0  5210.2     .17       0
Bank Sta=4986.1,5043.2
XS Rating Curve= 0 ,0
Exp/Cntr=0.3,0.1

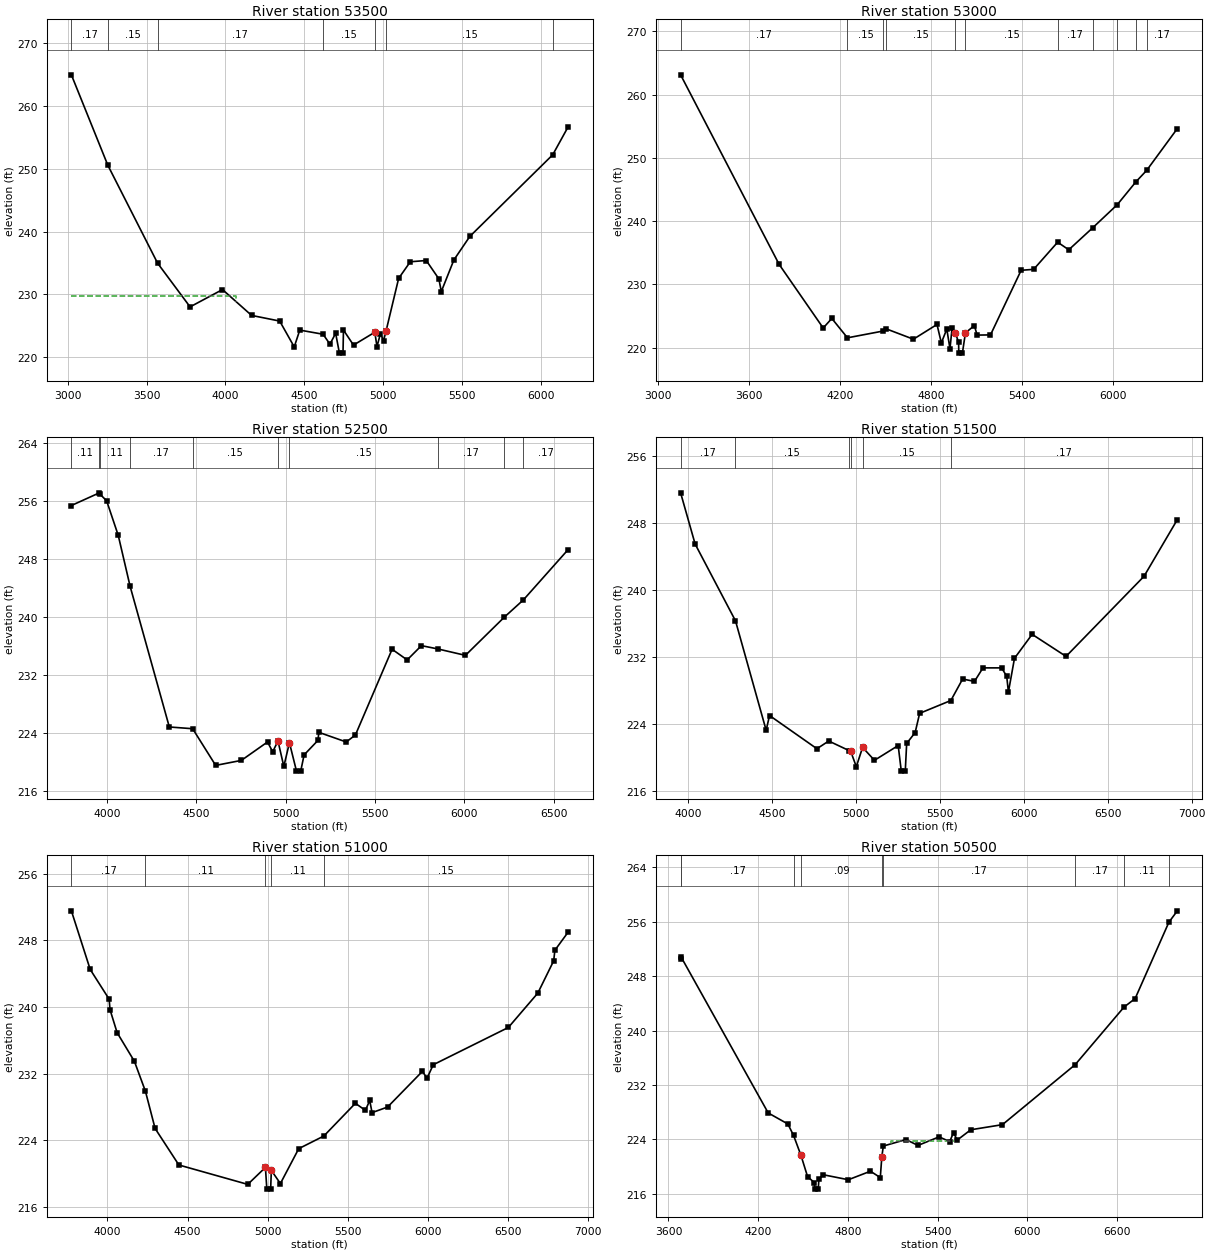
Type RM Length L Ch R = 1 ,53500   ,500,500,500
BEGIN DESCRIPTION:
LITTLE LAKE CREEK 100.0
END DESCRIPTION:
XS GIS Cut Line= 3
      3755671.42     10162368.67      3754158.46      10161096.4
      3753149.94     10160495.43
#Sta/Elev= 30
  3023.2  264.99  3254.4  250.58  3570.2  234.97  3776.1  228.01  3981.7  230.77
  4166.3  226.65  4344.5  225.75  4436.8  221.63  4471.9  224.31  4619.6  223.65
  4663.2  222.07  4699.5   223.8  4723.3  220.64  4746.1  220.64    4749  224.32
  4812.7  221.92  4947.9  223.97  4961.6  221.68  4983.1  223.71  5003.6  222.65
  5019.2  224.17    5099  232.55    5173   235.2  5274.2   235.4    5354  232.48
  5369.6  230.45  5449.4  235.49  5550.6  239.24  6076.4  252.25    6174   256.7
#Mann= 7 ,-1 , 0
  3023.2     .17       0  3254.4     .15       0  3570.2     .17       0
  4619.6     .15       0  4947.9     .09       0  5019.2     .15       0
  6076.4     .17       0
#XS Ineff= 2 , 0
       0  4067.4  229.69               0
Permanent Ineff=
       F       F
Bank Sta=4947.9,5019.2
XS Rating Curve= 0 ,0
Exp/Cntr=0.3,0.1

Type RM Length L Ch R = 1 ,53000   ,500,500,500
BEGIN DESCRIPTION:
LITTLE LAKE CREEK 99.0
END DESCRIPTION:
XS GIS Cut Line= 3
      3755946.64     10162100.07       3754546.4     10160887.49
      3753227.55     10160344.13
#Sta/Elev= 30
  3147.7  263.13  3798.1  233.17  4088.8  223.12  4145.8  224.63    4249  221.57
  4486.5  222.65  4506.6  222.97  4684.3  221.35    4840  223.68  4868.6  220.77
  4904.7  222.95  4925.6  219.85  4939.8  223.15  4960.7  222.37  4982.6  220.85
  4983.9  219.15  5007.5  219.15  5027.7  222.35  5086.4   223.5    5105     222
  5193.1  222.03  5395.3  232.24    5478  232.39  5636.3  236.68  5709.7  235.48
  5866.9  238.94  6029.4   242.6  6153.2  246.23  6223.9  248.03  6426.4  254.64
#Mann= 11 ,-1 , 0
  3147.7     .17       0    4249     .15       0  4486.5     .17       0
  4506.6     .15       0  4960.7     .09       0  5027.7     .15       0
  5636.3     .17       0  5866.9     .15       0  6029.4     .17       0
  6153.2     .15       0  6223.9     .17       0
Bank Sta=4960.7,5027.7
XS Rating Curve= 0 ,0
Exp/Cntr=0.3,0.1

Type RM Length L Ch R = 1 ,52500   ,1000,1000,1000
BEGIN DESCRIPTION:
LITTLE LAKE CREEK 98.0
END DESCRIPTION:
XS GIS Cut Line= 3
      3756018.68     10161072.32      3754918.26     10160596.21
      3753377.63     10160245.69
#Sta/Elev= 30
    3801  255.32  3957.8  257.07    3962  256.86  3998.2  255.97  4063.3  251.19
  4129.4  244.19  4348.9  224.77  4479.5  224.53  4608.2  219.47  4751.9  220.16
  4898.3   222.7  4927.2  221.35  4956.9  222.83  4989.5  219.33  5020.9   222.6
  5060.4  218.68    5084  218.68    5103  220.92  5180.4  222.92  5185.5  224.03
  5338.8   222.7  5390.1  223.67  5595.2  235.49  5679.6  234.02  5759.3  235.99
  5850.1  235.54  6005.5  234.65  6222.7  239.91  6329.7   242.3    6580  249.24
#Mann= 10 ,-1 , 0
    3801     .11       0  3957.8     .17       0    3962     .11       0
  4129.4     .17       0  4479.5     .15       0  4956.9     .09       0
  5020.9     .15       0  5850.1     .17       0  6222.7     .15       0
  6329.7     .17       0
Bank Sta=4956.9,5020.9
XS Rating Curve= 0 ,0
Exp/Cntr=0.3,0.1

Type RM Length L Ch R = 1 ,51500   ,500,500,500
BEGIN DESCRIPTION:
LITTLE LAKE CREEK 97.0
END DESCRIPTION:
XS GIS Cut Line= 3
      3756323.57     10159741.75      3755286.94      10159872.1
      3753391.36     10160143.47
#Sta/Elev= 30
  3955.2  251.57  4041.6  245.47  4282.2  236.31  4464.9  223.26  4485.1  225.02
  4767.3  221.06  4837.8  221.98  4958.8  220.84  4968.8  220.74  5002.1  218.92
  5039.5  221.22  5110.2  219.68  5251.6  221.44    5270  218.39  5293.8  218.39
  5302.1  221.69  5352.6  222.99  5379.4  225.28  5565.4  226.81  5635.5  229.37
  5706.2  229.09  5756.7   230.7  5867.8   230.7  5898.2   229.7  5908.3  227.82
  5944.5  231.84  6049.7   234.7  6251.7  232.07  6716.4  241.62  6914.9  248.38
#Mann= 6 ,-1 , 0
  3955.2     .17       0  4282.2     .15       0  4958.8     .12       0
  4968.8     .09       0  5039.5     .15       0  5565.4     .17       0
#XS Ineff= 2 , 0
       0  4485.1  225.02  5379.4       0  225.28
Permanent Ineff=
       F       F
Bank Sta=4968.8,5039.5
XS Rating Curve= 0 ,0
Exp/Cntr=0.3,0.1

Type RM Length L Ch R = 1 ,51000   ,500,500,500
BEGIN DESCRIPTION:
LITTLE LAKE CREEK 96.0
END DESCRIPTION:
XS GIS Cut Line= 3
       3756332.8     10159695.55      3755134.35     10159439.47
      3753331.36     10159958.44
#Sta/Elev= 30
  3774.5  251.56    3892  244.52  4010.5  240.94  4015.6   239.7    4060  236.93
  4168.1  233.48    4237  229.88  4297.2  225.42  4445.7  221.03  4875.8   218.7
  4986.2  220.74  4994.9  218.13  5018.7  218.13  5023.1  220.38  5079.6   218.8
  5194.1  222.99    5351  224.51  5547.9  228.44  5610.3  227.59  5637.4  228.78
  5651.9  227.32  5748.9  227.99  5966.6  232.28  5995.1  231.44  6033.9  233.07
  6503.1  237.55  6687.1  241.68  6786.2  245.56  6793.4  246.82  6876.2     249
#Mann= 5 ,-1 , 0
  3774.5     .17       0    4237     .11       0  4986.2     .06       0
  5023.1     .11       0    5351     .15       0
Bank Sta=4986.2,5023.1
XS Rating Curve= 0 ,0
Exp/Cntr=0.3,0.1

Type RM Length L Ch R = 1 ,50500   ,1000,1000,1000
BEGIN DESCRIPTION:
LITTLE LAKE CREEK 95.0
END DESCRIPTION:
XS GIS Cut Line= 3
      3756365.16     10159626.27      3755204.72     10158999.88
      3753217.82     10159261.08
#Sta/Elev= 30
  3681.3  250.47  3685.3  250.77  4267.3  227.89  4398.7  226.27  4436.8  224.59
  4486.2  221.67  4530.5  218.54    4576  217.65  4578.1   216.7  4601.9   216.7
  4606.2  218.12  4633.8  218.82  4803.3  218.08    4951  219.33    5017   218.4
  5027.1  221.41  5037.2  223.03  5188.5  223.98  5269.2  223.12  5410.4  224.38
    5481  223.68    5507     225  5531.4   223.9  5622.2  225.42    5834  226.17
  6320.4  234.98  6647.3  243.44  6721.6  244.69  6947.5  255.91    7004  257.58
#Mann= 9 ,-1 , 0
  3681.3     .17       0  3685.3     .17       0  4436.8     .12       0
  4486.2     .09       0  5027.1     .12       0  5037.2     .17       0
  6320.4     .17       0  6647.3     .11       0  6947.5     .15       0
#XS Ineff= 2 ,-1
  5087.6    5507  223.73    5507  5622.2     225
Permanent Ineff=
       F       F
Bank Sta=4486.2,5027.1
XS Rating Curve= 0 ,0
Exp/Cntr=0.3,0.1

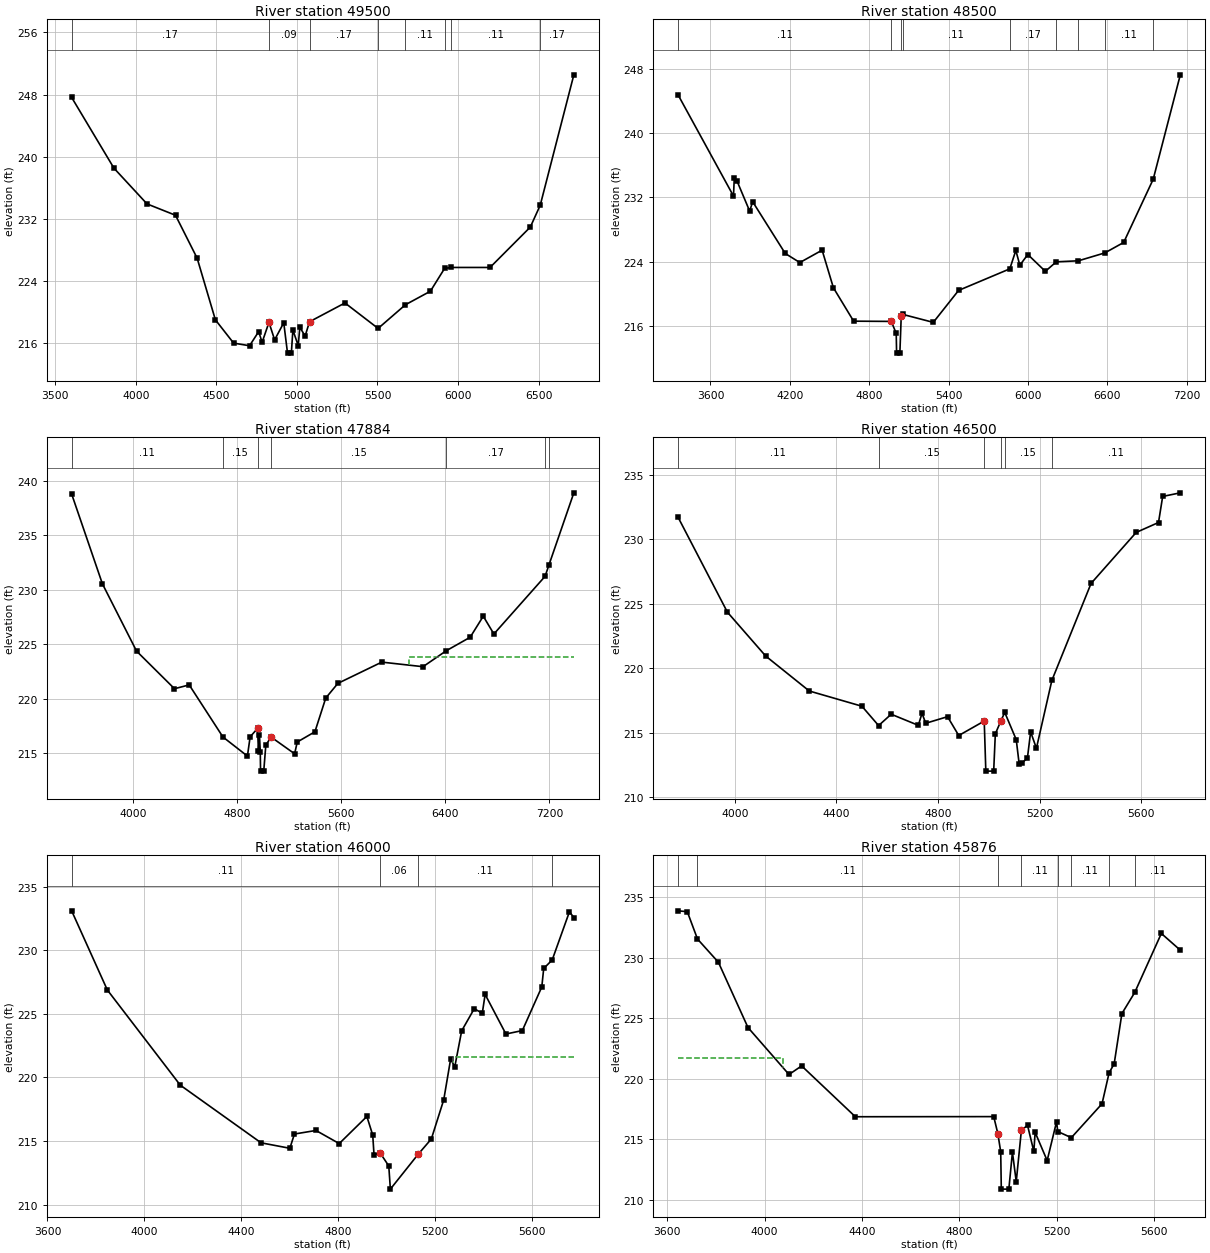
Type RM Length L Ch R = 1 ,49500   ,1000,1000,1000
BEGIN DESCRIPTION:
LITTLE LAKE CREEK 93.0
END DESCRIPTION:
XS GIS Cut Line= 3
      3756411.33     10159409.11      3755435.87     10158407.38
       3753717.9     10158361.07
#Sta/Elev= 30
  3601.8  247.64  3864.4  238.53  4069.6  233.93  4246.4  232.47  4380.7  226.94
  4493.8  219.01    4607  216.01    4706  215.67  4762.6  217.49  4783.9  216.11
  4826.4  218.68  4861.6  216.43  4918.2  218.63  4941.6  214.72  4965.4  214.72
  4974.8   217.7    5008  215.69    5018  218.06  5050.8  216.91  5078.1  218.76
  5298.1  221.18  5503.8   217.9  5673.5  220.95  5828.3  222.69  5916.2  225.62
  5957.2  225.75  6198.5  225.75  6448.5  230.95  6510.1  233.77  6718.6  250.55
#Mann= 8 ,-1 , 0
  3601.8     .17       0  4826.4     .09       0  5078.1     .17       0
  5503.8     .17       0  5673.5     .11       0  5916.2     .17       0
  5957.2     .11       0  6510.1     .17       0
Bank Sta=4826.4,5078.1
XS Rating Curve= 0 ,0
Exp/Cntr=0.3,0.1

Type RM Length L Ch R = 1 ,48500   ,616,616,616
BEGIN DESCRIPTION:
LITTLE LAKE CREEK 91.0
END DESCRIPTION:
XS GIS Cut Line= 4
      3756711.65     10159252.07      3755854.73     10157848.71
      3755811.65     10157825.98      3753722.73     10158060.06
#Sta/Elev= 30
  3355.7  244.72  3774.2  232.16    3780  234.36  3802.1  233.98  3896.2   230.3
  3919.3  231.45  4165.3  225.03  4275.5   223.9  4443.9  225.44  4529.1  220.77
  4682.1  216.62  4966.6  216.59  5003.9   215.1  5006.8  212.65  5031.4  212.65
  5041.7  217.22  5053.5  217.46    5284  216.47  5475.2  220.44  5862.4  223.12
  5907.8  225.41    5938  223.57  5998.4   224.9  6130.7  222.81  6213.3  223.99
  6380.8  224.12  6580.5   225.1  6722.9   226.4  6945.9  234.25  7150.7  247.22
#Mann= 9 ,-1 , 0
  3355.7     .11       0  4966.6     .06       0  5041.7     .09       0
  5053.5     .11       0  5862.4     .17       0  6213.3     .11       0
  6380.8     .17       0  6580.5     .11       0  6945.9     .17       0
#XS Ineff= 2 , 0
       0                  5907.8       0  225.41
Permanent Ineff=
       F       F
Bank Sta=4966.6,5041.7
XS Rating Curve= 0 ,0
Exp/Cntr=0.3,0.1

Type RM Length L Ch R = 1 ,47884   ,1384,1384,1384
BEGIN DESCRIPTION:
LITTLE LAKE CREEK 90.0
END DESCRIPTION:
XS GIS Cut Line= 3
      3757053.49     10158568.27      3756107.29     10157439.76
      3753736.38     10157718.21
#Sta/Elev= 30
  3527.3  238.76  3763.4  230.53  4026.2  224.35  4317.6   220.9  4430.8  221.25
  4690.2  216.47  4878.3  214.72  4899.2  216.49  4956.4  217.26  4962.9  215.18
  4970.7   216.7  4977.2  215.05  4979.2  213.34  5003.8  213.34  5019.6  215.71
  5059.8  216.47  5241.1  214.93  5261.2  216.01  5397.1  216.95  5480.2  220.04
  5573.5  221.39  5911.1  223.34  6227.8  222.92  6407.6  224.39  6590.3  225.62
    6691  227.55  6772.7  225.92  7166.1  231.21  7196.1  232.26  7387.2  238.87
#Mann= 7 ,-1 , 0
  3527.3     .11       0  4690.2     .15       0  4956.4     .09       0
  5059.8     .15       0  6407.6     .17       0  7166.1     .11       0
  7196.1     .17       0
#XS Ineff= 2 , 0
       0                  6117.1       0  223.81
Permanent Ineff=
       F       F
Bank Sta=4956.4,5059.8
XS Rating Curve= 0 ,0
Exp/Cntr=0.3,0.1

Type RM Length L Ch R = 1 ,46500   ,500,500,500
BEGIN DESCRIPTION:
LITTLE LAKE CREEK 87.0
END DESCRIPTION:
XS GIS Cut Line= 3
      3757334.61      10158056.1      3756616.17     10157066.62
      3756262.28     10156400.94
#Sta/Elev= 30
  3777.2  231.69  3971.2  224.34  4121.9  220.94  4293.5  218.23  4500.7  217.05
  4566.3  215.55  4615.9  216.43  4722.6  215.57  4737.2   216.5  4751.9  215.73
  4837.7  216.24  4881.8  214.78  4982.1   215.9  4988.4  212.02  5019.3  212.02
  5025.8  214.91  5047.8  215.92  5062.9  216.57  5108.1  214.46  5119.5   212.6
    5130  212.65    5152  213.02  5164.8  215.06  5187.5  213.79  5248.3  219.05
  5402.7  226.57  5580.2  230.52  5668.1  231.29  5684.5  233.31  5753.9  233.59
#Mann= 6 ,-1 , 0
  3777.2     .11       0  4566.3     .15       0  4982.1     .09       0
  5047.8     .12       0  5062.9     .15       0  5248.3     .11       0
Bank Sta=4982.1,5047.8
XS Rating Curve= 0 ,0
Exp/Cntr=0.3,0.1

Type RM Length L Ch R = 1 ,46000   ,124,124,124
BEGIN DESCRIPTION:
LITTLE LAKE CREEK 86.0
END DESCRIPTION:
XS GIS Cut Line= 3
      3757424.91     10158017.95      3756943.57     10156810.45
      3756615.89     10156108.24
#Sta/Elev= 30
  3700.1  233.09  3847.5  226.87  4148.9  219.39  4482.6  214.86  4601.6  214.43
  4620.5  215.55  4709.5  215.83  4805.6   214.8  4919.8  216.93    4944  215.47
  4949.4  213.91  4973.7  214.09  5010.3  213.04  5016.9  211.22  5131.7  213.96
  5186.1  215.16  5237.4  218.24  5265.8  221.43  5283.1  220.84  5311.5  223.66
  5363.5   225.4  5396.6  225.04  5408.4  226.52  5494.3  223.41  5562.1  223.68
  5642.5  227.11  5650.4  228.56  5685.5  229.23  5756.8  233.02  5774.9  232.56
#Mann= 4 ,-1 , 0
  3700.1     .11       0  4973.7     .06       0  5131.7     .11       0
  5685.5     .17       0
#XS Ineff= 2 , 0
       0                  5275.2       0  221.57
Permanent Ineff=
       F       F
Bank Sta=4973.7,5131.7
XS Rating Curve= 0 ,0
Exp/Cntr=0.3,0.1

Type RM Length L Ch R = 1 ,45876   ,669,669,669
BEGIN DESCRIPTION:
LITTLE LAKE CREEK 85.0
END DESCRIPTION:
XS GIS Cut Line= 3
      3757567.27     10157962.38      3757018.88      10156723.2
      3756786.62     10156054.39
#Sta/Elev= 30
  3644.9  233.88  3682.6  233.81  3724.5  231.55  3810.4  229.63  3931.9  224.24
  4100.4  220.36  4152.4  221.07    4373  216.87  4941.5  216.88  4958.6  215.46
  4970.2  213.97  4972.6  210.89  5003.6  210.89  5018.3  213.94    5034  211.51
  5055.2  215.77  5080.5  216.15  5106.3     214  5111.6  215.58    5161  213.25
  5199.7  216.46  5204.5  215.65  5260.3  215.14  5386.4  217.94  5415.5   220.5
  5436.3  221.24    5468  225.39  5520.9  227.14  5630.1  232.01    5708  230.63
#Mann= 8 ,-1 , 0
  3644.9     .17       0  3724.5     .11       0  4958.6     .07       0
  5055.2     .11       0  5204.5     .15       0  5260.3     .11       0
  5415.5     .17       0  5520.9     .11       0
#XS Ineff= 2 , 0
       0  4077.1  221.72               0
Permanent Ineff=
       F       F
Bank Sta=4958.6,5055.2
XS Rating Curve= 0 ,0
Exp/Cntr=0.3,0.1

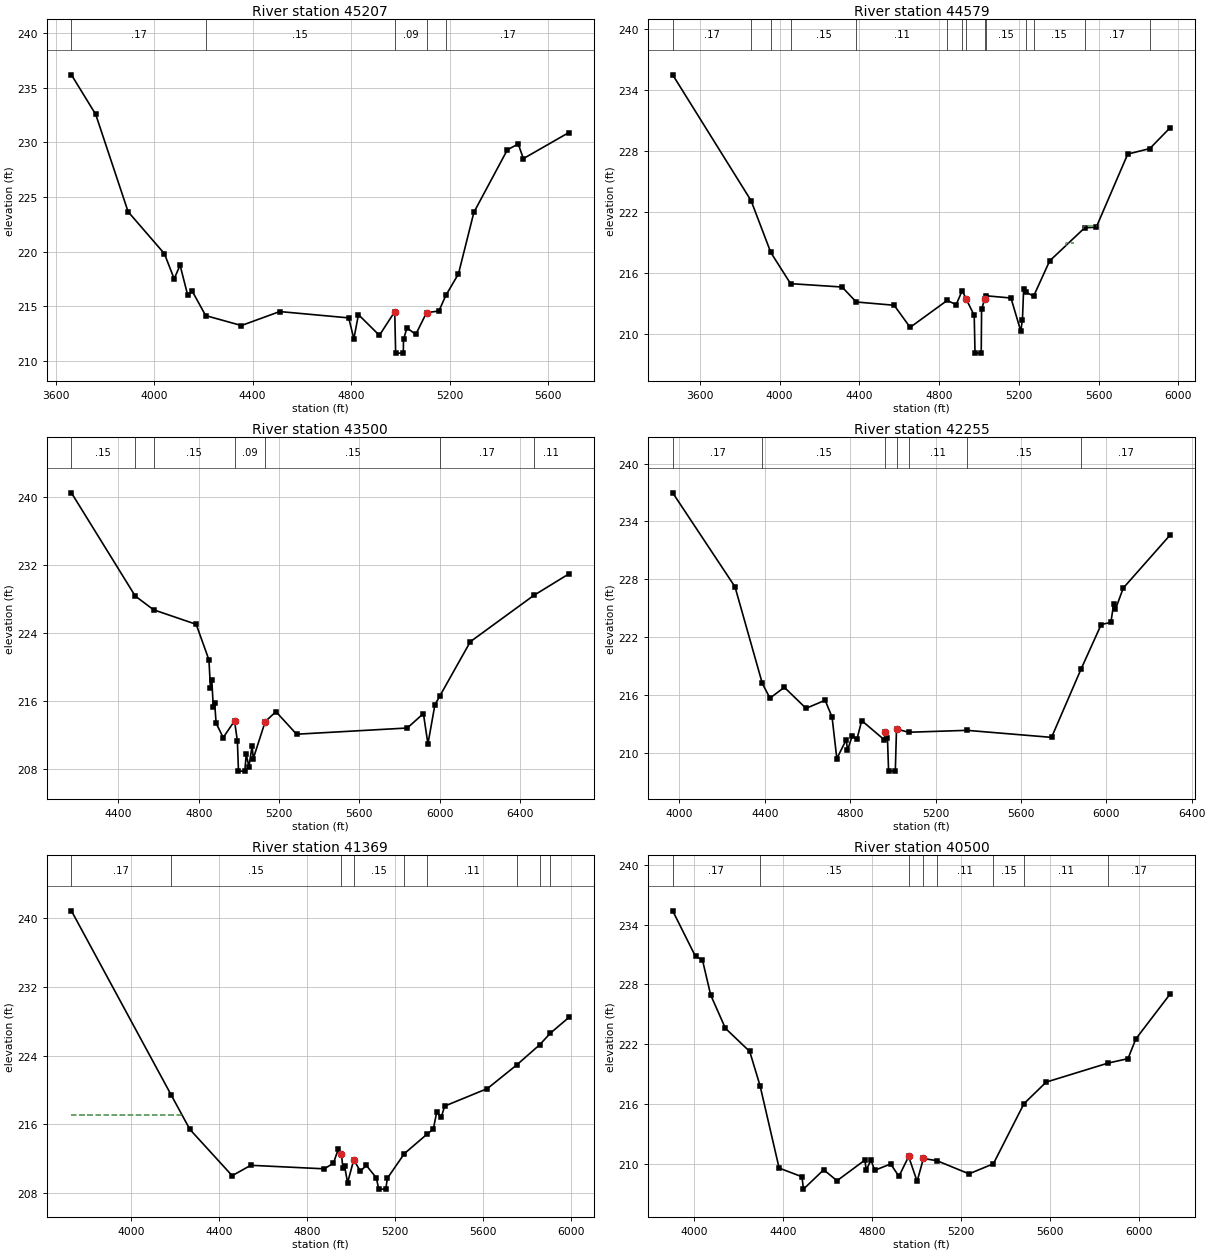
Type RM Length L Ch R = 1 ,45207   ,628,628,628
BEGIN DESCRIPTION:
LITTLE LAKE CREEK 84.0
END DESCRIPTION:
XS GIS Cut Line= 3
      3757754.75     10157726.23      3757398.22     10156438.99
      3756845.54     10156035.66
#Sta/Elev= 30
  3664.3   236.2    3763  232.57  3894.5  223.65    4042   219.8  4081.5   217.5
  4105.5  218.75  4136.6  215.99  4155.3  216.35  4209.4  214.13  4354.5  213.22
  4510.1   214.5  4790.2  213.92  4811.1     212  4829.7  214.22  4914.8  212.32
  4977.1  214.49  4980.8  210.69  5011.8  210.69  5012.8  211.94  5026.7  213.01
  5062.4   212.4  5106.2   214.4  5156.4  214.55  5184.8  215.99  5235.7  217.95
  5298.5   223.6  5434.5  229.33  5478.5  229.86  5499.4  228.52  5684.2  230.91
#Mann= 5 ,-1 , 0
  3664.3     .17       0  4209.4     .15       0  4977.1     .09       0
  5106.2     .15       0  5184.8     .17       0
Bank Sta=4977.1,5106.2
XS Rating Curve= 0 ,0
Exp/Cntr=0.3,0.1

Type RM Length L Ch R = 1 ,44579   ,1079,1079,1079
BEGIN DESCRIPTION:
LITTLE LAKE CREEK 83.0
END DESCRIPTION:
XS GIS Cut Line= 4
      3758008.24     10157747.13      3757868.68     10156216.98
      3757841.57     10156160.29      3757084.63     10155681.12
#Sta/Elev= 30
  3463.5  235.49  3856.6  223.14  3955.6  218.05  4054.7  214.99  4313.1  214.66
  4384.1  213.19  4574.2  212.87  4654.5   210.7  4840.1  213.34  4885.4  212.93
  4915.6  214.31  4935.6  213.48  4975.8  211.88  4979.9  208.17    5011  208.17
  5012.8  212.47  5028.7   213.5  5035.5   213.8  5160.1  213.58  5209.3  210.34
  5217.7  211.45  5223.7  214.47  5236.2  214.15  5273.8  213.76  5354.2  217.22
  5529.8  220.47    5588  220.53  5745.8  227.71  5856.4  228.25  5958.7   230.3
#Mann= 14 ,-1 , 0
  3463.5     .17       0  3856.6     .15       0  3955.6     .17       0
  4054.7     .15       0  4384.1     .11       0  4840.1     .15       0
  4915.6     .12       0  4935.6     .09       0  5028.7     .12       0
  5035.5     .15       0  5236.2     .17       0  5273.8     .15       0
  5529.8     .17       0  5856.4     .11       0
#XS Ineff= 2 ,-1
  5434.1  5478.8     219  5521.2  5594.1  220.63
Permanent Ineff=
       F       F
Bank Sta=4935.6,5028.7
XS Rating Curve= 0 ,0
Exp/Cntr=0.3,0.1

Type RM Length L Ch R = 1 ,43500   ,1245,1245,1245
BEGIN DESCRIPTION:
LITTLE LAKE CREEK 81.0
END DESCRIPTION:
XS GIS Cut Line= 3
      3759084.95     10157032.13      3758519.94     10156418.68
      3757085.46     10155615.75
#Sta/Elev= 30
    4166  240.49  4483.7  228.36  4575.1  226.74  4787.5  225.03    4851  220.85
  4858.4   217.6  4865.2   218.5  4872.6  215.34  4879.4  215.77  4886.8  213.41
  4921.9  211.71  4978.6  213.68  4992.8  211.26  4998.1  207.77  5029.6  207.77
  5036.8  209.75  5050.1  208.28  5066.1  210.75  5071.8  209.24  5131.2  213.59
  5184.8  214.76  5287.6  212.11    5839  212.84  5919.2  214.54  5941.8  210.96
  5976.5  215.57  6002.2  216.65    6153  222.99  6468.6  228.42  6643.9  230.96
#Mann= 7 ,-1 , 0
    4166     .15       0  4483.7     .17       0  4575.1     .15       0
  4978.6     .09       0  5131.2     .15       0  6002.2     .17       0
  6468.6     .11       0
Bank Sta=4978.6,5131.2
XS Rating Curve= 0 ,0
Exp/Cntr=0.3,0.1

Type RM Length L Ch R = 1 ,42255   ,886,886,886
BEGIN DESCRIPTION:
LITTLE LAKE CREEK 79.0
END DESCRIPTION:
XS GIS Cut Line= 3
      3759543.29     10156329.01      3758638.12     10155864.62
      3757949.64     10154745.83
#Sta/Elev= 30
  3968.3  236.97  4260.3  227.22  4388.1  217.21    4424  215.68  4491.4   216.8
  4593.2  214.62  4682.5  215.46  4715.1  213.71  4737.3  209.41  4781.7  211.37
  4787.3  210.26  4809.5  211.77  4831.7  211.43  4853.9  213.35  4959.2  211.37
  4964.8  212.21  4974.7  211.51  4979.9  208.11  5011.4  208.11    5017  212.48
  5073.5  212.14  5347.4  212.34  5743.5  211.61  5880.9  218.65  5976.1  223.31
  6021.6  223.54  6034.8  225.49  6042.9  224.89  6079.6   227.1  6299.3   232.6
#Mann= 7 ,-1 , 0
  3968.3     .17       0  4388.1     .15       0  4964.8     .09       0
    5017     .15       0  5073.5     .11       0  5347.4     .15       0
  5880.9     .17       0
Bank Sta=4964.8,5017
XS Rating Curve= 0 ,0
Exp/Cntr=0.3,0.1

Type RM Length L Ch R = 1 ,41369   ,869,869,869
BEGIN DESCRIPTION:
LITTLE LAKE CREEK 77.0
END DESCRIPTION:
XS GIS Cut Line= 3
       3759819.3     10156188.35       3758997.2      10155218.5
      3758454.76     10154391.53
#Sta/Elev= 30
  3728.6  240.82  4181.6  219.43  4266.7  215.42    4459  210.03  4543.6  211.24
  4877.5  210.83  4919.2  211.48  4941.2  213.14  4955.5   212.6  4962.1  210.88
  4969.8  211.15  4983.5  209.21  5011.4  211.87  5041.6  210.56  5068.7  211.23
  5113.9  209.78  5125.2  208.47  5156.8  208.47  5164.4  209.74  5241.5   212.6
  5344.5  214.86  5373.1  215.45  5388.2   217.4  5409.3  216.85  5424.4  218.12
  5618.8  220.16  5751.3  222.89  5855.8  225.24  5904.9   226.6    5989  228.43
#Mann= 9 ,-1 , 0
  3728.6     .17       0  4181.6     .15       0  4955.5     .09       0
  5011.4     .15       0  5241.5     .15       0  5344.5     .11       0
  5751.3     .17       0  5855.8     .11       0  5904.9     .17       0
#XS Ineff= 2 , 0
       0  4231.6  217.13  5388.2       0   217.4
Permanent Ineff=
       F       F
Bank Sta=4955.5,5011.4
XS Rating Curve= 0 ,0
Exp/Cntr=0.3,0.1

Type RM Length L Ch R = 1 ,40500   ,1070,1070,1070
BEGIN DESCRIPTION:
LITTLE LAKE CREEK 75.0
END DESCRIPTION:
XS GIS Cut Line= 3
      3760117.84     10155811.05      3759593.69     10154848.63
      3758792.76     10154038.09
#Sta/Elev= 30
  3904.1  235.37  4006.6   230.8  4037.5  230.47  4074.9  226.93    4141   223.6
  4250.2  221.28  4296.6  217.85  4382.3   209.6  4484.8  208.73  4491.8  207.49
  4582.6  209.43  4642.4  208.33  4767.8   210.4  4773.5  209.41  4795.3   210.4
  4811.5  209.37  4883.4  210.01  4920.7  208.77  4964.3  210.76  5002.4  208.27
  5030.7  210.56  5091.3  210.34  5235.7  209.02  5345.1  210.03  5482.5  216.05
  5582.3  218.21  5860.9  220.12    5950  220.56  5985.3  222.54  6139.5  227.04
#Mann= 8 ,-1 , 0
  3904.1     .17       0  4296.6     .15       0  4964.3     .09       0
  5030.7     .15       0  5091.3     .11       0  5345.1     .15       0
  5482.5     .11       0  5860.9     .17       0
Bank Sta=4964.3,5030.7
XS Rating Curve= 0 ,0
Exp/Cntr=0.3,0.1