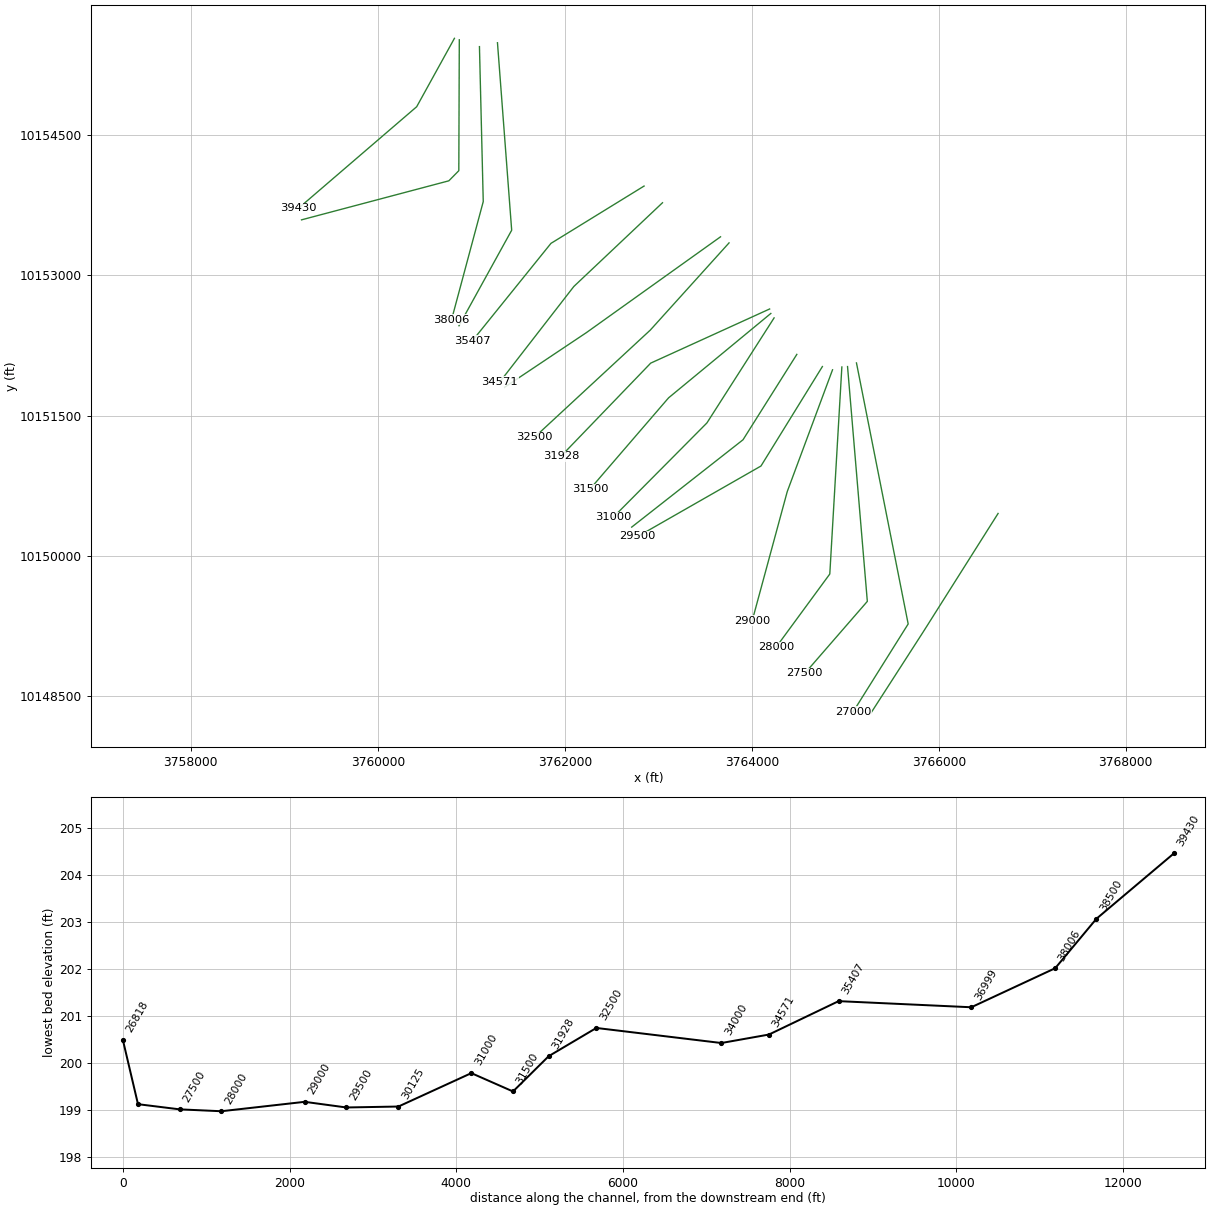
HEC-RAS study LITTLE LAKE CREEK.prj: LITTLE LAKE CREEK Base Level Engineering

--- LITTLE LAKE CREEK.g01 (geometry) --- (continued)

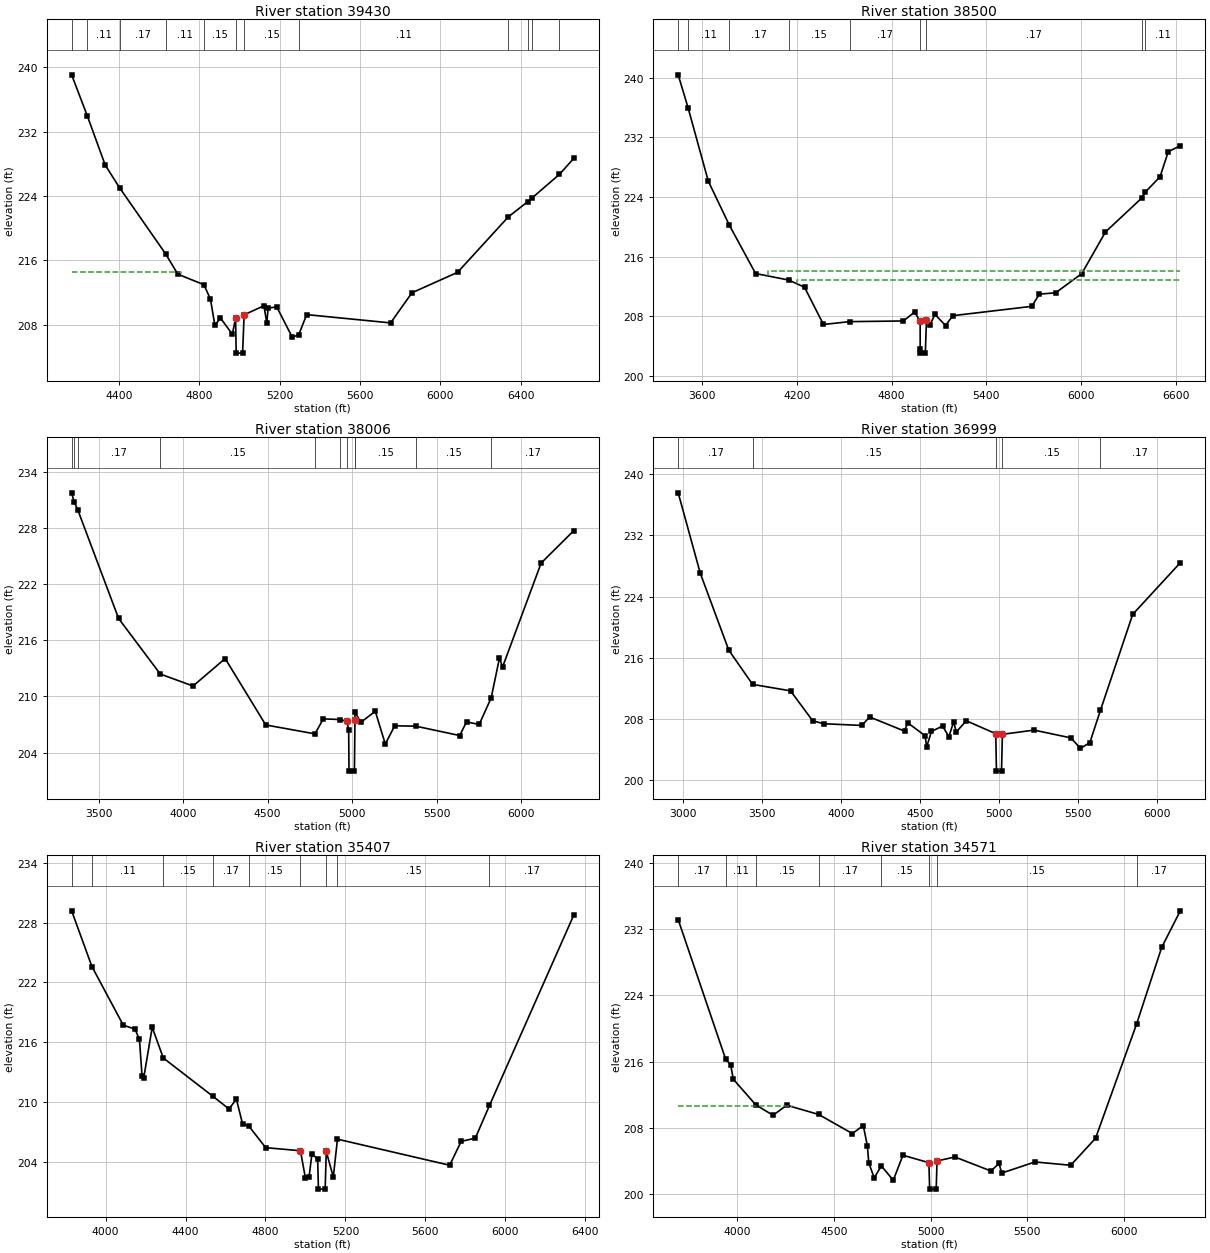
Type RM Length L Ch R = 1 ,39430   ,930,930,930
BEGIN DESCRIPTION:
LITTLE LAKE CREEK 73.0
END DESCRIPTION:
XS GIS Cut Line= 3
      3760819.35     10155537.38      3760415.52     10154805.27
      3759152.78     10153719.73
#Sta/Elev= 30
  4163.9  239.08  4242.7  233.92    4331  227.86  4402.9  225.02    4632  216.81
  4692.8  214.28    4823  212.97  4855.6  211.15  4877.4  207.92  4904.9  208.84
  4964.5  206.81  4980.5  208.81  4983.6  204.46  5015.5  204.46  5023.1  209.23
  5121.8  210.35  5136.1   208.2  5142.7  210.06  5185.5  210.21  5263.4  206.42
  5295.3  206.76  5334.7  209.25  5752.8  208.22  5859.2  211.97  6086.4  214.51
  6339.3  221.41    6436   223.3  6456.9  223.75  6593.8   226.7  6665.2  228.68
#Mann= 12 ,-1 , 0
  4163.9     .17       0  4242.7     .11       0  4402.9     .17       0
    4632     .11       0    4823     .15       0  4980.5     .09       0
  5023.1     .15       0  5295.3     .11       0  6339.3     .17       0
    6436     .11       0  6456.9     .17       0  6593.8     .11       0
#XS Ineff= 2 , 0
       0  4707.9  214.56               0
Permanent Ineff=
       F       F
Bank Sta=4980.5,5023.1
XS Rating Curve= 0 ,0
Exp/Cntr=0.3,0.1

Type RM Length L Ch R = 1 ,38500   ,494,494,494
BEGIN DESCRIPTION:
LITTLE LAKE CREEK 71.0
END DESCRIPTION:
XS GIS Cut Line= 4
      3760871.41     10155521.72      3760866.21     10154120.68
      3760759.82     10154012.46      3759183.88     10153594.62
#Sta/Elev= 30
  3447.2  240.37  3510.5   235.9  3637.8  226.13  3771.4  220.22  3937.8  213.74
  4146.6  212.87  4247.9  211.91  4367.9  206.91  4533.2  207.29  4875.1  207.38
  4945.9  208.58  4981.2  207.35  4981.3  203.57  4981.9  203.07  5013.8  203.07
  5021.2   207.5  5043.4  206.83  5074.5  208.27  5141.8  206.77  5188.3  208.09
  5689.1  209.34  5736.6  210.98  5839.6  211.15  6005.6  213.73    6156  219.31
  6386.7  223.87  6406.5  224.61  6502.1  226.71  6553.9  230.07  6630.4  230.86
#Mann= 9 ,-1 , 0
  3447.2     .17       0  3510.5     .11       0  3771.4     .17       0
  4146.6     .15       0  4533.2     .17       0  4981.2     .09       0
  5021.2     .17       0  6386.7     .17       0  6406.5     .11       0
#XS Ineff= 3 ,-1
  4017.8  3897.8  214.11  4197.9  4077.9  212.87  6000.4  6026.2  214.18
Permanent Ineff=
       F       F       F
Bank Sta=4981.2,5021.2
XS Rating Curve= 0 ,0
Exp/Cntr=0.3,0.1

Type RM Length L Ch R = 1 ,38006   ,1007,1007,1007
BEGIN DESCRIPTION:
LITTLE LAKE CREEK 70.0
END DESCRIPTION:
XS GIS Cut Line= 3
      3761086.98     10155448.64      3761127.55     10153789.94
      3760788.28     10152524.74
#Sta/Elev= 30
  3340.8  231.74  3354.9   230.8    3378  229.87  3618.5  218.32  3864.8  212.39
  4058.6  211.11  4248.6  214.04  4488.7  206.95  4779.6     206  4828.8   207.6
    4929  207.53  4968.9  207.34  4978.9  206.39  4980.9  202.02  5012.9  202.02
 5016.04  207.48  5016.3  208.33  5050.6  207.23  5136.3  208.41  5195.5  204.91
  5251.1  206.86  5376.1  206.82  5635.7  205.82  5675.7  207.28  5750.6     207
  5821.5  209.84  5870.6  214.09  5889.2  213.15    6117  224.24  6309.9   227.7
#Mann= 11 ,-1 , 0
  3340.8     .17       0  3354.9     .11       0    3378     .17       0
  3864.8     .15       0  4779.6     .15       0    4929     .15       0
  4968.9     .09       0 5016.04     .12       0  5016.3     .15       0
  5376.1     .15       0  5821.5     .17       0
#XS Ineff= 2 , 0
       0  4248.6  214.04  5870.6       0  214.09
Permanent Ineff=
       F       F
Bank Sta=4968.9,5016.04
XS Rating Curve= 0 ,0
Exp/Cntr=0.3,0.1

Type RM Length L Ch R = 1 ,36999   ,1592,1592,1592
BEGIN DESCRIPTION:
LITTLE LAKE CREEK 69.0
END DESCRIPTION:
XS GIS Cut Line= 3
      3761279.69     10155490.35      3761431.63     10153483.47
      3760867.83     10152461.04
#Sta/Elev= 30
  2968.7  237.55  3108.4  227.05  3288.9     217    3440  212.52    3680  211.68
  3820.4  207.77  3890.6  207.38  4131.3  207.16  4181.4  208.26  4402.1  206.42
  4422.1  207.51  4532.4  205.81  4542.5  204.36  4572.6  206.37  4642.8  207.08
  4682.9  205.69    4713  207.61  4730.3  206.31  4793.2  207.77    4980  206.08
  4984.3  201.19  5016.4  201.19  5022.1     206  5222.7  206.55  5456.5  205.53
  5516.2  204.16  5575.8  204.91  5642.8  209.12  5847.4  221.67  6148.9  228.42
#Mann= 5 ,-1 , 0
  2968.7     .17       0    3440     .15       0    4980     .09       0
  5022.1     .15       0  5642.8     .17       0
Bank Sta=4980,5022.1
XS Rating Curve= 0 ,0
Exp/Cntr=0.3,0.1

Type RM Length L Ch R = 1 ,35407   ,836,836,836
BEGIN DESCRIPTION:
LITTLE LAKE CREEK 68.0
END DESCRIPTION:
XS GIS Cut Line= 3
      3762847.81     10153956.34      3761851.79     10153342.85
      3761009.26     10152297.65
#Sta/Elev= 30
  3830.2  229.17  3931.7  223.59  4088.5  217.73  4147.3  217.33  4169.4   216.3
  4182.5  212.65  4190.7  212.43  4233.2  217.51  4288.9  214.44  4538.2  210.59
  4617.7  209.34  4654.4  210.33  4685.2  207.86  4717.1  207.62  4801.1  205.47
    4975  205.16  4999.4  202.48  5017.9  202.52  5032.3  204.81  5061.1  204.36
    5065  201.32  5098.7  201.32  5104.2  205.09  5139.4  202.53  5160.2  206.32
  5721.7  203.71  5779.2   206.1    5850  206.42  5920.7  209.69  6342.5  228.74
#Mann= 9 ,-1 , 0
  3830.2     .17       0  3931.7     .11       0  4288.9     .15       0
  4538.2     .17       0  4717.1     .15       0    4975     .09       0
  5104.2     .12       0  5160.2     .15       0  5920.7     .17       0
Bank Sta=4975,5104.2
XS Rating Curve= 0 ,0
Exp/Cntr=0.3,0.1

Type RM Length L Ch R = 1 ,34571   ,571,571,571
BEGIN DESCRIPTION:
LITTLE LAKE CREEK 67.0
END DESCRIPTION:
XS GIS Cut Line= 3
      3763044.84     10153777.67      3762096.05     10152880.94
      3761304.38     10151859.26
#Sta/Elev= 30
  3694.5  233.13  3940.1  216.29  3965.6  215.64  3979.8  213.87  4095.6  210.79
  4185.3  209.52  4255.7  210.74  4421.5  209.62  4595.5  207.32  4652.2  208.28
  4673.2  205.84  4680.5   203.8  4708.6  201.96  4745.4  203.41  4807.5  201.69
  4857.3   204.7  4991.6   203.8  4995.6  200.61  5029.4  200.61 5033.72  204.01
  5126.3  204.49  5312.6   202.8  5354.2  203.71  5368.7  202.55  5540.7  203.89
  5725.4  203.49    5854  206.75  6066.9  220.58  6196.2  229.79  6292.5   234.2
#Mann= 8 ,-1 , 0
  3694.5     .17       0  3940.1     .11       0  4095.6     .15       0
  4421.5     .17       0  4745.4     .15       0  4991.6     .09       0
 5033.72     .15       0  6066.9     .17       0
#XS Ineff= 2 , 0
       0    4284  210.66               0
Permanent Ineff=
       F       F
Bank Sta=4991.6,5033.72
XS Rating Curve= 0 ,0
Exp/Cntr=0.3,0.1

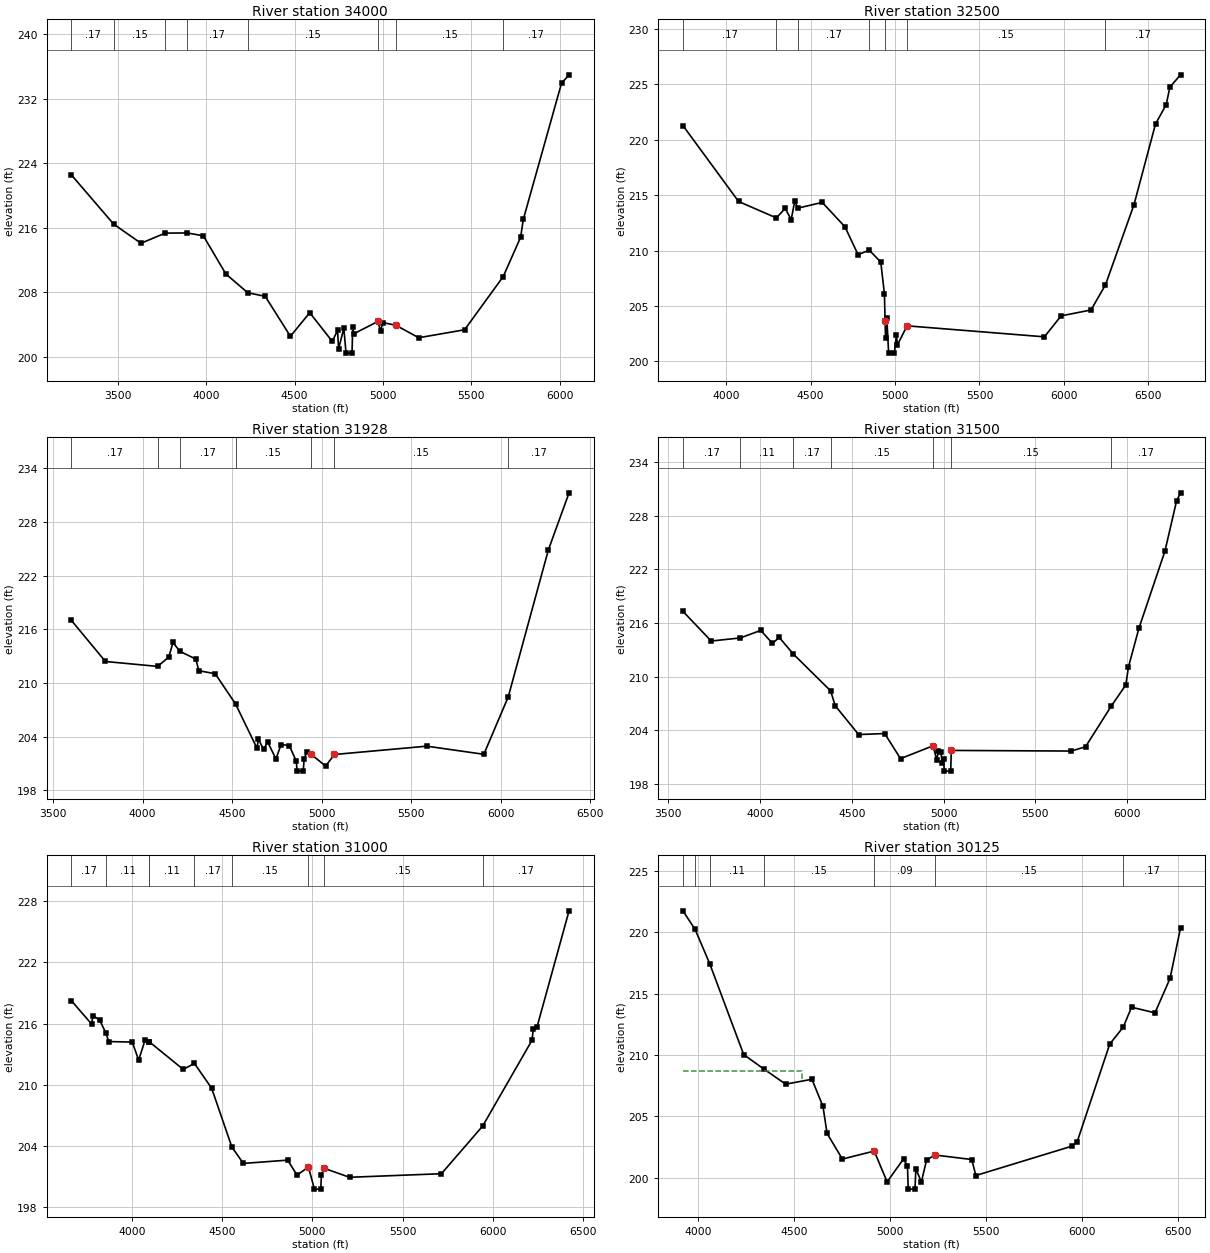
Type RM Length L Ch R = 1 ,34000   ,1500,1500,1500
BEGIN DESCRIPTION:
LITTLE LAKE CREEK 66.0
END DESCRIPTION:
XS GIS Cut Line= 3
      3763665.54     10153413.12      3762231.44     10152387.86
      3761356.49     10151802.86
#Sta/Elev= 30
  3237.1  222.55  3475.9  216.45  3630.6  214.07  3767.6  215.33  3891.1  215.35
  3983.3     215  4111.1  210.25  4234.5  207.93  4333.5  207.48    4476  202.52
  4585.4  205.45  4713.1  201.88  4742.6  203.26  4748.8  200.97  4778.3  203.53
  4790.8  200.43  4824.6  200.43  4828.6  203.69  4834.8  202.83  4971.2  204.36
  4985.9  203.16  4999.1  204.22  5072.8  203.89    5202  202.34  5461.4  203.33
  5680.2  209.94  5778.5  214.82  5793.5  217.02  6009.8  233.93  6052.5  234.98
#Mann= 8 ,-1 , 0
  3237.1     .17       0  3475.9     .15       0  3767.6     .11       0
  3891.1     .17       0  4234.5     .15       0  4971.2     .09       0
  5072.8     .15       0  5680.2     .17       0
Bank Sta=4971.2,5072.8
XS Rating Curve= 0 ,0
Exp/Cntr=0.3,0.1

Type RM Length L Ch R = 1 ,32500   ,572,572,572
BEGIN DESCRIPTION:
LITTLE LAKE CREEK 65.0
END DESCRIPTION:
XS GIS Cut Line= 3
      3763756.64     10153347.98      3762914.62     10152414.94
      3761674.07     10151265.36
#Sta/Elev= 30
  3743.2  221.27  4073.1  214.42    4297  212.94  4348.9   213.8  4384.8  212.79
  4405.7  214.44    4424  213.82  4568.6  214.34  4703.1  212.14  4780.9  209.63
  4847.4  210.03  4915.4  208.96    4937   206.1 4941.06  203.61  4943.8  202.13
  4951.2  203.94    4962  200.75  4995.8  200.75  5007.7  202.34  5014.5  201.51
  5071.2  203.21  5884.8  202.22    5984  204.11  6160.9  204.64  6246.7  206.91
  6415.5  214.13  6543.1  221.41  6606.6  223.16  6628.1  224.73  6691.3  225.84
#Mann= 7 ,-1 , 0
  3743.2     .17       0    4297     .11       0    4424     .17       0
  4847.4     .15       0 4941.06     .09       0  5071.2     .15       0
  6246.7     .17       0
Bank Sta=4941.06,5071.2
XS Rating Curve= 0 ,0
Exp/Cntr=0.3,0.1

Type RM Length L Ch R = 1 ,31928   ,428,428,428
BEGIN DESCRIPTION:
LITTLE LAKE CREEK 64.0
END DESCRIPTION:
XS GIS Cut Line= 3
      3764190.72     10152640.55      3762918.64     10152060.94
      3761960.26     10151065.51
#Sta/Elev= 30
  3602.1     217  3792.1  212.41  4083.3  211.86  4146.4  212.91  4169.4  214.54
  4206.8  213.56  4297.6  212.67  4313.2  211.38  4405.4  211.04  4519.2  207.65
  4638.2  202.73  4646.9  203.72  4675.4  202.57  4698.4  203.42  4744.5   201.5
  4773.1  203.12  4819.2  203.01    4858  201.27    4863  200.15  4896.9  200.15
    4902  201.52  4916.9   202.3  4939.9  202.06  5021.7  200.71  5071.1  202.01
  5587.4  202.94  5905.7  202.03  6042.1  208.45  6266.3  224.89  6381.8  231.27
#Mann= 7 ,-1 , 0
  3602.1     .17       0  4083.3     .11       0  4206.8     .17       0
  4519.2     .15       0  4939.9     .09       0  5071.1     .15       0
  6042.1     .17       0
Bank Sta=4939.9,5071.1
XS Rating Curve= 0 ,0
Exp/Cntr=0.3,0.1

Type RM Length L Ch R = 1 ,31500   ,500,500,500
BEGIN DESCRIPTION:
LITTLE LAKE CREEK 63.0
END DESCRIPTION:
XS GIS Cut Line= 3
      3764203.68     10152592.77      3763109.38     10151688.94
      3762267.86     10150711.08
#Sta/Elev= 30
  3580.7  217.31    3735  213.98  3893.6  214.33  4004.6  215.17  4068.5  213.71
    4105  214.39  4182.4  212.51  4384.9   208.4  4409.8  206.73  4537.5   203.5
  4679.5  203.61  4765.5   200.8  4942.7  202.24  4963.5  200.61  4971.3  201.65
  4985.7  201.56  4992.1  200.28    5000  200.77  5003.6   199.4  5038.8   199.4
    5042  201.72  5694.9  201.65  5772.8  202.13  5912.6  206.68  5992.2  209.06
  6006.5  211.07  6063.5  215.41  6205.1  224.05  6268.7   229.7  6290.1  230.59
#Mann= 7 ,-1 , 0
  3580.7     .17       0  3893.6     .11       0  4182.4     .17       0
  4384.9     .15       0  4942.7     .09       0    5042     .15       0
  5912.6     .17       0
Bank Sta=4942.7,5042
XS Rating Curve= 0 ,0
Exp/Cntr=0.3,0.1

Type RM Length L Ch R = 1 ,31000   ,875,875,875
BEGIN DESCRIPTION:
LITTLE LAKE CREEK 62.0
END DESCRIPTION:
XS GIS Cut Line= 3
      3764238.41     10152545.02      3763519.57     10151420.32
      3762517.84     10150411.06
#Sta/Elev= 30
  3665.2  218.25  3776.7  215.97  3784.8  216.78  3821.2  216.37  3857.2  215.05
  3871.6  214.25  4002.2   214.2  4037.8  212.43  4073.4  214.41  4095.4   214.2
  4096.4  214.23  4284.7  211.52  4346.5  212.11    4442  209.68  4554.3   203.9
    4618  202.31  4863.3  202.63  4914.9  201.16  4978.3  201.96  5011.3  199.79
  5046.5  199.79  5050.2  201.19  5064.3  201.84  5205.8  200.95  5714.9   201.3
  5943.4  205.97  6216.9  214.38    6224  215.51  6245.2  215.72    6422  227.06
#Mann= 9 ,-1 , 0
  3665.2     .17       0  3857.2     .11       0  4095.4     .17       0
  4096.4     .11       0  4346.5     .17       0  4554.3     .15       0
  4978.3     .09       0  5064.3     .15       0  5943.4     .17       0
Bank Sta=4978.3,5064.3
XS Rating Curve= 0 ,0
Exp/Cntr=0.3,0.1

Type RM Length L Ch R = 1 ,30125   ,625,625,625
BEGIN DESCRIPTION:
LITTLE LAKE CREEK 60.0
END DESCRIPTION:
XS GIS Cut Line= 3
       3764481.5     10152154.44      3763906.05     10151240.63
       3762715.4     10150305.79
#Sta/Elev= 30
  3920.1  221.75    3984  220.23  4059.7  217.45  4236.9  210.04  4341.2  208.87
  4455.9  207.63  4592.5  208.03  4650.2  205.82  4671.4  203.62  4751.3  201.53
  4917.4  202.18  4984.5  199.67  5069.9  201.54  5090.7  200.96  5094.4  199.08
  5129.8  199.08  5134.1  200.75    5163  199.66  5190.1  201.45  5233.5  201.86
    5426  201.49  5446.8  200.19  5945.7  202.57  5974.7  202.92  6144.6  210.89
  6215.2  212.28  6258.5   213.9  6380.5  213.44  6459.1  216.24  6513.8  220.37
#Mann= 7 ,-1 , 0
  3920.1     .11       0    3984     .17       0  4059.7     .11       0
  4341.2     .15       0  4917.4     .09       0  5233.5     .15       0
  6215.2     .17       0
#XS Ineff= 2 , 0
       0  4540.7   208.7               0
Permanent Ineff=
       F       F
Bank Sta=4917.4,5233.5
XS Rating Curve= 0 ,0
Exp/Cntr=0.3,0.1

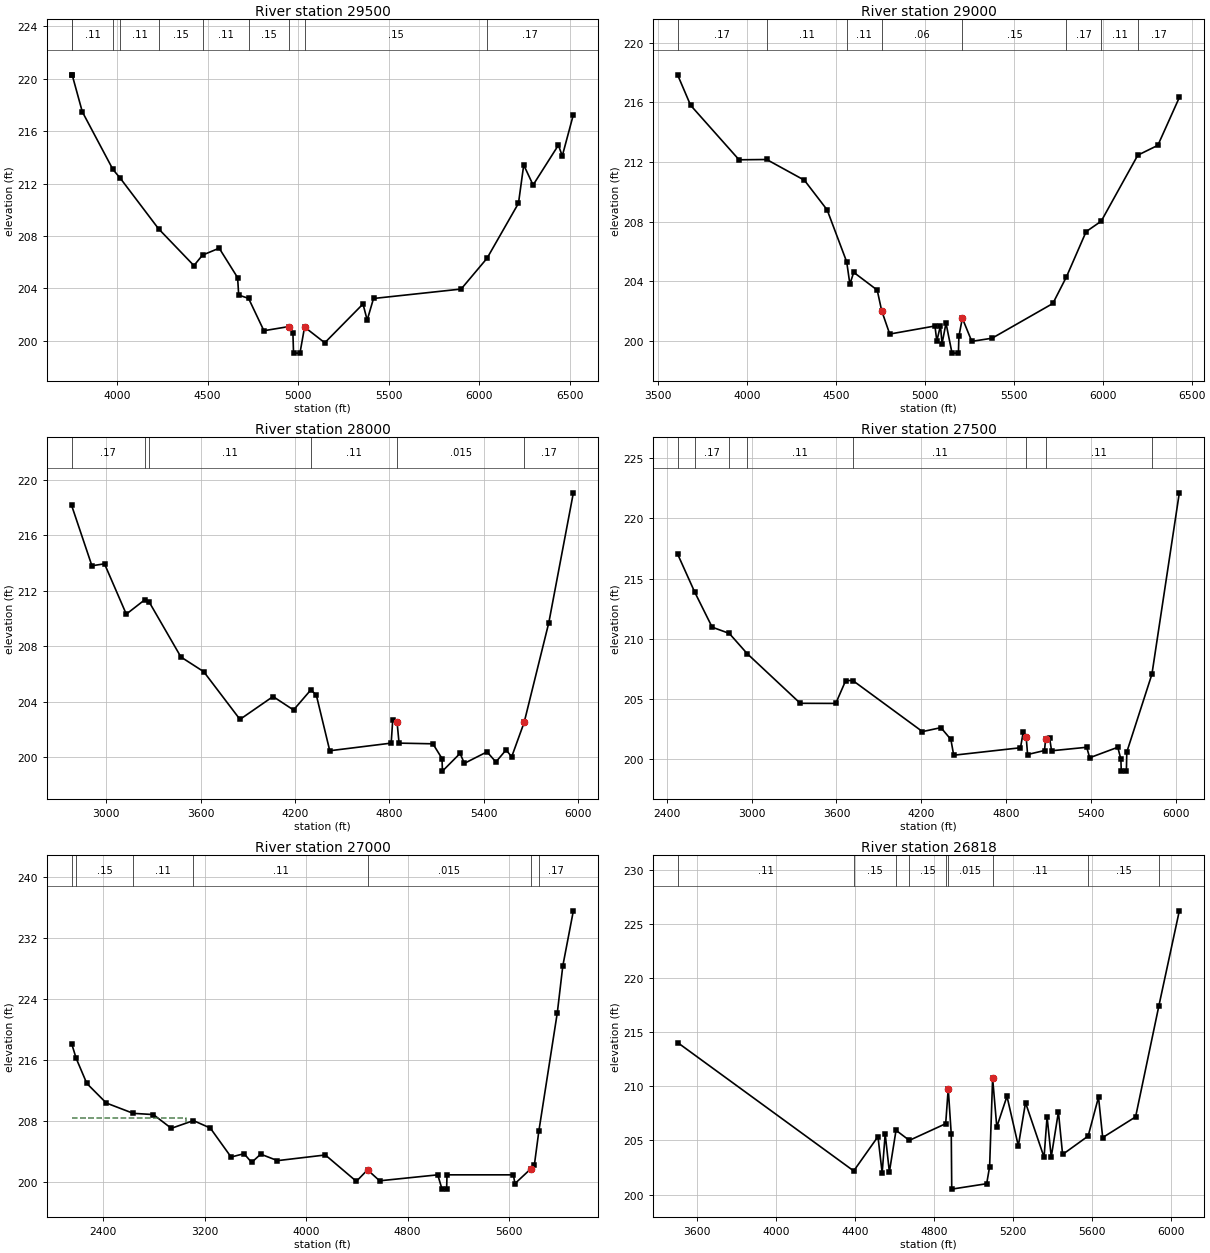
Type RM Length L Ch R = 1 ,29500   ,500,500,500
BEGIN DESCRIPTION:
LITTLE LAKE CREEK 59.0
END DESCRIPTION:
XS GIS Cut Line= 3
      3764754.95     10152024.25      3764098.11     10150959.68
      3762780.06     10150205.62
#Sta/Elev= 30
  3749.1  220.26    3752   220.3    3808  217.48    3977  213.08  4018.1   212.4
  4228.9  208.55  4424.1  205.74  4471.5  206.54  4563.6  207.07  4665.3  204.82
  4671.2  203.49  4725.7  203.24  4810.4  200.77  4949.2  201.09  4970.5  200.58
    4974  199.06  5009.4  199.06  5034.9  201.05  5146.3  199.85  5357.4  202.81
  5380.5  201.58  5415.4  203.23    5899  203.95    6042   206.3  6215.6   210.5
  6244.5  213.42  6296.2  211.89  6435.8  214.93  6457.4  214.11  6518.5  217.26
#Mann= 10 ,-1 , 0
  3749.1     .17       0    3752     .11       0    3977     .17       0
  4018.1     .11       0  4228.9     .15       0  4471.5     .11       0
  4725.7     .15       0  4949.2     .09       0  5034.9     .15       0
    6042     .17       0
Bank Sta=4949.2,5034.9
XS Rating Curve= 0 ,0
Exp/Cntr=0.3,0.1

Type RM Length L Ch R = 1 ,29000   ,1000,1000,1000
BEGIN DESCRIPTION:
LITTLE LAKE CREEK 58.0
END DESCRIPTION:
XS GIS Cut Line= 3
      3764863.44     10151989.52      3764378.93     10150685.41
       3764004.5     10149304.48
#Sta/Elev= 30
  3608.8  217.85  3681.8  215.81  3954.5  212.15  4109.8  212.17  4321.9  210.78
  4449.9  208.79    4560   205.3  4577.9   203.8  4599.3   204.6  4731.5  203.41
  4756.5  202.03  4801.9  200.46  5056.3     201  5066.7  199.99  5087.4  201.03
  5096.1  199.81  5118.5  201.19  5152.3  199.18  5188.3  199.18    5191  200.31
  5210.4  201.52  5263.5  199.97  5377.5  200.18  5719.4  202.51    5796   204.3
  5906.6  207.33  5991.4  208.03  6197.3  212.46    6310  213.12  6430.8  216.33
#Mann= 8 ,-1 , 0
  3608.8     .17       0  4109.8     .11       0    4560     .11       0
  4756.5     .06       0  5210.4     .15       0    5796     .17       0
  5991.4     .11       0  6197.3     .17       0
Bank Sta=4756.5,5210.4
XS Rating Curve= 0 ,0
Exp/Cntr=0.3,0.1

Type RM Length L Ch R = 1 ,28000   ,500,500,500
BEGIN DESCRIPTION:
LITTLE LAKE CREEK 56.0
END DESCRIPTION:
XS GIS Cut Line= 3
      3764963.26     10152019.85      3764834.24     10149803.81
      3764260.12     10149020.72
#Sta/Elev= 30
  2780.2  218.14  2909.2  213.79  2989.3  213.93  3127.9   210.3  3246.8  211.35
  3271.6  211.21  3475.3  207.21  3620.4  206.15  3850.8  202.71  4061.1  204.36
  4191.4  203.39  4301.6  204.84  4336.2  204.47  4421.8  200.45  4812.4     201
  4822.4  202.69  4849.7  202.53  4862.5     201  5077.8  200.95  5135.6  199.89
  5138.4  198.98  5250.6  200.26  5277.7  199.54    5422  200.37  5478.3  199.64
  5543.2  200.51  5578.7  200.01  5658.2   202.5  5814.9  209.69    5971  219.05
#Mann= 6 ,-1 , 0
  2780.2     .17       0  3246.8     .15       0  3271.6     .11       0
  4301.6     .11       0  4849.7    .015       0  5658.2     .17       0
Bank Sta=4849.7,5658.2
XS Rating Curve= 0 ,0
Exp/Cntr=0.3,0.1

Type RM Length L Ch R = 1 ,27500   ,500,500,500
BEGIN DESCRIPTION:
LITTLE LAKE CREEK 55.0
END DESCRIPTION:
XS GIS Cut Line= 3
      3765024.02     10152024.25      3765235.75     10149510.95
      3764566.28     10148739.68
#Sta/Elev= 30
  2477.8  217.04  2599.1  213.87  2721.8  210.97  2842.9  210.45  2969.4  208.77
    3344  204.65  3594.9  204.64  3665.2  206.54  3715.3  206.54  4207.1   202.3
  4337.5  202.63  4407.8  201.65  4427.9  200.34  4899.5  200.96  4919.6   202.3
  4939.7  201.83  4949.7   200.4  5069.1  200.73  5076.7  201.65  5105.2  201.77
    5119  200.71  5367.3     201  5388.1  200.13  5586.6     201  5608.5  200.01
  5611.3  199.02  5647.4  199.02  5650.2   200.6  5827.8  207.07  6021.3  222.12
#Mann= 8 ,-1 , 0
  2477.8     .15       0  2599.1     .17       0  2842.9     .15       0
  2969.4     .11       0  3715.3     .11       0  4939.7    .015       0
  5076.7     .11       0  5827.8     .17       0
Bank Sta=4939.7,5076.7
XS Rating Curve= 0 ,0
Exp/Cntr=0.3,0.1

Type RM Length L Ch R = 1 ,27000   ,182,182,182
BEGIN DESCRIPTION:
LITTLE LAKE CREEK 54.0
END DESCRIPTION:
XS GIS Cut Line= 3
      3765119.51     10152063.28      3765672.61      10149269.1
      3765084.77     10148330.61
#Sta/Elev= 30
  2151.6  218.18  2187.4  216.25  2271.5  212.96  2425.2   210.4  2637.4  209.05
  2796.1  208.89  2937.5  207.09  3112.1   208.1  3244.6  207.13  3408.8  203.33
  3511.3  203.77  3570.8  202.62  3642.2  203.71  3774.7  202.86  4151.9   203.6
  4396.5  200.15  4484.7  201.65    4580  200.22  5038.1     201  5071.9  199.13
    5108  199.13  5111.2     201  5634.5     201  5646.7  199.85  5771.2  201.78
  5800.1  202.31  5835.5  206.75    5981  222.24  6024.3  228.36  6107.4  235.56
#Mann= 7 ,-1 , 0
  2151.6     .17       0  2187.4     .15       0  2637.4     .11       0
  3112.1     .11       0  4484.7    .015       0  5771.2     .11       0
  5835.5     .17       0
#XS Ineff= 2 , 0
       0  3050.9  208.41               0
Permanent Ineff=
       F       F
Bank Sta=4484.7,5771.2
XS Rating Curve= 0 ,0
Exp/Cntr=0.3,0.1

Type RM Length L Ch R = 1 ,26818   ,86,86,86
BEGIN DESCRIPTION:
Mapping XS 79ae2818
END DESCRIPTION:
XS GIS Cut Line= 3
      3766634.26       10150452.      3765835.14     10149186.72
      3765271.86     10148312.12
#Sta/Elev= 30
  3503.5  214.03  4393.9  202.18  4516.6  205.35  4537.8     202  4553.1  205.59
  4574.3  202.08  4607.9  205.93  4675.3     205    4859  206.54  4871.9  209.78
  4887.2  205.55  4889.6   200.5  5066.2     201  5081.1  202.57  5096.3  210.74
  5117.4  206.24  5168.9  209.07  5226.3  204.49  5262.6  208.48  5356.4  203.44
  5371.6  207.18  5392.7  203.47    5429  207.63  5450.1   203.7  5579.3   205.4
  5631.7  208.99  5652.8  205.26  5819.2  207.17  5937.1  217.44  6040.3  226.19
#Mann= 9 ,-1 , 0
  3503.5     .11       0  4393.9     .15       0  4607.9     .11       0
  4675.3     .15       0    4859     .11       0  4871.9    .015       0
  5096.3     .11       0  5579.3     .15       0  5937.1     .17       0
#XS Ineff= 2 , 0
       0  4871.9  209.78  5096.3       0  210.74
Permanent Ineff=
       T       T
Bank Sta=4871.9,5096.3
XS Rating Curve= 0 ,0
Exp/Cntr=0.3,0.1