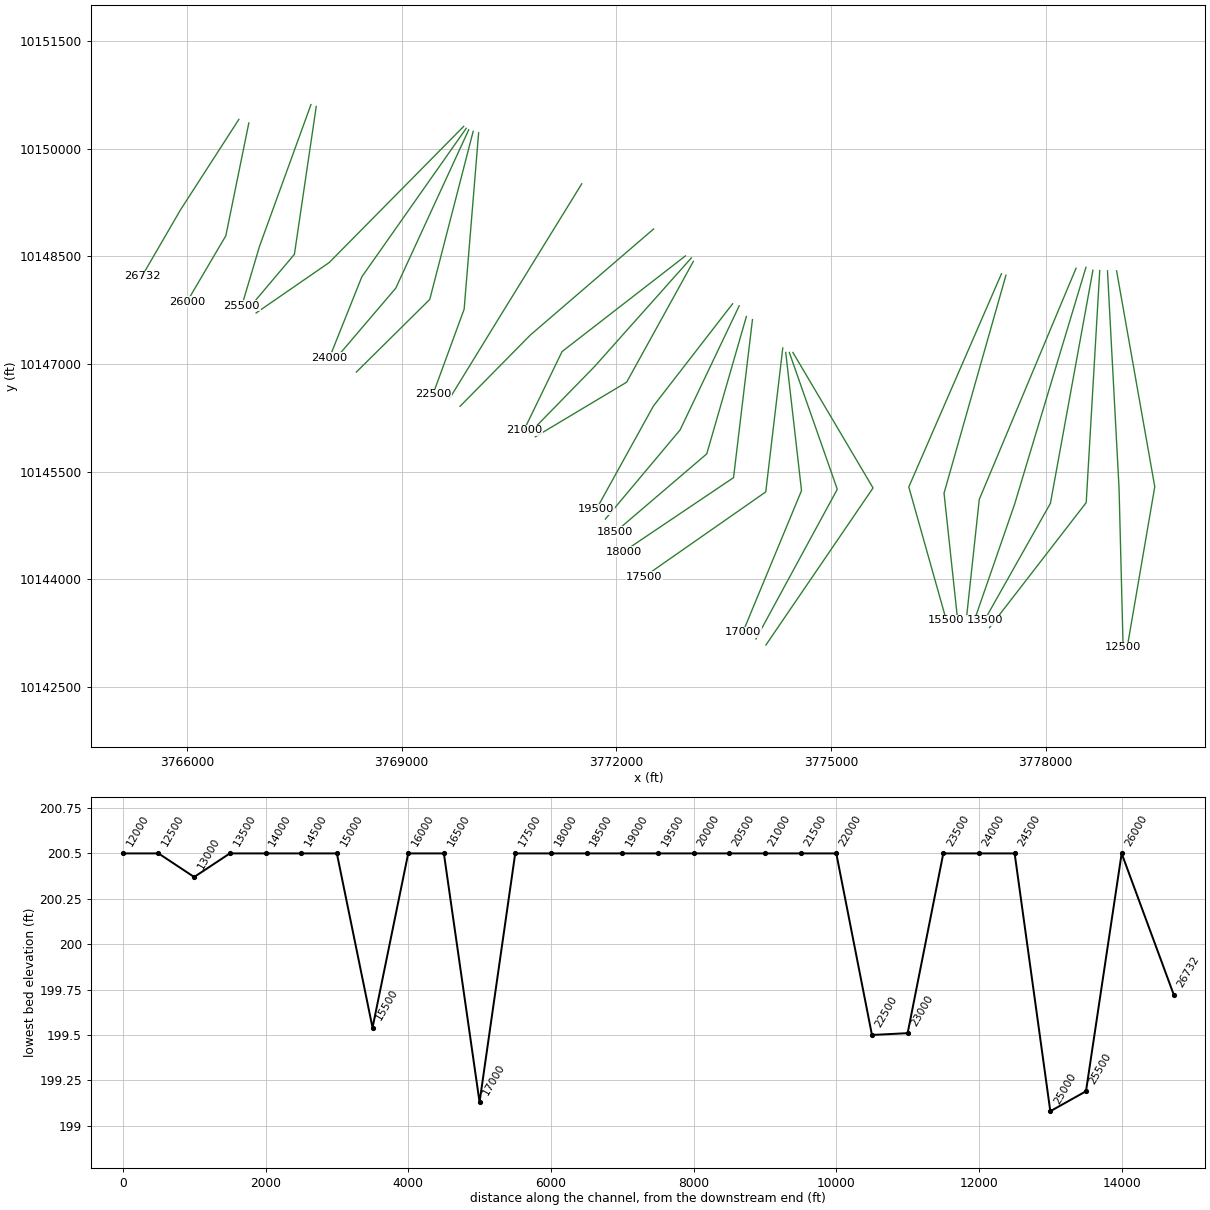
HEC-RAS study LITTLE LAKE CREEK.prj: LITTLE LAKE CREEK Base Level Engineering

--- LITTLE LAKE CREEK.g01 (geometry) --- (continued)

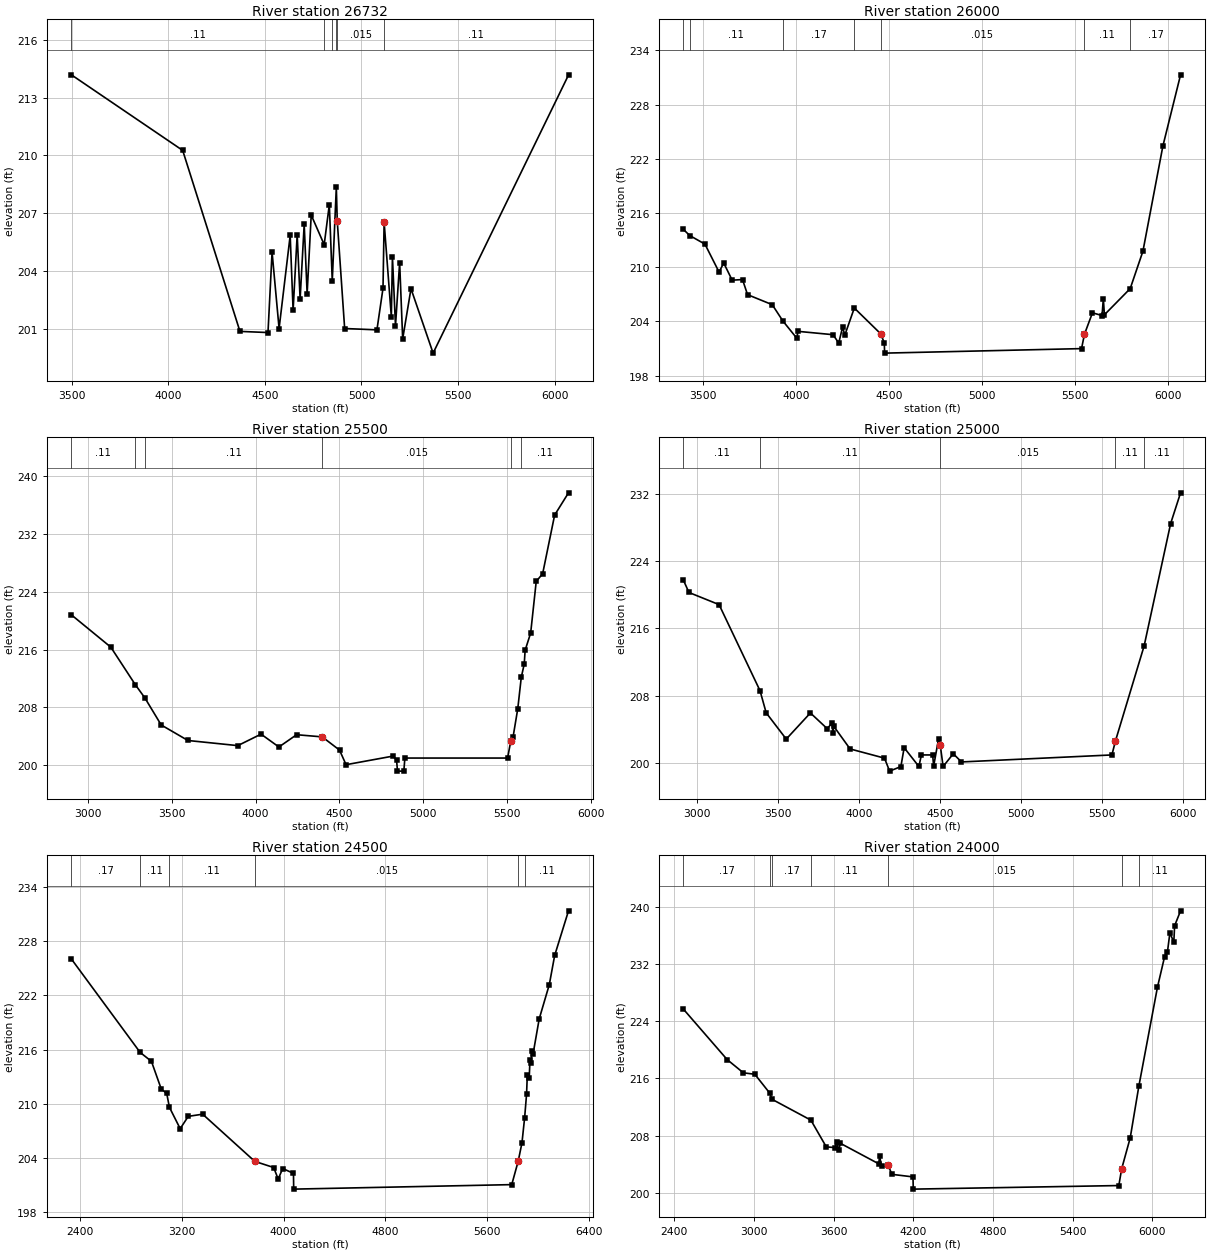
Type RM Length L Ch R = 1 ,26732   ,732,732,732
BEGIN DESCRIPTION:
LITTLE LAKE CREEK 53.0
END DESCRIPTION:
XS GIS Cut Line= 3
      3766726.52     10150408.11      3765911.44     10149148.05
      3765372.61     10148222.35
#Sta/Elev= 30
  3499.3  214.19  4075.1  210.26  4371.3  200.85  4516.4  200.79  4537.5  204.97
  4573.8     201  4631.2  205.84  4646.3  201.95  4667.4  205.87  4682.6  202.54
  4703.7  206.42  4718.9  202.81    4740   206.9  4807.1  205.36  4833.7  207.44
  4848.9  203.47  4869.9  208.35  4874.7  206.59    4913     201    5080  200.93
  5111.4  203.09  5117.2  206.53  5154.5  201.61  5160.2  204.73    5176  201.14
  5197.5  204.43  5213.2  200.46  5256.2  203.07  5370.6  199.72  6071.1  214.18
#Mann= 6 ,-1 , 0
  3499.3     .11       0  4807.1    .125       0  4848.9     .11       0
  4869.9     .11       0  4874.7    .015       0  5117.2     .11       0
#XS Ineff= 2 , 0
       0  4869.9  208.35  5117.2       0  206.53
Permanent Ineff=
       T       T
Bank Sta=4874.7,5117.2
XS Rating Curve= 0 ,0
Exp/Cntr=0.3,0.1

Type RM Length L Ch R = 1 ,26000   ,500,500,500
BEGIN DESCRIPTION:
LITTLE LAKE CREEK 52.0
END DESCRIPTION:
XS GIS Cut Line= 3
      3766866.12     10150358.54      3766544.96     10148787.63
      3766002.65     10147867.68
#Sta/Elev= 30
  3396.6  214.18  3430.3  213.51  3512.1  212.56  3587.9  209.47    3613  210.47
  3658.4  208.57    3714  208.64    3741  206.97  3873.7  205.86  3931.1  204.05
  4006.4  202.13  4011.8  202.91  4200.4  202.54    4231  201.62  4251.4  203.35
  4264.2  202.52  4314.7  205.49  4455.5  202.66  4475.9  201.65  4477.5   200.5
  5535.8     201  5551.5  202.59  5594.4  204.96  5646.1  204.66  5652.9  206.53
  5658.7  204.74  5797.3  207.64  5865.7  211.78    5973  223.42  6067.9  231.29
#Mann= 7 ,-1 , 0
  3396.6     .17       0  3430.3     .11       0  3931.1     .17       0
  4314.7     .11       0  4455.5    .015       0  5551.5     .11       0
  5797.3     .17       0
Bank Sta=4455.5,5551.5
XS Rating Curve= 0 ,0
Exp/Cntr=0.3,0.1

Type RM Length L Ch R = 1 ,25500   ,500,500,500
BEGIN DESCRIPTION:
LITTLE LAKE CREEK 51.0
END DESCRIPTION:
XS GIS Cut Line= 3
      3767734.17     10150614.63        3767016.     10148641.78
      3766767.85     10147811.05
#Sta/Elev= 30
  2900.5  220.82  3135.7  216.35  3282.3  211.14  3339.1  209.32  3436.4  205.58
    3596  203.43  3893.5  202.72  4032.3  204.31  4138.8  202.53  4244.5  204.23
  4397.4  203.93  4500.6   202.1  4539.6  200.08  4819.8  201.27  4841.1  200.71
  4846.4  199.19  4884.3  199.19  4890.6     201  5503.5     201  5522.6  203.37
  5536.6  203.97  5564.3  207.84  5585.2  212.18  5602.9  214.02  5608.1  215.91
  5641.2  218.31  5674.4  225.45  5712.7  226.51  5784.2  234.63    5867  237.71
#Mann= 6 ,-1 , 0
  2900.5     .11       0  3282.3     .17       0  3339.1     .11       0
  4397.4    .015       0  5522.6     .11       0  5585.2     .11       0
Bank Sta=4397.4,5522.6
XS Rating Curve= 0 ,0
Exp/Cntr=0.3,0.1

Type RM Length L Ch R = 1 ,25000   ,500,500,500
BEGIN DESCRIPTION:
LITTLE LAKE CREEK 50.0
END DESCRIPTION:
XS GIS Cut Line= 3
      3767807.96     10150588.59      3767502.98     10148528.44
      3766866.12     10147776.11
#Sta/Elev= 30
  2917.4  221.72  2951.3  220.27  3137.3  218.83    3390  208.62  3427.9     206
  3551.8  202.88  3700.9  205.98  3804.5  204.12  3834.8  204.78  3839.9  203.55
    3845   204.4    3946  201.71  4158.3  200.62  4189.8  199.08  4259.4  199.62
  4279.6  201.86  4370.6  199.63    4386     201  4455.6     201  4461.6  199.67
  4491.9  202.88    4502  202.23    4520  199.63  4582.9  201.14  4633.4  200.17
  5561.9     201    5584  202.67  5760.8  213.93  5924.5  228.45  5985.7  232.09
#Mann= 5 ,-1 , 0
  2917.4     .11       0    3390     .11       0    4502    .015       0
    5584     .11       0  5760.8     .11       0
Bank Sta=4502,5584
XS Rating Curve= 0 ,0
Exp/Cntr=0.3,0.1

Type RM Length L Ch R = 1 ,24500   ,500,500,500
BEGIN DESCRIPTION:
LITTLE LAKE CREEK 49.0
END DESCRIPTION:
XS GIS Cut Line= 3
      3769867.86     10150311.08      3767989.82     10148414.48
      3766967.89      10147711.1
#Sta/Elev= 30
  2330.9  226.05  2871.6  215.68  2960.3  214.69    3038   211.6  3080.4  211.14
  3101.7  209.59  3186.5  207.21  3250.1  208.58  3363.3  208.82  3773.4  203.58
  3921.9   202.9  3957.3  201.61  3992.6  202.79  4077.5  202.25  4079.3   200.5
  5794.2     201    5845   203.6  5874.7  205.65  5895.7  208.45  5910.6  211.01
  5916.6  213.18  5931.5  212.82  5937.6   214.8  5946.4  214.45  5952.5  215.87
  5961.3  215.46    6010  219.39  6089.8  223.22  6131.7  226.44  6240.6   231.4
#Mann= 6 ,-1 , 0
  2330.9     .17       0  2871.6     .11       0  3101.7     .11       0
  3773.4    .015       0    5845     .11       0  5895.7     .11       0
#XS Ineff= 2 , 0
       0  3398.7  208.31               0
Permanent Ineff=
       F       F
Bank Sta=3773.4,5845
XS Rating Curve= 0 ,0
Exp/Cntr=0.3,0.1

Type RM Length L Ch R = 1 ,24000   ,500,500,500
BEGIN DESCRIPTION:
LITTLE LAKE CREEK 48.0
END DESCRIPTION:
XS GIS Cut Line= 3
      3769903.44     10150283.91      3768445.35      10148215.6
      3767993.73     10147089.48
#Sta/Elev= 30
  2469.4  225.67  2798.6  218.62  2920.6  216.77  3006.8  216.57  3121.4  213.88
  3135.2  213.08  3429.2  210.15    3545  206.41  3610.3  206.31    3623  207.13
  3637.3  205.95  3652.1   206.9  3940.3  204.04  3946.4  205.14  3961.2  203.73
  4011.7  203.81    4039  202.57    4198  202.21  4200.4   200.5  5748.3     201
  5769.8  203.34  5834.3  207.69  5899.1   214.9  6039.2  228.74  6093.1  233.02
  6114.6  233.69  6132.9  236.35  6162.5  235.05  6168.5  237.34  6213.3  239.43
#Mann= 7 ,-1 , 0
  2469.4     .17       0  3121.4     .11       0  3135.2     .17       0
  3429.2     .11       0  4011.7    .015       0  5769.8     .11       0
  5899.1     .11       0
#XS Ineff= 2 , 0
       0  3652.1   206.9               0
Permanent Ineff=
       F       F
Bank Sta=4011.7,5769.8
XS Rating Curve= 0 ,0
Exp/Cntr=0.3,0.1

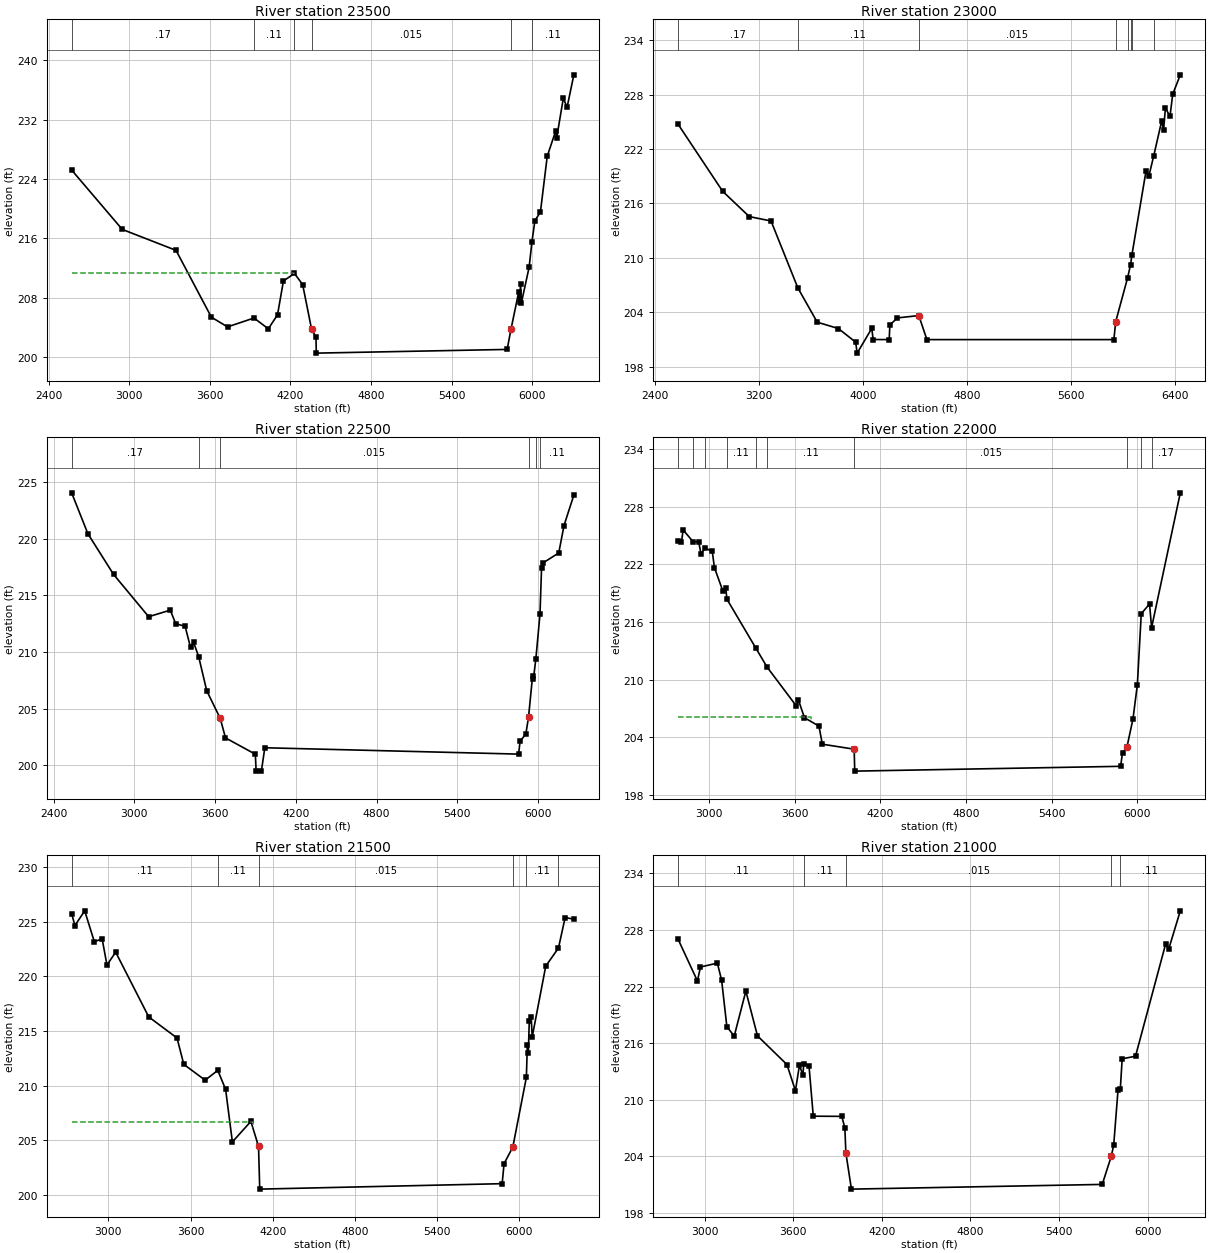
Type RM Length L Ch R = 1 ,23500   ,500,500,500
BEGIN DESCRIPTION:
LITTLE LAKE CREEK 47.0
END DESCRIPTION:
XS GIS Cut Line= 3
      3769938.17     10150263.09      3768919.69     10148057.48
      3768067.85     10147061.07
#Sta/Elev= 30
  2570.6  225.21  2947.3   217.2    3348  214.37  3611.3  205.35  3731.6  204.04
  3928.8  205.24  4035.3  203.78  4103.9  205.67  4147.9  210.24  4229.8  211.25
  4291.1  209.76  4357.2  203.76  4390.2  202.63  4392.8   200.5  5814.2     201
  5842.7  203.72  5899.8   208.7  5906.4  207.42  5914.1  209.85  5920.6  207.32
  5977.7  212.08  5998.6  215.47  6020.5  218.35  6062.2  219.57  6112.8  227.08
  6176.4  230.52    6183  229.54  6232.4  234.88  6260.9   233.7  6310.9  238.06
#Mann= 6 ,-1 , 0
  2570.6     .17       0  3928.8     .11       0  4229.8     .11       0
  4357.2    .015       0  5842.7     .11       0  5998.6     .11       0
#XS Ineff= 2 , 0
       0  4224.3  211.31               0
Permanent Ineff=
       F       F
Bank Sta=4357.2,5842.7
XS Rating Curve= 0 ,0
Exp/Cntr=0.3,0.1

Type RM Length L Ch R = 1 ,23000   ,500,500,500
BEGIN DESCRIPTION:
LITTLE LAKE CREEK 46.0
END DESCRIPTION:
XS GIS Cut Line= 3
      3770000.67     10150242.24       3769394.3     10147900.16
       3768368.7     10146888.07
#Sta/Elev= 30
  2580.7  224.73  2922.8  217.35  3127.4  214.56    3295  214.07  3501.3  206.69
  3650.1  202.92  3812.6  202.22  3945.4  200.72    3957  199.51  4069.4  202.24
  4079.7  201.01  4203.2     201  4208.3  202.61  4265.7  203.39  4430.9  203.65
  4492.9     201  5930.3     201  5944.4  202.98  6036.3  207.84  6058.8  209.27
  6068.2  210.27  6177.7  219.61    6199  219.01  6235.6  221.19    6298  225.11
  6312.1  224.06  6326.3  226.51  6361.6  225.62  6382.8  228.05  6440.9  230.18
#Mann= 8 ,-1 , 0
  2580.7     .17       0  3501.3     .11       0  4430.9    .015       0
  5944.4     .11       0  6036.3    .125       0  6058.8     .11       0
  6068.2    .125       0  6235.6     .11       0
Bank Sta=4430.9,5944.4
XS Rating Curve= 0 ,0
Exp/Cntr=0.3,0.1

Type RM Length L Ch R = 1 ,22500   ,500,500,500
BEGIN DESCRIPTION:
LITTLE LAKE CREEK 45.0
END DESCRIPTION:
XS GIS Cut Line= 3
      3770077.07     10150221.46      3769874.48      10147763.6
      3769438.27     10146575.86
#Sta/Elev= 30
  2533.8  224.03  2654.6  220.42  2845.2  216.84  3106.1  213.11  3266.7  213.69
  3306.8   212.5    3377  212.26  3417.2   210.4  3439.8  210.85  3477.4   209.6
  3537.6  206.58  3637.9  204.15  3676.9  202.43  3898.8  200.99  3904.5   199.5
  3943.6   199.5    3969  201.56  5854.9     201  5865.6  202.12  5908.7  202.78
  5928.6  204.25    5959  207.92  5964.4  207.58  5982.8  209.36  6013.8  213.33
  6025.4  217.39    6036  217.85  6153.2  218.73  6192.3  221.15  6265.3  223.83
#Mann= 6 ,-1 , 0
  2533.8     .17       0  3477.4     .11       0  3637.9    .015       0
  5928.6     .11       0  5982.8     .17       0  6013.8     .11       0
Bank Sta=3637.9,5928.6
XS Rating Curve= 0 ,0
Exp/Cntr=0.3,0.1

Type RM Length L Ch R = 1 ,22000   ,500,500,500
BEGIN DESCRIPTION:
LITTLE LAKE CREEK 44.0
END DESCRIPTION:
XS GIS Cut Line= 3
      3771517.84     10149511.05      3770351.15      10147624.1
      3769668.27     10146514.61
#Sta/Elev= 30
  2781.5  224.45  2804.6  224.27  2816.7  225.57  2887.1  224.34  2926.3  224.31
  2941.7  223.08    2971  223.69  3020.8  223.34  3036.2  221.65  3094.1  219.27
  3115.4  219.52  3123.9  218.37  3324.4  213.34    3405  211.32  3609.5  207.29
  3624.9   207.9  3667.4  206.05  3769.1  205.18  3792.6   203.3    4016  202.78
  4019.9   200.5  5884.2     201  5897.6  202.42  5928.5     203    5971  205.93
  6001.7  209.49    6029  216.86    6087  217.88  6101.5  215.43  6302.8  229.43
#Mann= 10 ,-1 , 0
  2781.5    .125       0  2887.1     .11       0    2971    .125       0
  3123.9     .11       0  3324.4     .17       0    3405     .11       0
    4016    .015       0  5928.5     .11       0    6029     .11       0
  6101.5     .17       0
#XS Ineff= 2 , 0
       0  3710.3  206.08               0
Permanent Ineff=
       F       F
Bank Sta=4016,5928.5
XS Rating Curve= 0 ,0
Exp/Cntr=0.3,0.1

Type RM Length L Ch R = 1 ,21500   ,500,500,500
BEGIN DESCRIPTION:
LITTLE LAKE CREEK 43.0
END DESCRIPTION:
XS GIS Cut Line= 3
      3772521.52     10148881.17      3770800.21     10147404.53
      3769817.88      10146411.1
#Sta/Elev= 30
  2732.1  225.76    2756  224.67  2827.3  226.02  2897.6  223.19  2954.6  223.45
  2989.8  221.05  3053.4  222.23  3294.9  216.29  3501.1  214.36  3550.6  211.94
  3706.4  210.49  3798.6  211.39  3855.7  209.65  3905.1  204.83  4040.1  206.71
    4096  204.42  4104.7   200.5  5873.9     201    5888  202.84  5951.6  204.35
  6050.6  210.74  6057.8  213.71  6064.8  212.97  6071.9   215.9    6086  216.26
  6093.1  214.45  6192.1  220.95  6284.9  222.61  6333.5   225.4  6397.1  225.26
#Mann= 6 ,-1 , 0
  2732.1     .11       0  3798.6     .11       0    4096    .015       0
  5951.6     .11       0  6050.6     .11       0  6284.9     .17       0
#XS Ineff= 2 , 0
       0  4054.3  206.67               0
Permanent Ineff=
       F       F
Bank Sta=4096,5951.6
XS Rating Curve= 0 ,0
Exp/Cntr=0.3,0.1

Type RM Length L Ch R = 1 ,21000   ,500,500,500
BEGIN DESCRIPTION:
LITTLE LAKE CREEK 42.0
END DESCRIPTION:
XS GIS Cut Line= 3
      3772965.96     10148506.16      3771242.56     10147173.27
      3770709.13     10146075.84
#Sta/Elev= 30
  2821.3  227.01  2951.9  222.59  2972.7  224.07  3086.8  224.48  3115.8  222.67
  3151.1  217.75  3200.9  216.73  3279.7  221.51  3358.5  216.76  3557.7  213.72
  3615.3  210.95  3642.8  213.68  3665.5  212.57  3671.8  213.77  3707.1  213.59
  3736.1  208.24    3929  208.22  3949.8     207  3956.7  204.34  3994.3   200.5
  5691.8     201  5753.6  204.01  5769.6  205.21  5798.7  211.03  5814.1   211.1
  5826.8  214.33    5917   214.6    6120  226.46  6142.6  226.02  6220.2  230.03
#Mann= 5 ,-1 , 0
  2821.3     .11       0  3671.8     .11       0  3956.7    .015       0
  5753.6     .11       0  5814.1     .11       0
Bank Sta=3956.7,5753.6
XS Rating Curve= 0 ,0
Exp/Cntr=0.3,0.1

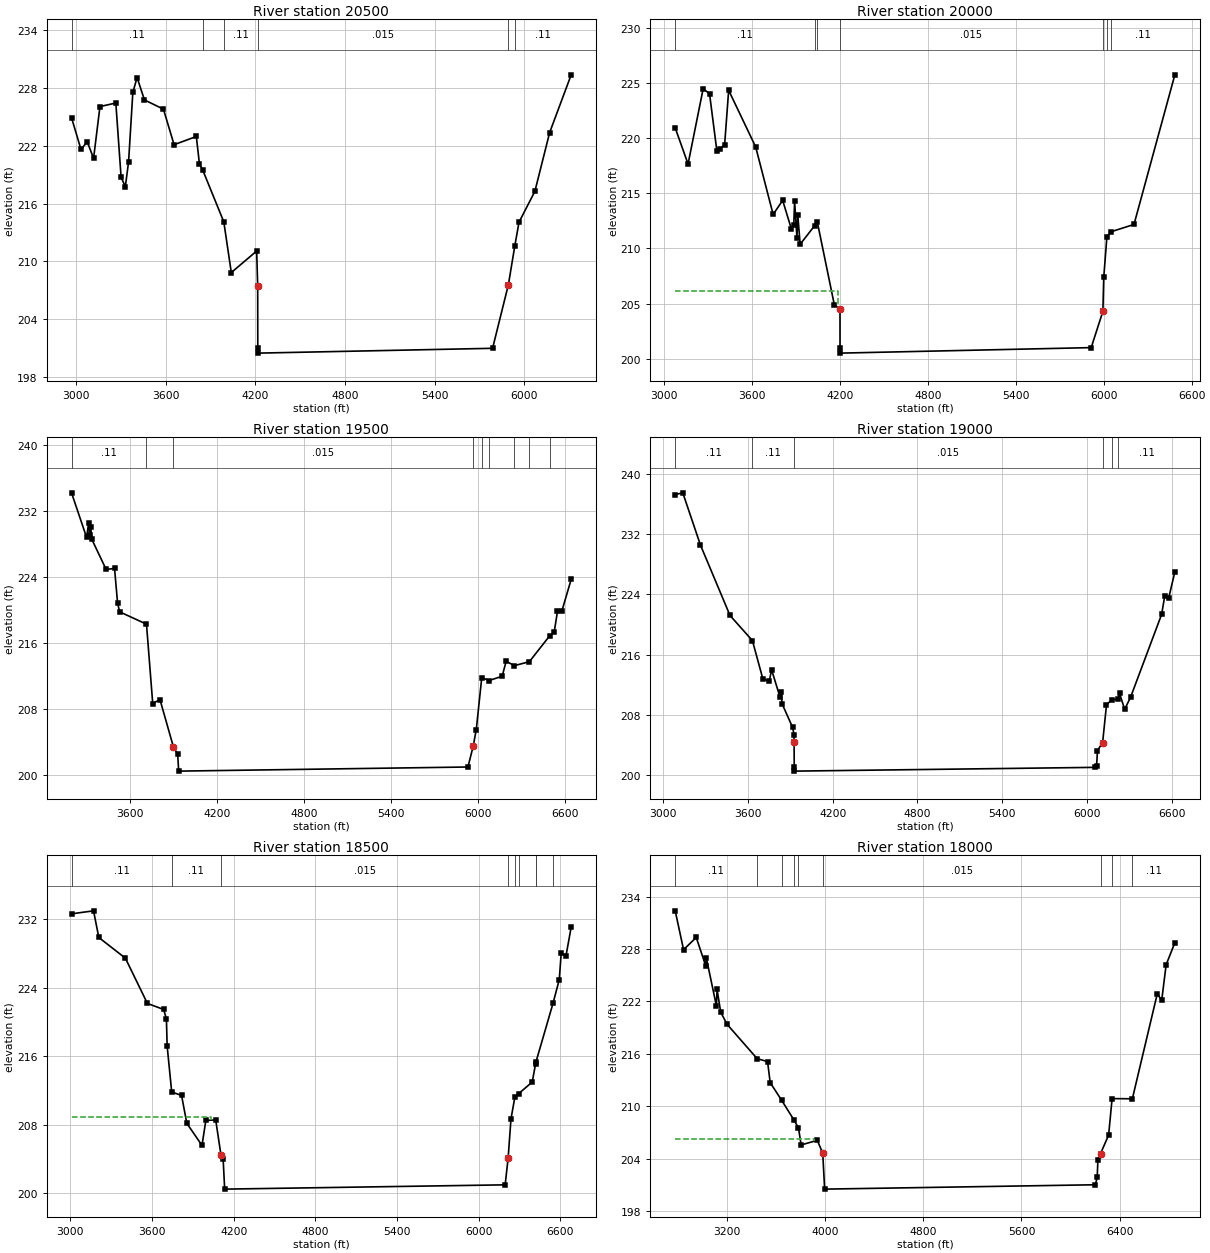
Type RM Length L Ch R = 1 ,20500   ,500,500,500
BEGIN DESCRIPTION:
LITTLE LAKE CREEK 41.0
END DESCRIPTION:
XS GIS Cut Line= 3
      3773049.25     10148478.34      3771697.34     10146965.48
      3770778.48     10146027.01
#Sta/Elev= 30
  2971.1   224.9  3034.3  221.61  3076.1   222.4  3118.7  220.69  3161.3  226.05
  3267.5  226.42  3302.7  218.73  3331.1  217.75  3352.8  220.33  3381.2  227.51
  3409.6  229.06  3458.9  226.74    3586  225.78  3657.1   222.1  3805.9  222.95
  3826.8  220.11  3849.9  219.43  3989.8   214.1  4039.9  208.85  4209.6  211.08
  4216.3  207.44  4217.1     201  4218.1   200.5  5787.7     201  5893.7  207.61
  5936.2   211.6  5964.5  214.07  6070.5  217.26  6169.5  223.36  6313.4  229.34
#Mann= 6 ,-1 , 0
  2971.1     .11       0  3849.9    .125       0  3989.8     .11       0
  4216.3    .015       0  5893.7     .11       0  5936.2     .11       0
Bank Sta=4216.3,5893.7
XS Rating Curve= 0 ,0
Exp/Cntr=0.3,0.1

Type RM Length L Ch R = 1 ,20000   ,500,500,500
BEGIN DESCRIPTION:
LITTLE LAKE CREEK 40.0
END DESCRIPTION:
XS GIS Cut Line= 3
      3773077.06     10148429.76      3772145.01     10146746.48
      3770869.35     10145985.69
#Sta/Elev= 30
  3075.9  220.93  3163.7  217.65  3266.7  224.48  3310.2  224.03  3360.2  218.84
    3383  219.04  3413.3  219.41  3440.7  224.34  3625.1   219.2  3744.1  213.08
  3809.4  214.35  3868.9  211.75    3885  212.14  3890.7  214.26  3906.7  210.94
  3912.5  213.01  3928.5  210.37  4026.8  212.05    4046  212.37    4162  204.87
 4200.45  204.52  4200.6     201  4201.6   200.5  5914.5     201  5994.3  204.29
  6000.2  207.37  6021.6  211.04  6050.4  211.51  6206.5  212.17  6485.3  225.74
#Mann= 7 ,-1 , 0
  3075.9     .11       0  4026.8    .125       0    4046     .11       0
 4200.45    .015       0  5994.3     .11       0  6021.6    .125       0
  6050.4     .11       0
#XS Ineff= 2 , 0
       0  4183.8   206.1               0
Permanent Ineff=
       F       F
Bank Sta=4200.45,5994.3
XS Rating Curve= 0 ,0
Exp/Cntr=0.3,0.1

Type RM Length L Ch R = 1 ,19500   ,500,500,500
BEGIN DESCRIPTION:
LITTLE LAKE CREEK 39.0
END DESCRIPTION:
XS GIS Cut Line= 3
      3773625.65     10147839.45      3772519.34       10146415.
      3771722.91      10144978.4
#Sta/Elev= 30
  3196.4  234.19  3300.4  228.79  3314.9  230.59  3321.2  229.07  3329.3  230.02
  3335.7  228.59  3435.2  224.91  3493.2  225.04    3514  220.84  3528.5  219.78
  3713.5  218.29  3756.5  208.68  3806.3  209.17  3899.5  203.41  3928.5  202.54
  3935.5   200.5  5930.6     201  5966.4  203.49  5988.1  205.52  6025.9  211.83
  6076.8  211.47  6166.7  211.99  6194.2   213.8  6251.1  213.27  6354.3  213.75
  6493.5  216.86  6525.2  217.29  6548.1  219.84  6578.8   219.9  6642.6  223.71
#Mann= 9 ,-1 , 0
  3196.4     .11       0  3713.5     .11       0  3899.5    .015       0
  5966.4     .11       0  6025.9     .11       0  6076.8    .125       0
  6251.1     .11       0  6354.3    .125       0  6493.5     .11       0
Bank Sta=3899.5,5966.4
XS Rating Curve= 0 ,0
Exp/Cntr=0.3,0.1

Type RM Length L Ch R = 1 ,19000   ,500,500,500
BEGIN DESCRIPTION:
LITTLE LAKE CREEK 38.0
END DESCRIPTION:
XS GIS Cut Line= 3
      3773717.84     10147811.05       3772892.4     10146082.09
      3771847.89     10144839.47
#Sta/Elev= 30
  3084.1  237.26    3138  237.49  3262.5  230.57  3472.3  221.19  3631.1  217.85
  3704.7  212.78    3750  212.44  3767.2  213.96  3826.5  210.34  3835.2  211.05
  3840.8  209.47  3915.2  206.34    3926  205.36  3926.2   204.4  3927.3     201
  3928.3   200.5  6054.5     201  6068.8  201.16  6075.4  203.24  6111.7   204.3
  6139.1  209.29  6175.5     210  6221.1  210.04  6231.4  210.83  6267.8  208.72
  6309.5  210.31  6529.8  221.34  6551.4  223.75    6580  223.53  6623.3  226.98
#Mann= 6 ,-1 , 0
  3084.1     .11       0  3631.1     .11       0  3926.2    .015       0
  6111.7     .11       0  6175.5    .125       0  6221.1     .11       0
Bank Sta=3926.2,6111.7
XS Rating Curve= 0 ,0
Exp/Cntr=0.3,0.1

Type RM Length L Ch R = 1 ,18500   ,500,500,500
BEGIN DESCRIPTION:
LITTLE LAKE CREEK 37.0
END DESCRIPTION:
XS GIS Cut Line= 3
      3773817.86     10147661.09      3773264.65     10145748.28
      3771986.76     10144658.91
#Sta/Elev= 30
  3008.8   232.6  3170.5  232.95  3209.3  229.84  3404.4  227.43  3566.2  222.15
  3685.5  221.45  3705.9  220.34  3711.1  217.21  3744.7  211.82  3817.1  211.43
  3855.9  208.17  3967.2   205.6  3995.6  208.51    4068  208.57  4106.8  204.46
  4122.7  203.96  4133.8   200.5  6194.2     201  6216.2  204.14  6237.1   208.7
  6265.6  211.23  6294.4  211.65    6393  212.98  6417.2  215.06    6420   215.3
  6545.5  222.15  6591.7  224.92    6606  228.03  6641.1   227.7  6679.2  231.04
#Mann= 9 ,-1 , 0
  3008.8     .11       0  3744.7     .11       0  4106.8    .015       0
  6216.2     .11       0  6265.6     .11       0  6294.4    .125       0
  6417.2     .11       0    6420    .125       0  6545.5     .11       0
#XS Ineff= 2 , 0
       0  4034.4  208.89               0
Permanent Ineff=
       F       F
Bank Sta=4106.8,6216.2
XS Rating Curve= 0 ,0
Exp/Cntr=0.3,0.1

Type RM Length L Ch R = 1 ,18000   ,500,500,500
BEGIN DESCRIPTION:
LITTLE LAKE CREEK 36.0
END DESCRIPTION:
XS GIS Cut Line= 3
      3773902.94     10147618.69      3773638.46     10145416.52
      3772103.92     10144386.62
#Sta/Elev= 30
    2782  232.38  2850.1  227.93  2953.2  229.33  3030.3  226.09  3035.4  226.98
  3117.6  221.48  3122.6  223.39  3152.3  220.77  3204.8  219.37  3449.3  215.44
  3533.7  215.11  3555.1   212.7  3648.2  210.68  3747.7  208.44  3785.4  207.51
  3806.9  205.56  3937.9  206.09 3982.64  204.63  3998.2   200.5  6201.1     201
  6216.1  201.84  6222.1  203.88  6243.1  204.57  6309.1  206.68  6337.5  210.87
  6502.4  210.85  6705.2  222.88  6741.2  222.12  6777.2   226.2  6848.1  228.73
#Mann= 9 ,-1 , 0
    2782     .11       0  3449.3    .125       0  3648.2     .11       0
  3747.7    .125       0  3785.4     .11       0 3982.64    .015       0
  6243.1     .11       0  6337.5    .125       0  6502.4     .11       0
#XS Ineff= 2 , 0
       0  3907.7  206.23               0
Permanent Ineff=
       F       F
Bank Sta=3982.64,6243.1
XS Rating Curve= 0 ,0
Exp/Cntr=0.3,0.1

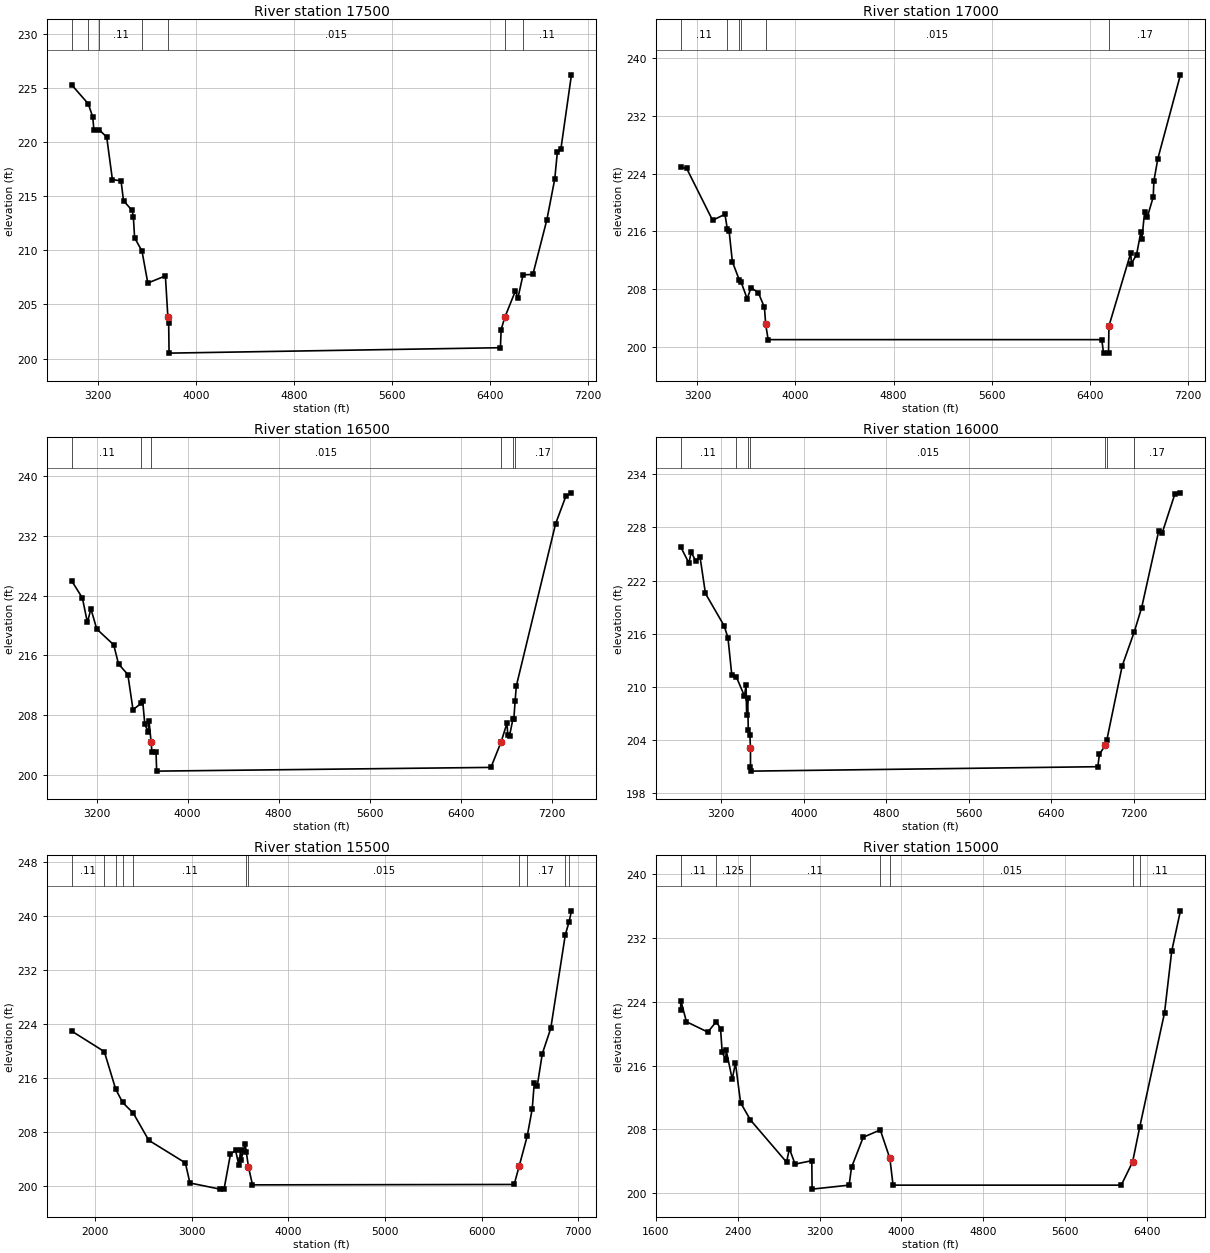
Type RM Length L Ch R = 1 ,17500   ,500,500,500
BEGIN DESCRIPTION:
LITTLE LAKE CREEK 35.0
END DESCRIPTION:
XS GIS Cut Line= 3
      3774326.55     10147222.87      3774088.74     10145217.72
      3772392.49     10144037.04
#Sta/Elev= 30
  2980.8  225.28  3117.7  223.51  3153.8  222.31  3163.9  221.08  3205.1  221.14
  3268.3  220.44  3314.9  216.51  3385.4  216.41  3405.6  214.57    3476  213.67
  3486.1  213.08  3496.2  211.15  3556.6  209.92  3604.2  206.97  3747.9  207.63
  3768.1  203.84  3774.7  203.26    3778   200.5  6486.1     201  6492.2  202.68
  6521.9   203.8  6608.3  206.23  6629.2  205.58  6671.1  207.73  6751.4  207.76
  6865.2  212.78  6930.3  216.57  6951.2  219.03  6980.9  219.38  7066.7  226.19
#Mann= 7 ,-1 , 0
  2980.8     .11       0  3117.7    .125       0  3205.1     .11       0
  3556.6     .11       0  3768.1    .015       0  6521.9     .11       0
  6671.1     .11       0
#XS Ineff= 2 , 0
       0                  6608.3       0  206.23
Permanent Ineff=
       F       F
Bank Sta=3768.1,6521.9
XS Rating Curve= 0 ,0
Exp/Cntr=0.3,0.1

Type RM Length L Ch R = 1 ,17000   ,500,500,500
BEGIN DESCRIPTION:
LITTLE LAKE CREEK 34.0
END DESCRIPTION:
XS GIS Cut Line= 3
      3774367.85      10147161.1       3774588.4      10145236.1
      3773767.85     10143261.07
#Sta/Elev= 30
  3062.4  224.91  3112.8  224.73  3324.1  217.54  3424.8  218.38  3443.8  216.36
  3458.9  216.03  3485.2   211.8  3542.3  209.25  3555.6  209.02    3606  206.67
  3637.3  208.19  3696.6  207.52  3746.9  205.46  3756.9  203.11  3777.1     201
  6497.3     201    6512  199.13  6552.5  199.13  6555.8  202.89  6733.7  213.02
  6739.1  211.54  6781.3  212.79  6816.1  215.91  6824.7  214.99  6846.3  218.65
  6869.2  218.02  6916.9  220.77  6922.3  222.99  6954.6  226.09  7138.7  237.71
#Mann= 6 ,-1 , 0
  3062.4     .11       0  3443.8    .125       0  3542.3     .11       0
  3555.6     .11       0  3756.9    .015       0  6555.8     .17       0
Bank Sta=3756.9,6555.8
XS Rating Curve= 0 ,0
Exp/Cntr=0.3,0.1

Type RM Length L Ch R = 1 ,16500   ,500,500,500
BEGIN DESCRIPTION:
LITTLE LAKE CREEK 33.0
END DESCRIPTION:
XS GIS Cut Line= 3
      3774417.84     10147161.09      3775088.06     10145254.46
       3773952.2     10143168.46
#Sta/Elev= 30
    2979  226.03  3074.4   223.7  3118.4  220.43  3149.4  222.24  3200.7  219.54
    3350  217.42  3392.4  214.85  3474.2  213.44  3519.6  208.73  3592.9   209.6
  3604.4   209.9  3623.8  206.76  3654.8   205.7  3660.1  207.26  3678.6  204.41
  3685.8  203.11  3722.1  203.06  3727.5   200.5  6667.4     201  6757.4  204.44
  6808.9  206.96  6814.6  205.39  6830.8  205.22  6859.8  207.44  6868.8   207.5
  6879.8   209.9  6890.6  211.92  7235.6  233.63  7326.5  237.35  7375.2  237.79
#Mann= 6 ,-1 , 0
    2979     .11       0  3592.9     .11       0  3678.6    .015       0
  6757.4     .11       0  6859.8     .11       0  6879.8     .17       0
#XS Ineff= 2 , 0
       0  3660.1  207.26  6808.9       0  206.96
Permanent Ineff=
       F       F
Bank Sta=3678.6,6757.4
XS Rating Curve= 0 ,0
Exp/Cntr=0.3,0.1

Type RM Length L Ch R = 1 ,16000   ,500,500,500
BEGIN DESCRIPTION:
LITTLE LAKE CREEK 32.0
END DESCRIPTION:
XS GIS Cut Line= 3
      3774467.83     10147161.11      3775587.72     10145272.82
      3774091.17     10143085.01
#Sta/Elev= 30
  2804.6  225.85    2886  223.98    2908  225.22  2950.8  224.25  2993.7  224.69
  3046.3  220.55  3227.6   216.9  3264.6  215.55  3301.7  211.35  3344.6  211.17
  3424.4  208.98    3440  210.22  3445.8  206.83  3455.6   208.8  3461.5  205.16
  3477.1  204.55  3482.9   203.1    3483     201    3484   200.5  6850.2     201
  6865.1   202.4    6922   203.4  6936.9  203.99  7086.5  212.39  7202.9  216.21
  7274.8  218.95  7439.3  227.56  7475.2  227.43  7597.8  231.81  7650.7  231.91
#Mann= 7 ,-1 , 0
  2804.6     .11       0  3344.6    .125       0  3455.6     .11       0
  3482.9    .015       0    6922     .11       0  6936.9     .11       0
  7202.9     .17       0
Bank Sta=3482.9,6922
XS Rating Curve= 0 ,0
Exp/Cntr=0.3,0.1

Type RM Length L Ch R = 1 ,15500   ,500,500,500
BEGIN DESCRIPTION:
LITTLE LAKE CREEK 31.0
END DESCRIPTION:
XS GIS Cut Line= 3
      3777382.11     10148257.57      3776087.17     10145286.83
      3776611.28     10143431.12
#Sta/Elev= 30
  1759.3  222.94  2098.1  219.89  2215.7  214.34  2287.9  212.36    2397   210.8
  2557.8  206.77  2936.4  203.42  2983.2  200.45  3294.5  199.54  3336.3  199.54
  3402.7  204.73  3455.5  205.27    3490  203.06  3507.8  205.37  3513.2  203.91
  3554.6  206.21  3566.3  205.03    3589  202.81  3630.4  200.17  6336.1  200.23
    6388  202.95  6471.1  207.39  6523.1  211.45  6543.9  215.26    6575  214.84
    6627  219.58  6714.3  223.32  6865.1   237.2  6904.4  239.11  6928.3  240.72
#Mann= 11 ,-1 , 0
  1759.3     .11       0  2098.1    .125       0  2215.7     .11       0
  2287.9    .125       0    2397     .11       0  3566.3     .11       0
    3589    .015       0    6388     .11       0  6471.1     .17       0
  6865.1     .11       0  6904.4     .17       0
#XS Ineff= 2 , 0
       0  3554.6  206.21               0
Permanent Ineff=
       F       F
Bank Sta=3589,6388
XS Rating Curve= 0 ,0
Exp/Cntr=0.3,0.1

Type RM Length L Ch R = 1 ,15000   ,500,500,500
BEGIN DESCRIPTION:
LITTLE LAKE CREEK 30.0
END DESCRIPTION:
XS GIS Cut Line= 3
      3777444.61     10148236.74       3776579.6     10145200.14
      3776764.04     10143486.74
#Sta/Elev= 30
  1842.6  223.04  1846.2  224.14  1900.5  221.51  2109.1  220.21  2191.8  221.52
  2233.2  220.65  2249.7  217.66  2283.5  216.72  2288.7  217.93  2347.6  214.29
  2378.8  216.32  2429.3  211.34  2525.8  209.17  2877.9  203.89  2905.7  205.58
  2961.1  203.64  3124.4  204.07  3127.3   200.5  3488.9     201  3512.1  203.23
  3626.5  207.01  3792.9  207.93  3886.5  204.36  3917.7     201  6145.6     201
  6256.3  203.91  6326.7  208.34  6568.1  222.63  6638.5  230.39  6723.3  235.43
#Mann= 7 ,-1 , 0
  1842.6     .11       0  2191.8    .125       0  2525.8     .11       0
  3792.9     .11       0  3886.5    .015       0  6256.3     .11       0
  6326.7     .11       0
#XS Ineff= 2 , 0
       0  3792.9  207.93               0
Permanent Ineff=
       F       F
Bank Sta=3886.5,6256.3
XS Rating Curve= 0 ,0
Exp/Cntr=0.3,0.1

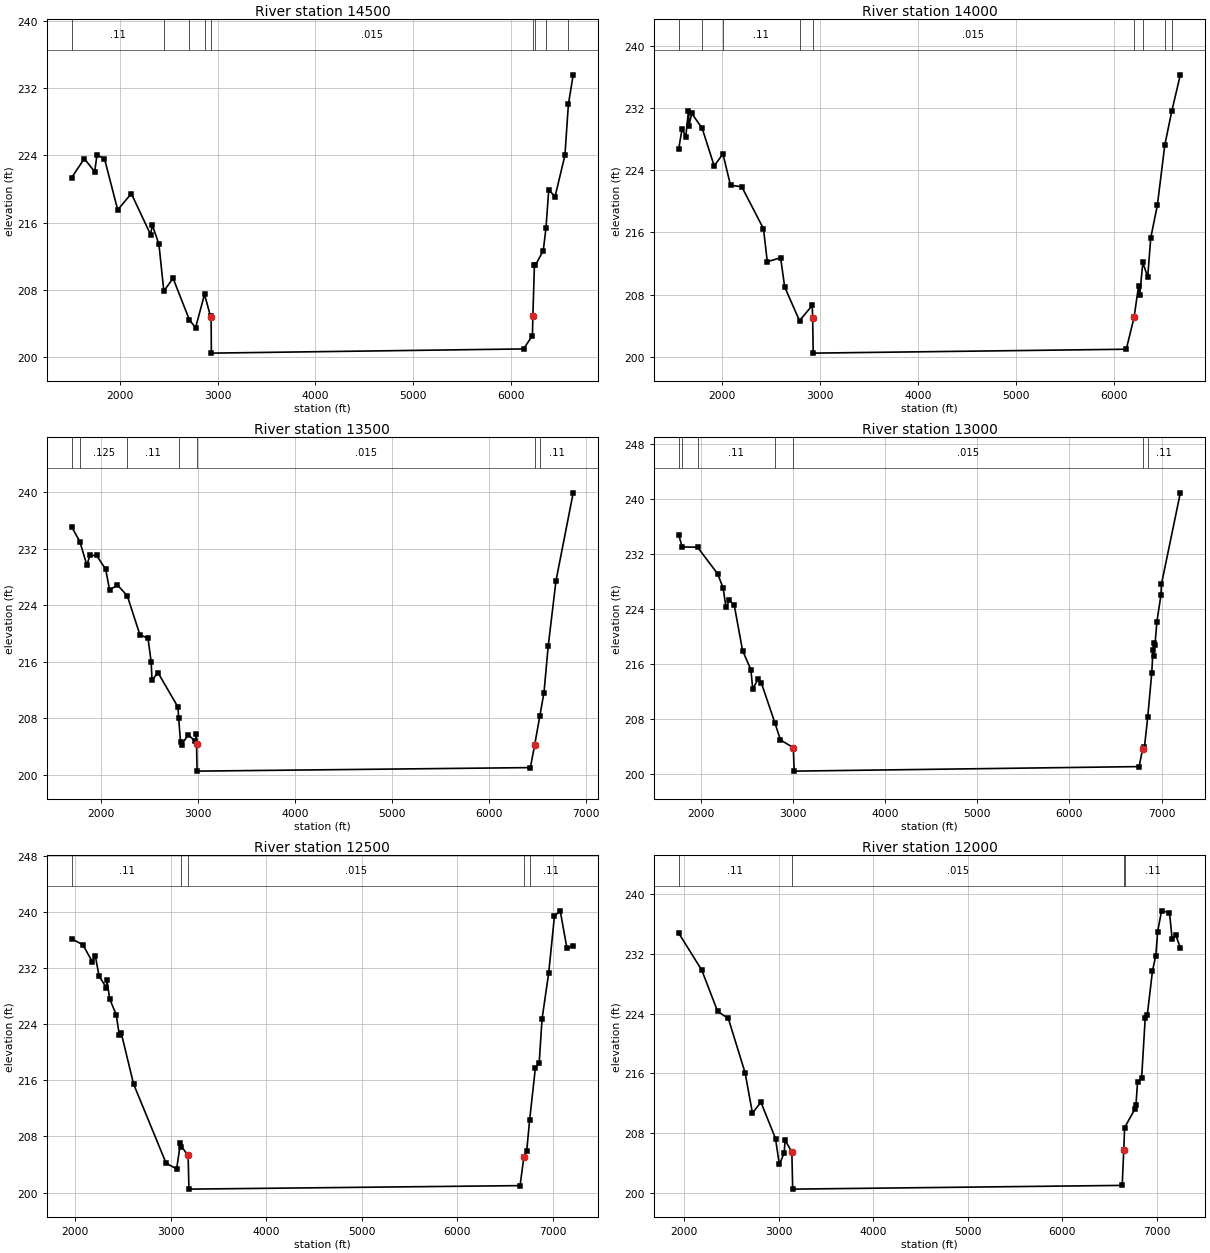
Type RM Length L Ch R = 1 ,14500   ,500,500,500
BEGIN DESCRIPTION:
LITTLE LAKE CREEK 29.0
END DESCRIPTION:
XS GIS Cut Line= 3
      3778423.77     10148333.94      3777072.04     10145113.52
      3776895.99     10143486.72
#Sta/Elev= 30
  1507.4  221.35  1637.1  223.61    1743  222.06  1766.8  224.04  1843.5   223.6
  1978.6  217.52  2117.8  219.46  2314.6  214.59    2333   215.7  2399.8  213.47
  2450.2  207.87  2544.8   209.4  2711.7  204.45  2774.9  203.52  2866.2  207.48
  2928.3  204.85  2933.8  204.94  2936.3   200.5    6129     201  6219.5  202.59
 6224.01  204.91  6239.6  210.93  6249.7  210.94  6330.2  212.69  6357.6  215.33
  6386.1  219.89  6450.9  219.11  6551.5     224  6587.1  230.07  6636.3  233.57
#Mann= 9 ,-1 , 0
  1507.4     .11       0  2450.2    .125       0  2711.7     .11       0
  2866.2     .11       0  2928.3    .015       0 6224.01     .11       0
  6249.7     .11       0  6357.6    .125       0  6587.1     .11       0
#XS Ineff= 2 , 0
       0  2866.2  207.48               0
Permanent Ineff=
       F       F
Bank Sta=2928.3,6224.01
XS Rating Curve= 0 ,0
Exp/Cntr=0.3,0.1

Type RM Length L Ch R = 1 ,14000   ,500,500,500
BEGIN DESCRIPTION:
LITTLE LAKE CREEK 28.0
END DESCRIPTION:
XS GIS Cut Line= 3
      3778562.67     10148347.86      3777566.23     10145048.75
      3777014.04     10143458.92
#Sta/Elev= 30
  1553.7  226.76  1587.3   229.3  1625.5  228.29  1653.2  231.65  1658.4  229.72
  1686.1   231.3  1793.1  229.38    1916  224.55  2005.6  226.09  2083.1  222.06
    2198  221.87  2420.2  216.47  2459.2  212.24  2595.4  212.75  2636.7  209.01
  2788.6  204.66  2918.8  206.63 2922.94  205.04  2928.9   200.5  6130.3     201
 6209.94   205.1    6256  209.15  6267.9     208  6299.6  212.15  6349.3  210.26
  6380.4  215.31    6448   219.5  6524.2  227.24  6596.1  231.62    6683  236.25
#Mann= 9 ,-1 , 0
  1553.7     .11       0  1793.1    .125       0  2005.6     .11       0
  2788.6    .125       0 2922.94    .015       0 6209.94     .11       0
  6299.6     .11       0  6524.2    .125       0  6596.1     .11       0
#XS Ineff= 2 , 0
       0  2918.8  206.63               0
Permanent Ineff=
       F       F
Bank Sta=2922.94,6209.94
XS Rating Curve= 0 ,0
Exp/Cntr=0.3,0.1

Type RM Length L Ch R = 1 ,13500   ,500,500,500
BEGIN DESCRIPTION:
LITTLE LAKE CREEK 27.0
END DESCRIPTION:
XS GIS Cut Line= 3
      3778659.87     10148306.13      3778066.13     10145058.87
      3777145.98     10143431.15
#Sta/Elev= 30
  1698.9  235.11  1783.6  233.01  1856.5  229.67    1887  231.05  1956.7  231.05
  2049.7   229.1  2090.3  226.18  2171.7  226.85  2272.2  225.35  2402.8  219.82
  2486.8   219.3  2519.4  215.89  2527.5  213.37  2588.5  214.46  2795.6  209.57
    2802  208.03  2822.3  204.56  2832.4  204.27    2902  205.65  2974.8   204.7
  2984.9  205.77 2986.79   204.4  2992.3   200.5  6428.4     201  6471.7  204.15
  6525.1  208.26  6568.4  211.61  6611.7  218.16  6692.6  227.49  6869.8  239.92
#Mann= 7 ,-1 , 0
  1698.9     .11       0  1783.6    .125       0  2272.2     .11       0
    2802     .11       0 2986.79    .015       0  6471.7     .11       0
  6525.1     .11       0
#XS Ineff= 2 , 0
       0  2984.9  205.77               0
Permanent Ineff=
       F       F
Bank Sta=2986.79,6471.7
XS Rating Curve= 0 ,0
Exp/Cntr=0.3,0.1

Type RM Length L Ch R = 1 ,13000   ,500,500,500
BEGIN DESCRIPTION:
LITTLE LAKE CREEK 26.0
END DESCRIPTION:
XS GIS Cut Line= 3
      3778755.03     10148302.38      3778566.03       10145069.
       3777215.4     10143326.95
#Sta/Elev= 30
  1761.1  234.76  1797.5  233.01  1965.3  232.96  2183.1  229.09  2243.2  227.01
  2273.3   224.2  2310.4  225.22  2363.4  224.52  2453.6  217.92  2543.7  215.15
  2563.8  212.34  2623.9  213.79  2657.1  213.22  2804.2  207.41  2864.3  204.92
  3004.5  203.78  3013.3  200.37    6757  201.03  6794.1  203.53    6815  203.89
  6850.3   208.2  6893.7   214.6  6908.1  218.01  6914.5  217.19  6920.9  219.07
    6929  218.77  6949.8  222.08  6993.3  225.95  6999.6   227.6  7204.3  240.88
#Mann= 7 ,-1 , 0
  1761.1     .11       0  1797.5    .125       0  1965.3     .11       0
  2804.2     .11       0  3004.5    .015       0  6794.1     .11       0
  6850.3     .11       0
Bank Sta=3004.5,6794.1
XS Rating Curve= 0 ,0
Exp/Cntr=0.3,0.1

Type RM Length L Ch R = 1 ,12500   ,500,500,500
BEGIN DESCRIPTION:
LITTLE LAKE CREEK 25.0
END DESCRIPTION:
XS GIS Cut Line= 3
      3778863.31     10148298.19      3779025.09       10145266.
      3779081.73     10143055.23
#Sta/Elev= 30
  1963.5  236.15  2080.8  235.31  2180.9  232.88    2211  233.75    2251  230.82
  2328.2  229.18  2333.2  230.28  2361.2  227.62  2431.3   225.3  2461.3  222.49
  2481.4   222.8  2611.5  215.48    2952  204.19  3062.2  203.38  3102.2  207.04
  3112.2  206.55  3182.3  205.33    3191   200.5  6655.5     201  6695.5   205.1
  6725.5     206  6755.5  210.33  6815.5  217.73  6855.5  218.47  6885.5  224.73
  6955.6  231.35  7015.6  239.43  7075.6  240.14  7145.6  234.84  7211.5  235.07
#Mann= 5 ,-1 , 0
  1963.5     .11       0  3112.2     .11       0  3182.3    .015       0
  6695.5     .11       0  6755.5     .11       0
#XS Ineff= 2 , 0
       0  3102.2  207.04               0
Permanent Ineff=
       F       F
Bank Sta=3182.3,6695.5
XS Rating Curve= 0 ,0
Exp/Cntr=0.3,0.1

Type RM Length L Ch R = 1 ,12000   ,500,500,500
BEGIN DESCRIPTION:
LITTLE LAKE CREEK 24.0
END DESCRIPTION:
XS GIS Cut Line= 3
      3778990.71     10148298.11      3779524.08     10145289.12
      3779143.03     10143075.37
#Sta/Elev= 30
  1944.1  234.78  2187.7  229.83  2354.9  224.31  2468.1  223.36  2645.4  216.09
  2723.1  210.68  2812.6  212.15  2966.8  207.28  3007.5   203.8  3058.2  205.33
  3068.4  207.04  3139.5  205.49  3148.6   200.5  6631.7     201 6648.27  205.72
  6657.5  208.75  6763.6  211.17  6777.3  211.82    6794  214.81  6837.2  215.43
  6875.2  223.46  6897.1  223.85    6952  229.74  6986.8  231.78  7006.8  235.01
  7047.7  237.78  7131.7  237.53  7159.3  234.07  7199.9  234.48  7246.3  232.83
#Mann= 4 ,-1 , 0
  1944.1     .11       0  3139.5    .015       0 6648.27     .11       0
  6657.5     .11       0
#XS Ineff= 2 , 0
       0  3068.4  207.04               0
Permanent Ineff=
       F       F
Bank Sta=3139.5,6648.27
XS Rating Curve= 0 ,0
Exp/Cntr=0.3,0.1