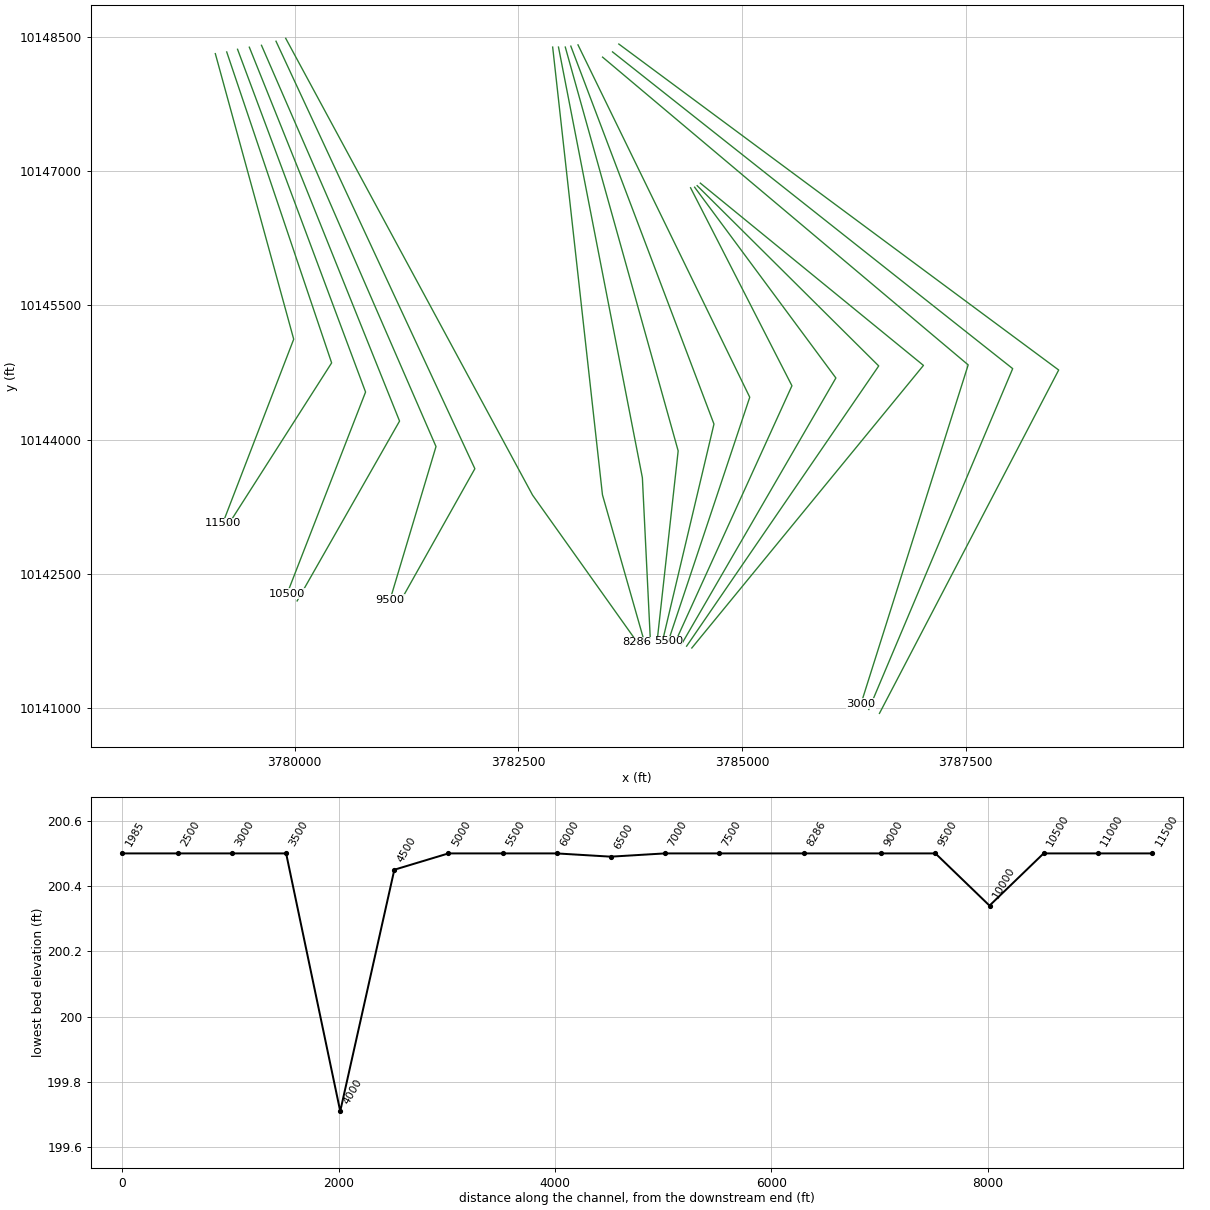
HEC-RAS study LITTLE LAKE CREEK.prj: LITTLE LAKE CREEK Base Level Engineering

--- LITTLE LAKE CREEK.g01 (geometry) --- (continued)

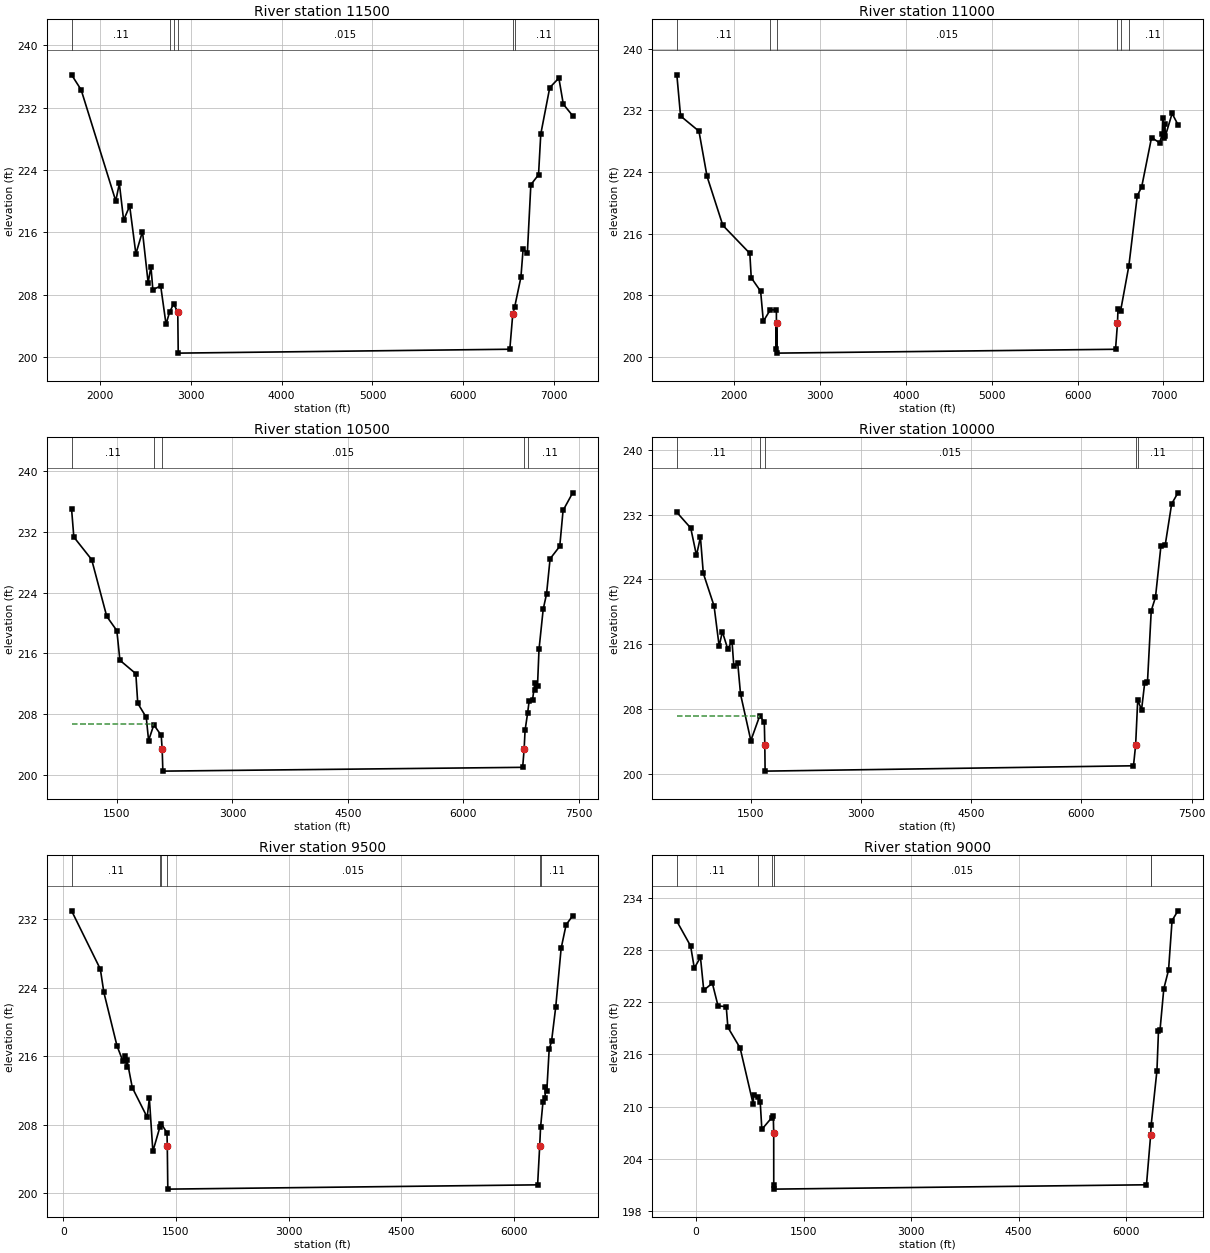
Type RM Length L Ch R = 1 ,11500   ,500,500,500
BEGIN DESCRIPTION:
LITTLE LAKE CREEK 23.0
END DESCRIPTION:
XS GIS Cut Line= 3
      3779113.84     10148313.04      3779990.05     10145121.02
      3779197.62     10143065.68
#Sta/Elev= 30
  1689.9  236.23    1795   234.3  2175.7  220.04  2215.3  222.28  2262.3  217.58
    2329  219.39  2397.1  213.24  2469.7  216.11  2531.9  209.55    2563  211.59
  2583.8  208.64  2670.1  209.13  2728.9  204.21  2768.6  205.79  2811.9  206.79
  2857.9  205.83  2863.1   200.5  6511.1     201  6543.3  205.46  6564.7  206.43
  6633.3  210.25  6657.9  213.92    6704  213.31  6742.5  222.12  6827.1   223.4
  6851.7  228.62  6950.5  234.59  7050.8  235.81    7100  232.45  7202.8  230.98
#Mann= 6 ,-1 , 0
  1689.9     .11       0  2768.6    .125       0  2811.9     .11       0
  2857.9    .015       0  6543.3     .11       0  6564.7     .11       0
#XS Ineff= 2 , 0
       0  2811.9  206.79               0
Permanent Ineff=
       F       F
Bank Sta=2857.9,6543.3
XS Rating Curve= 0 ,0
Exp/Cntr=0.3,0.1

Type RM Length L Ch R = 1 ,11000   ,500,500,500
BEGIN DESCRIPTION:
LITTLE LAKE CREEK 22.0
END DESCRIPTION:
XS GIS Cut Line= 3
      3779241.24     10148332.11      3780413.92      10144856.4
      3779246.68     10143028.38
#Sta/Elev= 30
  1331.8   236.6  1375.1  231.26  1589.3  229.29  1683.7  223.42  1867.2  217.08
  2181.9  213.44  2198.3  210.28  2307.8  208.52  2339.3  204.63  2419.9  206.11
  2491.4  206.12  2492.5     201 2492.65  204.42  2493.5   200.5    6442     201
  6464.8  204.37  6470.8  206.28  6501.2  205.99  6597.4  211.83    6695  220.91
  6746.6  222.06  6861.6  228.47  6955.6  227.78    6986  228.88  6991.9  231.06
  7007.2  228.43  7013.1   230.2  7022.4  228.66  7101.1  231.59  7168.9  230.14
#Mann= 6 ,-1 , 0
  1331.8     .11       0  2419.9     .11       0 2492.65    .015       0
  6464.8     .11       0  6501.2    .125       0  6597.4     .11       0
#XS Ineff= 2 , 0
       0  2491.4  206.12               0
Permanent Ineff=
       F       F
Bank Sta=2492.65,6464.8
XS Rating Curve= 0 ,0
Exp/Cntr=0.3,0.1

Type RM Length L Ch R = 1 ,10500   ,500,500,500
BEGIN DESCRIPTION:
LITTLE LAKE CREEK 21.0
END DESCRIPTION:
XS GIS Cut Line= 3
      3779362.27      10148361.8      3780793.21     10144530.61
      3779915.63     10142274.58
#Sta/Elev= 30
   910.3  234.99   939.2  231.33  1170.9  228.36    1367  220.88  1498.2     219
  1538.1   215.1  1744.9  213.33  1769.9  209.43  1880.4  207.58  1910.7  204.53
  1978.6   206.6  2074.6  205.21  2087.2  203.37  2096.1   200.5  6770.8     201
    6790  203.41  6802.1  205.87  6834.3  208.09  6855.8  209.77  6898.7  209.83
  6928.7  212.14  6934.1  211.15  6963.9  211.77  6983.1  216.52  7037.5  221.81
  7081.1  223.83  7127.2  228.46  7252.8  230.11  7295.8  234.83  7420.7  237.15
#Mann= 5 ,-1 , 0
   910.3     .11       0  1978.6     .11       0  2087.2    .015       0
    6790     .11       0  6834.3     .11       0
#XS Ineff= 2 , 0
       0  1971.3  206.68               0
Permanent Ineff=
       F       F
Bank Sta=2087.2,6790
XS Rating Curve= 0 ,0
Exp/Cntr=0.3,0.1

Type RM Length L Ch R = 1 ,10000   ,500,500,500
BEGIN DESCRIPTION:
LITTLE LAKE CREEK 20.0
END DESCRIPTION:
XS GIS Cut Line= 3
      3779493.87     10148385.23       3781173.2      10144205.9
      3780028.24     10142195.59
#Sta/Elev= 30
   495.9  232.29   684.9  230.35   762.9  226.98   816.7  229.23     856  224.76
  1002.1  220.74  1071.6  215.76    1115  217.56  1187.6  215.44  1246.8  216.33
    1271   213.3  1324.7  213.65  1362.5  209.84  1502.7  204.11  1623.1  207.16
  1685.9  206.39 1692.82  203.56  1696.7  200.34  6708.8     201    6738  203.57
  6766.3  209.11  6818.7  207.92  6861.9  211.28  6899.4  211.39  6950.4  220.15
    7008  221.81  7082.4  228.16  7141.4  228.31  7227.9  233.33  7313.5   234.7
#Mann= 5 ,-1 , 0
   495.9     .11       0  1623.1     .11       0 1692.82    .015       0
    6738     .11       0  6766.3     .11       0
#XS Ineff= 2 , 0
       0  1610.4  207.19               0
Permanent Ineff=
       F       F
Bank Sta=1692.82,6738
XS Rating Curve= 0 ,0
Exp/Cntr=0.3,0.1

Type RM Length L Ch R = 1 ,9500    ,500,500,500
BEGIN DESCRIPTION:
LITTLE LAKE CREEK 19.0
END DESCRIPTION:
XS GIS Cut Line= 3
      3779629.78     10148406.39      3781580.58     10143921.17
      3781067.85     10142211.08
#Sta/Elev= 30
   108.9  233.01   491.8   226.2   538.7  223.49   713.7  217.24   789.4  215.52
   823.8     216   841.8   214.8   847.2  215.57   917.6  212.36    1116   208.9
  1144.9  211.11  1191.8  204.91  1286.2  207.78  1303.3  208.15  1379.7  207.07
 1383.88  205.54  1390.9   200.5    6318     201  6345.8  205.54  6357.3  207.71
  6389.3  210.66  6417.2  211.16  6422.4  212.42  6440.8  212.02  6472.1  216.83
  6503.4  217.75  6559.9  221.81  6631.3  228.62  6697.4  231.37  6785.3  232.44
#Mann= 6 ,-1 , 0
   108.9     .11       0  1286.2    .125       0  1303.3     .11       0
 1383.88    .015       0  6345.8     .11       0  6357.3     .11       0
#XS Ineff= 2 , 0
       0  1303.3  208.15               0
Permanent Ineff=
       F       F
Bank Sta=1383.88,6345.8
XS Rating Curve= 0 ,0
Exp/Cntr=0.3,0.1

Type RM Length L Ch R = 1 ,9000    ,714,714,714
BEGIN DESCRIPTION:
LITTLE LAKE CREEK 18.0
END DESCRIPTION:
XS GIS Cut Line= 3
      3779792.19     10148451.63      3782014.96     10143673.55
      3781170.22     10142169.09
#Sta/Elev= 30
  -269.8  231.34   -77.4  228.49   -26.1  225.95    59.9  227.19   105.7   223.4
   225.6  224.21   305.3  221.59   419.7  221.51   442.6  219.13   613.8  216.74
   796.9  210.25   802.4  211.38   857.9  211.05   893.9  210.56   916.8  207.38
  1054.1  208.72  1076.4  208.97  1082.5  206.94  1082.9     201  1083.9   200.5
  6286.3     201  6344.7  206.73  6351.4  207.85  6432.4  214.15  6454.1  218.75
  6475.7  218.85  6528.2  223.57  6594.4  225.72  6643.4  231.42  6725.4  232.54
#Mann= 6 ,-1 , 0
  -269.8     .11       0   857.9    .125       0  1054.1     .11       0
  1082.5    .015       0  6344.7     .11       0  6351.4     .11       0
Bank Sta=1082.5,6344.7
XS Rating Curve= 0 ,0
Exp/Cntr=0.3,0.1

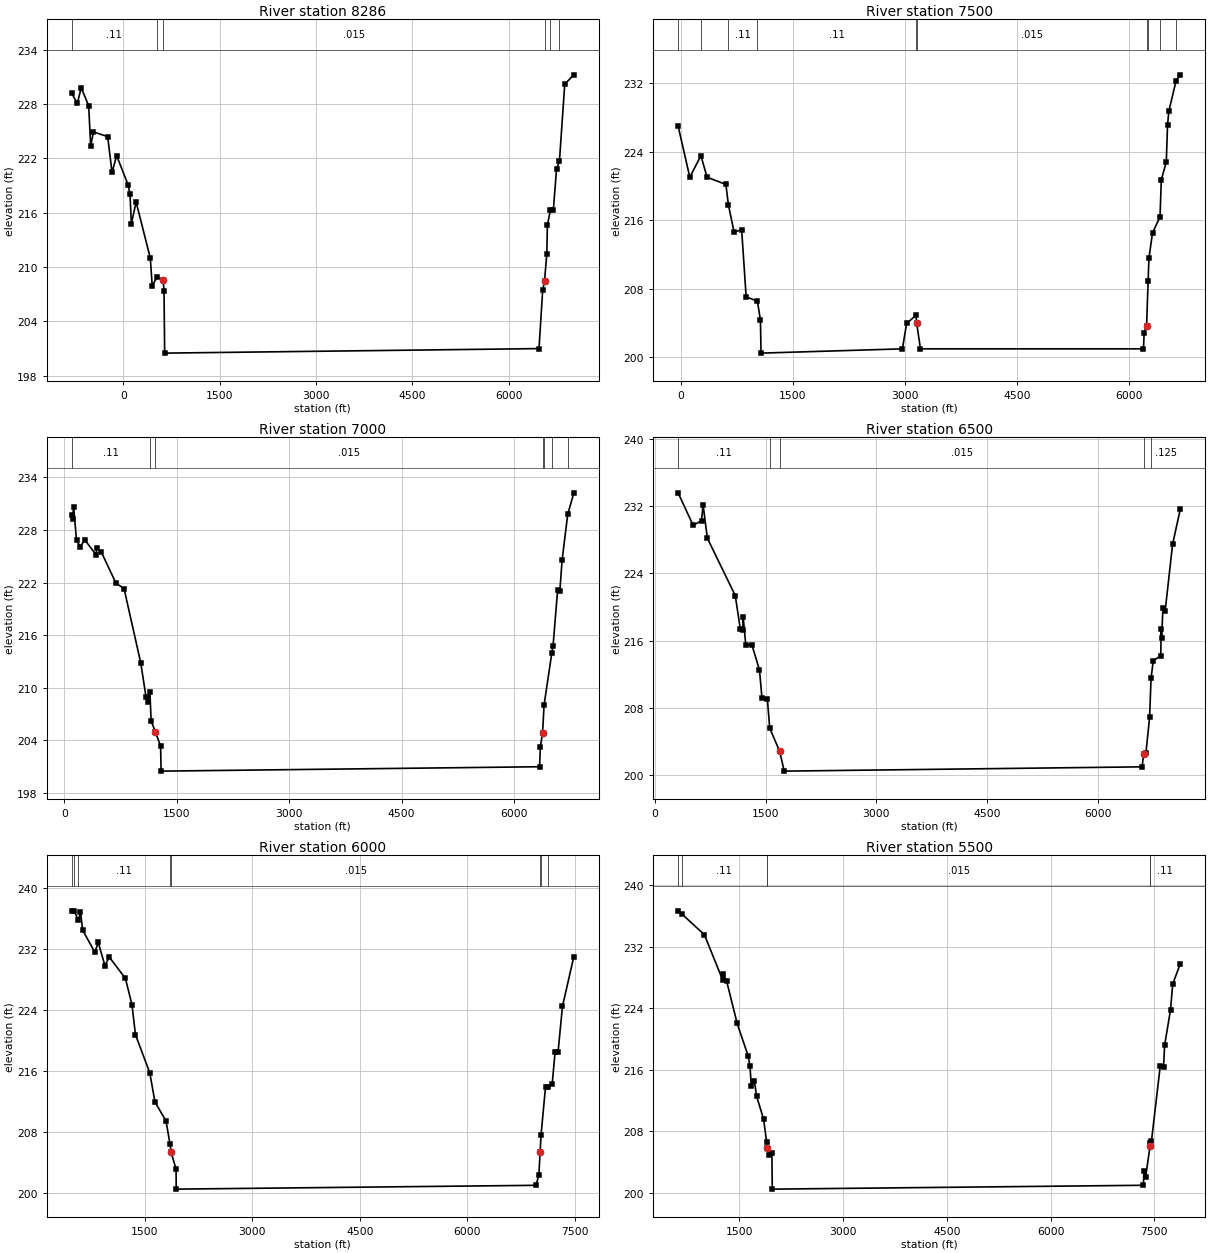
Type RM Length L Ch R = 1 ,8286    ,786,786,786
BEGIN DESCRIPTION:
LITTLE LAKE CREEK 16.0
END DESCRIPTION:
XS GIS Cut Line= 3
      3779900.67     10148484.24      3782659.96     10143378.44
      3783828.27      10141735.6
#Sta/Elev= 30
  -803.7  229.19  -714.9  228.05  -654.9   229.8  -538.7  227.79  -507.4  223.38
  -463.7  224.91  -243.1  224.39  -174.9  220.45    -103  222.29    75.2  219.07
   104.4  218.06   126.3  214.79   200.2  217.17   421.3  210.98   450.3  207.95
   527.1  208.88   620.8  208.56   634.5  207.38   644.5   200.5  6473.5     201
  6530.6  207.43  6559.6  208.48  6595.3  211.48  6603.9  214.61  6652.2  216.32
  6696.1  216.25  6746.5   220.8  6791.5  221.66  6874.4  230.19  7015.9  231.21
#Mann= 6 ,-1 , 0
  -803.7     .11       0   527.1    .125       0   620.8    .015       0
  6559.6     .11       0  6652.2    .125       0  6791.5     .11       0
Bank Sta=620.8,6559.6
XS Rating Curve= 0 ,0
Exp/Cntr=0.3,0.1

Type RM Length L Ch R = 1 ,7500    ,500,500,500
BEGIN DESCRIPTION:
LITTLE LAKE CREEK 15.0
END DESCRIPTION:
XS GIS Cut Line= 3
      3782884.64     10148386.53      3783441.19     10143381.58
       3783904.6     10141756.77
#Sta/Elev= 30
   -35.8     227   120.6  221.03   269.5  223.54     352  221.03   603.6  220.19
   637.9   217.8   714.2   214.6   814.9  214.92   875.2  207.08  1026.2  206.55
  1066.4  204.38  1074.8   200.5  2968.1     201  3023.9  203.96  3149.2  204.91
  3159.2  203.99    3210     201  6196.4     201  6205.4   202.9    6238   203.7
  6258.8  208.95  6269.2  211.57  6317.3  214.52  6417.9  216.42  6435.6  220.74
    6502  222.82  6518.7  227.14  6535.9  228.74  6633.8  232.31  6689.6  232.98
#Mann= 10 ,-1 , 0
   -35.8     .11       0   269.5    .125       0   637.9     .11       0
  1026.2     .11       0  3149.2     .11       0  3159.2    .015       0
    6238     .11       0  6258.8    .125       0  6417.9     .11       0
  6633.8    .125       0
#XS Ineff= 2 , 0
       0  3149.2  204.91               0
Permanent Ineff=
       F       F
Bank Sta=3159.2,6238
XS Rating Curve= 0 ,0
Exp/Cntr=0.3,0.1

Type RM Length L Ch R = 1 ,7000    ,500,500,500
BEGIN DESCRIPTION:
LITTLE LAKE CREEK 14.0
END DESCRIPTION:
XS GIS Cut Line= 3
      3782949.74     10148386.55      3783887.41     10143572.82
      3783975.67     10141774.39
#Sta/Elev= 30
    95.8  229.67   109.3  229.25   121.8  230.68   160.9  226.82   212.5   226.1
   269.2   226.9   424.1  225.17   429.2   225.9   488.5  225.55   687.3  221.95
   795.6  221.32  1018.3  212.85  1089.6  208.91  1110.5  208.41  1140.5  209.53
    1157  206.21  1213.7  204.99  1283.2  203.36    1290   200.5  6343.4     201
  6353.4  203.25  6383.4  204.88  6403.4  208.05  6505.6  213.93  6523.6  214.83
  6583.7  221.12  6613.7  221.04  6643.7  224.55  6718.9  229.79  6800.6  232.25
#Mann= 7 ,-1 , 0
    95.8     .11       0  1140.5     .11       0  1213.7    .015       0
  6383.4     .11       0  6403.4    .125       0  6505.6     .11       0
  6718.9    .125       0
Bank Sta=1213.7,6383.4
XS Rating Curve= 0 ,0
Exp/Cntr=0.3,0.1

Type RM Length L Ch R = 1 ,6500    ,500,500,500
BEGIN DESCRIPTION:
LITTLE LAKE CREEK 13.0
END DESCRIPTION:
XS GIS Cut Line= 3
      3783025.69     10148386.56      3784287.49     10143872.71
      3784054.55     10141767.35
#Sta/Elev= 30
   313.1  233.59   516.1  229.73   630.3  230.27   651.1  232.18   709.7  228.19
  1087.5  221.37  1155.8   217.4  1189.9   217.3  1195.1  218.79  1229.3  215.55
  1315.6  215.44  1415.6  212.51  1449.7  209.15  1523.2  209.02  1554.4   205.6
  1689.4  202.84  1750.6  200.49  6601.3     201  6621.5  202.56  6651.7  202.59
    6702  206.87  6722.1  211.57  6752.3  213.64  6852.9   214.2  6859.4  217.34
  6864.4  216.37  6883.1  219.86  6913.2  219.56  7013.8  227.48  7118.2  231.66
#Mann= 5 ,-1 , 0
   313.1     .11       0  1554.4     .11       0  1689.4    .015       0
  6621.5     .11       0  6722.1    .125       0
Bank Sta=1689.4,6621.5
XS Rating Curve= 0 ,0
Exp/Cntr=0.3,0.1

Type RM Length L Ch R = 1 ,6000    ,500,500,500
BEGIN DESCRIPTION:
LITTLE LAKE CREEK 12.0
END DESCRIPTION:
XS GIS Cut Line= 3
      3783087.56     10148397.04      3784687.58     10144172.59
      3784114.85     10141756.75
#Sta/Elev= 30
   482.7  237.02   519.3  236.98   576.4  235.77     606  236.85   636.1  234.49
   806.4  231.57   852.6   232.9   946.5  229.83  1006.8  230.96    1232  228.15
  1323.2  224.72  1372.1  220.77  1572.5  215.74  1643.9  211.93  1797.7  209.46
  1852.6  206.47  1868.5  205.37  1937.8  203.14  1940.7   200.5  6954.2     201
  6995.3  202.31  7012.7  205.38  7026.2  207.65  7087.8  213.91  7122.9  213.93
  7180.3  214.23  7221.4  218.47  7262.5  218.46  7324.2  224.48  7482.8  231.02
#Mann= 8 ,-1 , 0
   482.7     .11       0   519.3    .125       0   576.4     .11       0
  1852.6     .11       0  1868.5    .015       0  7012.7     .11       0
  7026.2     .11       0  7122.9    .125       0
Bank Sta=1868.5,7012.7
XS Rating Curve= 0 ,0
Exp/Cntr=0.3,0.1

Type RM Length L Ch R = 1 ,5500    ,500,500,500
BEGIN DESCRIPTION:
LITTLE LAKE CREEK 11.0
END DESCRIPTION:
XS GIS Cut Line= 3
      3783167.84     10148411.09      3785087.66     10144472.48
      3784177.01     10141745.41
#Sta/Elev= 30
   618.4  236.69   671.1  236.29   998.6  233.58  1263.5  227.66  1269.1  228.51
  1319.7  227.54  1471.9  222.04  1629.6  217.84  1657.7  216.49  1674.7  213.89
  1719.8  214.55  1753.4  212.56  1853.3   209.6  1897.8  206.63  1905.6  205.89
  1928.2  204.94  1973.2  205.15    1979   200.5    7342     201  7349.4  202.82
  7373.6  202.03  7436.9  206.05  7444.2  206.44    7458  206.72  7584.5  216.46
  7633.8  216.42  7647.7  219.18  7733.9  223.82  7765.5  227.18  7875.1   229.8
#Mann= 6 ,-1 , 0
   618.4    .125       0   671.1     .11       0  1897.8     .11       0
  1905.6    .015       0  7436.9     .11       0  7444.2     .11       0
Bank Sta=1905.6,7436.9
XS Rating Curve= 0 ,0
Exp/Cntr=0.3,0.1

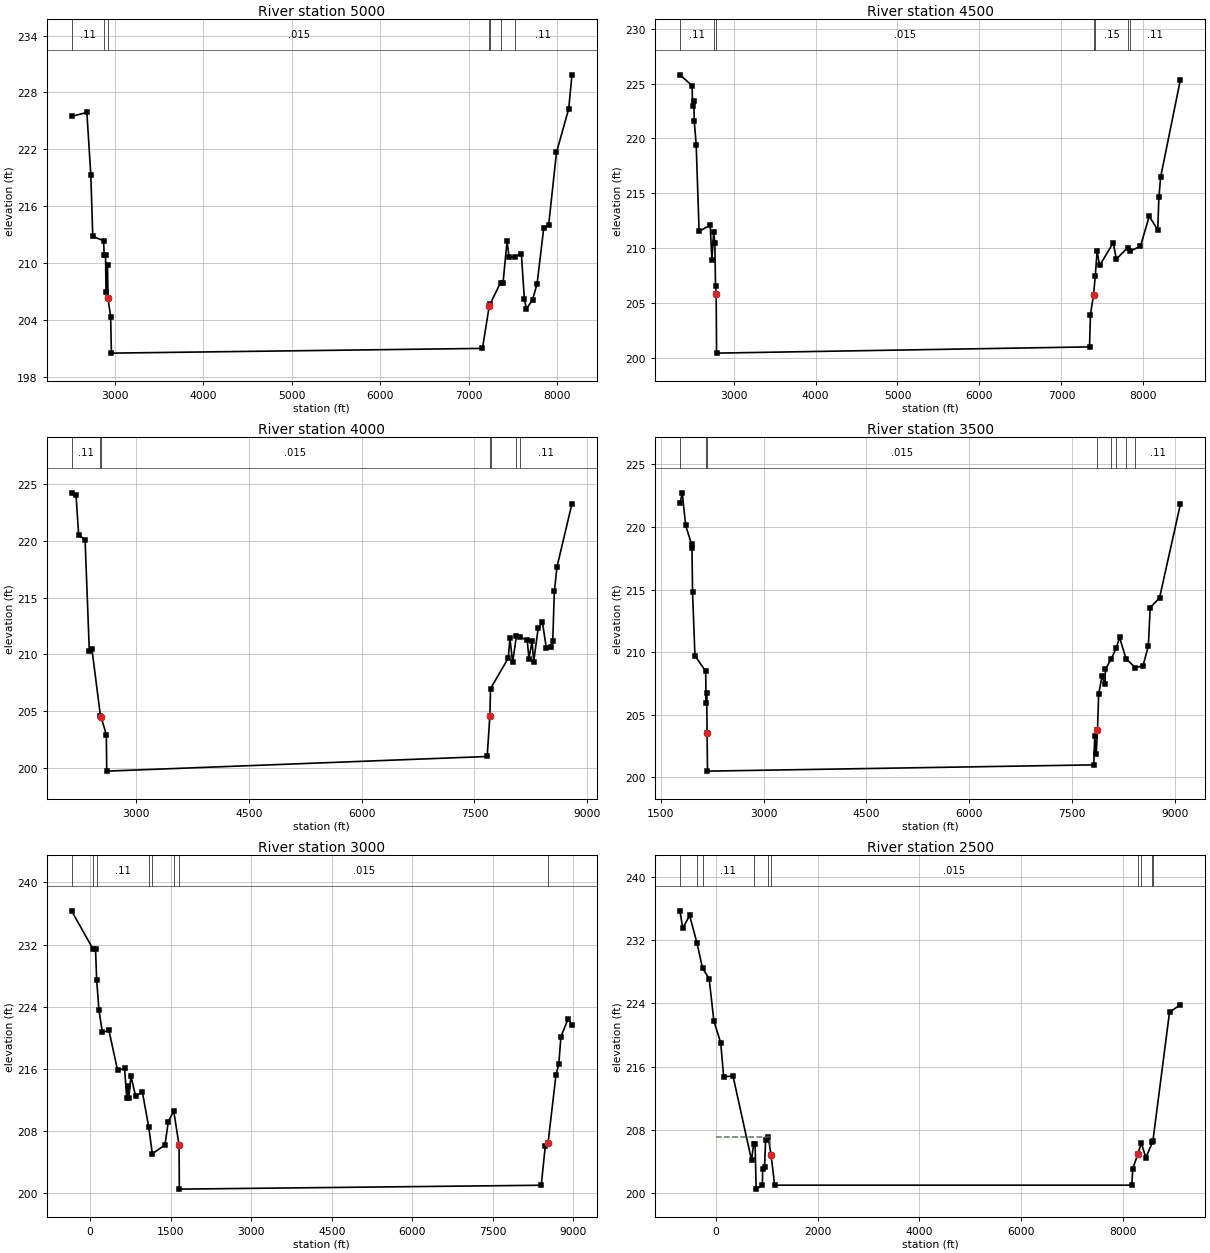
Type RM Length L Ch R = 1 ,5000    ,500,500,500
BEGIN DESCRIPTION:
LITTLE LAKE CREEK 10.0
END DESCRIPTION:
XS GIS Cut Line= 3
      3784426.09     10146813.73      3785559.16     10144600.74
       3784248.3     10141720.95
#Sta/Elev= 30
  2513.8  225.48  2686.6  225.89    2731  219.32  2753.2  212.81  2875.2  212.36
  2882.8   210.8  2897.4  210.87    2903  206.96  2919.6  209.84  2925.2   206.3
  2954.9  204.35  2963.7   200.5  7153.1     201  7230.1  205.47  7241.2  205.71
  7358.2  207.95    7385  207.87  7431.1  212.31  7454.2  210.59  7515.8  210.69
  7592.5  210.97  7626.6  206.19  7649.6  205.16  7718.8  206.13  7770.4  207.83
  7845.3  213.72  7900.3  213.97  7988.9  221.67  8127.2  226.28  8164.1  229.86
#Mann= 7 ,-1 , 0
  2513.8     .11       0  2882.8     .15       0  2925.2    .015       0
  7230.1     .11       0  7241.2     .11       0  7358.2    .125       0
  7515.8     .11       0
Bank Sta=2925.2,7230.1
XS Rating Curve= 0 ,0
Exp/Cntr=0.3,0.1

Type RM Length L Ch R = 1 ,4500    ,500,500,500
BEGIN DESCRIPTION:
LITTLE LAKE CREEK 9.0
END DESCRIPTION:
XS GIS Cut Line= 3
      3784471.29     10146820.11      3786050.38     10144687.62
       3784319.8      10141701.9
#Sta/Elev= 30
  2346.5  225.79  2494.4   224.8  2500.6  222.98  2515.2  223.42  2521.4  221.56
  2544.4   219.4  2579.9  211.54  2715.6   212.1  2736.4  208.91  2757.3  211.48
  2771.9  210.48  2780.3  206.56 2787.99   205.8    2793  200.45  7342.4  201.02
  7353.9  203.96  7391.2  205.74  7412.7  207.47  7434.8  209.72  7465.8  208.43
  7632.2   210.5  7669.5  209.01  7805.8  210.04  7835.6  209.74  7963.5  210.17
  8071.2  212.92  8174.6  211.66  8188.8  214.63  8210.3  216.49    8451  225.35
#Mann= 7 ,-1 , 0
  2346.5     .11       0  2757.3     .15       0 2787.99    .015       0
  7391.2     .11       0  7412.7     .15       0  7805.8    .125       0
  7835.6     .11       0
Bank Sta=2787.99,7391.2
XS Rating Curve= 0 ,0
Exp/Cntr=0.3,0.1

Type RM Length L Ch R = 1 ,4000    ,500,500,500
BEGIN DESCRIPTION:
LITTLE LAKE CREEK 8.0
END DESCRIPTION:
XS GIS Cut Line= 3
      3784499.89     10146837.15      3786529.22     10144822.29
      3784381.79      10141689.9
#Sta/Elev= 30
  2140.3  224.25  2199.7  224.05  2235.1  220.52    2320  220.11  2376.5  210.32
  2411.9  210.44    2525  204.55    2532  204.51  2602.8  202.92  2608.2  199.71
  7669.5     201  7705.3  204.58  7714.2  206.99  7950.4  209.68  7971.9  211.44
  8008.3   209.3  8058.1  211.61  8100.2  211.55  8202.3  211.25  8225.2  209.64
  8267.2  211.18  8288.1  209.34  8347.8  212.31  8404.6  212.84  8455.4  210.61
  8518.3  210.68  8541.8  211.18    8563  215.55  8598.9  217.74  8797.8   223.3
#Mann= 7 ,-1 , 0
  2140.3     .11       0    2525     .11       0    2532    .015       0
  7705.3     .11       0  7714.2     .11       0  8058.1    .125       0
  8100.2     .11       0
Bank Sta=2532,7705.3
XS Rating Curve= 0 ,0
Exp/Cntr=0.3,0.1

Type RM Length L Ch R = 1 ,3500    ,500,500,500
BEGIN DESCRIPTION:
LITTLE LAKE CREEK 7.0
END DESCRIPTION:
XS GIS Cut Line= 3
      3784535.21     10146865.65      3787029.19     10144828.24
        3784440.     10141669.51
#Sta/Elev= 30
  1779.6  221.89  1812.9  222.73  1862.5  220.13  1948.6  218.62  1955.1   218.3
    1963   214.8  1998.1  209.73  2154.7  208.48  2161.1  205.95    2169  206.75
  2175.5  203.52  2181.4   200.5  7819.7     201  7834.1  203.28  7854.9  201.85
 7874.17  203.77  7891.5  206.66    7941   208.1  7983.2  207.42  7990.5  208.65
  8070.6  209.42  8146.7  210.31  8196.5  211.18  8290.9  209.47  8427.5  208.77
  8538.1  208.91  8616.3  210.49  8643.6  213.57  8779.3  214.33  9084.3  221.82
#Mann= 8 ,-1 , 0
  1779.6     .11       0  2161.1     .11       0  2175.5    .015       0
 7874.17     .11       0  8070.6    .125       0  8146.7     .11       0
  8290.9    .125       0  8427.5     .11       0
Bank Sta=2175.5,7874.17
XS Rating Curve= 0 ,0
Exp/Cntr=0.3,0.1

Type RM Length L Ch R = 1 ,3000    ,500,500,500
BEGIN DESCRIPTION:
LITTLE LAKE CREEK 6.0
END DESCRIPTION:
XS GIS Cut Line= 3
      3783442.52     10148274.15      3787529.15     10144834.21
      3786331.37     10141047.21
#Sta/Elev= 30
  -341.7  236.35      61  231.39   104.4  231.38   125.6  227.47   168.1  223.55
   231.9  220.69   352.8  220.97   515.4  215.79   644.1  216.05   685.8  212.25
   707.8  213.76   722.1  212.26   763.8  215.04   849.6  212.51   977.1  212.98
  1093.7  208.53  1161.4  205.05  1395.8   206.2  1459.6   209.2  1559.7  210.57
  1658.6  206.19  1664.4   200.5  8399.7     201  8474.9  206.04  8527.3   206.5
  8674.2  215.22  8726.6  216.61  8765.7  220.12  8900.2  222.45  8971.9  221.61
#Mann= 8 ,-1 , 0
  -341.7     .11       0      61    .125       0   125.6     .11       0
  1093.7    .125       0  1161.4     .11       0  1559.7    .125       0
  1658.6    .015       0  8527.3     .11       0
Bank Sta=1658.6,8527.3
XS Rating Curve= 0 ,0
Exp/Cntr=0.3,0.1

Type RM Length L Ch R = 1 ,2500    ,515,515,515
BEGIN DESCRIPTION:
LITTLE LAKE CREEK 5.0
END DESCRIPTION:
XS GIS Cut Line= 3
      3783553.79     10148332.66      3788026.76     10144792.18
      3786418.18     10140982.12
#Sta/Elev= 30
  -704.6  235.71  -650.2  233.49  -515.6  235.12  -372.4   231.7  -260.9  228.45
    -131  227.13     -38  221.78    96.6     219   154.3  214.73   338.6   214.8
   702.4  204.18   744.1  206.18   772.9  206.19   793.4   200.5   915.6     201
     922  203.06   958.5  203.28   979.7  206.68  1029.4  207.15  1086.1  204.83
  1157.6     201  8181.6     201    8198  203.08  8298.3  204.92  8366.2  206.33
  8456.8  204.49  8586.2  206.42  8595.7  206.62  8921.6  222.89  9135.7  223.83
#Mann= 10 ,-1 , 0
  -704.6     .11       0  -372.4    .125       0  -260.9     .11       0
   744.1     .11       0  1029.4     .11       0  1086.1    .015       0
  8298.3     .11       0  8366.2     .11       0  8586.2    .125       0
  8595.7     .11       0
#XS Ineff= 2 , 0
       0  1058.2  207.05    8198       0  203.08
Permanent Ineff=
       F       F
Bank Sta=1086.1,8298.3
XS Rating Curve= 0 ,0
Exp/Cntr=0.3,0.1

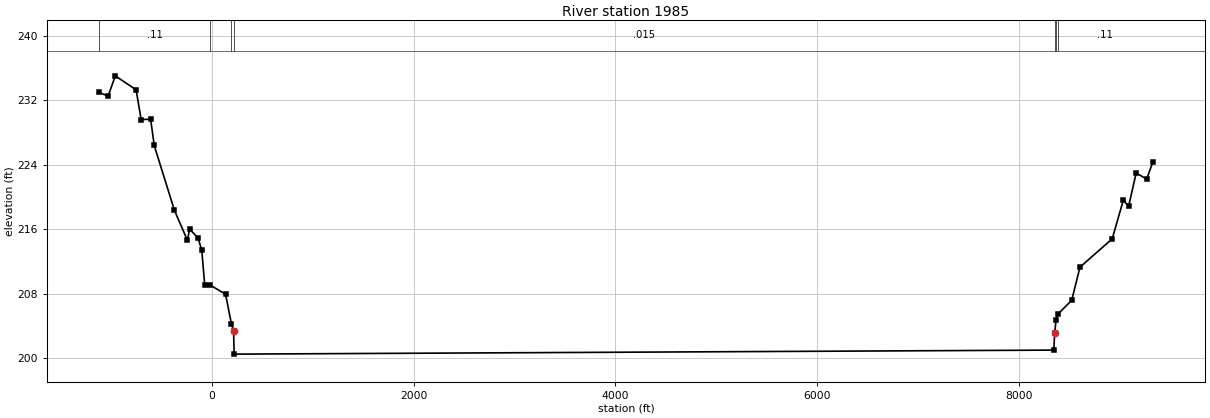
Type RM Length L Ch R = 1 ,1985    ,502,502,502
BEGIN DESCRIPTION:
LITTLE LAKE CREEK 2.0
END DESCRIPTION:
XS GIS Cut Line= 3
        3783624.      10148420.5      3788540.89     10144776.69
      3786537.52     10140938.69
#Sta/Elev= 30
 -1119.9     233 -1031.3  232.54  -960.4  235.06  -753.8  233.32  -703.8  229.62
  -609.8  229.68  -574.3  226.41    -374  218.36  -244.6  214.62  -223.7  216.04
  -138.2  214.89  -102.7  213.39   -73.5  209.09   -17.3  209.06   133.1  207.94
   191.6  204.24   212.4  203.42   218.7   200.5  8348.2     201  8356.6  203.11
  8370.3  204.73  8389.2  205.47  8525.8  207.19  8607.6   211.3  8927.6  214.82
    9038  219.64  9089.8  218.85  9164.9  222.98  9269.7  222.24  9329.4  224.33
#Mann= 7 ,-1 , 0
 -1119.9     .11       0   -17.3    .125       0   191.6     .11       0
   212.4    .015       0  8356.6     .11       0  8370.3    .125       0
  8389.2     .11       0
Bank Sta=212.4,8356.6
XS Rating Curve= 0 ,0
Exp/Cntr=0.3,0.1