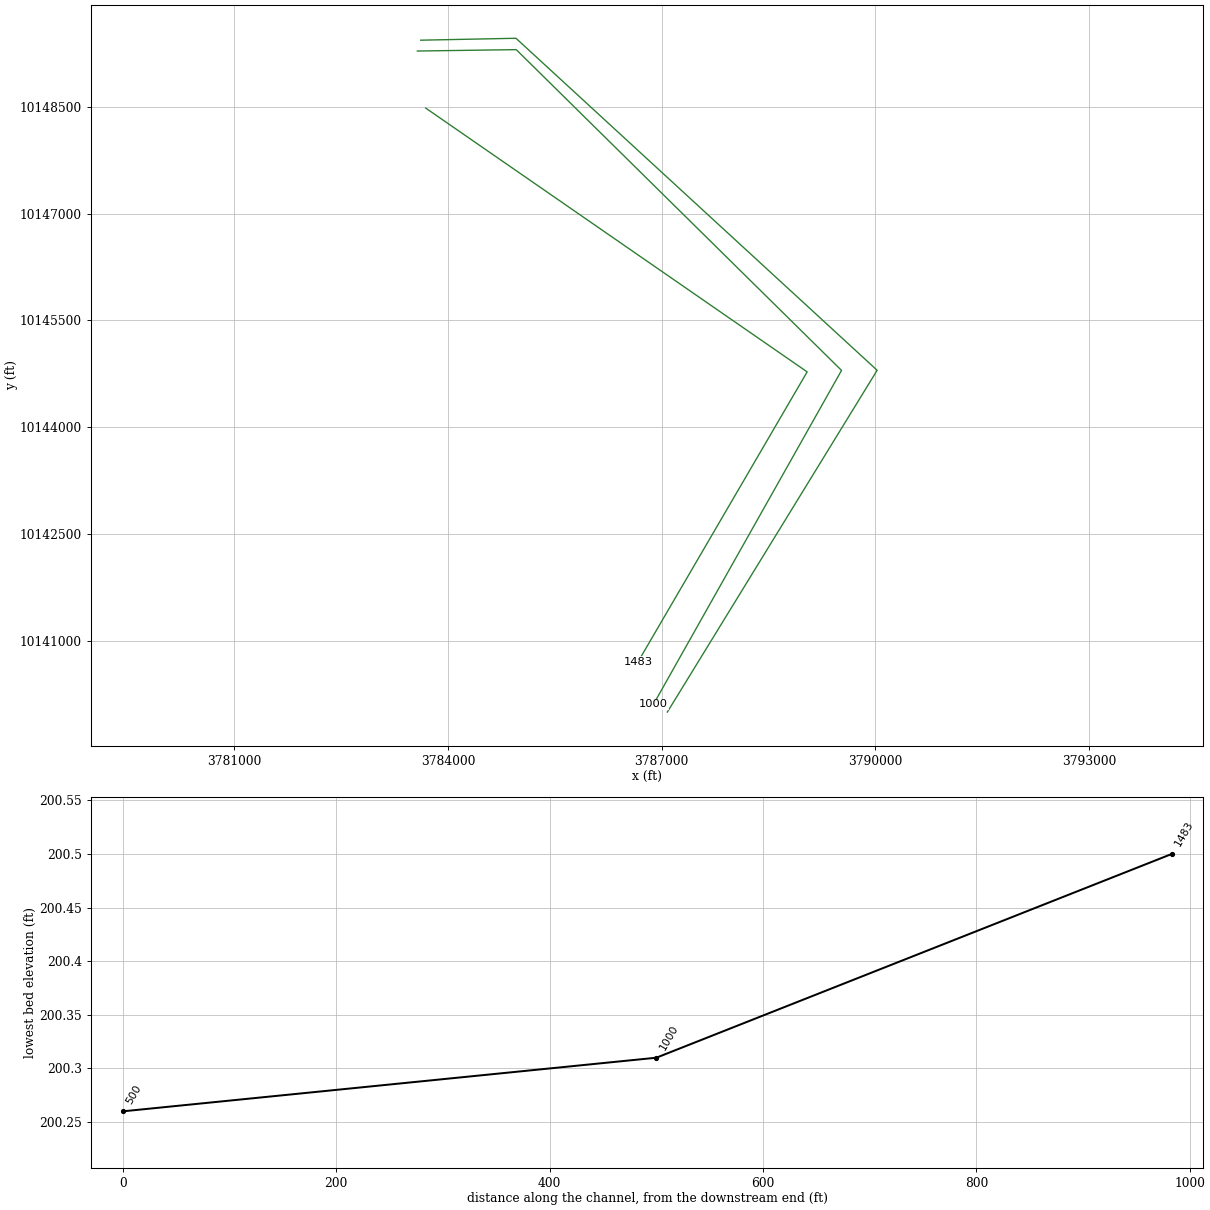
HEC-RAS study LITTLE LAKE CREEK.prj: LITTLE LAKE CREEK Base Level Engineering

--- LITTLE LAKE CREEK.g01 (geometry) --- (continued)

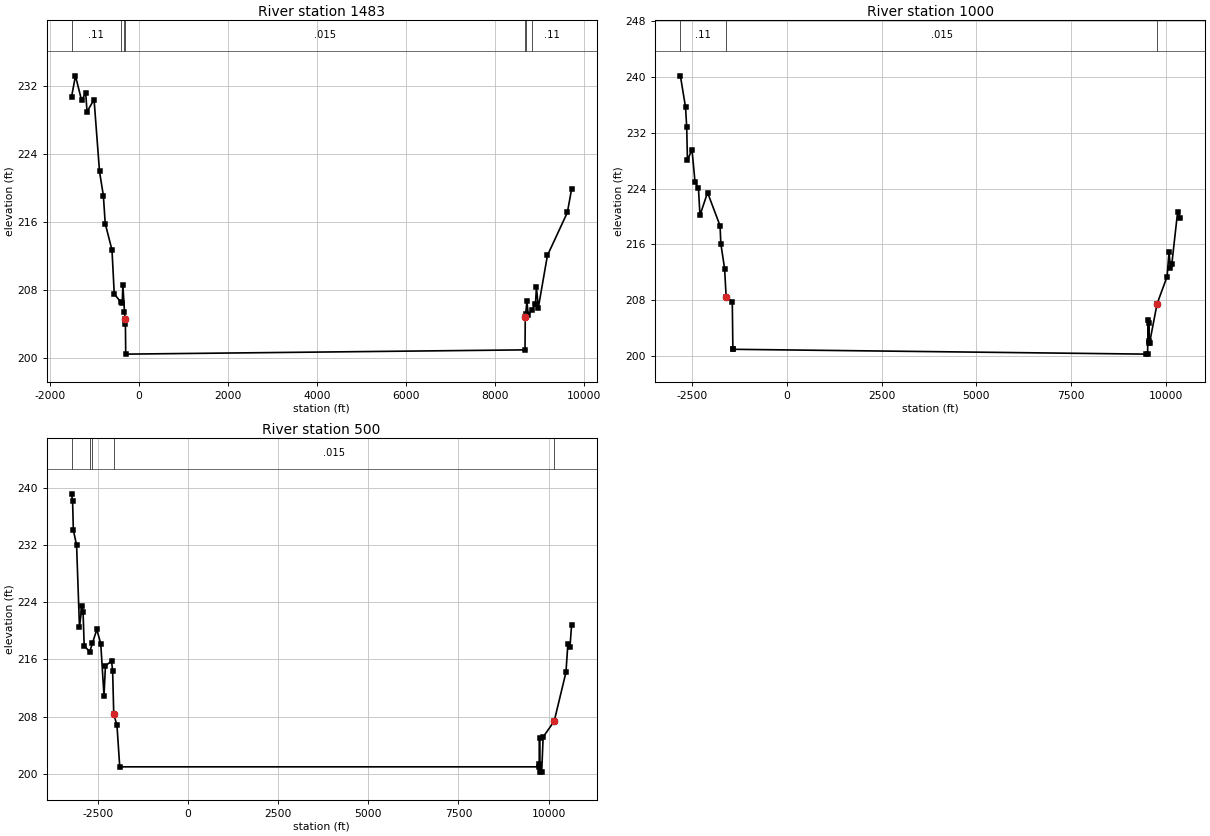
Type RM Length L Ch R = 1 ,1483    ,483,483,483
BEGIN DESCRIPTION:
LITTLE LAKE CREEK 1.0
END DESCRIPTION:
XS GIS Cut Line= 3
      3783688.22     10148484.99      3789043.03     10144777.18
      3786667.75     10140700.02
#Sta/Elev= 30
 -1513.2   230.7 -1424.8  233.17 -1287.7  230.29 -1195.1  231.15 -1165.4  228.96
 -1007.3  230.38    -885  221.94  -798.5  219.12  -756.6  215.82  -604.6  212.72
  -553.9  207.57  -409.1  206.62  -374.8  206.48    -360  208.59  -324.2  205.47
  -309.5  204.65  -303.2  204.05  -296.3   200.5  8672.7     201  8678.5  204.91
  8687.4  205.19  8715.7  206.72  8745.2  205.08  8830.4  205.73  8907.3  206.35
  8929.2  208.35  8972.2  205.96  9175.7  212.08    9624  217.13  9718.6  219.86
#Mann= 7 ,-1 , 0
 -1513.2     .11       0  -409.1    .125       0  -324.2     .11       0
  -309.5    .015       0  8678.5     .11       0  8687.4    .125       0
  8830.4     .11       0
Bank Sta=-309.5,8678.5
XS Rating Curve= 0 ,0
Exp/Cntr=0.3,0.1

Type RM Length L Ch R = 1 ,1000    ,500,500,500
BEGIN DESCRIPTION:
LITTLE LAKE CREEK 2.5
END DESCRIPTION:
XS GIS Cut Line= 4
      3783571.35      10149286.9      3784959.22     10149306.37
      3789525.65     10144797.84      3786885.56     10140104.65
#Sta/Elev= 30
 -2805.1  240.12 -2668.6  235.61 -2638.6  232.78 -2618.6  228.05 -2498.6  229.56
 -2418.6   224.9 -2328.6  224.05 -2288.6  220.17 -2088.5  223.42 -1758.5  218.67
 -1738.5  216.13 -1638.5  212.54 -1598.5  208.54   -1436  207.78 -1420.3  201.03
 -1407.2     201  9473.4  200.31  9519.1  200.31  9533.9  205.23  9549.8  201.92
  9555.6  204.78  9562.8  202.15  9571.5  201.92  9769.3  207.51 10033.2   211.4
 10084.6  214.89 10122.2  212.68 10159.4  213.27 10311.5  220.66 10384.8   219.8
#Mann= 3 ,-1 , 0
 -2805.1     .11       0 -1598.5    .015       0  9769.3     .11       0
#XS Ineff= 2 , 0
       0                  9533.9       0  205.23
Permanent Ineff=
       F       F
Bank Sta=-1598.5,9769.3
XS Rating Curve= 0 ,0
Exp/Cntr=0.3,0.1

Type RM Length L Ch R = 1 ,500     ,0,0,0
BEGIN DESCRIPTION:
LITTLE LAKE CREEK 1.5
END DESCRIPTION:
XS GIS Cut Line= 4
      3783618.16     10149439.11       3784955.5     10149466.03
      3790025.64     10144799.64      3787080.51     10139995.42
#Sta/Elev= 30
 -3228.3  239.14 -3198.6  238.08 -3178.6  234.07 -3088.6  231.98 -3008.6  220.53
 -2938.5  223.42 -2908.5  222.61   -2878  217.91 -2724.3  217.08 -2649.5  218.26
 -2528.5  220.19 -2418.4  218.21 -2328.4  210.91 -2288.4  215.11 -2118.4  215.78
 -2088.4  214.33 -2058.4  208.37 -1968.4  206.78   -1892     201  9725.3     201
  9737.1  201.46  9746.7  204.99  9760.6  200.26  9806.3  200.26  9847.3  205.18
 10152.9  207.37 10479.7  214.22 10531.9  218.16 10589.9  217.71 10635.1  220.77
#Mann= 5 ,-1 , 0
 -3228.3     .11       0 -2724.3    .125       0 -2649.5     .11       0
 -2058.4    .015       0 10152.9     .11       0
#XS Ineff= 2 , 0
       0                  9746.7       0  204.99
Permanent Ineff=
       F       F
Bank Sta=-2058.4,10152.9
XS Rating Curve= 0 ,0
Exp/Cntr=0.3,0.1

Chan Stop Cuts=-1
Use User Specified Reach Order=0
Composite Channel Slope=5