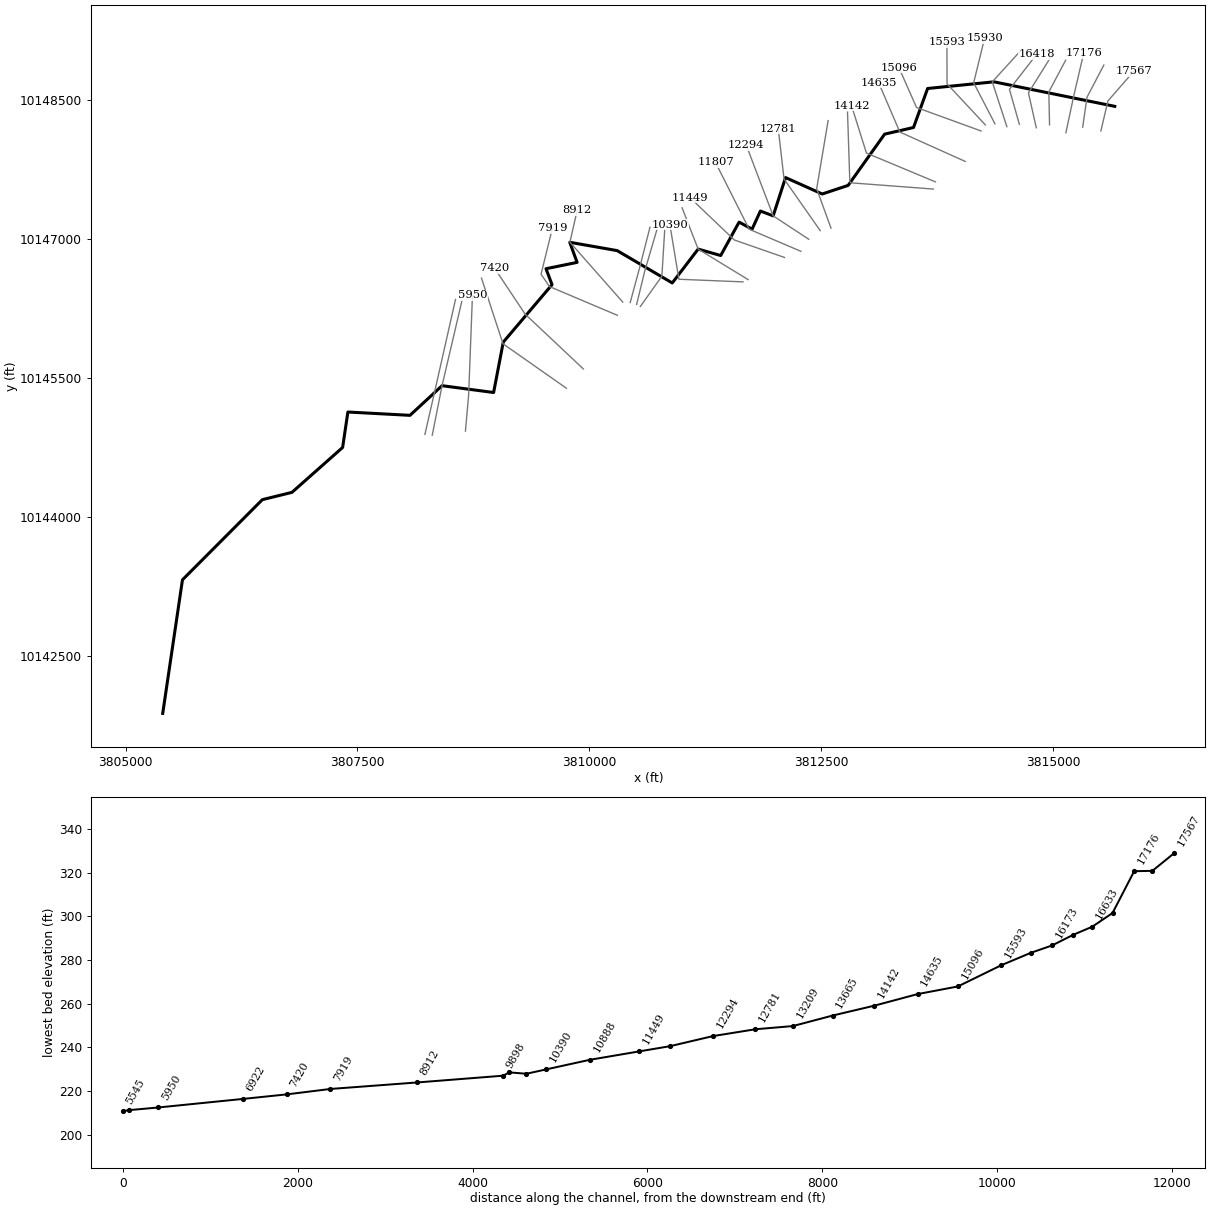
--- LIVE BRANCH.prj (project) ---

Proj Title=LIVE BRANCH Base Level Engineering
Current Plan=p01
Default Exp/Contr=0.3,0.1
English Units
Geom File=g01
Flow File=f01
Plan File=p01
Y Axis Title=Elevation
X Axis Title(PF)=Main Channel Distance
X Axis Title(XS)=Station
BEGIN DESCRIPTION:
LIVE BRANCH
END DESCRIPTION:
DSS Export Rating Curves= 0
DSS Export Rating Curve Sorted= 0
DSS Export Volume Flow Curves= 0
DXF OffsetX= 0
DXF OffsetY= 0
DXF ScaleX= 1
DXF ScaleY= 10

--- LIVE BRANCH.p01 (plan) ---

Plan Title=Multiple Run
Short Identifier=Multiple
Geom File=g01
Flow File=f01
Subcritical Flow
K Sum by GR= 0
Std Step Tol= 0.01
Critical Tol= 0.01
Num of Std Step Trials= 20
Max Error Tol= 0.3
Flow Tol Ratio= 0.001
Split Flow NTrial= 30
Split Flow Tol= 0.02
Split Flow Ratio= 0.02
Log Output Level= 0
Friction Slope Method= 1
Unsteady Friction Slope Method= 2
Unsteady Bridges Friction Slope Method= 1
Parabolic Critical Depth
Global Vel Dist=  1 , 1 , 1
Global Log Level= 0
CheckData=True
Encroach Param= -1, 0, 0, 0
BEGIN DESCRIPTION:
Multiple Run
END DESCRIPTION:

--- LIVE BRANCH.f01 (steady flow) ---

Flow Title=Multiple
Program Version=4.10
Number of Profiles= 7
Profile Names=10-year,25-year,50-year,1pct_min,100-year,1pct_plu,500-year
River Rch & RM=LIVE BRANCH,Reach-1         ,17567
     200     252     324     139     420    1268     722
River Rch & RM=LIVE BRANCH,Reach-1         ,15593
     584     791    1068     476    1439    4346    2692
River Rch & RM=LIVE BRANCH,Reach-1         ,10162
    1289    1809    2506    1139    3441   10392    6710
River Rch & RM=LIVE BRANCH,Reach-1         ,2657
    2023    2895    4058    1865    5633   17011   11228
River Rch & RM=LIVE BRANCH,Reach-1         ,2515
    2023    2895    4058    1865    5633   17011   11228
River Rch & RM=LIVE BRANCH,Reach-1         ,2000
    2023    2895    4058    1865    5633   17011   11228
River Rch & RM=LIVE BRANCH,Reach-1         ,1500
    2023    2895    4058    1865    5633   17011   11228
River Rch & RM=LIVE BRANCH,Reach-1         ,1000
    2023    2895    4058    1865    5633   17011   11228
River Rch & RM=LIVE BRANCH,Reach-1         ,500
    2023    2895    4058    1865    5633   17011   11228
Boundary for River Rch & Prof#=LIVE BRANCH,Reach-1         , 1
Up Type= 0
Dn Type= 3
Dn Slope=0.001
Boundary for River Rch & Prof#=LIVE BRANCH,Reach-1         , 2
Up Type= 0
Dn Type= 3
Dn Slope=0.001
Boundary for River Rch & Prof#=LIVE BRANCH,Reach-1         , 3
Up Type= 0
Dn Type= 3
Dn Slope=0.001
Boundary for River Rch & Prof#=LIVE BRANCH,Reach-1         , 4
Up Type= 0
Dn Type= 3
Dn Slope=0.001
Boundary for River Rch & Prof#=LIVE BRANCH,Reach-1         , 5
Up Type= 0
Dn Type= 3
Dn Slope=0.001
Boundary for River Rch & Prof#=LIVE BRANCH,Reach-1         , 6
Up Type= 0
Dn Type= 3
Dn Slope=0.001
Boundary for River Rch & Prof#=LIVE BRANCH,Reach-1         , 7
Up Type= 0
Dn Type= 3
Dn Slope=0.001
DSS Import GetInterval= 0
DSS Import GetPeak= 0
DSS Import FillOption= 0

--- LIVE BRANCH.g01 (geometry) ---

Geom Title=Existing Conditions
Program Version=4.10

River Reach=LIVE BRANCH     ,Reach-1
Reach XY= 30
      3815660.76     10148430.47      3814358.63     10148694.97
      3813644.05     10148622.94      3813492.06     10148202.37
      3813180.79     10148130.73      3812787.57     10147578.04
       3812508.2     10147485.15      3812113.01     10147662.35
      3811979.44     10147249.48      3811841.84     10147301.56
       3811752.3     10147105.82       3811612.5     10147181.98
      3811414.03     10146821.59      3811171.22     10146891.03
      3810892.09     10146525.75      3810298.26     10146874.67
      3809787.47     10146964.41       3809866.6     10146747.75
      3809531.49     10146679.17      3809596.47     10146507.46
      3809070.88     10145887.67        3808967.     10145344.26
      3808411.25     10145417.91      3808065.79     10145098.14
      3807396.52     10145133.84      3807339.77     10144751.63
      3806794.16     10144267.69       3806474.7     10144188.62
      3805613.84     10143324.37      3805401.16     10141883.89

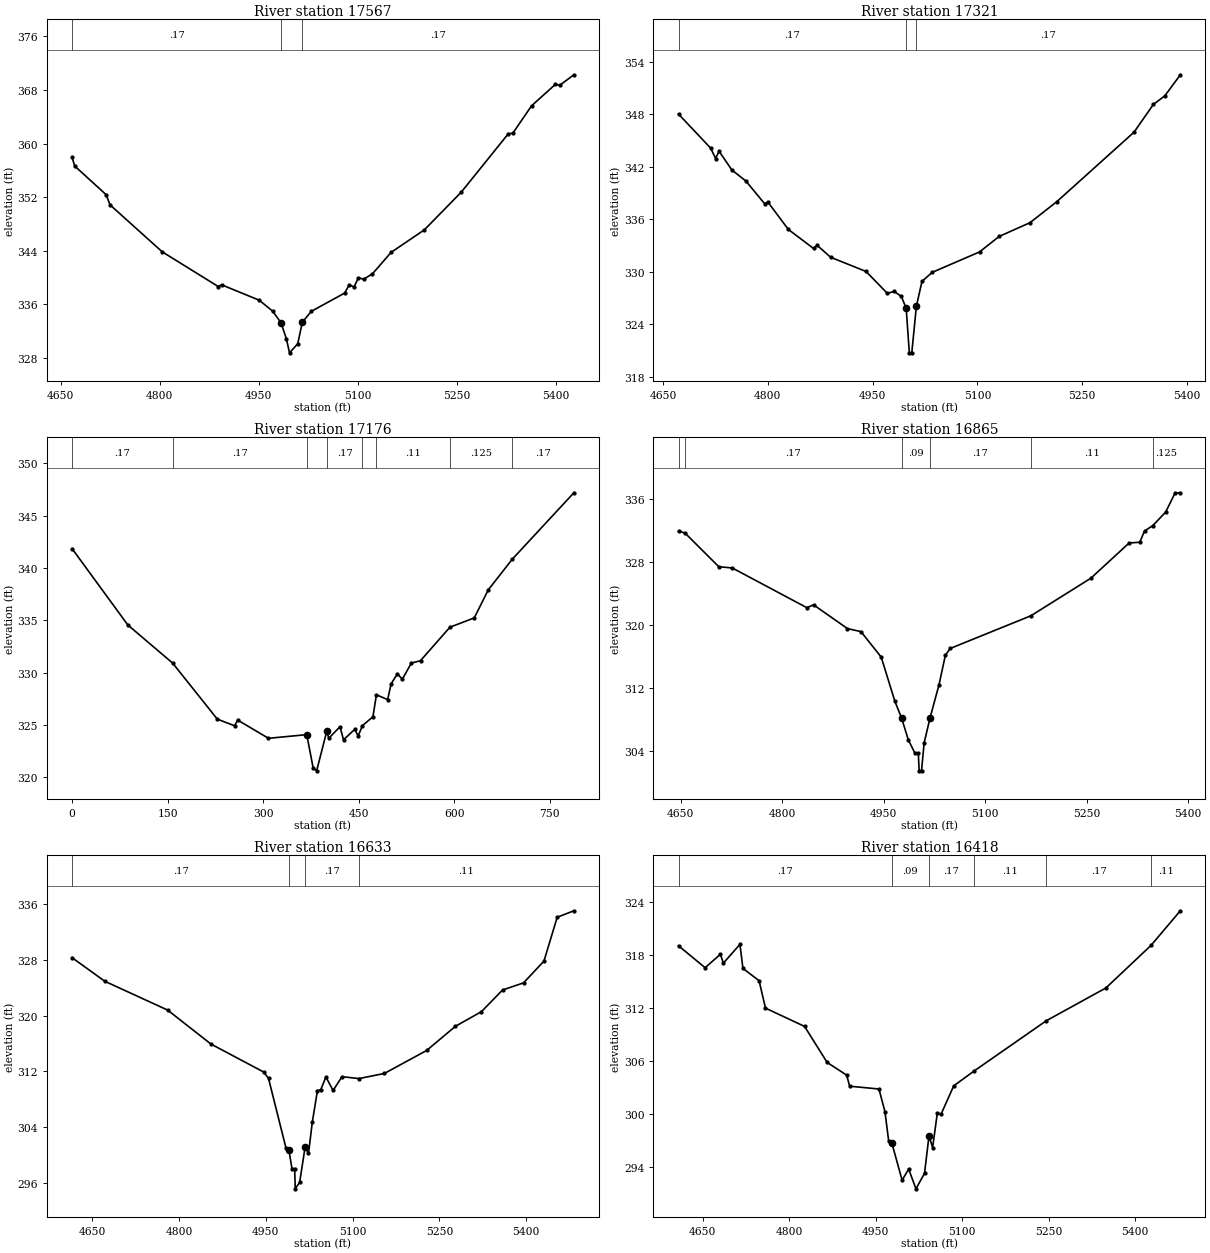
Type RM Length L Ch R = 1 ,17567   ,246,246,246
BEGIN DESCRIPTION:
LIVE BRANCH 29.0
END DESCRIPTION:
XS GIS Cut Line= 3
      3815511.26     10148165.08      3815587.15     10148488.81
      3815867.87     10148811.09
#Sta/Elev= 30
  4667.5  357.94  4671.5  356.65  4719.1  352.37    4725  350.85    4804  343.84
  4888.9  338.65    4894  338.91    4951  336.61  4971.5  334.95    4984  333.23
  4992.1  330.83  4996.8  328.75  5009.2   330.1  5016.3  333.35    5030  334.96
  5080.4  337.68    5087  338.87  5094.6   338.6  5101.2  339.98  5108.9  339.74
  5122.4  340.55  5150.6  343.75    5201  347.12  5256.9  352.75  5328.2  361.48
  5334.8  361.53  5363.3  365.64  5399.4  368.85    5406  368.71  5427.4  370.28
#Mann= 3 , 0 , 0
  4667.5     .17       0    4984     .09       0  5016.3     .17       0
Bank Sta=4984,5016.3
XS Rating Curve= 0 ,0
Exp/Cntr=0.3,0.1

Type RM Length L Ch R = 1 ,17321   ,208,208,208
BEGIN DESCRIPTION:
Mapping XS 848a9a8e
END DESCRIPTION:
XS GIS Cut Line= 3
      3815314.93      10148205.6      3815362.15     10148529.78
      3815543.12     10148875.59
#Sta/Elev= 30
  4672.4  348.02  4718.4  344.13  4725.4  342.95  4730.4  343.78  4748.7  341.64
  4768.9  340.37  4795.4   337.8  4800.5  337.95  4829.5  334.85  4865.5  332.68
  4870.6  333.04  4890.1  331.67  4940.7  330.05    4971  327.56  4981.1  327.77
  4991.2   327.2  4998.1  325.84  5002.6  320.76  5006.1  320.76  5012.7  326.09
  5020.7  328.92  5035.3  329.95    5103  332.28  5131.1  334.05  5175.2  335.62
  5213.7  338.03  5324.1  345.96  5351.8  349.13  5368.2  350.11  5390.3  352.51
#Mann= 3 ,-1 , 0
  4672.4     .17       0  4998.1     .09       0  5012.7     .17       0
#XS Ineff= 2 , 0
       0  4981.1  327.77               0
Permanent Ineff=
       F       F
Bank Sta=4998.1,5012.7
XS Rating Curve= 0 ,0
Exp/Cntr=0.3,0.1

Type RM Length L Ch R = 1 ,17176   ,248,248,248
BEGIN DESCRIPTION:
LIVE BRANCH 28.0
END DESCRIPTION:
XS GIS Cut Line= 3
      3815134.11     10148145.76      3815218.75     10148542.89
      3815325.52     10149001.23
#Sta/Elev= 30
       0  341.84    87.6  334.54   157.9   330.9   228.1  325.54   255.1  324.91
   260.1  325.45   308.4  323.71   368.5  324.06   378.5   320.9     384   320.6
     400   324.4   403.1  323.71   420.7  324.82   426.2  323.57   443.8  324.56
   449.3  323.94   455.9  324.92   472.4  325.77   477.9  327.87   495.5  327.41
     501  328.92   510.8  329.87   518.6  329.36   532.7   330.9   547.1  331.13
   593.3  334.33   631.5  335.22   653.5   337.9   691.2  340.83   787.9  347.18
#Mann= 8 ,-1 , 0
       0     .17       0   157.9     .17       0   368.5     .07       0
     400     .17       0   455.9     .17       0   477.9     .11       0
   593.3    .125       0   691.2     .17       0
Bank Sta=368.5,400
XS Rating Curve= 0 ,0
Exp/Cntr=0.3,0.1

Type RM Length L Ch R = 1 ,16865   ,232,232,232
BEGIN DESCRIPTION:
Mapping XS ad780a5f
END DESCRIPTION:
XS GIS Cut Line= 3
      3814957.98     10148231.64      3814950.17     10148585.84
      3815131.53     10148927.84
#Sta/Elev= 30
  4646.9  331.97  4656.5  331.72  4706.3  327.44  4726.4  327.27  4836.4  322.22
  4846.4  322.58  4896.4  319.56  4916.4  319.17  4946.4  315.92  4966.4  310.33
  4976.4  308.17  4986.4  305.39  4996.3  303.66  5001.2  303.66  5002.4  301.44
  5005.9  301.44  5009.8     305  5018.4  308.15  5031.8  312.42  5041.1  316.14
  5048.2  317.02  5167.6  321.19  5256.1  325.97  5312.7  330.46  5328.4  330.55
  5335.4  331.99  5347.5  332.66  5366.7   334.4  5380.6  336.84  5388.3  336.85
#Mann= 6 ,-1 , 0
  4646.9     .11       0  4656.5     .17       0  4976.4     .09       0
  5018.4     .17       0  5167.6     .11       0  5347.5    .125       0
Bank Sta=4976.4,5018.4
XS Rating Curve= 0 ,0
Exp/Cntr=0.3,0.1

Type RM Length L Ch R = 1 ,16633   ,215,215,215
BEGIN DESCRIPTION:
LIVE BRANCH 27.0
END DESCRIPTION:
XS GIS Cut Line= 3
      3814815.09     10148199.88      3814730.55     10148575.18
      3814985.28     10148984.96
#Sta/Elev= 30
  4615.3  328.29  4671.9  324.91  4780.5  320.78  4855.2  315.92  4946.8  311.89
  4954.8  310.99    4985  301.01  4990.1   300.7  4995.3  298.07    5000  298.07
    5001  295.17  5008.6  296.11  5018.1  301.17  5023.9  300.24  5030.5  304.73
  5039.3  309.22  5045.2   309.4    5054   311.2  5066.4  309.26  5081.8  311.24
  5111.1  310.97    5155   311.7  5228.2     315  5277.8  318.46  5322.7  320.55
  5359.3  323.66  5395.5  324.68  5430.8   327.8  5453.7  334.08  5482.5  335.01
#Mann= 4 ,-1 , 0
  4615.3     .17       0  4990.1     .09       0  5018.1     .17       0
  5111.1     .11       0
#XS Ineff= 2 , 0
       0                  5018.1       0  301.17
Permanent Ineff=
       F       F
Bank Sta=4990.1,5018.1
XS Rating Curve= 0 ,0
Exp/Cntr=0.3,0.1

Type RM Length L Ch R = 1 ,16418   ,245,245,245
BEGIN DESCRIPTION:
Mapping XS a5d2caa4
END DESCRIPTION:
XS GIS Cut Line= 3
      3814632.82     10148236.68       3814525.8     10148613.48
      3814819.21     10148991.59
#Sta/Elev= 30
  4608.3     319  4654.4  316.52  4680.9  318.04  4686.1  317.04  4714.8  319.16
    4720  316.44    4748  315.05  4759.1  311.95  4826.9  309.88    4866  305.81
  4899.9  304.37  4905.1  303.12  4955.9   302.8  4966.3  300.24  4972.8  296.91
    4978  296.75  4996.1  292.48  5007.4  293.75  5020.1  291.51  5034.9  293.26
  5042.7  297.49    5049  296.18  5057.2  300.12  5063.5  299.93  5085.6  303.16
  5120.1   304.8  5246.1  310.52  5349.5  314.23  5427.7  319.04  5478.6  322.96
#Mann= 6 ,-1 , 0
  4608.3     .17       0    4978     .09       0  5042.7     .17       0
  5120.1     .11       0  5246.1     .17       0  5427.7     .11       0
Bank Sta=4978,5042.7
XS Rating Curve= 0 ,0
Exp/Cntr=0.3,0.1

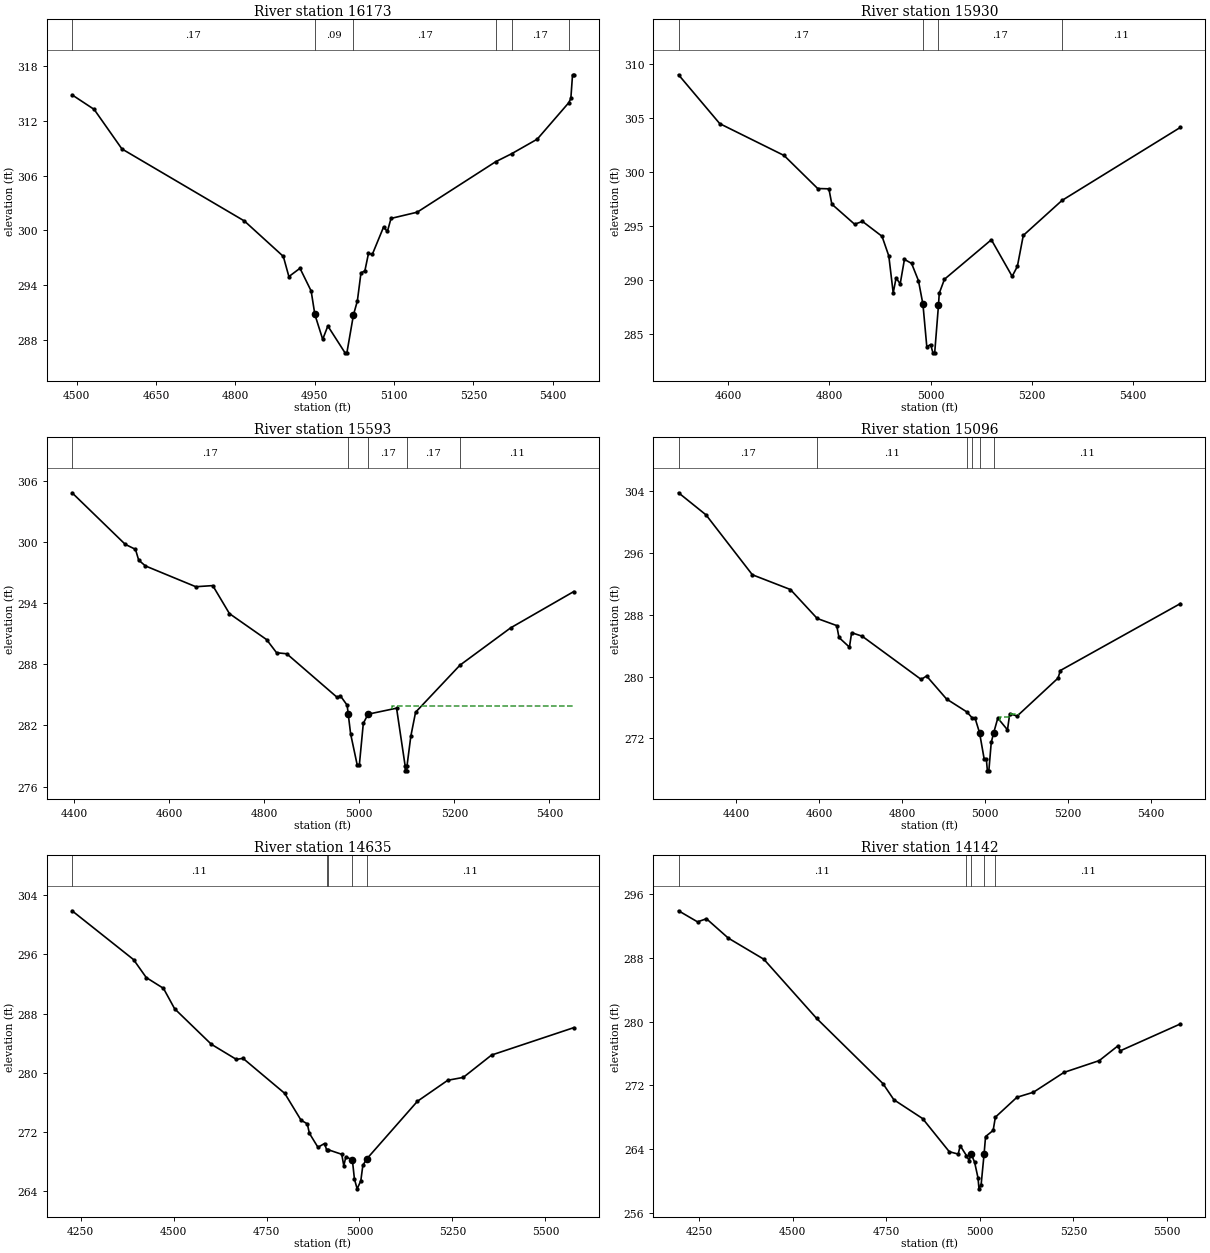
Type RM Length L Ch R = 1 ,16173   ,243,243,243
BEGIN DESCRIPTION:
LIVE BRANCH 26.0
END DESCRIPTION:
XS GIS Cut Line= 3
      3814497.96     10148211.46       3814340.7     10148694.92
       3814637.2     10149019.75
#Sta/Elev= 30
  4491.6  314.83  4533.3  313.24  4585.8  308.91  4817.2  301.02  4890.8  297.14
  4901.3  294.93  4922.3  295.84  4943.4  293.35 4950.37  290.78  4965.2  288.06
  4974.9  289.52  5007.4  286.58  5010.9  286.58  5023.3  290.73  5030.7  292.26
  5037.5  295.33  5044.9  295.56  5051.7  297.46  5059.1  297.38  5080.1  300.34
  5087.5  299.88  5094.3   301.3  5143.7  301.98  5292.1  307.51  5322.1  308.38
  5370.6  309.98    5430  313.96  5434.1  314.44  5437.3  317.03  5439.8  317.03
#Mann= 6 ,-1 , 0
  4491.6     .17       0 4950.37     .09       0  5023.3     .17       0
  5292.1     .11       0  5322.1     .17       0    5430    .125       0
Bank Sta=4950.37,5023.3
XS Rating Curve= 0 ,0
Exp/Cntr=0.3,0.1

Type RM Length L Ch R = 1 ,15930   ,337,337,337
BEGIN DESCRIPTION:
Mapping XS 7efa10af
END DESCRIPTION:
XS GIS Cut Line= 3
      3814369.45     10148242.06      3814140.28     10148684.53
      3814257.45     10149163.92
#Sta/Elev= 30
  4501.7  308.98  4583.2  304.45  4710.3   301.5  4776.7  298.44  4798.9  298.41
  4804.7  296.99  4849.7  295.13  4865.3  295.39  4903.9  294.01  4917.3  292.19
    4926  288.76  4931.7  290.15  4939.8   289.6  4948.2  291.87  4962.3   291.5
  4975.9   289.9  4984.8   287.7  4992.4  283.78    5000  283.98  5004.5  283.21
    5008  283.21 5015.51  287.64    5017  288.73  5027.3  290.03    5120  293.69
  5161.1   290.3  5171.4  291.22  5183.1  294.09  5259.5  297.33  5493.5   304.1
#Mann= 4 ,-1 , 0
  4501.7     .17       0  4984.8     .09       0 5015.51     .17       0
  5259.5     .11       0
#XS Ineff= 2 , 0
       0  4948.2  291.87    5120       0  293.69
Permanent Ineff=
       F       F
Bank Sta=4984.8,5015.51
XS Rating Curve= 0 ,0
Exp/Cntr=0.3,0.1

Type RM Length L Ch R = 1 ,15593   ,497,497,497
BEGIN DESCRIPTION:
LIVE BRANCH 25.0
END DESCRIPTION:
XS GIS Cut Line= 3
      3814265.92     10148230.78      3813853.39     10148672.77
       3813852.1     10149124.17
#Sta/Elev= 30
  4395.4  304.83  4507.3  299.77  4528.8  299.28  4535.6  298.22  4549.8  297.65
  4655.8  295.61  4691.5  295.72  4726.6  292.97  4804.8  290.42  4825.8  289.13
  4847.2  289.03  4953.3  284.75  4960.1   284.9  4974.3  283.98 4976.52  283.13
  4981.6  281.17  4995.4  278.13    5000  278.13  5008.3   282.2  5018.3   283.1
  5078.3  283.69  5096.3  278.04  5096.5  277.54    5100  277.54  5100.3  278.04
  5108.3  280.94  5118.3  283.29  5211.7  287.91  5318.3  291.57  5451.4  295.14
#Mann= 5 ,-1 , 0
  4395.4     .17       0 4976.52     .09       0  5018.3     .17       0
  5100.3     .17       0  5211.7     .11       0
#XS Ineff= 2 , 0
       0                  5068.3       0  283.88
Permanent Ineff=
       F       T
Bank Sta=4976.52,5018.3
XS Rating Curve= 0 ,0
Exp/Cntr=0.3,0.1

Type RM Length L Ch R = 1 ,15096   ,461,461,461
BEGIN DESCRIPTION:
LIVE BRANCH 24.0
END DESCRIPTION:
XS GIS Cut Line= 3
      3814219.55     10148165.02      3813524.77     10148417.98
      3813334.64     10148847.81
#Sta/Elev= 30
  4260.6  303.76  4326.9   300.9  4438.5  293.16  4530.3  291.25  4594.8  287.51
  4641.9  286.59  4647.3  285.05  4672.5   283.8  4677.8  285.67  4703.1  285.22
  4845.3  279.63  4858.4  280.07  4906.5   277.1  4955.4  275.43  4967.6   274.7
  4975.4   274.6  4986.1  272.74  4997.2  269.35  5002.4  269.35    5005  267.81
  5008.5  267.81  5014.3  271.49 5020.19  272.74  5030.1  274.63  5053.4  273.11
  5058.9   275.2  5076.7  274.89  5175.3   279.8  5180.8  280.78    5470  289.43
#Mann= 6 ,-1 , 0
  4260.6     .17       0  4594.8     .11       0  4955.4     .17       0
  4967.6     .11       0  4986.1     .06       0 5020.19     .11       0
#XS Ineff= 2 ,-1
  5036.2  5058.9  274.76  5058.9  5082.1   275.2
Permanent Ineff=
       F       F
Bank Sta=4986.1,5020.19
XS Rating Curve= 0 ,0
Exp/Cntr=0.3,0.1

Type RM Length L Ch R = 1 ,14635   ,493,493,493
BEGIN DESCRIPTION:
LIVE BRANCH 23.0
END DESCRIPTION:
XS GIS Cut Line= 3
      3814049.36     10147836.29      3813344.55     10148153.51
      3813117.26     10148683.31
#Sta/Elev= 30
  4227.1  301.91  4392.4  295.31  4426.6  292.88  4472.9  291.42  4502.9  288.66
  4601.6  283.86    4669  281.81  4686.7  281.96    4799  277.22  4842.9  273.59
  4859.7   273.1  4865.2  271.83  4888.3  269.93    4906  270.44    4912  269.53
  4914.6  269.62  4952.3  268.98  4957.8  267.43  4963.5  268.66  4980.9   268.2
  4986.4  265.64  4993.7  264.31  5003.6   265.4    5009  267.47  5019.1  268.33
  5155.8  276.15  5237.4  278.99  5279.1  279.38  5355.2   282.4  5576.5  286.11
#Mann= 5 ,-1 , 0
  4227.1     .11       0    4912     .17       0  4914.6     .11       0
  4980.9     .06       0  5019.1     .11       0
#XS Ineff= 2 , 0
       0    4906  270.44               0
Permanent Ineff=
       F       F
Bank Sta=4980.9,5019.1
XS Rating Curve= 0 ,0
Exp/Cntr=0.3,0.1

Type RM Length L Ch R = 1 ,14142   ,477,477,477
BEGIN DESCRIPTION:
LIVE BRANCH 22.0
END DESCRIPTION:
XS GIS Cut Line= 3
      3813728.31     10147615.86      3812984.89     10147926.49
       3812823.9     10148437.84
#Sta/Elev= 30
  4194.3  293.91  4245.1  292.52  4268.9  292.91  4327.4  290.48  4422.4  287.83
  4563.3  280.42  4740.8  272.23  4770.1   270.2  4846.9  267.84  4918.3  263.68
  4942.1  263.38  4947.5  264.43  4964.1   263.2  4971.3  262.57  4976.8  263.39
    4986  262.36  4995.2  260.37  4997.7  259.02  5003.4  259.52 5011.35  263.39
  5015.3  265.58  5035.6  266.35  5041.5  268.01  5099.2  270.51  5143.2  271.14
    5225  273.63  5319.3  275.11  5369.8  276.98    5375  276.33  5536.1  279.71
#Mann= 5 ,-1 , 0
  4194.3     .11       0  4964.1     .17       0  4976.8     .09       0
 5011.35     .17       0  5041.5     .11       0
Bank Sta=4976.8,5011.35
XS Rating Curve= 0 ,0
Exp/Cntr=0.3,0.1

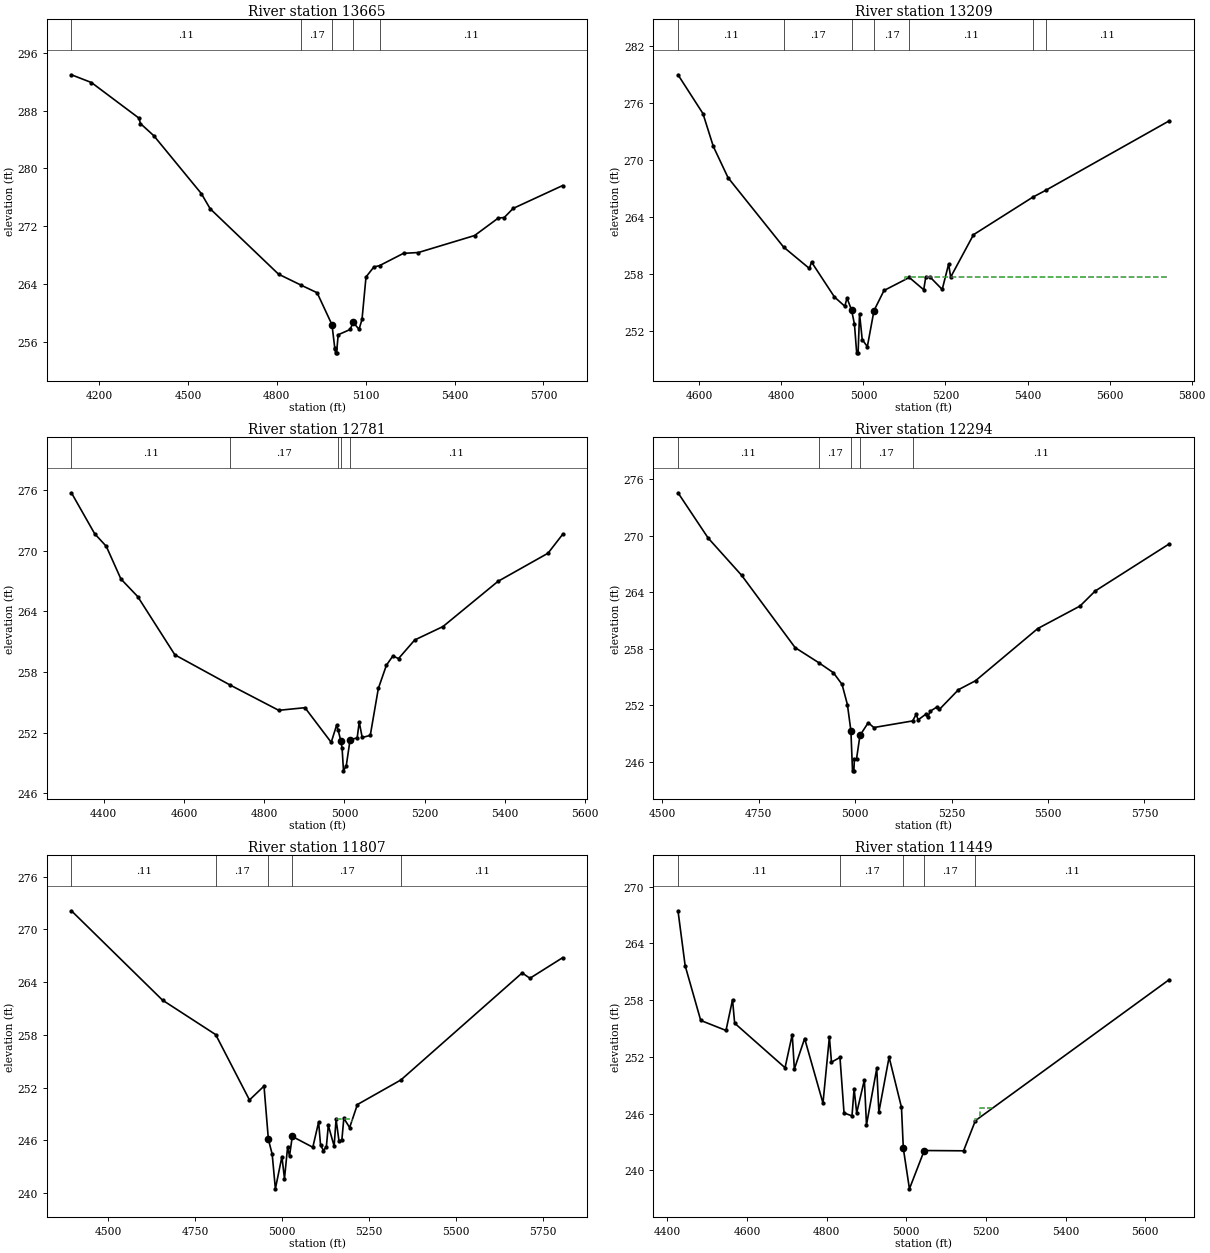
Type RM Length L Ch R = 1 ,13665   ,456,456,456
BEGIN DESCRIPTION:
LIVE BRANCH 21.5
END DESCRIPTION:
XS GIS Cut Line= 4
      3813705.14      10147538.5      3812814.08     10147605.79
      3812805.57     10147620.71      3812780.87     10148368.03
#Sta/Elev= 30
  4106.4  292.95  4173.9  291.88  4334.3  286.96  4339.6   286.2  4384.5  284.53
  4544.9  276.53    4575  274.42  4805.7  265.38  4882.4  263.85    4936  262.81
  4986.2  258.39  4995.6  255.17    4998     255  4998.2   254.5  5001.7   254.5
  5007.2     257  5047.6  257.73  5057.6  258.72  5077.6  257.75  5087.6  259.12
  5101.1  264.99  5127.6  266.37  5146.8  266.56  5227.7  268.26  5277.7  268.37
  5467.8  270.72  5547.8  273.14  5567.8  273.21  5597.9  274.47  5764.9  277.63
#Mann= 5 ,-1 , 0
  4106.4     .11       0  4882.4     .17       0  4986.2     .09       0
  5057.6     .17       0  5146.8     .11       0
Bank Sta=4986.2,5057.6
XS Rating Curve= 0 ,0
Exp/Cntr=0.3,0.1

Type RM Length L Ch R = 1 ,13209   ,428,428,428
BEGIN DESCRIPTION:
LIVE BRANCH 20.0
END DESCRIPTION:
XS GIS Cut Line= 3
      3812602.91     10147116.91      3812448.42     10147541.69
      3812571.86      10148276.6
#Sta/Elev= 30
    4548  278.93  4608.8  274.85  4634.1  271.39    4670   268.1  4805.4   260.8
  4868.2  258.55  4873.5  259.22  4929.3  255.55  4954.6  254.57  4959.9  255.43
 4971.04  254.18  4978.1  252.68  4983.5  249.67    4987  249.67  4990.5   253.8
    4997  251.07  5009.5  250.32  5025.7  254.11  5050.1  256.23  5111.7   257.6
  5146.9  256.31    5152  257.66  5161.6  257.68    5192  256.34  5207.6  259.01
  5212.6  257.64  5268.2   262.1  5412.7  266.05  5444.3  266.77  5745.2  274.08
#Mann= 7 ,-1 , 0
    4548     .11       0  4805.4     .17       0 4971.04     .09       0
  5025.7     .17       0  5111.7     .11       0  5412.7     .17       0
  5444.3     .11       0
#XS Ineff= 2 , 0
       0                  5100.8       0  257.67
Permanent Ineff=
       F       F
Bank Sta=4971.04,5025.7
XS Rating Curve= 0 ,0
Exp/Cntr=0.3,0.1

Type RM Length L Ch R = 1 ,12781   ,487,487,487
BEGIN DESCRIPTION:
LIVE BRANCH 19.0
END DESCRIPTION:
XS GIS Cut Line= 3
      3812486.89     10147089.85      3812096.79     10147647.31
       3812034.5     10148187.13
#Sta/Elev= 30
  4319.6  275.73  4377.5  271.68  4406.5  270.43  4442.9   267.2  4484.7  265.46
  4577.4  259.69  4714.2  256.72  4836.1   254.2  4901.5  254.46  4966.9  251.03
  4980.2  252.71  4983.8  252.29 4990.63  251.21    4994  250.46  4997.5  248.21
  5004.4  248.71  5013.9  251.29  5031.6  251.47  5036.7  253.04  5044.1  251.51
  5064.2  251.72  5084.3  256.36  5104.5  258.67  5120.6  259.58  5134.6  259.32
  5174.9  261.16  5245.4  262.49  5382.3  266.96  5507.1  269.75  5543.4  271.61
#Mann= 5 ,-1 , 0
  4319.6     .11       0  4714.2     .17       0  4983.8     .11       0
 4990.63     .07       0  5013.9     .11       0
#XS Ineff= 2 , 0
       0  4901.5  254.46               0
Permanent Ineff=
       F       F
Bank Sta=4990.63,5013.9
XS Rating Curve= 0 ,0
Exp/Cntr=0.3,0.1

Type RM Length L Ch R = 1 ,12294   ,487,487,487
BEGIN DESCRIPTION:
LIVE BRANCH 18.0
END DESCRIPTION:
XS GIS Cut Line= 3
      3812363.14     10146997.03      3811979.44     10147249.48
      3811690.16     10148010.34
#Sta/Elev= 30
  4540.7  274.54  4618.9  269.74  4705.7  265.79  4844.3  258.13  4905.3  256.54
  4943.6  255.47    4966  254.23  4979.8   252.1  4988.9  249.33  4993.1  245.07
  4996.6  245.07    4998  246.33  5003.5  246.33  5012.4  248.82  5033.8  250.17
  5048.3  249.66    5149  250.36    5158  251.05  5163.4  250.48  5182.8  251.06
  5188.2  250.74  5194.3  251.38  5212.9  251.86  5218.3  251.58  5267.8  253.67
    5312  254.62  5473.3  260.15    5583  262.54  5622.2  264.13    5814  269.12
#Mann= 5 ,-1 , 0
  4540.7     .11       0  4905.3     .17       0  4988.9     .09       0
  5012.4     .17       0    5149     .11       0
Bank Sta=4988.9,5012.4
XS Rating Curve= 0 ,0
Exp/Cntr=0.3,0.1

Type RM Length L Ch R = 1 ,11807   ,358,358,358
BEGIN DESCRIPTION:
LIVE BRANCH 17.0
END DESCRIPTION:
XS GIS Cut Line= 3
      3812278.86      10146866.9      3811721.34     10147105.16
      3811358.22      10147825.4
#Sta/Elev= 30
  4393.7  272.12  4655.8  261.95  4808.7  258.03  4905.9  250.59  4947.7  252.17
  4960.3   246.1  4971.2  244.43  4980.4  240.48  4999.2  244.14  5006.6  241.64
  5015.5   245.2  5021.1  244.21    5029  246.44  5088.1  245.21  5104.8  248.08
  5110.4  245.45  5118.6  244.84  5127.1  245.28  5132.7  247.69  5149.4  245.34
    5155   248.4  5163.4  245.92  5171.7  246.05  5177.3  248.51    5194  247.45
  5216.3  250.07  5341.5  252.87  5690.3  265.05  5712.6  264.44  5806.6  266.78
#Mann= 5 ,-1 , 0
  4393.7     .11       0  4808.7     .17       0  4960.3     .09       0
    5029     .17       0  5341.5     .11       0
#XS Ineff= 2 ,-1
  5104.8    5155  248.08    5155  5199.6   248.4
Permanent Ineff=
       F       F
Bank Sta=4960.3,5029
XS Rating Curve= 0 ,0
Exp/Cntr=0.3,0.1

Type RM Length L Ch R = 1 ,11449   ,561,561,561
BEGIN DESCRIPTION:
Mapping XS d942c333
END DESCRIPTION:
XS GIS Cut Line= 3
      3812101.73     10146800.83      3811561.27     10146989.23
      3811082.73     10147446.01
#Sta/Elev= 30
  4426.4  267.44  4444.4  261.63  4483.5  255.85    4547  254.79  4563.4  258.04
  4568.7  255.56  4695.3  250.85  4713.4  254.36  4718.7  250.71  4744.5  253.94
  4790.6  247.11  4806.7  254.09    4812  251.44  4833.3  251.94  4843.5  246.07
  4863.5  245.76  4868.8  248.64  4875.3  246.08  4894.6  249.57  4899.9  244.81
  4925.7  250.77    4931  246.16  4956.7  251.97  4987.8  246.66 4992.43  242.33
  5007.8  238.05    5045   242.1  5143.8  242.07  5173.5  245.26  5660.3  260.16
#Mann= 5 ,-1 , 0
  4426.4     .11       0  4833.3     .17       0 4992.43     .09       0
    5045     .17       0  5173.5     .11       0
#XS Ineff= 3 ,-1
  5172.1  5186.3  245.39  5186.3  5221.8  246.61  4956.7  4806.7  251.97
Permanent Ineff=
       F       F       F
Bank Sta=4992.43,5045
XS Rating Curve= 0 ,0
Exp/Cntr=0.3,0.1

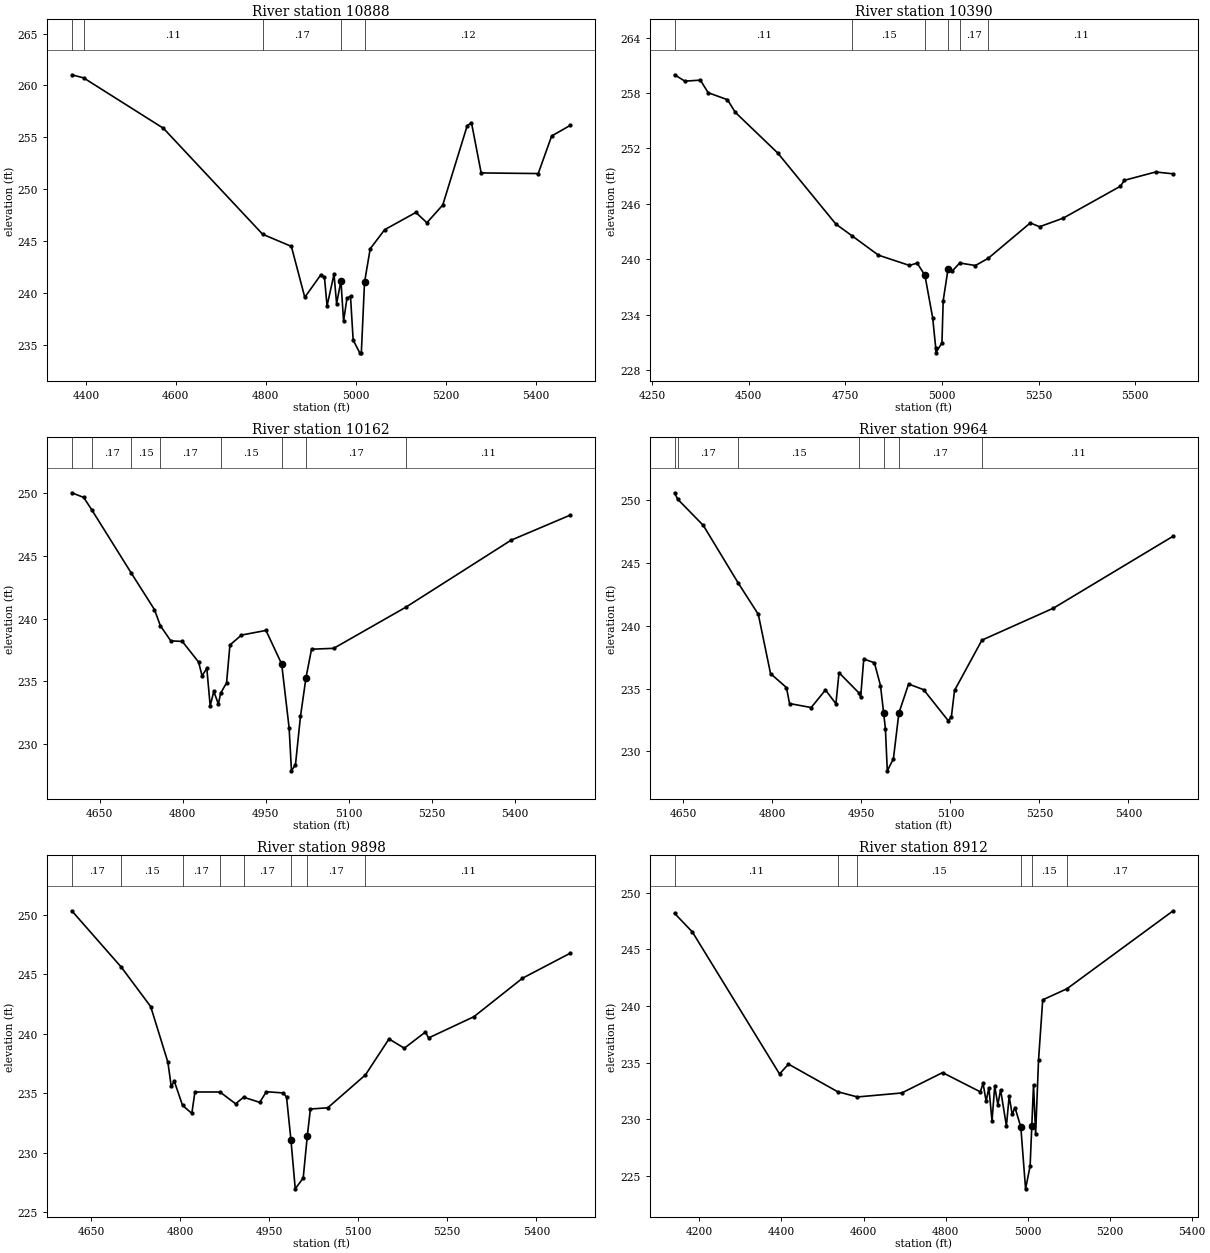
Type RM Length L Ch R = 1 ,10888   ,498,498,498
BEGIN DESCRIPTION:
LIVE BRANCH 15.0
END DESCRIPTION:
XS GIS Cut Line= 3
      3811710.05      10146561.7      3811171.22     10146891.03
      3810998.23     10147335.99
#Sta/Elev= 30
  4368.5  261.03  4394.8  260.73  4572.4  255.87    4793  245.66  4856.9  244.49
  4886.7  239.58  4921.9  241.72  4930.4  241.56  4936.2  238.75  4951.7   241.8
  4957.5  238.97  4967.1  241.17    4973  237.27  4980.5  239.49  4988.4  239.69
  4994.3  235.46    5009  234.23  5012.5  234.23  5019.6  241.03  5032.2  244.26
  5064.4   246.1  5133.8  247.76  5158.3  246.77  5193.6  248.48    5248  256.13
  5257.5   256.4    5279  251.57  5405.9  251.51  5435.8  255.13  5477.4  256.16
#Mann= 5 ,-1 , 0
  4368.5    .125       0  4394.8     .11       0    4793     .17       0
  4967.1     .07       0  5019.6     .12       0
Bank Sta=4967.1,5019.6
XS Rating Curve= 0 ,0
Exp/Cntr=0.3,0.1

Type RM Length L Ch R = 1 ,10390   ,228,228,228
BEGIN DESCRIPTION:
LIVE BRANCH 14.0
END DESCRIPTION:
XS GIS Cut Line= 3
      3811654.45     10146537.42      3810963.83     10146565.71
      3810866.27      10147155.5
#Sta/Elev= 30
  4308.8  259.97  4335.4  259.28  4375.5  259.39  4395.5  258.03  4445.5  257.27
  4465.5  255.91  4575.6  251.49  4725.7   243.8  4768.7  242.49  4835.8  240.43
  4915.9  239.32  4935.9  239.57  4955.9  238.26    4976  233.65    4984  230.35
  4984.2  229.85    5000  230.93  5003.2   235.5  5015.6  238.88  5025.7  238.67
  5045.9  239.58  5086.5  239.31  5119.6  240.09  5228.4  243.92  5252.4  243.51
  5313.5  244.44  5461.5   247.9  5471.7  248.54  5552.6  249.44  5597.8  249.24
#Mann= 6 ,-1 , 0
  4308.8     .11       0  4768.7     .15       0  4955.9     .09       0
  5015.6     .15       0  5045.9     .17       0  5119.6     .11       0
Bank Sta=4955.9,5015.6
XS Rating Curve= 0 ,0
Exp/Cntr=0.3,0.1

Type RM Length L Ch R = 1 ,10162   ,198,198,198
BEGIN DESCRIPTION:
LIVE BRANCH 21.0
END DESCRIPTION:
XS GIS Cut Line= 3
      3810547.98      10146271.9      3810780.11     10146598.14
      3810810.88      10147098.1
#Sta/Elev= 30
  4599.6  250.05  4621.1  249.68  4635.7  248.69  4707.2  243.63    4749  240.72
  4759.7  239.43  4778.5  238.22  4799.4  238.17  4828.9  236.52  4835.1  235.42
  4843.7  236.02  4849.8  233.02  4856.3  234.18  4864.6  233.17  4868.7  234.04
  4879.4  234.86  4885.5  237.89  4906.4  238.68  4950.7  239.05    4979  236.37
  4992.5  231.26  4996.7  227.83    5004  228.33    5013  232.18    5023  235.28
    5033  237.55  5073.1  237.62  5203.6  240.91  5393.7  246.26  5500.9  248.27
#Mann= 8 ,-1 , 0
  4599.6     .11       0  4635.7     .17       0  4707.2     .15       0
  4759.7     .17       0  4868.7     .15       0    4979     .09       0
    5023     .17       0  5203.6     .11       0
Bank Sta=4979,5023
XS Rating Curve= 0 ,0
Exp/Cntr=0.3,0.1

Type RM Length L Ch R = 1 ,9964    ,66,66,66
BEGIN DESCRIPTION:
LIVE BRANCH 20.5
END DESCRIPTION:
XS GIS Cut Line= 3
      3810507.94     10146293.97      3810594.35     10146648.49
      3810727.88     10147104.75
#Sta/Elev= 30
  4635.1  250.56  4640.3  250.05  4683.6  247.96  4742.4  243.38  4776.2   240.9
  4796.8  236.19  4823.6  235.08  4828.8  233.81  4865.3  233.49  4889.4  234.89
    4907  233.79  4912.2  236.26  4946.7  234.61  4948.7  234.33  4953.9  237.35
  4971.8  237.05  4982.1  235.24 4987.37  233.08  4990.4   231.8  4993.6  228.46
  5003.9  229.42  5013.1  233.05  5029.5  235.36  5054.8  234.91  5096.4  232.44
  5101.6  232.76  5106.9  234.85  5153.1  238.85  5273.6  241.39  5475.4  247.11
#Mann= 7 ,-1 , 0
  4635.1     .11       0  4640.3     .17       0  4742.4     .15       0
  4946.7     .17       0 4987.37     .09       0  5013.1     .17       0
  5153.1     .11       0
Bank Sta=4987.37,5013.1
XS Rating Curve= 0 ,0
Exp/Cntr=0.3,0.1

Type RM Length L Ch R = 1 ,9898    ,986,986,986
BEGIN DESCRIPTION:
LIVE BRANCH 13.0
END DESCRIPTION:
XS GIS Cut Line= 3
      3810438.97     10146314.79      3810538.89       10146684.
      3810652.12     10147127.07
#Sta/Elev= 30
  4617.5  250.32  4701.1  245.57  4750.4  242.27  4779.4  237.59    4785  235.56
  4790.2  235.99    4804  233.97  4819.7  233.29  4824.9  235.09  4867.1  235.09
  4893.4   234.1  4906.9  234.65  4934.1  234.22  4945.2  235.11    4974  235.01
  4979.2  234.67  4986.6  231.09  4993.9  226.95  5007.3  227.86  5014.2  231.39
  5019.4  233.66  5048.6  233.76  5112.2  236.53  5151.8  239.55  5177.6  238.77
  5213.2  240.13  5218.4  239.63  5294.9  241.42  5376.6  244.65  5457.3  246.76
#Mann= 8 ,-1 , 0
  4617.5     .17       0  4701.1     .15       0    4804     .17       0
  4867.1     .15       0  4906.9     .17       0  4986.6     .09       0
  5014.2     .17       0  5112.2     .11       0
#XS Ineff= 2 , 0
       0                  5151.8       0  239.55
Permanent Ineff=
       F       F
Bank Sta=4986.6,5014.2
XS Rating Curve= 0 ,0
Exp/Cntr=0.3,0.1

Type RM Length L Ch R = 1 ,8912    ,993,993,993
BEGIN DESCRIPTION:
LIVE BRANCH 12.0
END DESCRIPTION:
XS GIS Cut Line= 3
       3810358.3     10146319.97      3809788.93     10146965.17
      3809867.85     10147311.08
#Sta/Elev= 30
  4139.5  248.18  4182.8  246.54  4395.3  233.99  4417.1  234.86    4537  232.42
  4585.1  231.96  4693.1  232.31  4792.7  234.11  4884.7  232.41  4891.4  233.16
  4898.9  231.58  4905.6  232.78  4913.2  229.83  4919.8  232.91  4927.4  231.27
  4934.1  232.59  4948.3   229.4    4955  232.01  4962.5  230.41  4969.2  231.02
  4983.4  229.31    4995  223.84  5006.1  225.86 5010.16  229.38  5014.4  233.05
  5019.5  228.65  5026.6  235.21  5036.8  240.54  5095.9  241.52  5354.8  248.41
#Mann= 6 ,-1 , 0
  4139.5     .11       0    4537     .17       0  4585.1     .15       0
  4983.4     .09       0 5010.16     .15       0  5095.9     .17       0
#XS Ineff= 2 , 0
       0  4417.1  234.86               0
Permanent Ineff=
       F       F
Bank Sta=4983.4,5010.16
XS Rating Curve= 0 ,0
Exp/Cntr=0.3,0.1

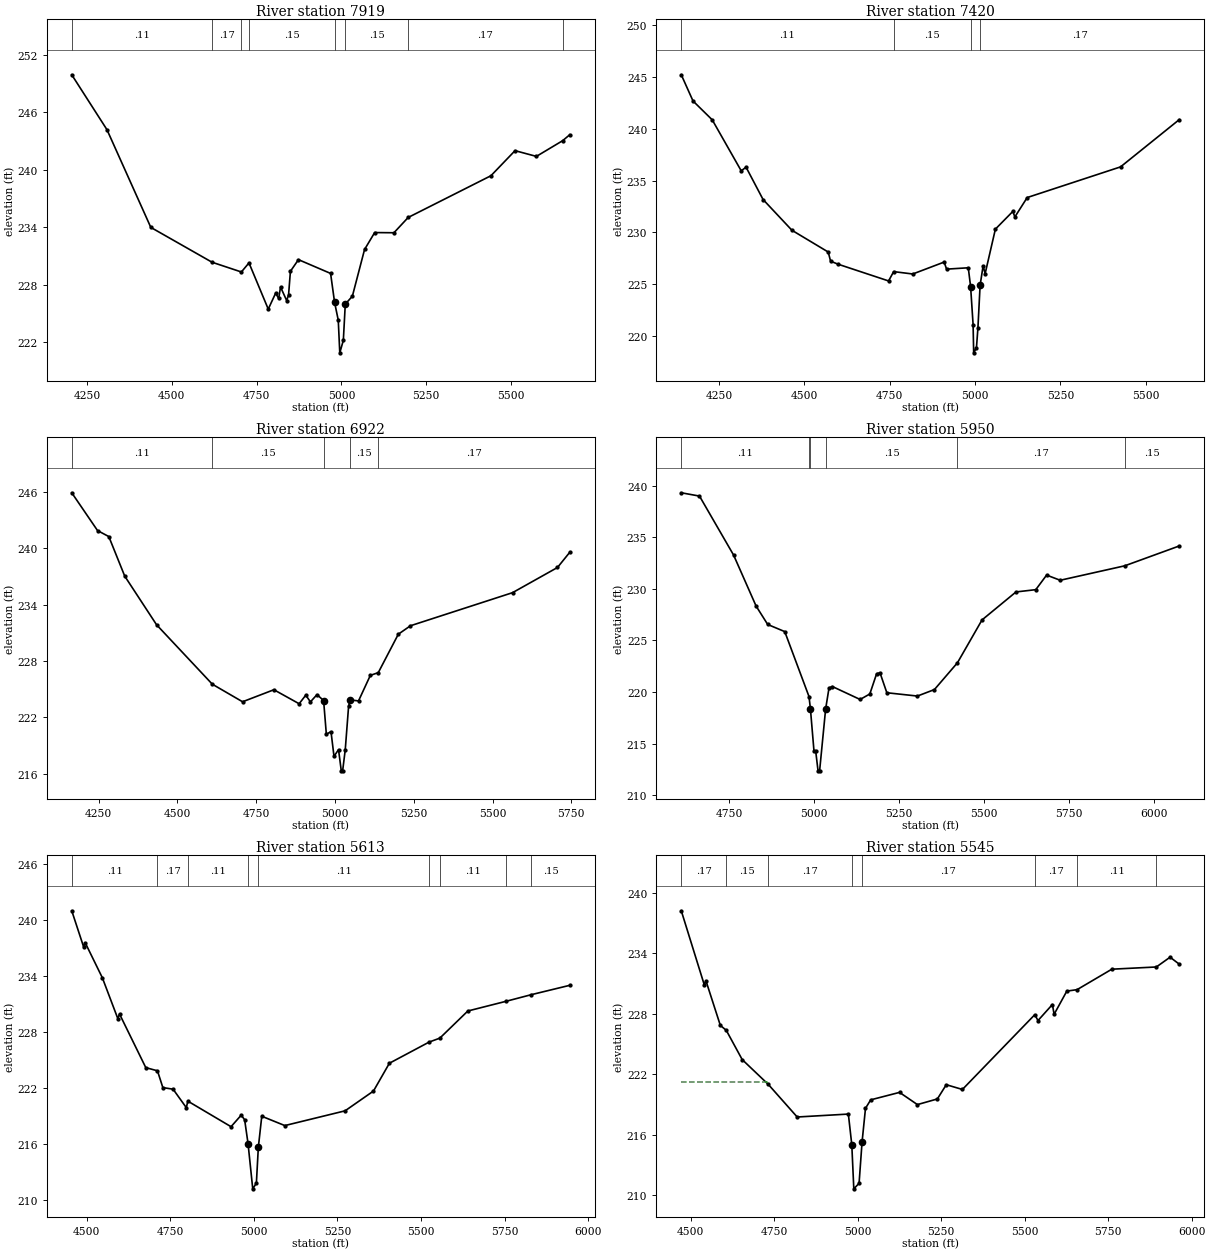
Type RM Length L Ch R = 1 ,7919    ,499,499,499
BEGIN DESCRIPTION:
LIVE BRANCH 11.0
END DESCRIPTION:
XS GIS Cut Line= 4
      3810301.04     10146176.72       3809569.3     10146486.75
      3809478.11     10146619.43       3809600.4      10147116.4
#Sta/Elev= 30
  4205.3  249.92  4309.1  244.18  4438.3  233.97  4618.7  230.33  4705.2  229.31
  4727.6  230.26  4784.4  225.43  4806.1  227.09  4815.2  226.55  4820.6  227.74
  4838.7  226.32  4844.3  226.93  4849.7  229.38  4873.4   230.6  4968.1  229.16
  4979.9  226.13  4990.7  224.28  4995.2  220.86  5005.7  222.17  5011.4  225.95
  5032.3  226.78  5068.2  231.66    5098  233.43  5154.8  233.41  5196.8  235.01
  5440.7  239.37  5511.7  241.99  5574.6  241.39  5651.9  243.03  5672.8  243.65
#Mann= 8 ,-1 , 0
  4205.3     .11       0  4618.7     .17       0  4705.2     .11       0
  4727.6     .15       0  4979.9     .09       0  5011.4     .15       0
  5196.8     .17       0  5651.9     .11       0
Bank Sta=4979.9,5011.4
XS Rating Curve= 0 ,0
Exp/Cntr=0.3,0.1

Type RM Length L Ch R = 1 ,7420    ,498,498,498
BEGIN DESCRIPTION:
LIVE BRANCH 10.0
END DESCRIPTION:
XS GIS Cut Line= 3
      3809933.84      10145598.6      3809307.36      10146188.8
      3808975.85     10146686.62
#Sta/Elev= 30
  4139.3  245.22  4173.7  242.69    4230  240.87  4314.9  235.95  4329.1   236.3
  4378.9  233.18  4463.5  230.21  4569.8  228.11  4576.7  227.23  4598.2  226.94
  4746.6  225.32  4761.5  226.22  4817.4  225.99  4909.3  227.14  4916.6  226.46
  4980.1  226.59  4986.9  224.78  4994.2  221.11  4995.9  218.38  5004.1  218.88
  5008.4  220.81  5014.7  224.89  5023.5  226.77  5029.5  226.03  5059.5  230.32
  5110.6  232.03  5116.6   231.5  5152.7  233.37  5426.2  236.33  5598.1  240.89
#Mann= 4 ,-1 , 0
  4139.3     .11       0  4761.5     .15       0  4986.9     .09       0
  5014.7     .17       0
Bank Sta=4986.9,5014.7
XS Rating Curve= 0 ,0
Exp/Cntr=0.3,0.1

Type RM Length L Ch R = 1 ,6922    ,972,972,972
BEGIN DESCRIPTION:
LIVE BRANCH 9.0
END DESCRIPTION:
XS GIS Cut Line= 3
      3809751.55     10145390.26      3809067.97     10145869.96
      3808836.26     10146577.91
#Sta/Elev= 30
  4164.9   245.9  4246.7  241.88  4282.5  241.24    4333  237.03  4434.1  231.85
  4610.9  225.53  4706.9  223.66  4806.3  224.94  4886.4  223.45  4907.4  224.36
  4922.2  223.65  4943.1  224.42    4964  223.79  4972.7  220.21  4987.5  220.48
    4997  217.85  5011.4  218.57  5020.1  216.31  5024.4  216.31  5032.7  218.55
  5043.3  223.18  5048.6  223.86  5074.8  223.75  5112.3  226.47  5137.5  226.76
  5201.1  230.85  5239.7  231.75  5563.5  235.27  5706.1  237.95  5744.9  239.56
#Mann= 5 ,-1 , 0
  4164.9     .11       0  4610.9     .15       0    4964     .09       0
  5048.6     .15       0  5137.5     .17       0
#XS Ineff= 2 , 0
       0                  5112.3       0  226.47
Permanent Ineff=
       F       F
Bank Sta=4964,5048.6
XS Rating Curve= 0 ,0
Exp/Cntr=0.3,0.1

Type RM Length L Ch R = 1 ,5950    ,337,337,337
BEGIN DESCRIPTION:
LIVE BRANCH 8.0
END DESCRIPTION:
XS GIS Cut Line= 3
      3808663.34      10144927.7      3808697.83     10145317.48
      3808738.86     10146391.19
#Sta/Elev= 30
  4608.7   239.3  4662.3  238.98  4762.7  233.27    4829  228.33  4863.1  226.55
  4913.3  225.86  4984.7  219.57 4988.86  218.38  4999.3  214.31  5004.3  214.31
  5011.3  212.38  5015.9  212.38  5033.6  218.36  5043.6  220.41  5053.6  220.54
  5135.1  219.29  5163.7  219.82  5183.7  221.78  5193.7  221.87  5213.8  219.94
  5303.8  219.62  5353.9  220.25  5421.6  222.84    5494  226.99    5594   229.7
  5652.2  229.92  5684.1  231.33  5724.1  230.83  5914.2  232.23  6074.5  234.15
#Mann= 6 ,-1 , 0
  4608.7     .11       0  4984.7     .15       0 4988.86     .09       0
  5033.6     .15       0  5421.6     .17       0  5914.2     .15       0
Bank Sta=4988.86,5033.6
XS Rating Curve= 0 ,0
Exp/Cntr=0.3,0.1

Type RM Length L Ch R = 1 ,5613    ,68,68,68
BEGIN DESCRIPTION:
Mapping XS 1cd113d4
END DESCRIPTION:
XS GIS Cut Line= 3
      3808305.57     10144883.87      3808411.25     10145417.91
      3808626.53     10146337.66
#Sta/Elev= 30
  4455.6  240.95  4490.8  237.11  4495.9  237.52  4547.1  233.77  4593.3   229.4
  4598.4  229.89    4677  224.14  4711.9   223.8    4728     222  4758.6  221.83
  4798.2  219.85  4802.7  220.55  4931.9  217.81  4962.4  219.05  4972.6  218.55
  4982.8  215.99  4996.8  211.15  5007.7  211.76  5013.5  215.59  5023.8  218.93
  5092.7  217.93  5272.9  219.51  5357.8  221.63  5405.4  224.61  5524.3  226.88
  5556.2   227.3    5640  230.21  5753.3  231.24  5829.9  231.96  5944.6  232.96
#Mann= 9 ,-1 , 0
  4455.6     .11       0  4711.9     .17       0  4802.7     .11       0
  4982.8     .06       0  5013.5     .11       0  5524.3     .17       0
  5556.2     .11       0  5753.3     .17       0  5829.9     .15       0
Bank Sta=4982.8,5013.5
XS Rating Curve= 0 ,0
Exp/Cntr=0.3,0.1

Type RM Length L Ch R = 1 ,5545    ,584,584,584
BEGIN DESCRIPTION:
LIVE BRANCH 7.0
END DESCRIPTION:
XS GIS Cut Line= 3
      3808226.55     10144893.12      3808344.29     10145408.54
      3808556.18     10146347.84
#Sta/Elev= 30
  4471.3  238.22  4540.2  230.88  4545.3  231.27  4588.3  226.86  4606.1  226.37
  4653.8  223.47    4732  221.01  4818.5  217.78  4971.8  218.07  4982.1  215.02
  4988.1  210.66  5003.9  211.21  5012.8  215.29  5023.1  218.64  5038.7  219.48
  5125.1  220.22  5178.6  219.01  5238.4  219.57  5265.1  220.98  5313.4  220.51
  5530.2  227.92  5539.8  227.34    5583  228.93  5588.1  227.96  5626.2  230.26
  5656.8   230.4    5761  232.43  5894.4  232.65  5935.5  233.62  5962.9  232.93
#Mann= 8 ,-1 , 0
  4471.3     .17       0  4606.1     .15       0    4732     .17       0
  4982.1     .06       0  5012.8     .17       0  5530.2     .17       0
  5656.8     .11       0  5894.4     .15       0
#XS Ineff= 2 , 0
       0  4727.4  221.26  5356.6       0  221.96
Permanent Ineff=
       F       F
Bank Sta=4982.1,5012.8
XS Rating Curve= 0 ,0
Exp/Cntr=0.3,0.1