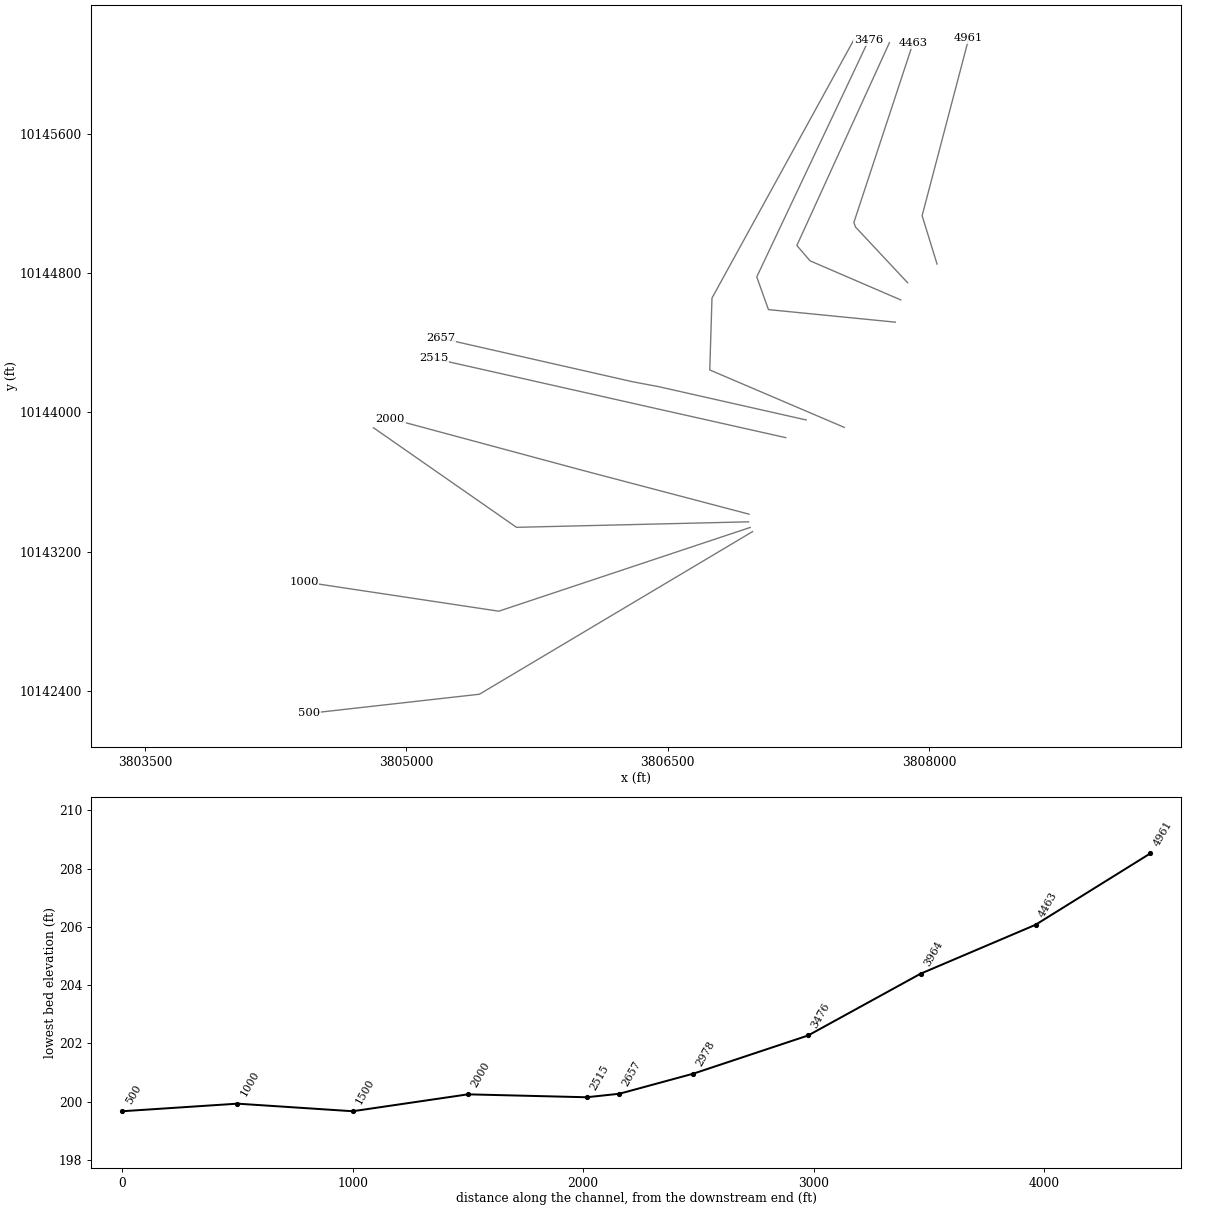
HEC-RAS study LIVE BRANCH.prj: LIVE BRANCH Base Level Engineering

--- LIVE BRANCH.g01 (geometry) --- (continued)

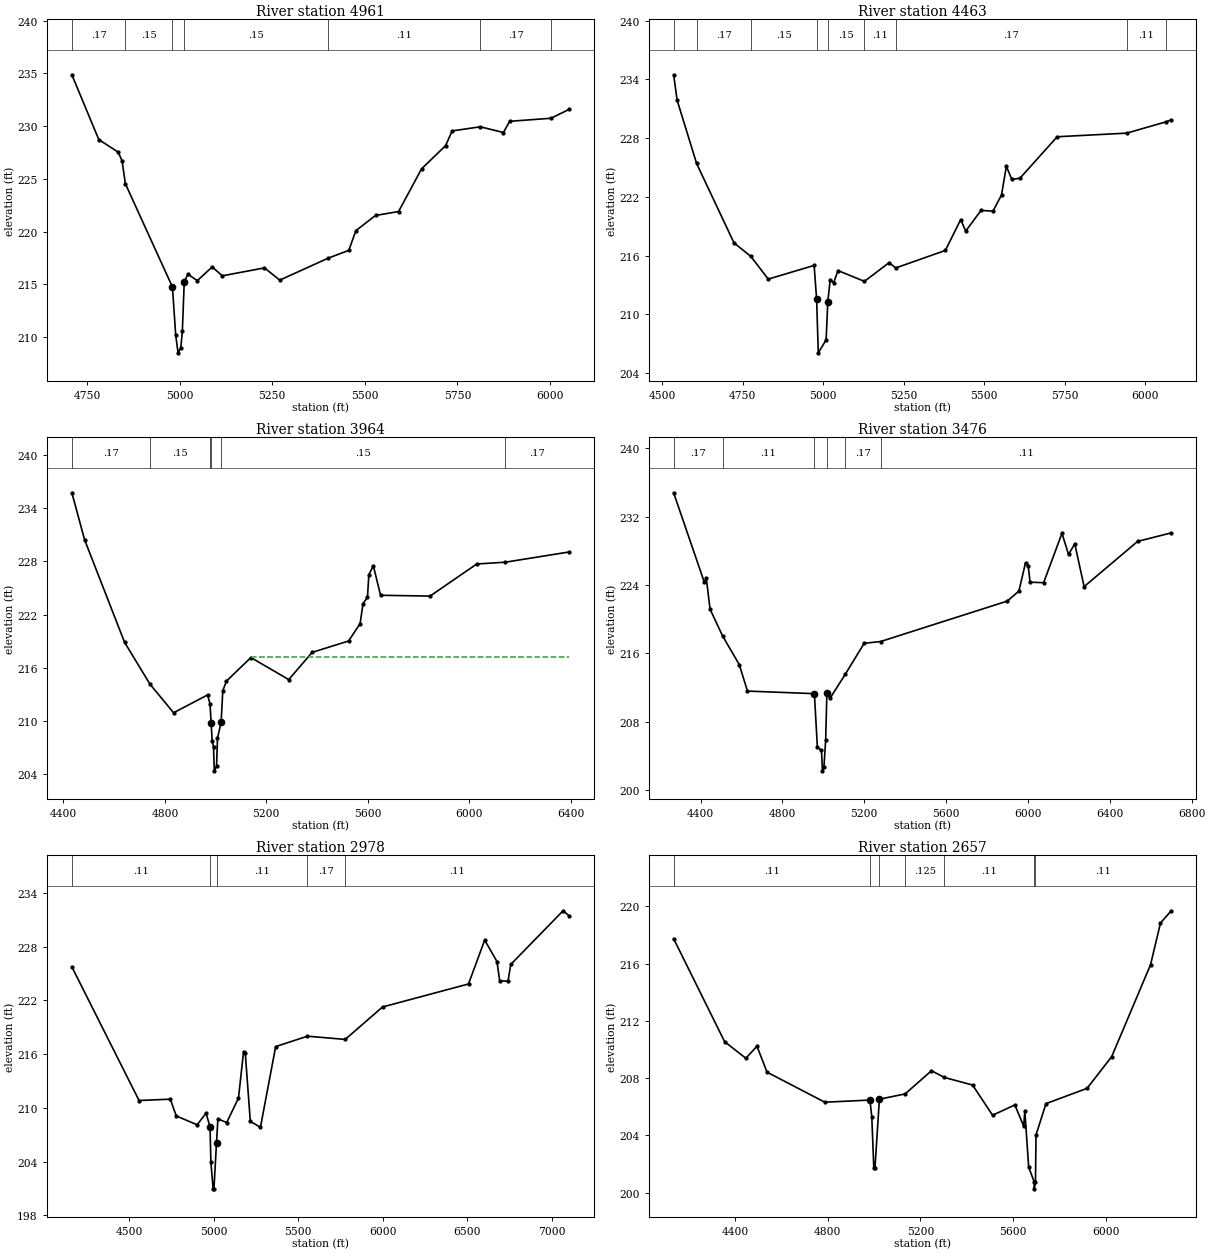
Type RM Length L Ch R = 1 ,4961    ,498,498,498
BEGIN DESCRIPTION:
LIVE BRANCH 6.0
END DESCRIPTION:
XS GIS Cut Line= 3
      3808046.49     10144851.65       3807960.8     10145129.43
      3808228.49     10146147.32
#Sta/Elev= 30
  4709.3  234.87    4782  228.73  4834.3  227.54  4844.7  226.73  4853.8  224.54
  4980.8  214.76  4989.5  210.24  4995.9  208.52  5003.4  209.02  5007.5  210.56
  5012.6  215.24  5022.4  215.98  5047.8  215.36  5088.1  216.66  5115.4  215.82
  5229.2  216.57  5270.5  215.41    5401  217.49  5456.7  218.23    5476   220.1
    5529  221.54  5591.1  221.91  5653.1  225.95  5718.1  228.16  5735.8  229.55
  5811.7  229.94  5874.2   229.4  5890.9  230.46  6002.6  230.75  6052.5  231.61
#Mann= 7 ,-1 , 0
  4709.3     .17       0  4853.8     .15       0  4980.8     .09       0
  5012.6     .15       0    5401     .11       0  5811.7     .17       0
  6002.6     .15       0
Bank Sta=4980.8,5012.6
XS Rating Curve= 0 ,0
Exp/Cntr=0.3,0.1

Type RM Length L Ch R = 1 ,4463    ,499,499,499
BEGIN DESCRIPTION:
LIVE BRANCH 5.0
END DESCRIPTION:
XS GIS Cut Line= 4
       3807877.2     10144744.86      3807578.74     10145063.86
      3807569.12     10145090.53      3807907.85     10146117.93
#Sta/Elev= 30
  4534.8  234.47  4545.7  231.87  4606.2  225.41  4722.5   217.3  4774.8  215.92
    4829   213.6  4971.6     215  4979.3  211.55  4984.5  206.07  5008.9  207.39
  5014.1  211.31  5021.6  213.55  5032.2  213.23  5045.9  214.47  5127.9  213.37
  5204.7  215.28  5225.3  214.74  5379.6  216.53  5427.1  219.67  5442.8  218.51
  5490.6  220.62  5527.6  220.54  5554.1  222.19  5569.2  225.13  5585.9  223.79
  5611.3   223.9  5727.1  228.14  5943.5  228.51  6063.9  229.65  6081.8  229.86
#Mann= 9 ,-1 , 0
  4534.8     .11       0  4606.2     .17       0  4774.8     .15       0
  4979.3     .09       0  5014.1     .15       0  5127.9     .11       0
  5225.3     .17       0  5943.5     .11       0  6063.9     .17       0
Bank Sta=4979.3,5014.1
XS Rating Curve= 0 ,0
Exp/Cntr=0.3,0.1

Type RM Length L Ch R = 1 ,3964    ,488,488,488
BEGIN DESCRIPTION:
LIVE BRANCH 4.0
END DESCRIPTION:
XS GIS Cut Line= 4
      3807838.13     10144645.89      3807317.63     10144870.24
      3807241.82     10144958.37      3807772.98     10146122.24
#Sta/Elev= 30
  4433.2  235.75  4483.4  230.45  4640.8   218.9  4740.9  214.18  4834.4  210.94
  4968.4  212.95    4978  211.93 4982.43   209.8  4986.4  207.81  4991.9  207.06
  4994.8  204.39  5003.7  204.89  5007.5  208.07  5021.8  209.86  5028.4  213.42
  5042.6   214.5  5139.3  217.17  5288.5  214.68  5380.6  217.75  5524.3  219.03
  5569.9  220.99  5581.4  223.26  5598.9  223.95  5604.4   226.5    5622  227.53
  5650.5  224.19  5845.8   224.1    6030  227.72  6142.4  227.92  6395.6  229.08
#Mann= 6 ,-1 , 0
  4433.2     .17       0  4740.9     .15       0    4978     .12       0
 4982.43     .09       0  5021.8     .15       0  6142.4     .17       0
#XS Ineff= 2 , 0
       0                  5144.8       0  217.21
Permanent Ineff=
       F       F
Bank Sta=4982.43,5021.8
XS Rating Curve= 0 ,0
Exp/Cntr=0.3,0.1

Type RM Length L Ch R = 1 ,3476    ,498,498,498
BEGIN DESCRIPTION:
LIVE BRANCH 3.0
END DESCRIPTION:
XS GIS Cut Line= 4
      3807806.97     10144518.26      3807078.82     10144590.32
      3807011.66     10144778.16      3807653.06       10146135.
#Sta/Elev= 30
  4268.3   234.8  4418.1  224.35  4428.2  224.78  4446.2  221.19  4507.4  218.06
    4589   214.7  4629.2   211.6  4956.3   211.3  4970.8  205.02  4990.9  204.69
  4995.6  202.27  5003.1  202.77  5011.4  205.91  5017.2  211.34  5032.7  210.76
  5107.8  213.59  5199.5  217.19    5280   217.4  5899.1  222.13  5955.7   223.3
    5988  226.61  6001.2  226.27  6010.2  224.34  6076.5  224.28  6166.1  230.06
  6198.2  227.59  6228.8  228.82  6274.4  223.82  6535.8  229.11  6700.3  230.11
#Mann= 6 ,-1 , 0
  4268.3     .17       0  4507.4     .11       0  4956.3     .06       0
  5017.2     .11       0  5107.8     .17       0    5280     .11       0
Bank Sta=4956.3,5017.2
XS Rating Curve= 0 ,0
Exp/Cntr=0.3,0.1

Type RM Length L Ch R = 1 ,2978    ,321,321,321
BEGIN DESCRIPTION:
LIVE BRANCH 2.0
END DESCRIPTION:
XS GIS Cut Line= 4
      3807513.66     10143914.46      3806741.97     10144243.97
      3806754.71     10144656.63      3807570.14     10146141.05
#Sta/Elev= 30
  4160.9  225.74  4558.7  210.82  4743.5  210.97  4778.9   209.1  4902.3  208.11
    4955   209.4  4978.6   207.9    4984  203.91  4997.1  200.96  5001.9  200.96
  5017.1  206.13  5025.4  208.78  5077.1  208.35  5147.2  211.09  5177.2  216.29
  5187.2  216.15  5217.2  208.49  5277.2  207.83  5367.3  216.84  5555.5     218
    5779  217.64  5999.8  221.26  6508.7  223.83  6604.5  228.73  6677.3  226.33
  6693.4  224.17  6742.7  224.15  6758.8  226.01  7068.6     232  7106.5  231.41
#Mann= 5 ,-1 , 0
  4160.9     .11       0  4978.6     .06       0  5017.1     .11       0
  5555.5     .17       0    5779     .11       0
Bank Sta=4978.6,5017.1
XS Rating Curve= 0 ,0
Exp/Cntr=0.3,0.1

Type RM Length L Ch R = 1 ,2657    ,142,142,142
BEGIN DESCRIPTION:
LIVE BRANCH 6.5
END DESCRIPTION:
XS GIS Cut Line= 4
      3807295.16     10143956.98      3806450.31     10144147.67
      3806301.27     10144175.78       3805197.1     10144426.29
#Sta/Elev= 30
  4133.9  217.74  4354.2  210.55  4445.8  209.39  4494.1  210.23  4537.3  208.42
  4787.2  206.32    4982  206.47    4990  205.31  4998.7  201.74  5003.8  201.74
  5022.9  206.53  5134.2   206.9    5248  208.52  5303.3  208.05  5425.5  207.52
  5511.8  205.41  5608.2  206.13  5646.2  204.65  5651.3  205.69  5667.9  201.78
  5691.5  200.77    5692  200.27  5697.3  200.77  5699.6  204.04  5742.7  206.22
  5920.2  207.29  6026.8  209.51  6194.3  215.92  6237.4  218.84  6283.9  219.69
#Mann= 7 ,-1 , 0
  4133.9     .11       0    4982     .07       0  5022.9     .11       0
  5134.2    .125       0  5303.3     .11       0  5691.5     .11       0
  5697.3     .11       0
Bank Sta=4982,5022.9
XS Rating Curve= 0 ,0
Exp/Cntr=0.3,0.1

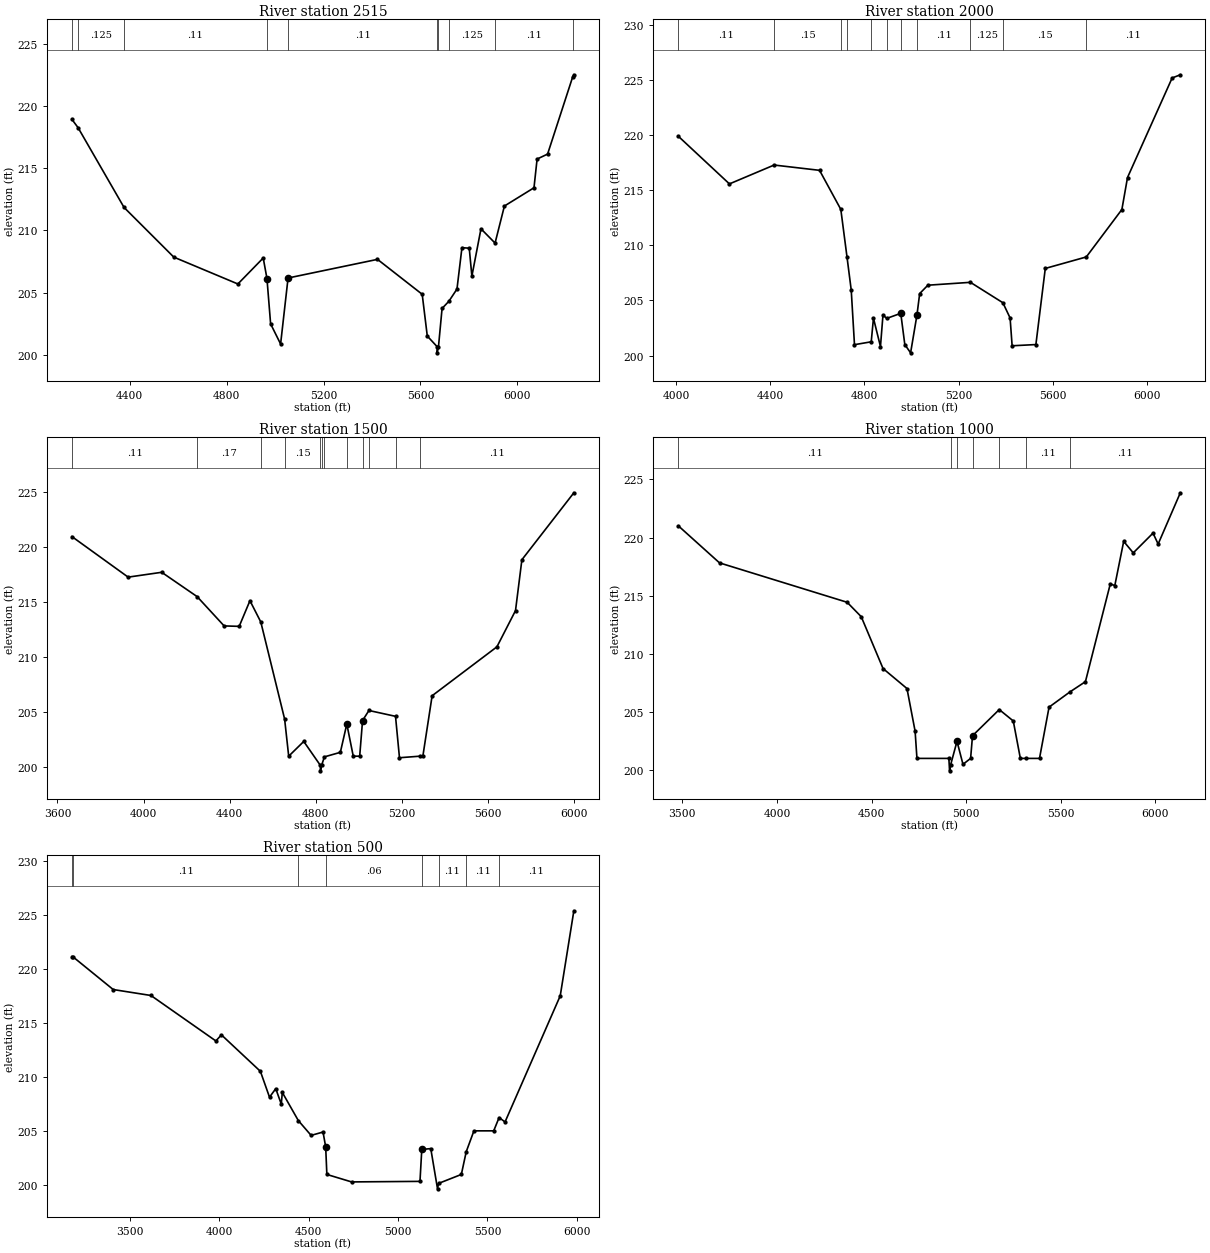
Type RM Length L Ch R = 1 ,2515    ,515,515,515
BEGIN DESCRIPTION:
LIVE BRANCH 1.0
END DESCRIPTION:
XS GIS Cut Line= 3
      3807177.98     10143855.42      3806360.14     10144039.05
      3805157.38     10144309.97
#Sta/Elev= 30
  4161.8  218.93  4186.9  218.27  4376.7  211.85  4582.1  207.85  4846.5  205.69
  4951.1  207.78 4966.49  206.13  4981.6  202.48  5022.8  200.86  5053.6  206.17
  5422.6  207.67  5607.1  204.86  5628.1   201.5  5668.5  200.65    5669  200.15
  5674.3  200.65  5689.1  203.72  5717.2   204.3  5750.6  205.28  5771.1  208.61
  5801.2  208.57  5812.1  206.32  5849.6  210.13  5907.8  208.98  5946.3  211.96
  6068.4  213.43  6081.2  215.74  6124.5  216.14  6227.4  222.31  6232.9  222.52
#Mann= 10 ,-1 , 0
  4161.8     .11       0  4186.9    .125       0  4376.7     .11       0
 4966.49     .06       0  5053.6     .11       0  5668.5     .11       0
  5674.3     .11       0  5717.2    .125       0  5907.8     .11       0
  6227.4    .125       0
Bank Sta=4966.49,5053.6
XS Rating Curve= 0 ,0
Exp/Cntr=0.3,0.1

Type RM Length L Ch R = 1 ,2000    ,500,500,500
BEGIN DESCRIPTION:
LIVE BRANCH 4.5
END DESCRIPTION:
XS GIS Cut Line= 3
      3806967.36     10143416.25      3806010.45      10143668.1
       3804908.3     10143964.87
#Sta/Elev= 30
  4010.5  219.87  4227.1  215.56  4416.8  217.27  4609.7  216.79    4700  213.25
    4726  208.98  4744.2  205.94    4758  200.99  4829.1  201.25  4838.6  203.39
  4868.3  200.82    4879  203.68  4894.9  203.37  4954.5  203.83  4971.7     201
  4996.3  200.25  5023.4   203.7  5034.8  205.62  5069.6  206.38  5250.2  206.64
  5388.1  204.79  5418.7  203.41  5427.3  200.89  5528.2     201  5568.1   207.9
  5742.2  208.94  5893.3  213.24  5917.2  216.14  6106.6  225.16  6141.4  225.45
#Mann= 11 ,-1 , 0
  4010.5     .11       0  4416.8     .15       0    4700     .17       0
    4726     .15       0  4829.1     .17       0  4894.9     .11       0
  4954.5     .06       0  5023.4     .11       0  5250.2    .125       0
  5388.1     .15       0  5742.2     .11       0
Bank Sta=4954.5,5023.4
XS Rating Curve= 0 ,0
Exp/Cntr=0.3,0.1

Type RM Length L Ch R = 1 ,1500    ,500,500,500
BEGIN DESCRIPTION:
LIVE BRANCH 3.5
END DESCRIPTION:
XS GIS Cut Line= 3
      3806964.96     10143372.24      3805632.63     10143340.65
      3804811.94     10143912.19
#Sta/Elev= 30
  3667.3  220.94  3928.5  217.26  4084.5   217.7  4249.2  215.49  4374.6  212.83
  4444.6  212.79  4494.6  215.12    4545  213.19  4655.8  204.37  4674.7     201
  4744.7  202.34  4821.8  200.17  4822.3  199.67  4827.6  200.17  4840.8  200.94
  4914.8  201.35  4944.8  203.92  4974.8     201  5004.7     201    5018  204.24
  5047.7  205.15  5171.2  204.62  5189.6  200.86    5284     201  5298.3     201
  5341.4  206.49  5642.5  210.93  5728.9  214.22  5758.6  218.84  6000.1  224.92
#Mann= 12 ,-1 , 0
  3667.3     .11       0  4249.2     .17       0    4545     .11       0
  4655.8     .15       0  4821.8     .11       0  4827.6     .15       0
  4840.8     .11       0  4944.8     .06       0    5018     .11       0
  5047.7     .11       0  5171.2     .15       0    5284     .11       0
Bank Sta=4944.8,5018
XS Rating Curve= 0 ,0
Exp/Cntr=0.3,0.1

Type RM Length L Ch R = 1 ,1000    ,500,500,500
BEGIN DESCRIPTION:
LIVE BRANCH 2.5
END DESCRIPTION:
XS GIS Cut Line= 3
      3806973.88     10143339.92       3805530.9     10142859.34
      3804411.92     10143027.83
#Sta/Elev= 30
  3479.1     221  3696.3  217.82  4370.8  214.43  4445.3  213.19  4560.5  208.73
    4687  207.01    4730  203.34  4739.7     201  4908.4     201  4912.1  199.93
  4917.5  200.43  4951.4  202.47    4983  200.49  5023.3     201  5033.4  202.95
  5174.7   205.2  5248.8  204.22  5286.2     201    5318     201  5387.4     201
  5437.9  205.41  5549.2  206.73  5630.1   207.6  5761.5  216.01  5785.4  215.87
  5832.3  219.67  5882.9  218.68  5987.3  220.38  6014.4  219.44  6131.6  223.85
#Mann= 7 ,-1 , 0
  3479.1     .11       0  4917.5     .11       0  4951.4     .06       0
  5033.4     .11       0  5174.7     .11       0    5318     .11       0
  5549.2     .11       0
Bank Sta=4951.4,5033.4
XS Rating Curve= 0 ,0
Exp/Cntr=0.3,0.1

Type RM Length L Ch R = 1 ,500     ,0,0,0
BEGIN DESCRIPTION:
LIVE BRANCH 1.5
END DESCRIPTION:
XS GIS Cut Line= 3
      3806987.82     10143316.29      3805419.91     10142382.71
      3804442.17     10142272.84
#Sta/Elev= 30
  3175.2  221.13  3181.2  221.11  3406.1  218.09  3617.4  217.54  3980.5  213.34
  4011.7   213.9  4229.8  210.53  4280.8  208.14  4315.7  208.93  4346.6   207.5
  4352.4  208.58    4442  205.98  4513.6  204.61  4580.3  204.92  4595.1  203.55
  4601.7     201  4739.9  200.31  5122.8  200.36  5132.9  203.31  5183.2  203.39
    5221  199.67  5226.5  200.17  5354.3     201  5381.6   203.1  5424.7  205.03
  5535.4  205.03  5565.6  206.26  5598.8  205.85  5907.7  217.51  5983.9  225.37
#Mann= 8 ,-1 , 0
  3175.2    .125       0  3181.2     .11       0    4442     .11       0
  4595.1     .06       0  5132.9     .11       0  5226.5     .11       0
  5381.6     .11       0  5565.6     .11       0
Bank Sta=4595.1,5132.9
XS Rating Curve= 0 ,0
Exp/Cntr=0.3,0.1
Stream Node=LIVE BRANCH     ,Reach-1         , 0 , 0 ,Upstream end
Stream Node=LIVE BRANCH     ,Reach-1         , 0 , 1 ,Downstream end

Chan Stop Cuts=-1
Use User Specified Reach Order=0
Composite Channel Slope=5