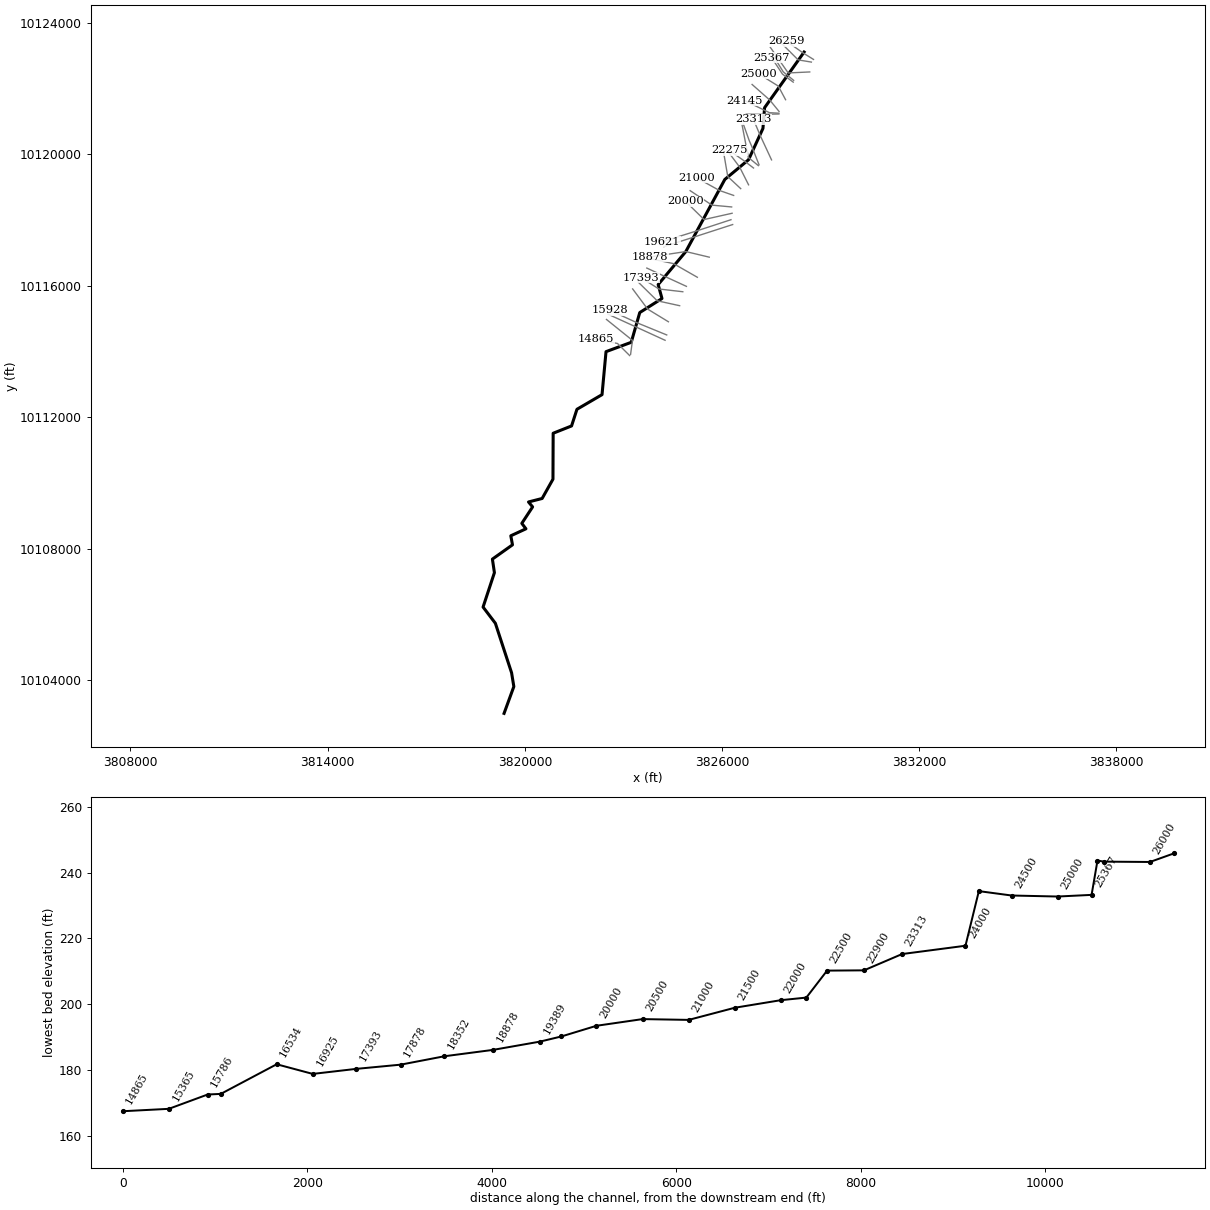
--- LIVE OAK BRANCH.prj (project) ---

Proj Title=LIVE OAK BRANCH Base Level Engineering
Current Plan=p01
Default Exp/Contr=0.3,0.1
English Units
Geom File=g01
Flow File=f01
Plan File=p01
Y Axis Title=Elevation
X Axis Title(PF)=Main Channel Distance
X Axis Title(XS)=Station
BEGIN DESCRIPTION:
LIVE OAK BRANCH
END DESCRIPTION:
DSS Export Rating Curves= 0
DSS Export Rating Curve Sorted= 0
DSS Export Volume Flow Curves= 0
DXF OffsetX= 0
DXF OffsetY= 0
DXF ScaleX= 1
DXF ScaleY= 10

--- LIVE OAK BRANCH.p01 (plan) ---

Plan Title=Multiple Run
Short Identifier=Multiple
Geom File=g01
Flow File=f01
Subcritical Flow
K Sum by GR= 0
Std Step Tol= 0.01
Critical Tol= 0.01
Num of Std Step Trials= 20
Max Error Tol= 0.3
Flow Tol Ratio= 0.001
Split Flow NTrial= 30
Split Flow Tol= 0.02
Split Flow Ratio= 0.02
Log Output Level= 0
Friction Slope Method= 1
Unsteady Friction Slope Method= 2
Unsteady Bridges Friction Slope Method= 1
Parabolic Critical Depth
Global Vel Dist=  1 , 1 , 1
Global Log Level= 0
CheckData=True
Encroach Param= -1, 0, 0, 0
BEGIN DESCRIPTION:
Multiple Run
END DESCRIPTION:

--- LIVE OAK BRANCH.f01 (steady flow) ---

Flow Title=Multiple
Program Version=4.10
Number of Profiles= 7
Profile Names=10-year,25-year,50-year,1pct_min,100-year,1pct_plu,500-year
River Rch & RM=LIVE OAK BRANCH,Reach-1         ,26259
     184     230     293     124     374    1129     631
River Rch & RM=LIVE OAK BRANCH,Reach-1         ,26000
     184     230     293     124     374    1129     631
River Rch & RM=LIVE OAK BRANCH,Reach-1         ,25000
     348     453     597     259     783    2365    1391
River Rch & RM=LIVE OAK BRANCH,Reach-1         ,22500
     813    1114    1517     679    2051    6194    3879
River Rch & RM=LIVE OAK BRANCH,Reach-1         ,19389
    1239    1730    2386    1081    3264    9857    6316
River Rch & RM=LIVE OAK BRANCH,Reach-1         ,8776
    1446    2023    2793    1265    3819   11533    7391
Boundary for River Rch & Prof#=LIVE OAK BRANCH,Reach-1         , 1
Up Type= 0
Dn Type= 3
Dn Slope=0.005
Boundary for River Rch & Prof#=LIVE OAK BRANCH,Reach-1         , 2
Up Type= 0
Dn Type= 3
Dn Slope=0.005
Boundary for River Rch & Prof#=LIVE OAK BRANCH,Reach-1         , 3
Up Type= 0
Dn Type= 3
Dn Slope=0.005
Boundary for River Rch & Prof#=LIVE OAK BRANCH,Reach-1         , 4
Up Type= 0
Dn Type= 3
Dn Slope=0.005
Boundary for River Rch & Prof#=LIVE OAK BRANCH,Reach-1         , 5
Up Type= 0
Dn Type= 3
Dn Slope=0.005
Boundary for River Rch & Prof#=LIVE OAK BRANCH,Reach-1         , 6
Up Type= 0
Dn Type= 3
Dn Slope=0.005
Boundary for River Rch & Prof#=LIVE OAK BRANCH,Reach-1         , 7
Up Type= 0
Dn Type= 3
Dn Slope=0.005
DSS Import GetInterval= 0
DSS Import GetPeak= 0
DSS Import FillOption= 0

--- LIVE OAK BRANCH.g01 (geometry) ---

Geom Title=Existing Conditions
Program Version=4.10

River Reach=LIVE OAK BRANCH ,Reach-1
Reach XY= 30
       3828496.2     10123116.59      3827294.23     10121423.46
      3827244.12     10120792.27      3826805.73      10119839.2
      3826084.03     10119240.47      3824897.59     10117046.62
      3824056.45     10116042.71      3824172.33     10115618.23
      3823496.55     10115191.15      3823237.09     10114285.62
      3822470.02     10114001.46      3822348.64     10112693.44
      3821585.23     10112247.85      3821421.83     10111741.49
      3820861.83     10111519.18      3820855.84     10110121.38
      3820526.34     10109534.72      3820111.47      10109428.4
      3820236.74     10109278.58      3819908.22     10108777.76
      3820033.35     10108612.02      3819573.07     10108399.65
      3819624.31     10108124.23      3819013.36     10107689.98
       3819074.6     10107277.69      3818729.65     10106230.92
      3819103.82     10105737.72      3819596.85     10104232.04
      3819665.52       10103812.      3819368.23     10102996.84

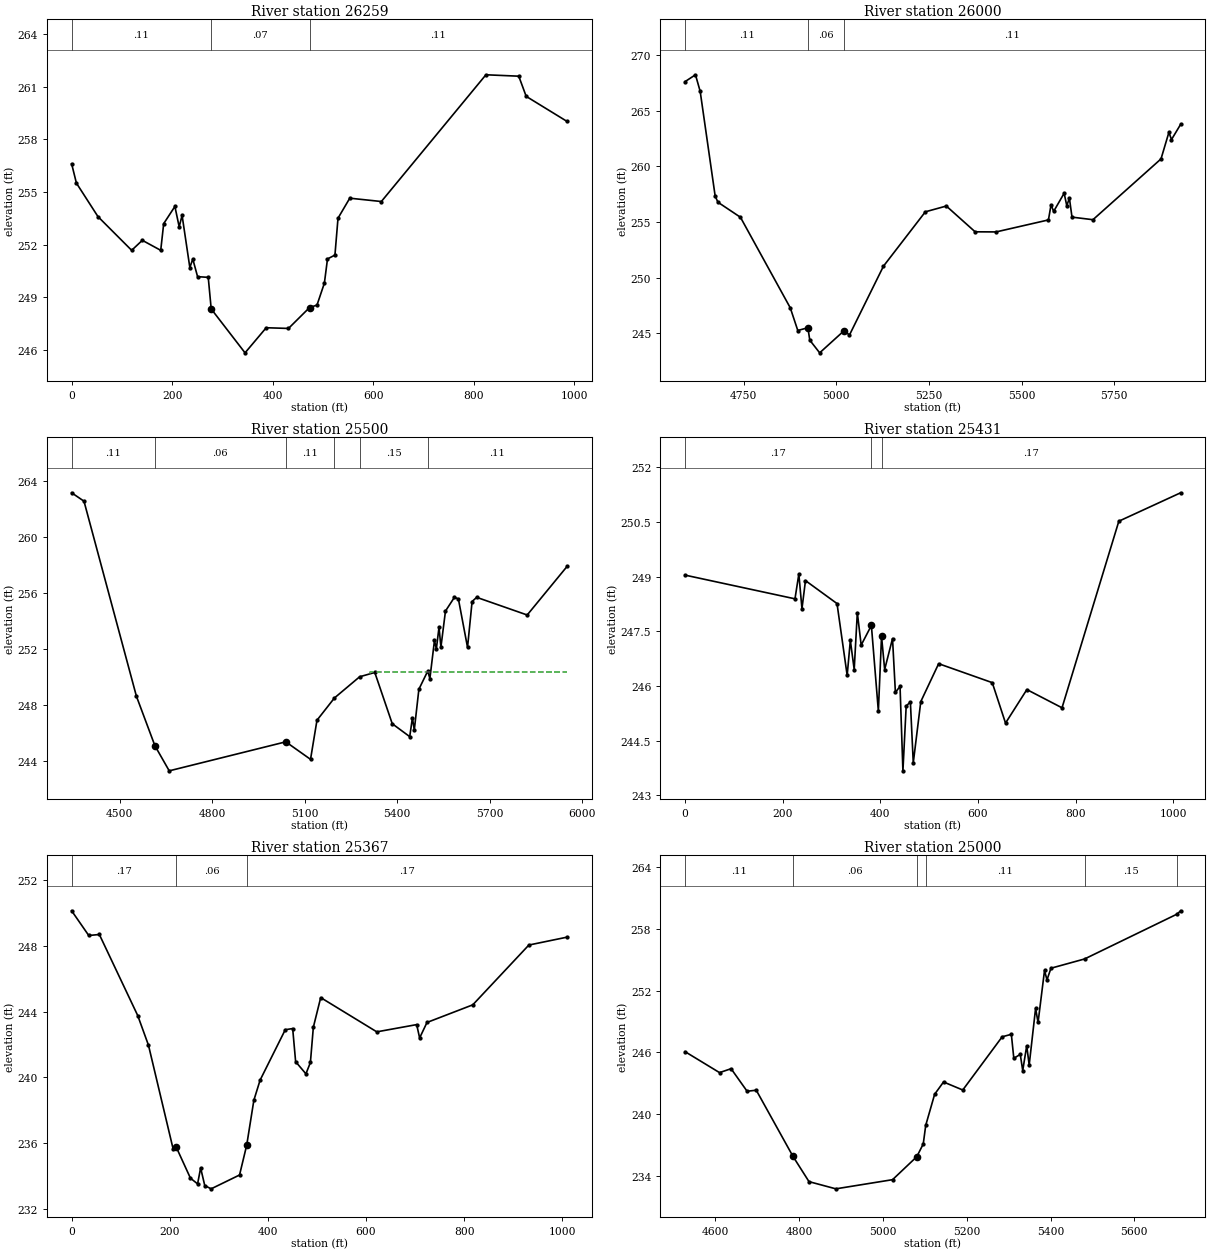
Type RM Length L Ch R = 1 ,26259   ,259,259,259
XS GIS Cut Line= 3
      3828782.39     10122891.93      3828471.94     10123084.69
      3827965.38     10123442.39
#Sta/Elev= 30
       0   256.6     9.5   255.5    52.4  253.59   119.4  251.67   140.6  252.24
   177.2  251.67   183.1  253.19   205.4  254.17   213.9  253.01   219.7  253.66
   235.1  250.69     241  251.17   250.5  250.17   271.7  250.13   277.6  248.33
   344.9  245.83     387  247.26   431.3  247.22   473.2  248.41     488  248.55
   502.7   249.8   508.9  251.18   523.7   251.4   529.8   253.5   553.2  254.64
     616  254.45     824  261.67   889.3  261.59   904.1  260.44   985.5  259.01
#Mann= 3 , 0 , 0
       0     .11       0   277.6     .07       0   473.2     .11       0
Bank Sta=277.6,473.2
XS Rating Curve= 0 ,0
Exp/Cntr=0.3,0.1

Type RM Length L Ch R = 1 ,26000   ,500,500,500
BEGIN DESCRIPTION:
LIVE OAK BRANCH 51.0
END DESCRIPTION:
XS GIS Cut Line= 3
      3828717.88     10122811.07      3828315.08     10122878.43
      3827655.54     10123533.68
#Sta/Elev= 30
  4591.6  267.64  4619.5  268.25  4632.2  266.76  4672.7  257.33  4680.2  256.78
  4740.9  255.43  4875.5  247.28  4895.8  245.24  4923.1  245.49  4928.2  244.37
  4954.9  243.23  5021.1  245.23  5035.3  244.83  5127.2  251.03  5240.3  255.92
  5296.9  256.44  5374.7  254.12  5431.3  254.11  5572.7  255.19  5579.7  256.55
  5586.8  255.96  5615.1  257.59  5622.2  256.47  5629.3  257.15  5636.3  255.44
  5692.9  255.21  5876.7  260.68    5898  263.07    5905  262.42  5929.7  263.79
#Mann= 3 , 0 , 0
  4591.6     .11       0  4923.1     .06       0  5021.1     .11       0
Bank Sta=4923.1,5021.1
XS Rating Curve= 0 ,0
Exp/Cntr=0.3,0.1

Type RM Length L Ch R = 1 ,25500   ,69,69,69
BEGIN DESCRIPTION:
LIVE OAK BRANCH 50.0
END DESCRIPTION:
XS GIS Cut Line= 3
      3828667.89     10122511.07      3828012.41     10122480.45
      3827467.85     10123261.08
#Sta/Elev= 30
  4343.8  263.17  4383.9  262.57  4554.1  248.65  4614.1  245.12  4660.5  243.33
  5038.8   245.4  5119.1  244.15    5140  246.94  5196.7  248.53  5278.4  250.04
  5327.6  250.35  5384.3  246.69    5441  245.77  5449.7  247.11  5455.8  246.24
  5470.7  249.15  5499.5  250.45  5506.4  249.91  5521.3  252.63  5527.4  252.03
  5536.1  253.58  5542.2  252.15    5557  254.73    5586  255.71  5598.9   255.6
  5628.6  252.14  5643.4  255.41  5658.2  255.71  5822.2  254.45  5951.8  257.92
#Mann= 6 ,-1 , 0
  4343.8     .11       0  4614.1     .06       0  5038.8     .11       0
  5196.7     .11       0  5278.4     .15       0  5499.5     .11       0
#XS Ineff= 2 , 0
       0                  5312.8       0  250.41
Permanent Ineff=
       F       F
Bank Sta=4614.1,5038.8
XS Rating Curve= 0 ,0
Exp/Cntr=0.3,0.1

Type RM Length L Ch R = 1 ,25431   ,64,64,64
XS GIS Cut Line= 3
      3828178.63     10122254.97      3827861.71     10122514.27
      3827541.59     10123029.66
#Sta/Elev= 30
       0  249.04     225  248.39   232.9  249.07   239.3  248.12   246.5  248.89
   311.1  248.26   331.9  246.29   338.4  247.25   346.3  246.45   352.7  248.01
   360.6  247.12   381.5  247.66   395.8  245.31   402.3  247.36   408.7  246.45
   424.8   247.3   430.7  245.82   440.2  245.99   446.1  243.67   452.8  245.45
   461.4  245.56   467.3  243.89   482.7  245.57   519.3  246.61   629.1  246.09
   656.3  244.98     700   245.9     772   245.4   888.4  250.52    1015   251.3
#Mann= 3 , 0 , 0
       0     .17       0   381.5     .06       0   402.3     .17       0
#XS Ineff= 2 , 0
       0   246.5  248.89               0
Permanent Ineff=
       T       F
Bank Sta=381.5,402.3
XS Rating Curve= 0 ,0
Exp/Cntr=0.3,0.1

Type RM Length L Ch R = 1 ,25367   ,367,367,367
XS GIS Cut Line= 3
      3828165.83     10122200.55       3827839.3     10122443.84
      3827506.38     10122946.43
#Sta/Elev= 30
       0  250.12    34.9  248.62    56.5  248.68   134.7  243.76   156.6  241.96
   206.7  235.68   212.9  235.79   242.1  233.89   256.7  233.54   262.9  234.51
   271.3  233.44   284.3  233.24   342.2  234.08   356.8  235.89   371.4  238.62
   384.1  239.84   435.4   242.9   450.5  242.97   456.5  240.96   477.5  240.22
   486.6  240.91   492.6  243.05   507.6  244.85   621.9  242.77   703.2  243.21
   709.2   242.4   724.2  243.34   817.5  244.41   931.8  248.04  1009.8  248.52
#Mann= 3 , 0 , 0
       0     .17       0   212.9     .06       0   356.8     .17       0
#XS Ineff= 2 , 0
       0                   450.5       0  242.97
Permanent Ineff=
       F       F
Bank Sta=212.9,356.8
XS Rating Curve= 0 ,0
Exp/Cntr=0.3,0.1

Type RM Length L Ch R = 1 ,25000   ,500,500,500
BEGIN DESCRIPTION:
LIVE OAK BRANCH 49.0
END DESCRIPTION:
XS GIS Cut Line= 3
      3827932.99     10121666.15      3827709.73     10122082.47
      3827105.59     10122456.59
#Sta/Elev= 30
  4527.6  246.06  4609.7  244.03  4637.3  244.41  4675.5  242.22  4697.4  242.32
  4785.1  235.89  4823.3  233.44  4887.4  232.74  5022.8  233.63  5080.6  235.86
  5096.1   237.1    5102  238.91  5123.3  241.93  5144.5  243.12  5190.4  242.34
  5284.5  247.51  5306.4  247.75  5312.3  245.42  5327.7   245.8  5333.6  244.23
  5343.1  246.64    5349  244.77  5364.3  250.27  5370.2   248.9  5385.6  253.95
  5391.5  253.04    5401  254.17  5481.3  255.07  5702.2  259.43  5710.6  259.75
#Mann= 6 ,-1 , 0
  4527.6     .11       0  4785.1     .06       0  5080.6     .11       0
    5102     .11       0  5481.3     .15       0  5702.2    .125       0
Bank Sta=4785.1,5080.6
XS Rating Curve= 0 ,0
Exp/Cntr=0.3,0.1

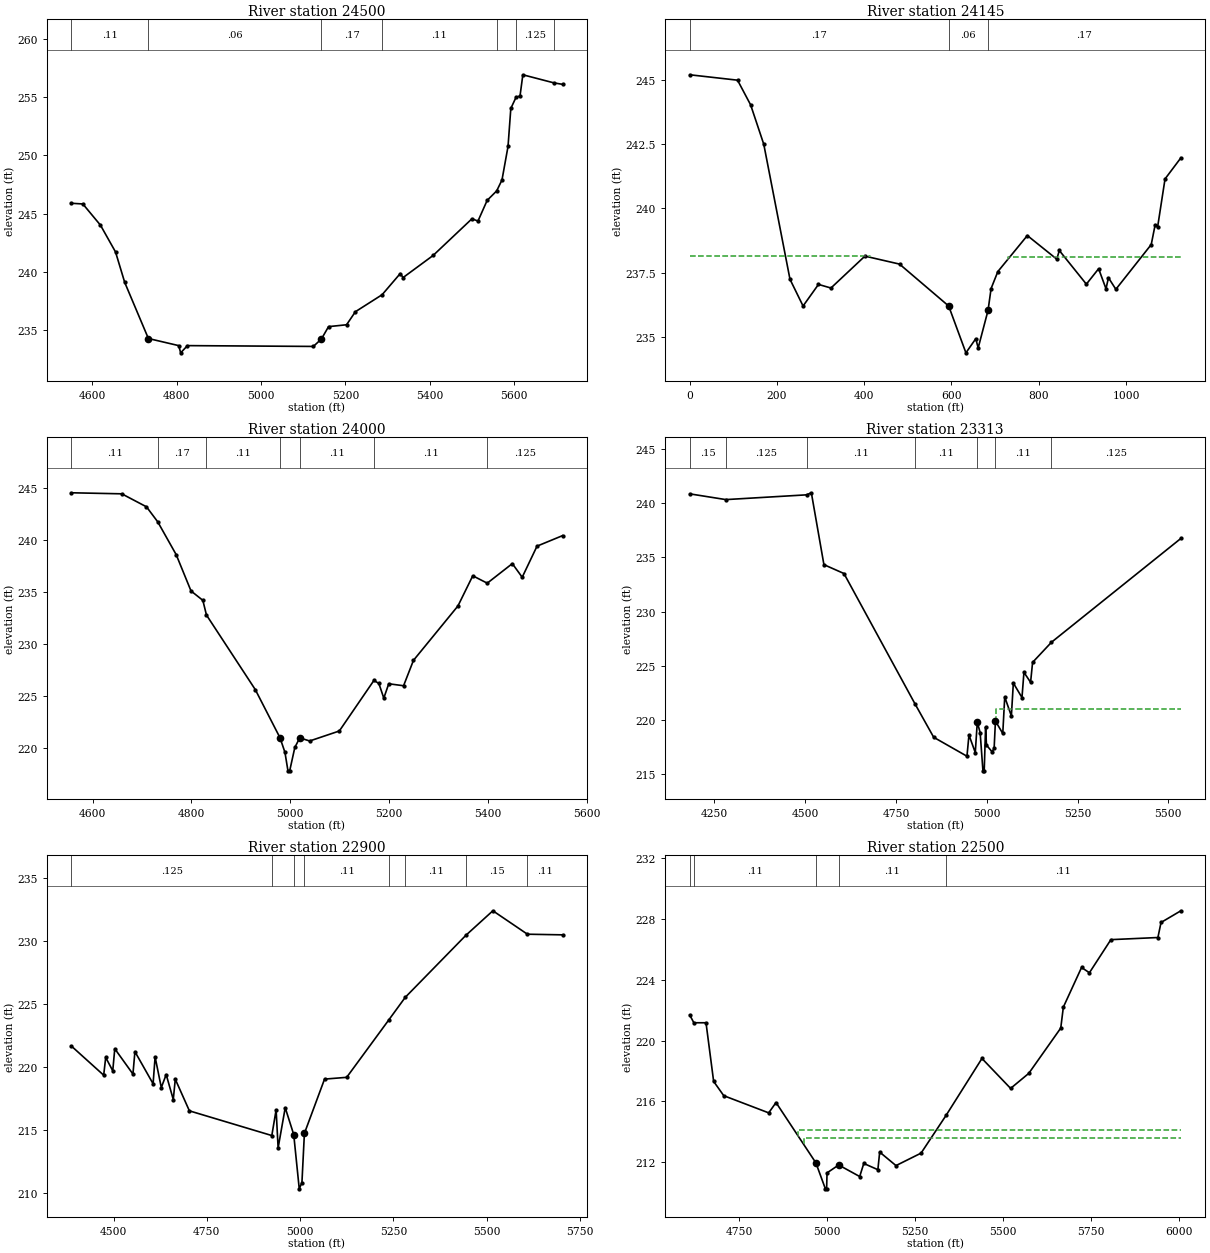
Type RM Length L Ch R = 1 ,24500   ,355,355,355
BEGIN DESCRIPTION:
LIVE OAK BRANCH 48.0
END DESCRIPTION:
XS GIS Cut Line= 3
       3827734.2      10121310.1      3827450.12     10121657.93
       3826914.3     10122129.99
#Sta/Elev= 30
  4550.9  245.89    4578  245.83  4619.7  244.01  4655.4  241.71  4677.2  239.09
  4733.2  234.28    4805  233.67  4809.7  233.05  4825.8  233.67  5123.9   233.6
 5143.08  234.24  5159.9   235.3  5202.6  235.46  5223.5  236.58  5286.8  238.04
  5329.8  239.86  5336.4  239.51  5407.6  241.41  5499.6  244.56  5513.8  244.36
  5535.6  246.14  5558.1  246.95  5570.7  247.89    5585  250.77  5591.6  254.03
  5603.9  254.98  5613.4   255.1  5620.1  256.92  5694.2  256.22  5714.1   256.1
#Mann= 7 ,-1 , 0
  4550.9     .11       0  4733.2     .06       0 5143.08     .17       0
  5286.8     .11       0  5558.1     .15       0  5603.9    .125       0
  5694.2     .15       0
Bank Sta=4733.2,5143.08
XS Rating Curve= 0 ,0
Exp/Cntr=0.3,0.1

Type RM Length L Ch R = 1 ,24145   ,145,145,145
XS GIS Cut Line= 3
      3827727.26      10121256.2      3827442.35      10121272.2
      3826686.87     10121640.34
#Sta/Elev= 30
       0  245.19   109.6  244.98   139.6  244.02   169.7  242.49   229.8  237.24
   259.8   236.2   295.1  237.04   323.7   236.9   401.6  238.14   480.9  237.83
   593.6   236.2   633.1  234.38   655.7  234.93   661.2  234.57   683.8  236.03
   690.8  236.88   706.3  237.54   773.9  238.94   841.5  238.02   847.1  238.36
   909.2  237.05   937.3  237.65   954.2  236.87   959.8   237.3   976.8  236.85
  1057.9  238.59  1066.9  239.36  1072.5  239.27  1089.5  241.14  1125.8  241.96
#Mann= 3 , 0 , 0
       0     .17       0   593.6     .06       0   683.8     .17       0
#XS Ineff= 2 , 0
       0   413.3  238.13   728.8       0  238.12
Permanent Ineff=
       F       F
Bank Sta=593.6,683.8
XS Rating Curve= 0 ,0
Exp/Cntr=0.3,0.1

Type RM Length L Ch R = 1 ,24000   ,687,687,687
BEGIN DESCRIPTION:
LIVE OAK BRANCH 47.0
END DESCRIPTION:
XS GIS Cut Line= 3
      3827729.75      10121231.8      3827287.16     10121222.22
      3826736.28     10121227.27
#Sta/Elev= 30
  4557.3  244.53  4659.2  244.43  4709.2  243.18  4731.9  241.74  4769.3  238.58
  4799.3  235.09  4823.2  234.19  4830.5  232.78  4929.3  225.61  4979.3  220.98
  4989.3  219.58  4995.4   217.8  4998.9   217.8  5009.3  220.05  5019.3  220.97
  5039.3  220.67  5099.3  221.63  5169.3  226.49  5179.3   226.2  5189.3  224.79
  5199.3  226.17  5229.3  225.98  5249.3  228.42  5339.3  233.65  5369.3  236.55
  5398.6  235.84  5449.3  237.72  5469.3  236.41  5499.3   239.4  5550.9  240.41
#Mann= 7 ,-1 , 0
  4557.3     .11       0  4731.9     .17       0  4830.5     .11       0
  4979.3     .06       0  5019.3     .11       0  5169.3     .11       0
  5398.6    .125       0
Bank Sta=4979.3,5019.3
XS Rating Curve= 0 ,0
Exp/Cntr=0.3,0.1

Type RM Length L Ch R = 1 ,23313   ,413,413,413
BEGIN DESCRIPTION:
LIVE OAK BRANCH 46.0
END DESCRIPTION:
XS GIS Cut Line= 3
      3827505.79       10119836.      3827160.79     10120577.68
      3826953.73     10121070.34
#Sta/Elev= 30
    4182  240.87  4281.5  240.34    4504  240.78  4516.9  240.97  4551.5  234.33
  4606.7  233.51  4802.6  221.45  4853.8  218.38  4945.4  216.63  4950.9  218.59
  4968.3  216.97  4973.8  219.77  4981.7  218.82  4989.4  215.28  4992.9  215.28
  4996.7  219.33  4999.1  217.66  5014.5  217.04  5020.2  217.35 5023.82  219.88
    5044  218.73  5049.4  222.11  5067.7  220.35  5073.1  223.39  5096.9  222.05
  5102.3  224.38  5120.6  223.46  5126.1   225.3  5178.1  227.16  5534.4  236.75
#Mann= 7 ,-1 , 0
    4182     .15       0  4281.5    .125       0    4504     .11       0
  4802.6     .11       0  4973.8     .07       0 5023.82     .11       0
  5178.1    .125       0
#XS Ineff= 2 , 0
       0                  5025.6       0  220.98
Permanent Ineff=
       F       T
Bank Sta=4973.8,5023.82
XS Rating Curve= 0 ,0
Exp/Cntr=0.3,0.1

Type RM Length L Ch R = 1 ,22900   ,400,400,400
BEGIN DESCRIPTION:
LIVE OAK BRANCH 45.0
END DESCRIPTION:
XS GIS Cut Line= 4
      3827125.24     10119687.08      3826899.67     10120256.85
      3826829.21     10120416.38      3826650.79     10120914.38
#Sta/Elev= 30
  4387.2  221.66  4473.7  219.35  4479.1  220.76    4498   219.7  4503.4  221.45
  4552.1  219.44  4557.4  221.22  4606.1  218.67  4611.5   220.8  4628.1  218.37
  4641.2   219.4  4660.2  217.42  4665.6  219.03  4703.4  216.52  4924.3  214.56
  4935.8   216.6  4941.2  213.58  4960.2  216.77    4983  214.64  4997.8  210.33
    5005  210.83  5011.6  214.73  5065.6  219.04  5124.9  219.18  5238.6  223.77
  5281.9  225.53  5444.6  230.46  5516.7   232.4  5609.3  230.54  5703.4  230.49
#Mann= 8 ,-1 , 0
  4387.2    .125       0  4924.3     .15       0    4983     .06       0
  5011.6     .11       0  5238.6     .15       0  5281.9     .11       0
  5444.6     .15       0  5609.3     .11       0
Bank Sta=4983,5011.6
XS Rating Curve= 0 ,0
Exp/Cntr=0.3,0.1

Type RM Length L Ch R = 1 ,22500   ,225,225,225
BEGIN DESCRIPTION:
LIVE OAK BRANCH 44.0
END DESCRIPTION:
XS GIS Cut Line= 3
      3827103.71     10119661.54      3826801.25     10119908.53
      3826609.68     10120896.43
#Sta/Elev= 30
  4609.5  221.69  4621.2  221.18  4655.8  221.18  4677.5  217.32  4706.3  216.38
  4834.1  215.25  4854.9  215.93  4968.3  211.96  4995.3  210.25  4998.8  210.25
    5000   211.3  5033.1  211.82  5092.9  211.06  5104.5  211.92  5144.6  211.51
  5149.7  212.67  5196.1  211.78  5267.4   212.6  5338.7  215.09  5440.6  218.83
  5522.1  216.86  5573.8  217.85  5664.7  220.83  5672.1  222.21  5723.9  224.82
  5746.2  224.47  5807.3  226.65    5941  226.79  5949.9  227.78  6006.3  228.55
#Mann= 5 ,-1 , 0
  4609.5    .125       0  4621.2     .11       0  4968.3     .06       0
  5033.1     .11       0  5338.7     .11       0
#XS Ineff= 2 ,-1
  4918.8  4904.4  214.15  4933.1  4918.8  213.58
Permanent Ineff=
       F       F
Bank Sta=4968.3,5033.1
XS Rating Curve= 0 ,0
Exp/Cntr=0.3,0.1

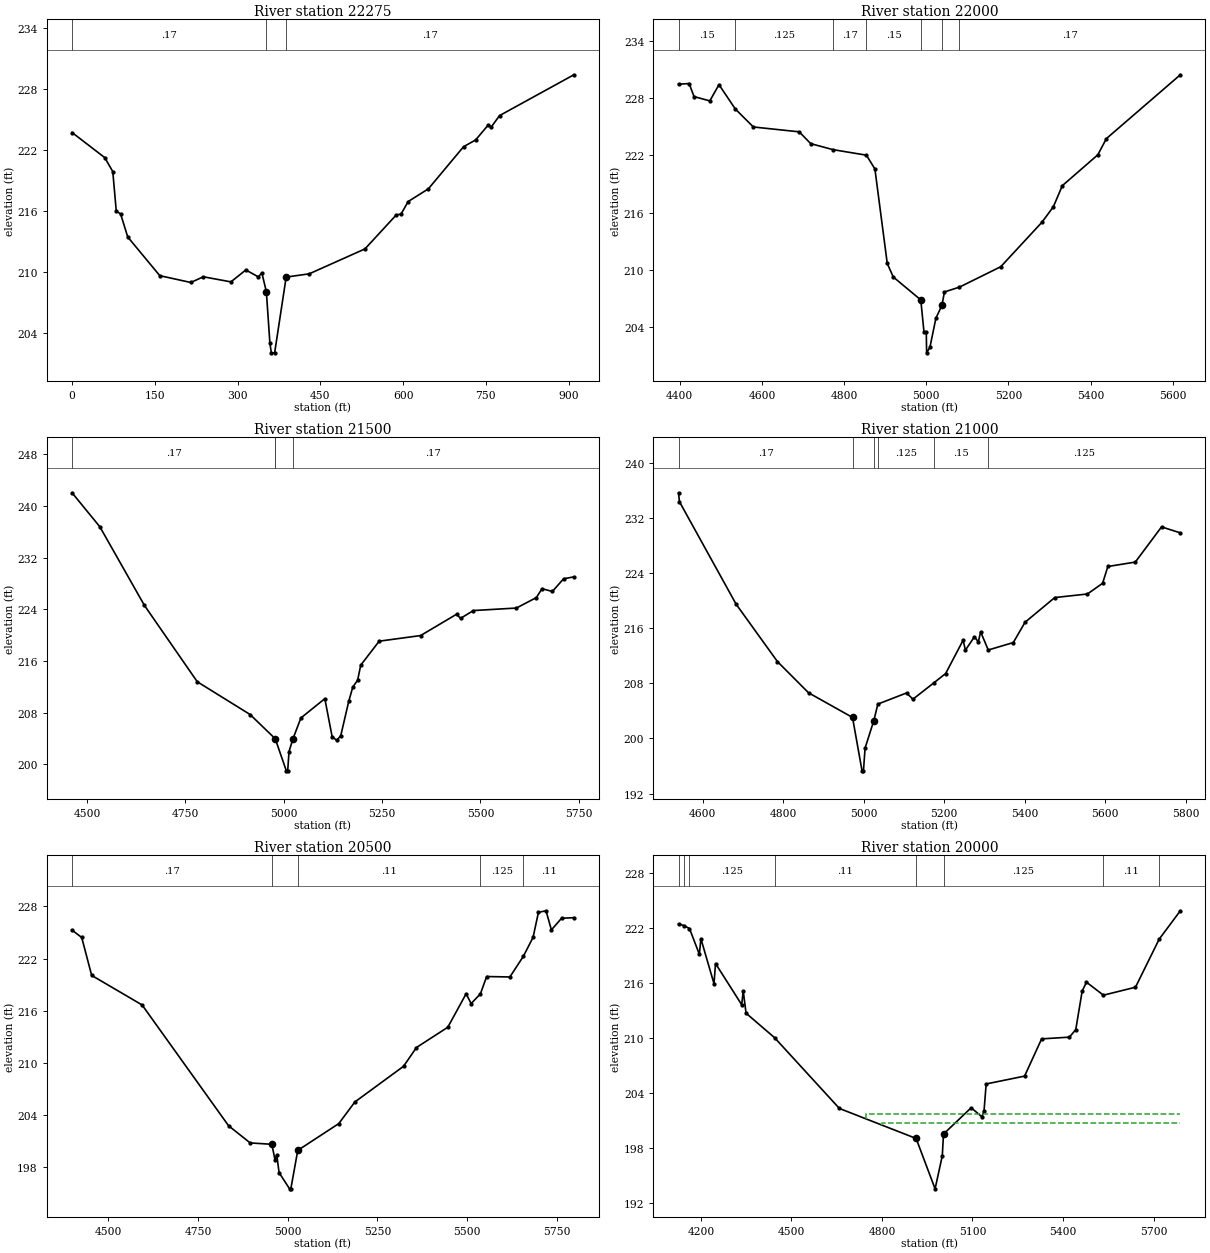
Type RM Length L Ch R = 1 ,22275   ,275,275,275
BEGIN DESCRIPTION:
LIVE OAK BRANCH 43.5
END DESCRIPTION:
XS GIS Cut Line= 3
      3826957.83      10119588.5      3826668.74     10119809.05
      3826221.61      10120123.7
#Sta/Elev= 30
       0   223.7    59.3  221.23    73.8  219.86    80.1  215.99      88   215.7
   100.9  213.44     159  209.64   215.2  208.97     238  209.53   287.9  209.03
     315   210.2   337.7  209.52     344  209.92   352.2  208.06   358.6  203.01
   361.2  202.06   367.2  202.06   388.1   209.5   429.9  209.82     531  212.27
   587.6   215.6   596.3  215.69   609.3  216.92   645.9  218.17   709.6   222.3
   731.5  222.97     754  224.41   760.1  224.26   774.9  225.36   909.6  229.37
#Mann= 3 , 0 , 0
       0     .17       0   352.2     .09       0   388.1     .17       0
Bank Sta=352.2,388.1
XS Rating Curve= 0 ,0
Exp/Cntr=0.3,0.1

Type RM Length L Ch R = 1 ,22000   ,500,500,500
BEGIN DESCRIPTION:
LIVE OAK BRANCH 43.0
END DESCRIPTION:
XS GIS Cut Line= 3
       3826806.7     10119077.42      3826535.77      10119615.9
       3826165.9     10120111.13
#Sta/Elev= 30
  4397.2  229.48    4423  229.55  4434.9  228.18  4473.3  227.73  4495.6  229.43
  4535.5  226.87  4579.3  224.99  4690.9  224.48  4718.8  223.24  4773.1  222.61
  4854.3  222.03    4875  220.58    4905  210.67  4919.7  209.24  4986.6  206.84
  4994.5  203.43    5000  203.43  5000.8  201.28  5008.8  201.85  5023.4  204.92
    5038  206.26  5044.2  207.67  5080.7  208.18  5181.2  210.32    5281  214.97
    5309   216.6    5331  218.83  5417.4  222.07  5438.2  223.77  5618.1  230.47
#Mann= 7 ,-1 , 0
  4397.2     .15       0  4535.5    .125       0  4773.1     .17       0
  4854.3     .15       0  4986.6     .09       0    5038     .15       0
  5080.7     .17       0
Bank Sta=4986.6,5038
XS Rating Curve= 0 ,0
Exp/Cntr=0.3,0.1

Type RM Length L Ch R = 1 ,21500   ,500,500,500
BEGIN DESCRIPTION:
LIVE OAK BRANCH 42.0
END DESCRIPTION:
XS GIS Cut Line= 3
      3826567.84     10118961.09      3826174.31     10119328.09
      3826048.97     10120054.96
#Sta/Elev= 30
  4461.9  242.02  4532.5  236.76  4645.8  224.59  4780.2  212.77  4914.5   207.7
  4978.5  203.94  5006.6  198.98  5010.1  198.98  5013.4  201.96  5023.3  203.91
  5043.6  207.16  5104.5  210.15    5123  204.28  5134.9  203.69  5145.1  204.45
  5165.4  209.77  5175.5  211.93  5187.9  213.02  5195.8  215.34  5242.7  219.05
    5348  219.92  5439.4  223.22  5449.5  222.58  5482.2  223.79  5591.6  224.18
  5642.3   225.8  5656.7  227.18  5682.9  226.74  5711.5  228.71  5737.6     229
#Mann= 4 ,-1 , 0
  4461.9     .17       0  4978.5     .11       0  4978.5     .06       0
  5023.3     .17       0
#XS Ineff= 2 , 0
       0                  5104.5       0  210.15
Permanent Ineff=
       F       T
Bank Sta=4978.5,5023.3
XS Rating Curve= 0 ,0
Exp/Cntr=0.3,0.1

Type RM Length L Ch R = 1 ,21000   ,500,500,500
BEGIN DESCRIPTION:
LIVE OAK BRANCH 41.0
END DESCRIPTION:
XS GIS Cut Line= 3
        3826353.     10118754.65      3825918.23     10118905.83
      3825230.42     10119287.88
#Sta/Elev= 30
  4539.7  235.65  4541.9  234.36  4682.8  219.48  4785.5  211.15  4862.8  206.62
  4972.1  203.04  4995.8  195.29  4999.3  195.29  5003.3  198.59  5025.1  202.59
  5035.1  204.98  5106.3  206.59  5122.3  205.69  5174.2  208.06  5203.5  209.41
    5247  214.25  5252.7  212.81    5275  214.74  5284.8  214.01  5290.5  215.47
  5309.4  212.83  5371.7  213.91  5400.8  216.85  5474.7  220.44  5555.9  220.96
  5593.6  222.51  5606.7  224.95  5674.9  225.59  5740.1   230.7  5786.8  229.83
#Mann= 6 ,-1 , 0
  4539.7     .17       0  4972.1     .07       0  5025.1    .125       0
  5035.1    .125       0  5174.2     .15       0  5309.4    .125       0
Bank Sta=4972.1,5025.1
XS Rating Curve= 0 ,0
Exp/Cntr=0.3,0.1

Type RM Length L Ch R = 1 ,20500   ,500,500,500
BEGIN DESCRIPTION:
LIVE OAK BRANCH 40.0
END DESCRIPTION:
XS GIS Cut Line= 3
      3826292.21     10118403.84      3825694.04     10118458.96
      3825029.25     10118899.67
#Sta/Elev= 30
  4399.3  225.27  4426.2  224.43  4453.9  220.07  4594.5  216.67  4835.5  202.78
  4895.7  200.81    4956  200.65  4964.8  198.87  4969.8  199.42  4976.1   197.4
  5005.4  195.53  5008.9  195.53  5028.2  199.95  5142.5  203.03  5187.4  205.52
    5323  209.62    5359  211.78  5446.3  214.11  5497.4  217.96  5511.3  216.83
  5537.1  217.94  5554.6  219.94  5619.3  219.89  5656.8  222.26  5683.9  224.44
  5698.9  227.32    5720   227.5    5735   225.3  5763.3  226.64  5797.6  226.71
#Mann= 5 ,-1 , 0
  4399.3     .17       0    4956     .06       0  5028.2     .11       0
  5537.1    .125       0  5656.8     .11       0
Bank Sta=4956,5028.2
XS Rating Curve= 0 ,0
Exp/Cntr=0.3,0.1

Type RM Length L Ch R = 1 ,20000   ,379,379,379
BEGIN DESCRIPTION:
LIVE OAK BRANCH 39.0
END DESCRIPTION:
XS GIS Cut Line= 3
      3826306.19     10118212.06      3825453.17     10118020.81
      3824888.97     10118572.21
#Sta/Elev= 30
  4125.8  222.47  4143.3   222.3  4162.1  221.97  4194.8  219.15  4199.9  220.86
  4243.3  215.94  4248.4  218.14  4335.1  213.64  4340.2  215.14  4349.6  212.71
  4444.1  210.03    4659  202.29  4913.2  199.01  4976.1   193.5    5000  197.12
    5004  199.49  5095.8  202.37  5131.3  201.37  5138.3  202.02  5145.4  204.97
  5272.7  205.83  5329.2   209.9  5421.2  210.09  5442.3  210.91  5463.6  215.13
  5477.8   216.1  5534.1  214.68  5640.3  215.55  5718.7   220.8  5788.9  223.91
#Mann= 8 ,-1 , 0
  4125.8    .125       0  4143.3     .11       0  4162.1    .125       0
  4444.1     .11       0  4913.2     .09       0    5004    .125       0
  5534.1     .11       0  5718.7     .17       0
#XS Ineff= 3 ,-1
  4745.8  4697.3  201.71  4800.5  4759.5  200.72  5095.8  5145.4  202.37
Permanent Ineff=
       F       F       F
Bank Sta=4913.2,5004
XS Rating Curve= 0 ,0
Exp/Cntr=0.3,0.1

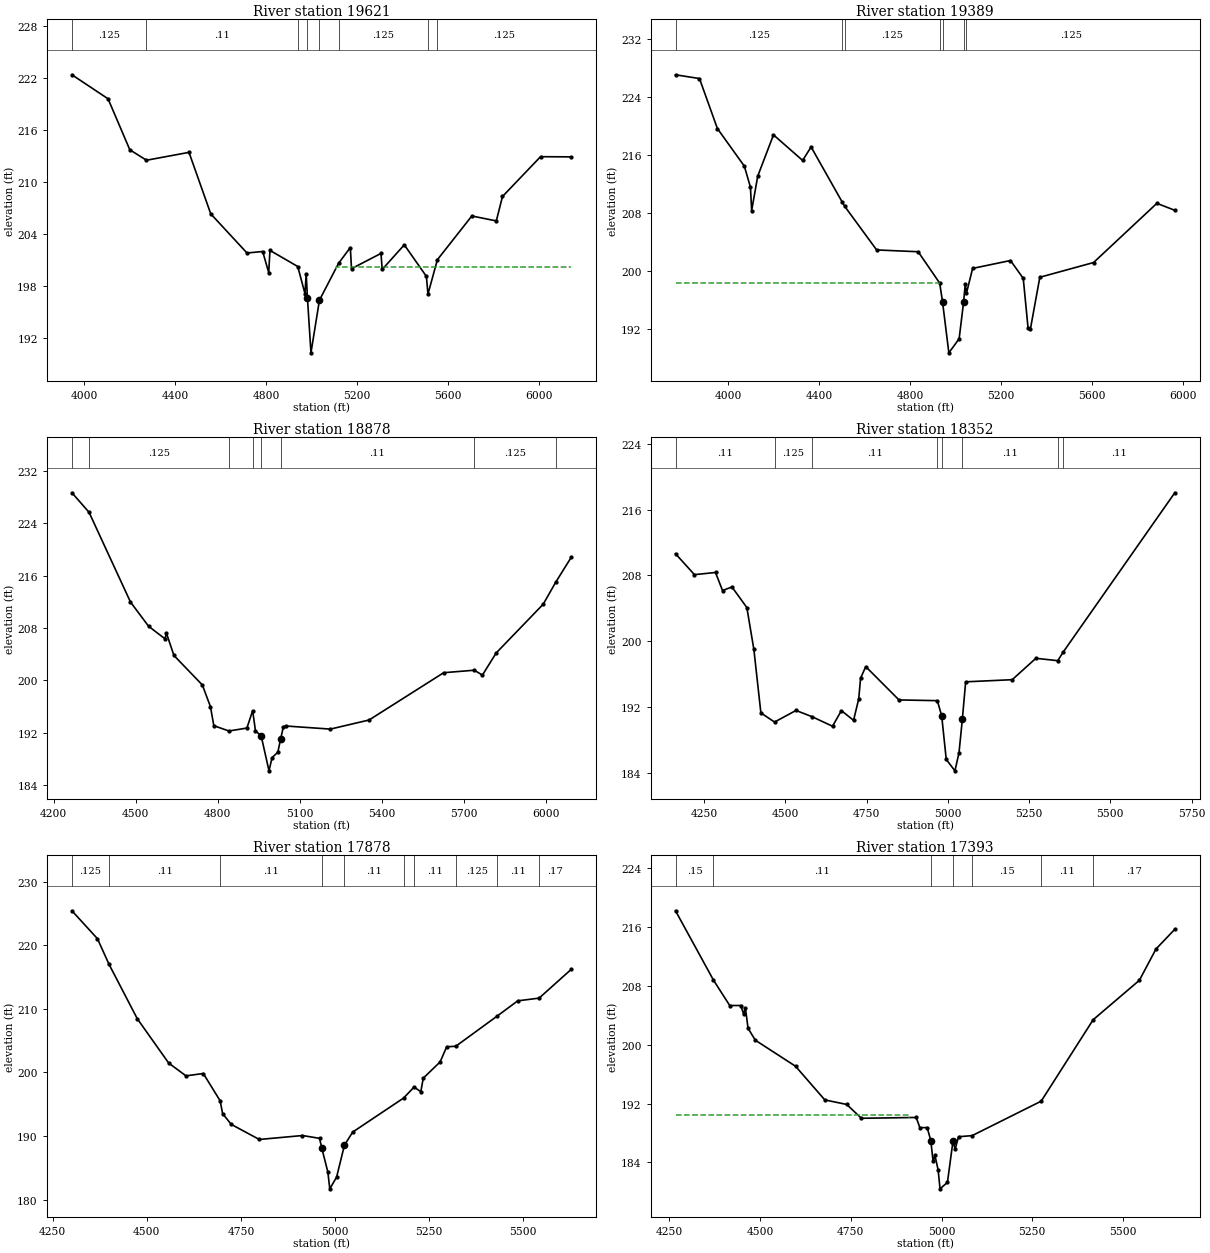
Type RM Length L Ch R = 1 ,19621   ,232,232,232
BEGIN DESCRIPTION:
LIVE OAK BRANCH 38.0
END DESCRIPTION:
XS GIS Cut Line= 3
      3826271.75     10118016.04      3825270.47     10117688.47
       3824182.2     10117346.29
#Sta/Elev= 30
  3946.5  222.35  4105.2  219.58  4200.8   213.7  4274.1  212.49  4460.9   213.4
  4556.5  206.31  4715.8  201.79  4784.8  201.96  4811.4  199.53  4816.7  202.09
  4938.9  200.23  4970.7  197.09    4976   199.4  4981.7  196.54    4997  190.27
  5034.2  196.34  5118.1  200.59    5170  202.42  5175.2  199.98  5304.8  201.74
    5310  199.89  5407.2  202.73  5504.4  199.09  5511.2  197.04  5552.5  201.01
    5704  206.06  5811.6  205.49  5838.8  208.31    6006   212.9  6140.8  212.88
#Mann= 8 ,-1 , 0
  3946.5    .125       0  4274.1     .11       0  4938.9     .11       0
  4981.7     .07       0  5034.2    .125       0  5118.1    .125       0
  5511.2     .11       0  5552.5    .125       0
#XS Ineff= 2 , 0
       0    4976   199.4  5105.2       0  200.15
Permanent Ineff=
       F       T
Bank Sta=4981.7,5034.2
XS Rating Curve= 0 ,0
Exp/Cntr=0.3,0.1

Type RM Length L Ch R = 1 ,19389   ,511,511,511
BEGIN DESCRIPTION:
LIVE OAK BRANCH 37.0
END DESCRIPTION:
XS GIS Cut Line= 3
      3826323.14     10117868.48      3825152.03     10117489.85
      3824232.81     10117197.79
#Sta/Elev= 30
  3769.2  227.07  3874.6  226.55  3953.4  219.65  4071.9  214.46  4098.7  211.56
    4104  208.34  4130.7  213.08    4200  218.78  4328.1  215.25  4365.4  217.11
  4502.1  209.51  4513.4  208.91  4653.5   202.9  4836.2  202.65  4930.8  198.32
 4943.43  195.71  4971.1   188.7  5016.3  190.64  5035.9  195.69  5043.3  198.23
  5048.6  196.94  5075.6  200.35  5242.1  201.44  5298.2  198.98  5319.2  192.19
  5329.7  191.99  5371.1  199.13  5607.3  201.16  5885.8  209.33  5964.5  208.37
#Mann= 7 ,-1 , 0
  3769.2    .125       0  4502.1     .11       0  4513.4    .125       0
  4930.8     .12       0 4943.43     .09       0  5035.9    .125       0
  5048.6    .125       0
#XS Ineff= 2 , 0
       0  4930.9  198.31  5043.3       0  198.23
Permanent Ineff=
       F       T
Bank Sta=4943.43,5035.9
XS Rating Curve= 0 ,0
Exp/Cntr=0.3,0.1

Type RM Length L Ch R = 1 ,18878   ,526,526,526
BEGIN DESCRIPTION:
LIVE OAK BRANCH 36.0
END DESCRIPTION:
XS GIS Cut Line= 3
      3825610.81      10116876.2      3824897.59     10117046.62
      3823816.55       10116884.
#Sta/Elev= 30
  4266.7  228.68  4329.2   225.7  4480.9  211.98  4547.3  208.27  4607.1  206.36
  4612.3  207.23  4639.9  203.81  4743.7  199.31  4773.5  195.98  4785.7  193.08
  4841.1  192.27  4906.8  192.72  4927.8  195.38    4938  192.33  4959.2  191.48
  4987.6  186.18  4998.8  188.19    5020  189.04  5030.1  191.04  5040.2  192.92
  5050.3  193.03  5212.1  192.56  5353.7  193.95  5626.7  201.18  5738.8  201.56
  5768.3  200.81  5818.8   204.2  5990.8  211.65  6036.4     215  6093.2  218.81
#Mann= 8 ,-1 , 0
  4266.7     .11       0  4329.2    .125       0  4841.1     .11       0
  4927.8     .11       0  4959.2     .06       0  5030.1     .11       0
  5738.8    .125       0  6036.4     .11       0
#XS Ineff= 2 , 0
       0  4927.8  195.38               0
Permanent Ineff=
       F       F
Bank Sta=4959.2,5030.1
XS Rating Curve= 0 ,0
Exp/Cntr=0.3,0.1

Type RM Length L Ch R = 1 ,18352   ,474,474,474
BEGIN DESCRIPTION:
LIVE OAK BRANCH 34.0
END DESCRIPTION:
XS GIS Cut Line= 3
      3825248.56      10116264.4      3824521.53     10116680.13
      3823838.92     10116826.39
#Sta/Elev= 30
  4162.5  210.64  4220.7   208.1  4285.5  208.36  4307.1  206.17  4336.1   206.6
  4381.9   204.1  4403.5  199.01  4425.1  191.29  4467.1  190.18  4533.1  191.59
  4582.6  190.83  4645.4  189.67  4672.7  191.57  4710.1  190.39    4726     193
  4731.7  195.51  4747.6  196.92  4849.8  192.87  4967.8  192.78  4981.2  190.93
  4995.2  185.64  5021.9  184.25  5034.4  186.44  5044.7  190.51  5054.9  195.07
  5198.1  195.33  5270.9  197.93  5338.2  197.64  5355.5  198.72  5698.1  218.05
#Mann= 8 ,-1 , 0
  4162.5     .11       0  4467.1    .125       0  4582.6     .11       0
  4967.8     .11       0  4981.2     .07       0  5044.7     .11       0
  5338.2    .125       0  5355.5     .11       0
#XS Ineff= 2 , 0
       0  4747.6  196.92               0
Permanent Ineff=
       T       F
Bank Sta=4981.2,5044.7
XS Rating Curve= 0 ,0
Exp/Cntr=0.3,0.1

Type RM Length L Ch R = 1 ,17878   ,485,485,485
BEGIN DESCRIPTION:
LIVE OAK BRANCH 33.0
END DESCRIPTION:
XS GIS Cut Line= 3
      3824915.51     10115988.18      3824280.64      10116280.4
      3823711.32     10116544.75
#Sta/Elev= 30
  4301.1  225.41  4368.9  221.02  4399.5  217.01  4474.7  208.44  4558.2  201.47
  4604.1  199.46  4650.1  199.83  4694.8  195.55  4701.5  193.52  4724.5  191.83
  4798.9  189.46  4913.7  190.08    4959  189.64  4965.1  188.07  4981.1  184.34
  4986.2   181.7  5004.3  183.54  5025.1  188.56  5047.2  190.63  5182.3  195.97
  5210.2   197.7  5228.1  196.96  5234.6   199.1  5279.4  201.65  5296.8  204.03
  5320.9  204.11  5431.7  208.89  5485.5  211.25  5542.4  211.68  5627.7   216.2
#Mann= 10 ,-1 , 0
  4301.1    .125       0  4399.5     .11       0  4694.8     .11       0
  4965.1     .06       0  5025.1     .11       0  5182.3     .17       0
  5210.2     .11       0  5320.9    .125       0  5431.7     .11       0
  5542.4     .17       0
Bank Sta=4965.1,5025.1
XS Rating Curve= 0 ,0
Exp/Cntr=0.3,0.1

Type RM Length L Ch R = 1 ,17393   ,468,468,468
BEGIN DESCRIPTION:
LIVE OAK BRANCH 32.0
END DESCRIPTION:
XS GIS Cut Line= 3
      3824806.19      10115824.1      3824078.58      10115908.6
      3823535.29     10116251.21
#Sta/Elev= 30
  4267.5  218.24  4372.1   208.8  4416.8  205.35    4447  205.35    4455   204.2
    4460  205.02  4467.2  202.26  4487.3  200.63    4598  197.09  4678.6  192.51
    4739  191.89  4779.3  190.01  4930.3  190.12  4940.3  188.74  4960.5  188.74
  4970.5  186.97  4976.8  184.15  4981.9  184.95  4990.7  182.97  4995.9  180.41
  5016.3  181.29  5031.6  186.92  5037.5   185.8  5046.9   187.5  5084.4  187.65
  5274.5  192.34  5417.6  203.42  5544.8  208.78  5590.6  213.04  5642.3  215.72
#Mann= 7 ,-1 , 0
  4267.5     .15       0  4372.1     .11       0  4970.5     .09       0
  5031.6     .17       0  5084.4     .15       0  5274.5     .11       0
  5417.6     .17       0
#XS Ineff= 2 , 0
       0  4910.1  190.47               0
Permanent Ineff=
       F       F
Bank Sta=4970.5,5031.6
XS Rating Curve= 0 ,0
Exp/Cntr=0.3,0.1

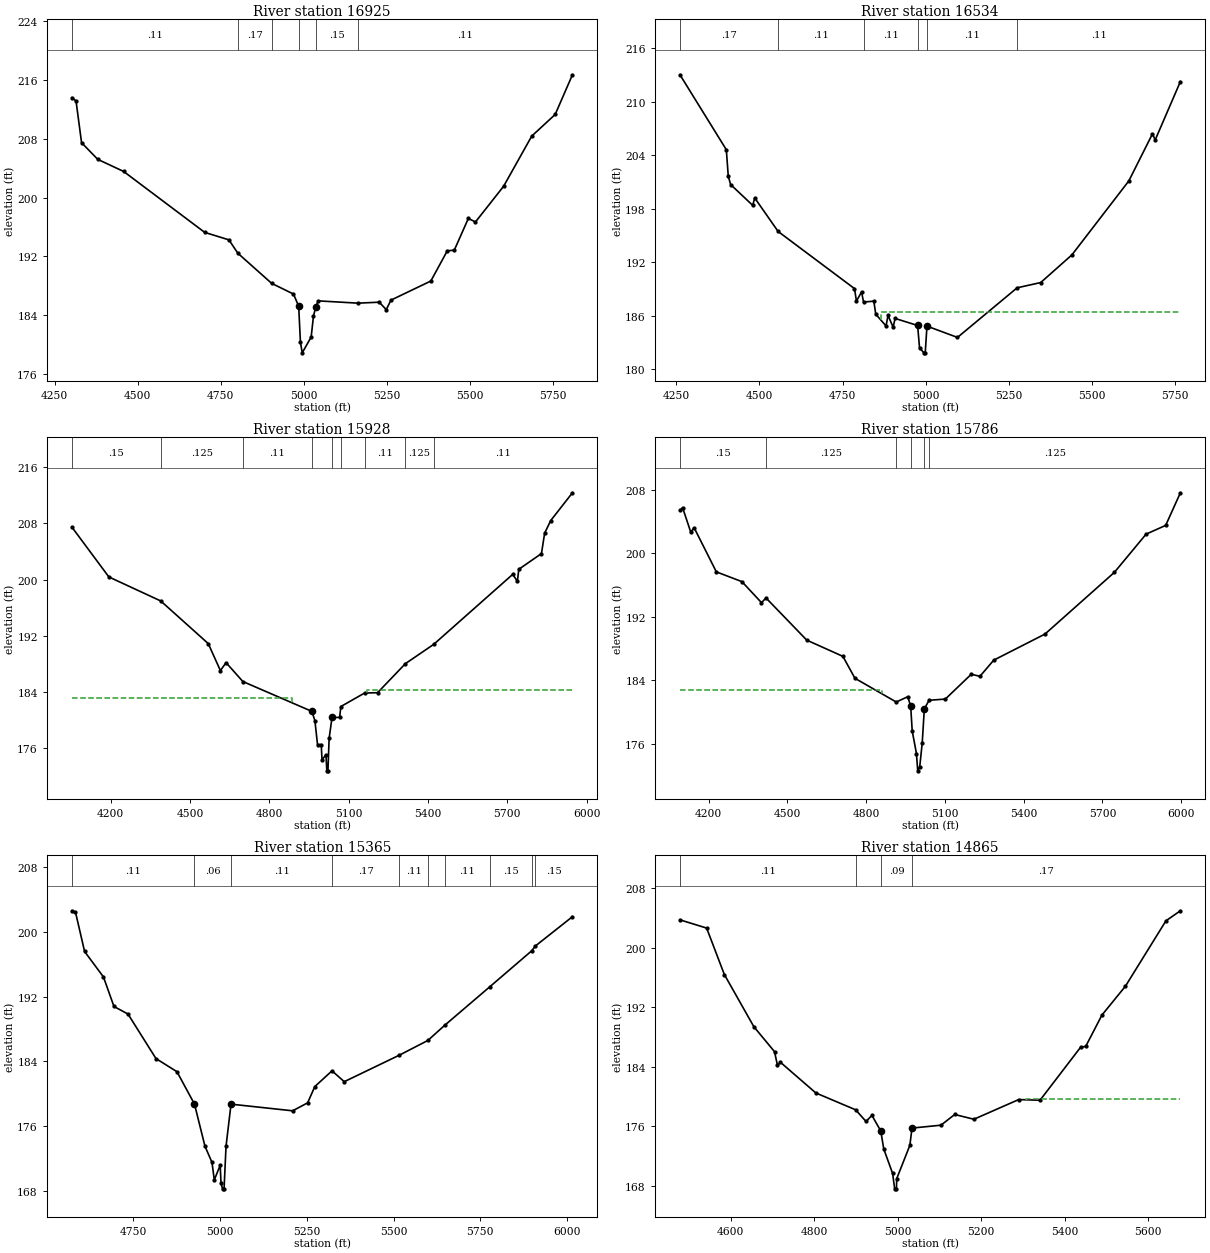
Type RM Length L Ch R = 1 ,16925   ,391,391,391
BEGIN DESCRIPTION:
LIVE OAK BRANCH 31.0
END DESCRIPTION:
XS GIS Cut Line= 3
      3824709.79     10115399.63       3824027.8     10115549.22
      3823450.58      10116117.2
#Sta/Elev= 30
  4301.8  213.61    4314  213.15  4330.6  207.48  4379.5  205.21  4457.3  203.57
  4701.6  195.28  4774.7  194.26  4801.6  192.44  4903.5  188.34  4969.2  186.89
  4984.9  185.23  4990.1  180.35  4995.5  178.89  5022.5  181.04  5029.5  183.91
  5036.6  185.16  5043.7  185.96  5163.5  185.65  5227.5  185.78  5248.8  184.77
  5262.9  186.06  5383.1  188.66  5432.7  192.77  5453.8  192.86  5496.2  197.18
  5517.5  196.69  5602.4  201.55  5687.2  208.38  5757.8  211.32  5809.8  216.72
#Mann= 6 ,-1 , 0
  4301.8     .11       0  4801.6     .17       0  4903.5     .11       0
  4984.9     .07       0  5036.6     .15       0  5163.5     .11       0
Bank Sta=4984.9,5036.6
XS Rating Curve= 0 ,0
Exp/Cntr=0.3,0.1

Type RM Length L Ch R = 1 ,16534   ,606,606,606
BEGIN DESCRIPTION:
LIVE OAK BRANCH 30.0
END DESCRIPTION:
XS GIS Cut Line= 3
      3824367.86     10114911.07      3823737.07     10115295.69
      3823280.09     10115910.07
#Sta/Elev= 30
  4261.2  213.03  4400.6  204.62  4406.4  201.65  4413.5  200.71    4480  198.37
  4485.9  199.21  4556.4  195.44  4785.9  189.03  4791.8  187.63  4807.2  188.66
  4813.1  187.52    4844  187.62  4849.9  186.15  4880.8  184.84  4886.7  186.02
  4902.1   184.7    4908  185.68  4975.7  184.89  4981.5  182.37  4994.7  181.82
  4998.6  181.82  5003.8  184.82  5095.5  183.55  5274.9  189.12  5345.8  189.71
  5439.7  192.82  5610.7  201.12  5681.6  206.39    5690  205.72  5765.7  212.27
#Mann= 6 ,-1 , 0
  4261.2     .17       0  4556.4     .11       0  4813.1     .11       0
  4975.7     .06       0  5003.8     .11       0  5274.9     .11       0
#XS Ineff= 2 ,-1
    4844  4822.7  187.62  4865.3    4844  186.44
Permanent Ineff=
       F       F
Bank Sta=4975.7,5003.8
XS Rating Curve= 0 ,0
Exp/Cntr=0.3,0.1

Type RM Length L Ch R = 1 ,15928   ,142,142,142
BEGIN DESCRIPTION:
LIVE OAK BRANCH 29.0
END DESCRIPTION:
XS GIS Cut Line= 3
      3824316.86     10114509.71      3823441.86     10114868.23
      3822581.33     10115261.65
#Sta/Elev= 30
  4054.4  207.43  4193.8  200.37  4389.8  196.96  4569.5   190.9  4615.3  187.07
  4636.9  188.19  4700.3  185.51  4961.1  181.27  4972.6  179.96  4982.7  176.51
  4996.6  176.56  4999.5  174.36  5014.4  175.12  5017.8  172.82  5021.9  172.82
  5026.4  177.42  5037.4  180.41  5065.9  180.41  5070.9  181.96  5160.7  183.88
  5209.5  183.92  5314.7  188.05  5421.7  190.79  5720.5  200.74    5738  199.75
  5743.5  201.46  5829.1  203.69  5841.1  206.59  5864.1  208.38  5946.2  212.33
#Mann= 9 ,-1 , 0
  4054.4     .15       0  4389.8    .125       0  4700.3     .11       0
  4961.1     .07       0  5037.4     .11       0  5070.9    .125       0
  5160.7     .11       0  5314.7    .125       0  5421.7     .11       0
#XS Ineff= 2 , 0
       0  4884.4  183.22  5169.3       0  184.37
Permanent Ineff=
       F       F
Bank Sta=4961.1,5037.4
XS Rating Curve= 0 ,0
Exp/Cntr=0.3,0.1

Type RM Length L Ch R = 1 ,15786   ,421,421,421
BEGIN DESCRIPTION:
LIVE OAK BRANCH 28.0
END DESCRIPTION:
XS GIS Cut Line= 3
      3824267.05     10114347.56      3823440.11      10114726.2
        3822533.     10115139.92
#Sta/Elev= 30
  4090.5  205.37  4100.6  205.72  4131.5  202.65  4144.6  203.19  4229.1  197.65
  4326.6  196.42  4401.1  193.78  4418.4  194.37  4573.5  189.07  4711.2  187.03
  4757.2  184.27  4914.5  181.29  4958.5  181.96  4969.5  180.76  4975.3  177.65
  4991.5  174.81  4996.3  172.64    5004  173.16  5013.5  176.16  5021.4  180.41
  5039.4  181.51  5101.5  181.66  5200.3  184.78  5233.3  184.52  5285.8  186.55
  5481.1  189.83  5745.6  197.59  5866.3  202.39  5940.9  203.49    5997  207.59
#Mann= 6 ,-1 , 0
  4090.5     .15       0  4418.4    .125       0  4914.5     .11       0
  4969.5     .06       0  5021.4     .11       0  5039.4    .125       0
#XS Ineff= 2 , 0
       0  4860.3  182.74               0
Permanent Ineff=
       F       F
Bank Sta=4969.5,5021.4
XS Rating Curve= 0 ,0
Exp/Cntr=0.3,0.1

Type RM Length L Ch R = 1 ,15365   ,500,500,500
BEGIN DESCRIPTION:
LIVE OAK BRANCH 27.0
END DESCRIPTION:
XS GIS Cut Line= 3
      3823217.86     10113921.15      3823274.88     10114344.53
       3822483.5     10114981.06
#Sta/Elev= 30
  4572.8  202.57  4582.8  202.41  4609.1  197.55  4663.5  194.41  4693.8  190.77
  4734.2  189.84  4814.9  184.35  4875.4  182.73  4925.9  178.74  4956.1  173.55
  4976.3  171.56  4983.1  169.39    5000   171.2  5002.5  168.95  5006.9  168.29
  5011.2  168.29  5016.9  173.55  5031.3  178.73  5208.9  177.91  5252.1  178.89
  5272.9   180.9  5322.5  182.84  5357.7   181.5  5516.6  184.77  5598.7  186.58
  5647.3  188.45  5777.9  193.22  5898.3  197.64  5908.5  198.22  6015.6  201.84
#Mann= 10 ,-1 , 0
  4572.8     .11       0  4925.9     .06       0  5031.3     .11       0
  5322.5     .17       0  5516.6     .11       0  5598.7     .17       0
  5647.3     .11       0  5777.9     .15       0  5898.3     .17       0
  5908.5     .15       0
Bank Sta=4925.9,5031.3
XS Rating Curve= 0 ,0
Exp/Cntr=0.3,0.1

Type RM Length L Ch R = 1 ,14865   ,496,496,496
BEGIN DESCRIPTION:
LIVE OAK BRANCH 26.0
END DESCRIPTION:
XS GIS Cut Line= 3
      3823189.22     10113882.12      3822819.68     10114249.96
       3822155.4     10114382.11
#Sta/Elev= 30
  4478.6  203.78  4542.5  202.67  4584.9  196.42  4655.6  189.39  4705.1  186.03
  4712.2  184.18  4719.3   184.6  4804.1  180.47  4899.4   178.2  4924.3  176.63
  4938.4  177.45  4959.7  175.34  4966.7  172.94    4988  169.63  4992.9  167.56
  4997.2  167.56  4997.8  168.93  5029.3  173.42  5034.4  175.74  5103.8  176.13
  5136.7  177.57  5182.7  176.93    5290  179.58  5341.1  179.49  5438.3  186.63
  5450.5  186.74  5489.4  190.96  5545.6  194.84  5642.7  203.65  5677.3     205
#Mann= 4 ,-1 , 0
  4478.6     .11       0  4899.4     .17       0  4959.7     .09       0
  5034.4     .17       0
#XS Ineff= 2 , 0
       0                  5307.7       0  179.61
Permanent Ineff=
       F       F
Bank Sta=4959.7,5034.4
XS Rating Curve= 0 ,0
Exp/Cntr=0.3,0.1