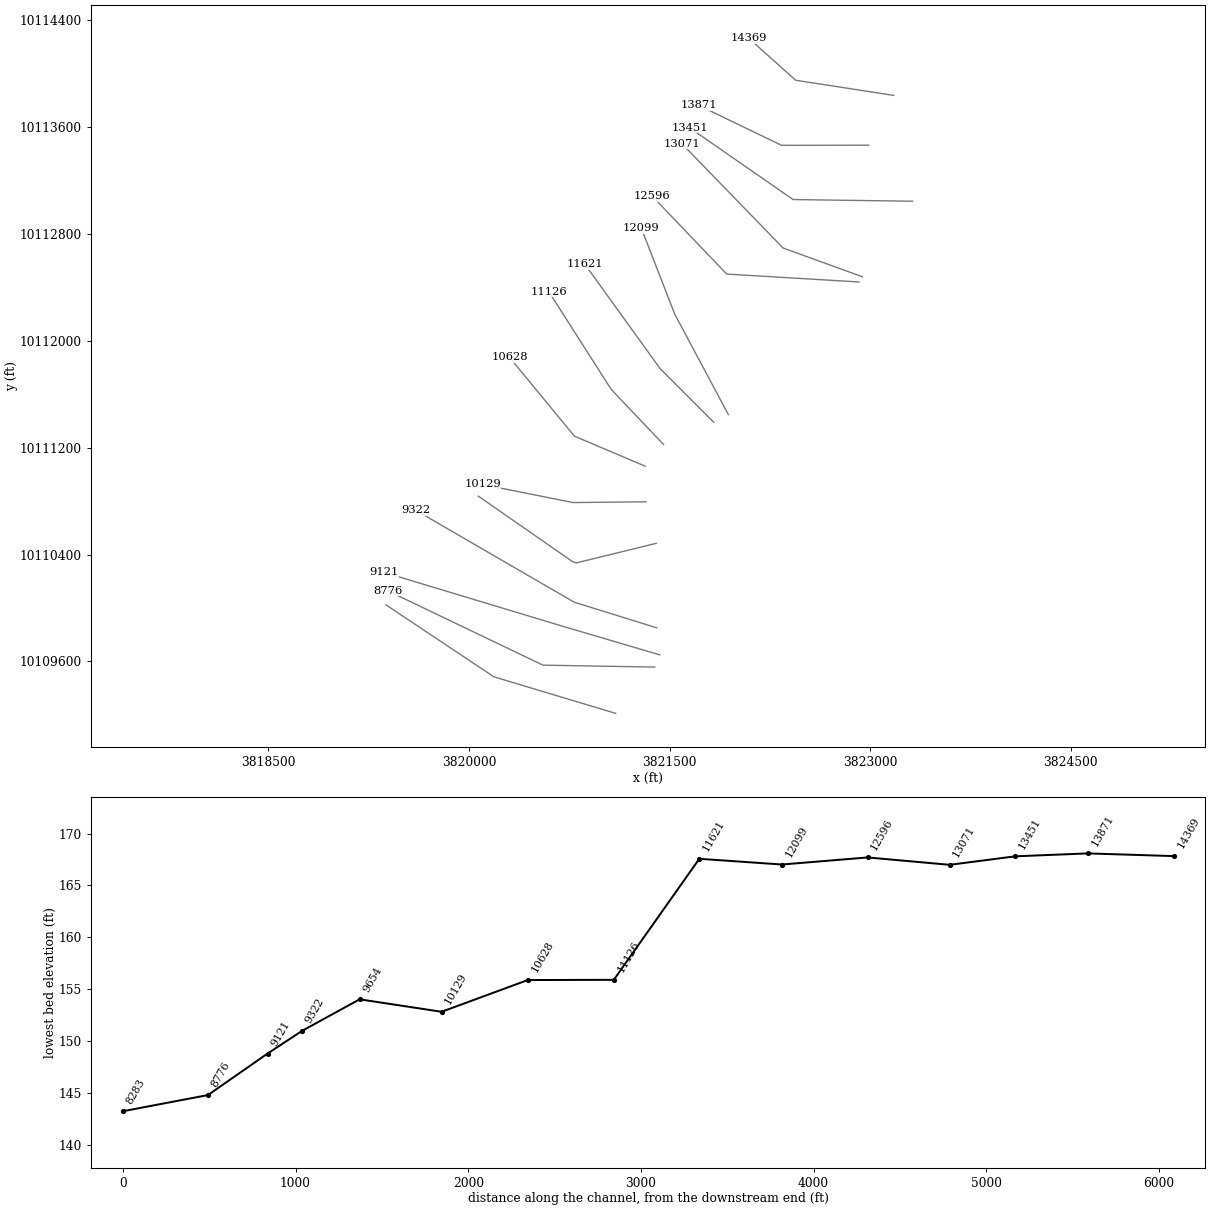
HEC-RAS study LIVE OAK BRANCH.prj: LIVE OAK BRANCH Base Level Engineering

--- LIVE OAK BRANCH.g01 (geometry) --- (continued)

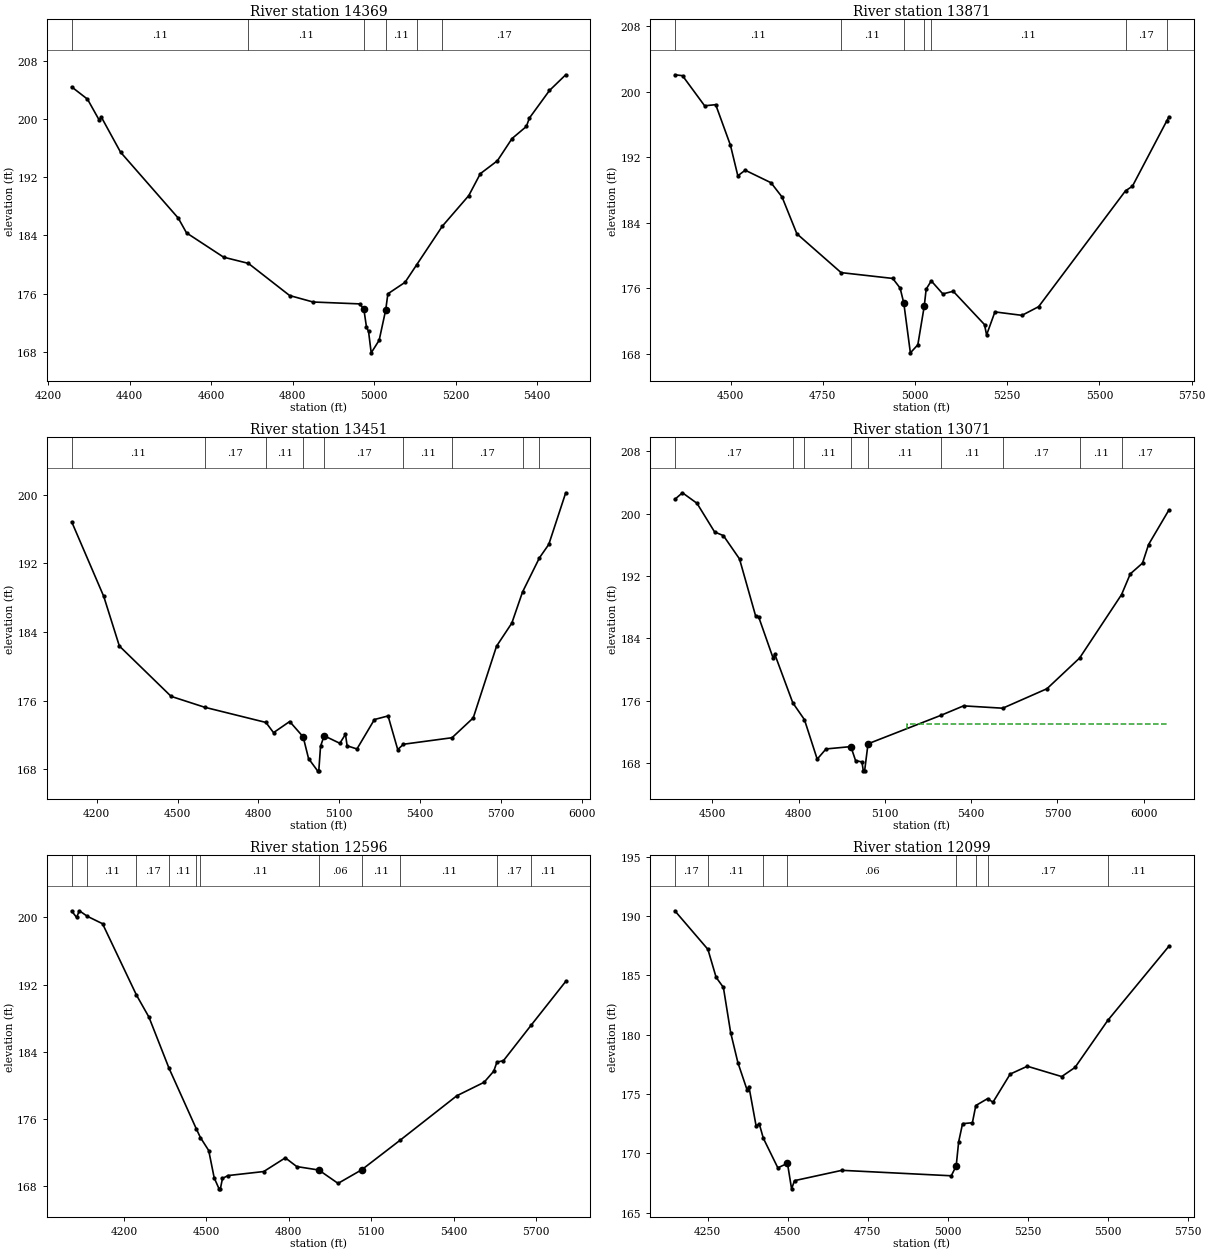
Type RM Length L Ch R = 1 ,14369   ,498,498,498
BEGIN DESCRIPTION:
LIVE OAK BRANCH 25.0
END DESCRIPTION:
XS GIS Cut Line= 3
      3823176.23     10113835.24      3822442.87     10113948.76
      3822092.88     10114262.31
#Sta/Elev= 30
  4257.9  204.45  4296.7  202.76  4325.4  199.88  4330.4  200.32  4377.7  195.47
  4519.4  186.38  4539.6  184.35  4630.7     181  4691.4  180.15  4792.6  175.72
    4850  174.83  4964.6  174.57  4974.7  173.83  4981.1  171.38  4986.2  170.77
  4992.7  167.83  5012.2  169.56 5028.28  173.74  5033.6  175.96  5075.7  177.54
  5104.2  179.95  5167.3  185.28    5232  189.48  5260.4   192.5  5302.3  194.28
  5338.2  197.34  5373.3     199  5380.8  200.16  5430.1  203.96  5469.9  206.12
#Mann= 6 ,-1 , 0
  4257.9     .11       0  4691.4     .11       0  4974.7     .06       0
 5028.28     .11       0  5104.2     .11       0  5167.3     .17       0
Bank Sta=4974.7,5028.28
XS Rating Curve= 0 ,0
Exp/Cntr=0.3,0.1

Type RM Length L Ch R = 1 ,13871   ,420,420,420
BEGIN DESCRIPTION:
LIVE OAK BRANCH 24.0
END DESCRIPTION:
XS GIS Cut Line= 3
      3822988.66     10113462.84      3822337.46     10113461.64
      3821717.82     10113761.09
#Sta/Elev= 30
  4348.8  202.06  4369.6  201.95  4429.6  198.27  4459.6  198.41  4499.6  193.45
  4519.6  189.72  4539.6   190.4  4609.6  188.87  4639.6  187.12  4679.6  182.64
  4799.6  177.89  4939.6  177.18  4959.6     176  4969.6  174.16  4987.4  168.09
  5007.6  169.07    5025  173.79  5030.2  175.87    5044  176.88  5075.4  175.29
  5103.6  175.61  5188.4  171.54    5194  170.28  5216.6  173.09  5289.9  172.67
  5335.1  173.73  5570.7  187.89  5589.3  188.44  5682.4  196.42  5688.2  196.92
#Mann= 7 ,-1 , 0
  4348.8     .11       0  4799.6     .11       0  4969.6     .06       0
    5025     .11       0    5044     .11       0  5570.7     .17       0
  5682.4     .11       0
#XS Ineff= 2 , 0
       0                    5044       0  176.88
Permanent Ineff=
       F       T
Bank Sta=4969.6,5025
XS Rating Curve= 0 ,0
Exp/Cntr=0.3,0.1

Type RM Length L Ch R = 1 ,13451   ,380,380,380
BEGIN DESCRIPTION:
LIVE OAK BRANCH 23.0
END DESCRIPTION:
XS GIS Cut Line= 3
      3823316.82     10113043.57       3822423.7     10113055.98
      3821651.48     10113592.14
#Sta/Elev= 30
  4106.8  196.84  4225.8  188.14  4283.7  182.36  4475.8  176.49  4600.5  175.22
  4827.7  173.45  4855.8  172.26  4915.8  173.56  4965.8  171.77  4985.8  169.24
  5019.3  167.81  5023.8  167.81  5030.3  170.67  5043.6   171.9  5101.9  171.02
  5122.8  172.07  5128.9  170.73  5165.4  170.36  5230.2  173.79  5280.9  174.21
  5316.7  170.29    5338  170.91  5518.2  171.67  5596.9  173.98  5683.4  182.34
  5740.1  185.03  5779.9  188.66  5842.6  192.64  5877.2   194.2  5940.1  200.22
#Mann= 9 ,-1 , 0
  4106.8     .11       0  4600.5     .17       0  4827.7     .11       0
  4965.8     .09       0  5043.6     .17       0    5338     .11       0
  5518.2     .17       0  5779.9     .11       0  5842.6     .17       0
#XS Ineff= 2 , 0
       0                  5251.2       0  173.95
Permanent Ineff=
       F       T
Bank Sta=4965.8,5043.6
XS Rating Curve= 0 ,0
Exp/Cntr=0.3,0.1

Type RM Length L Ch R = 1 ,13071   ,475,475,475
BEGIN DESCRIPTION:
LIVE OAK BRANCH 22.0
END DESCRIPTION:
XS GIS Cut Line= 3
      3822941.79     10112478.48      3822348.64     10112693.44
      3821591.55     10113474.54
#Sta/Elev= 30
  4369.1  201.84  4395.6  202.68  4446.2  201.33  4507.5  197.65  4538.1  197.18
  4594.1  194.19  4649.8  186.92  4660.7  186.75  4711.3  181.43  4716.6  181.98
  4779.5  175.72    4820  173.56  4864.4  168.49  4895.1   169.8  4981.6   170.1
  4997.8  168.31  5020.1  168.13  5024.8  166.99  5029.4  166.99  5041.2  170.46
  5295.9  174.13  5373.6  175.33  5509.8  175.03  5663.7  177.53  5777.3  181.47
  5923.2  189.61  5953.6  192.27  5996.1  193.65  6017.2  196.04  6087.8  200.46
#Mann= 9 ,-1 , 0
  4369.1     .17       0  4779.5     .11       0    4820     .11       0
  4981.6     .06       0  5041.2     .11       0  5295.9     .11       0
  5509.8     .17       0  5777.3     .11       0  5923.2     .17       0
#XS Ineff= 2 , 0
       0                  5175.8       0  172.98
Permanent Ineff=
       F       F
Bank Sta=4981.6,5041.2
XS Rating Curve= 0 ,0
Exp/Cntr=0.3,0.1

Type RM Length L Ch R = 1 ,12596   ,497,497,497
BEGIN DESCRIPTION:
LIVE OAK BRANCH 21.0
END DESCRIPTION:
XS GIS Cut Line= 3
      3822915.74     10112439.41      3821927.01     10112498.59
      3821368.93     10113082.62
#Sta/Elev= 30
  4009.5  200.77  4027.4  200.01  4037.4   200.8  4066.7  200.14  4121.8  199.26
  4245.4  190.76  4290.6  188.15  4363.9  182.05    4463  174.85  4478.2   173.8
  4508.3  172.26  4528.3     169    4546   167.7  4550.7   167.7  4558.4  168.94
  4578.4  169.28  4708.6  169.76  4787.1  171.39  4828.8  170.35    4909  169.94
  4979.1  168.35  5064.8  169.96  5206.3  173.52  5411.4  178.78  5510.5  180.38
  5545.7   181.7  5557.4  182.78  5581.2  182.96  5681.2  187.15  5807.8  192.39
#Mann= 11 ,-1 , 0
  4009.5     .17       0  4066.7     .11       0  4245.4     .17       0
  4363.9     .11       0    4463     .17       0  4478.2     .11       0
    4909     .06       0  5064.8     .11       0  5206.3     .11       0
  5557.4     .17       0  5681.2     .11       0
Bank Sta=4909,5064.8
XS Rating Curve= 0 ,0
Exp/Cntr=0.3,0.1

Type RM Length L Ch R = 1 ,12099   ,478,478,478
BEGIN DESCRIPTION:
LIVE OAK BRANCH 20.0
END DESCRIPTION:
XS GIS Cut Line= 3
      3821939.22     10111447.23      3821538.28     10112199.22
      3821288.18     10112843.05
#Sta/Elev= 30
  4147.8  190.45  4251.1   187.2  4276.8  184.84  4299.5  183.99  4322.1  180.19
  4344.8  177.65  4373.5  175.35  4379.2  175.64  4401.5  172.34  4411.8  172.47
  4424.1  171.29  4469.5  168.79  4499.6  169.17  4512.4  167.02  4521.6  167.71
  4669.6  168.58  5011.2  168.12 5026.52  168.95  5034.2  170.98  5046.4  172.51
  5077.1  172.59  5087.8  174.04  5124.5  174.62  5141.4  174.32  5195.1  176.69
  5248.7  177.35    5356  176.48  5397.6  177.25  5499.8  181.21  5690.7  187.46
#Mann= 8 ,-1 , 0
  4147.8     .17       0  4251.1     .11       0  4424.1     .11       0
  4499.6     .06       0 5026.52     .11       0  5087.8     .11       0
  5124.5     .17       0  5499.8     .11       0
Bank Sta=4499.6,5026.52
XS Rating Curve= 0 ,0
Exp/Cntr=0.3,0.1

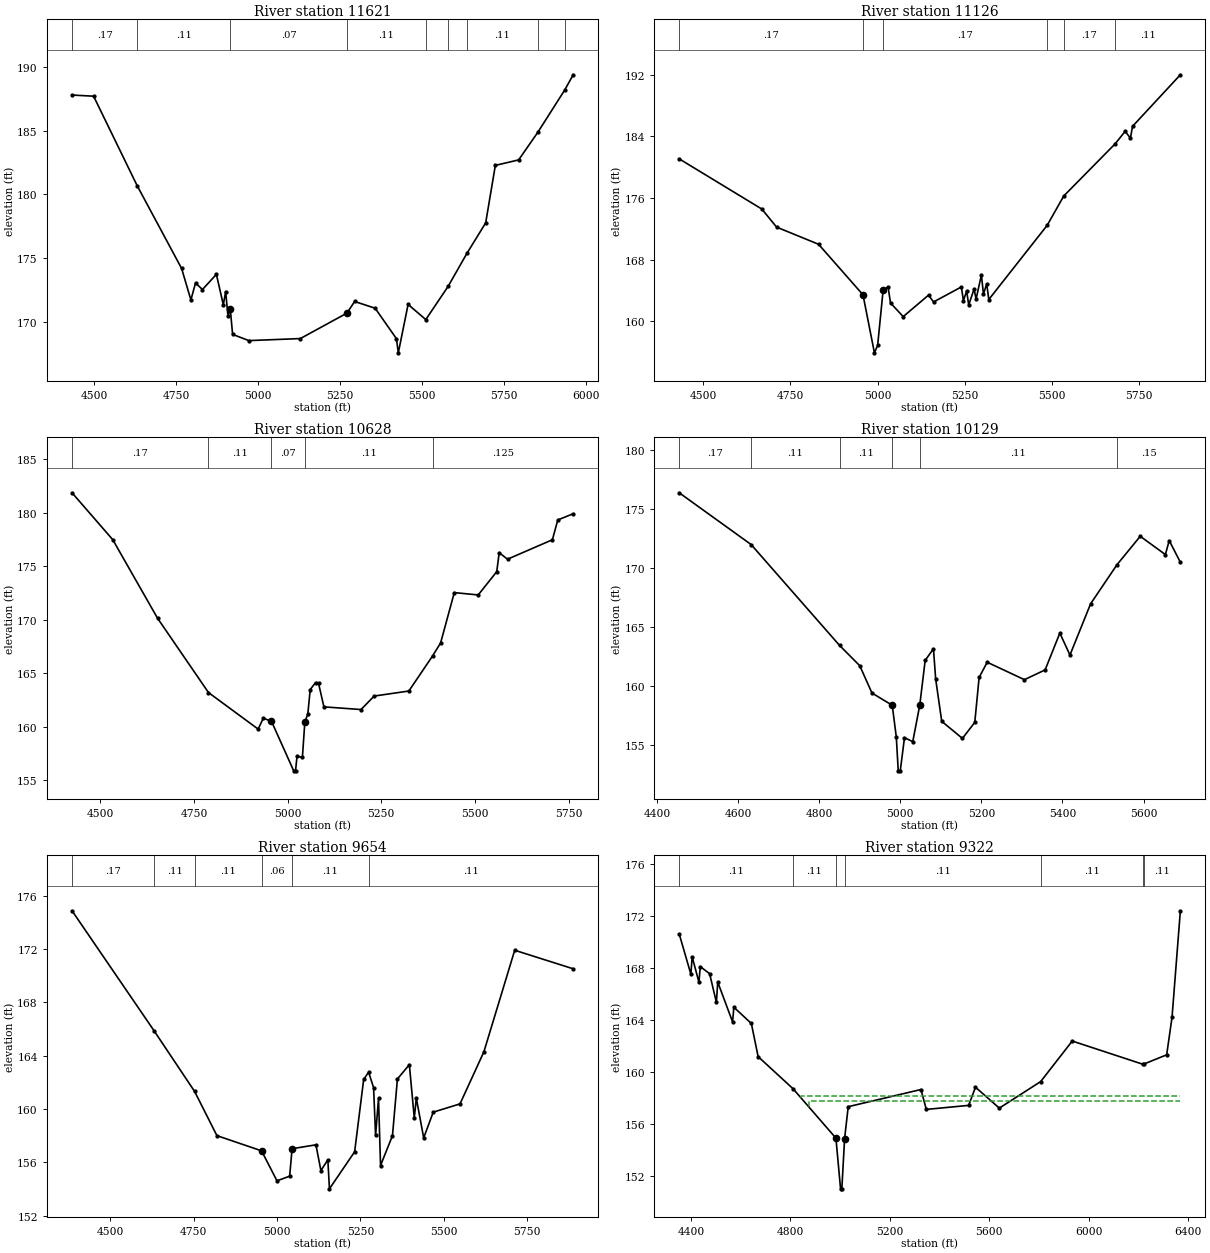
Type RM Length L Ch R = 1 ,11621   ,495,495,495
BEGIN DESCRIPTION:
LIVE OAK BRANCH 19.0
END DESCRIPTION:
XS GIS Cut Line= 3
      3821829.82     10111389.96      3821428.32      10111792.3
      3820866.32     10112572.21
#Sta/Elev= 30
  4431.6   187.8  4497.4  187.71  4630.5  180.68  4766.1  174.19  4794.4  171.72
  4808.5  173.05  4829.7  172.54  4872.2  173.73  4893.4  171.34  4900.5  172.38
  4907.5  170.46  4914.6  171.01  4921.7  169.02  4971.2  168.53  5128.5  168.69
  5270.9  170.69  5294.1   171.6  5356.8  171.07  5421.8  168.68  5427.5  167.57
  5457.4  171.37  5511.4  170.18  5579.4  172.78  5636.8  175.37  5694.2  177.77
  5723.7  182.28  5794.8  182.71  5853.7  184.89  5935.8  188.21  5961.3  189.39
#Mann= 9 ,-1 , 0
  4431.6     .17       0  4630.5     .11       0  4914.6     .07       0
  5270.9     .11       0  5511.4     .17       0  5579.4    .125       0
  5636.8     .11       0  5853.7    .125       0  5935.8     .11       0
#XS Ineff= 2 , 0
       0  4914.6  171.01  5294.1       0   171.6
Permanent Ineff=
       F       T
Bank Sta=4914.6,5270.9
XS Rating Curve= 0 ,0
Exp/Cntr=0.3,0.1

Type RM Length L Ch R = 1 ,11126   ,498,498,498
BEGIN DESCRIPTION:
LIVE OAK BRANCH 18.0
END DESCRIPTION:
XS GIS Cut Line= 3
      3821454.88     10111223.23      3821063.29     10111635.91
      3820596.45     10112367.56
#Sta/Elev= 30
  4431.1  181.07  4667.9  174.56  4710.4  172.21  4830.6  169.99    4958  163.43
  4990.8   155.9    5000  156.87  5015.7  164.01  5029.9  164.47  5036.9  162.37
  5073.3   160.6    5146  163.39  5160.3   162.5    5240  164.45  5245.9  162.67
  5255.2  163.93  5261.1  162.11  5276.4  164.17  5282.3  162.89  5297.5     166
  5303.4  163.52  5312.7  164.84  5318.7  162.82    5486  172.44  5533.6  176.25
  5681.1  183.03  5709.6  184.64  5724.8  183.76  5730.8  185.29  5867.9  191.98
#Mann= 6 ,-1 , 0
  4431.1     .17       0    4958     .09       0  5015.7     .17       0
    5486     .11       0  5533.6     .17       0  5681.1     .11       0
#XS Ineff= 2 , 0
       0                  5297.5       0     166
Permanent Ineff=
       F       T
Bank Sta=4958,5015.7
XS Rating Curve= 0 ,0
Exp/Cntr=0.3,0.1

Type RM Length L Ch R = 1 ,10628   ,499,499,499
BEGIN DESCRIPTION:
LIVE OAK BRANCH 17.0
END DESCRIPTION:
XS GIS Cut Line= 3
      3821317.82     10111061.09      3820788.24     10111285.84
      3820303.81      10111874.3
#Sta/Elev= 30
  4424.7  181.87  4533.3  177.49  4652.8  170.15  4788.8   163.2  4921.4  159.78
  4935.2   160.8    4957  160.51  5016.3  155.88  5021.2  155.88  5025.2  157.25
  5039.5  157.13    5046  160.45  5053.9  161.18  5060.4  163.48  5074.7  164.13
  5082.6  164.06  5096.9  161.86  5195.9  161.61  5231.1  162.87  5323.6  163.34
  5387.7  166.66  5408.3  167.83  5444.9  172.54  5508.7  172.32  5558.2   174.5
  5564.7  176.27  5586.9  175.66  5706.7  177.48  5721.1  179.33  5762.2  179.91
#Mann= 5 ,-1 , 0
  4424.7     .17       0  4788.8     .11       0    4957     .07       0
    5046     .11       0  5387.7    .125       0
#XS Ineff= 2 , 0
       0  4826.7  162.22  5074.7       0  164.13
Permanent Ineff=
       F       T
Bank Sta=4957,5046
XS Rating Curve= 0 ,0
Exp/Cntr=0.3,0.1

Type RM Length L Ch R = 1 ,10129   ,475,475,475
BEGIN DESCRIPTION:
LIVE OAK BRANCH 16.0
END DESCRIPTION:
XS GIS Cut Line= 3
        3821323.     10110794.34      3820778.23     10110788.86
      3820100.91     10110924.17
#Sta/Elev= 30
  4455.2   176.4  4632.5  172.01  4850.4  163.46  4900.4  161.73  4930.4  159.42
  4980.4  158.38  4990.4  155.69  4995.2  152.82  5000.2  152.82  5010.6  155.64
    5031  155.29 5048.23  158.39  5061.6  162.19    5082  163.17  5087.5   160.6
  5102.4  157.02  5153.4  155.57  5183.9  156.93  5194.6  160.74  5214.5  162.03
  5306.3  160.55  5357.3  161.38  5393.6   164.5  5418.5  162.64  5469.5  166.99
  5534.7  170.31  5591.8  172.71  5653.8  171.16  5663.2  172.35  5690.7  170.51
#Mann= 6 ,-1 , 0
  4455.2     .17       0  4632.5     .11       0  4850.4     .11       0
  4980.4     .07       0 5048.23     .11       0  5534.7     .15       0
#XS Ineff= 2 , 0
       0                    5082       0  163.17
Permanent Ineff=
       F       T
Bank Sta=4980.4,5048.23
XS Rating Curve= 0 ,0
Exp/Cntr=0.3,0.1

Type RM Length L Ch R = 1 ,9654    ,332,332,332
BEGIN DESCRIPTION:
LIVE OAK BRANCH 15.0
END DESCRIPTION:
XS GIS Cut Line= 4
      3821399.86     10110483.72      3820802.87     10110337.25
      3820774.83     10110346.39      3820069.79     10110836.93
#Sta/Elev= 30
  4385.3  174.87  4632.5  165.83    4753  161.32  4819.8  158.01  4953.7  156.87
    5000  154.62    5038  154.97  5045.3  157.03  5116.8  157.32  5131.7  155.39
  5152.6   156.2  5157.3  154.02  5232.9   156.8    5260  162.22  5274.8  162.77
  5289.7  161.61  5295.7  158.02  5304.5   160.8  5310.6  155.77  5346.4  158.01
  5361.2  162.26    5397  163.33  5411.8  159.33  5417.9  160.82    5440  157.84
  5468.6  159.77  5548.9  160.39  5620.5  164.29    5713  171.91  5888.4  170.52
#Mann= 6 ,-1 , 0
  4385.3     .17       0  4632.5     .11       0    4753     .11       0
  4953.7     .06       0  5045.3     .11       0  5274.8     .11       0
#XS Ineff= 2 , 0
       0                  5274.8       0  162.77
Permanent Ineff=
       F       T
Bank Sta=4953.7,5045.3
XS Rating Curve= 0 ,0
Exp/Cntr=0.3,0.1

Type RM Length L Ch R = 1 ,9322    ,201,201,201
BEGIN DESCRIPTION:
Mapping XS c84b2657
END DESCRIPTION:
XS GIS Cut Line= 3
      3821404.73     10109851.21      3820785.87     10110043.68
      3819601.37     10110731.47
#Sta/Elev= 30
  4351.9   170.6  4398.9   167.5  4404.1  168.84  4431.4  166.88  4436.6  168.09
  4474.4  167.54  4501.7  165.33    4507   166.9  4566.8  163.83    4572  164.96
  4642.4  163.71  4669.7  161.16  4810.3  158.69  4982.9  154.89  5001.6  150.99
  5006.7  150.99 5017.86  154.86  5032.4  157.31  5325.3  158.63  5346.8   157.1
  5517.4  157.41  5544.7  158.81  5640.8   157.2  5807.2  159.24  5934.4  162.36
  6220.9  160.56  6221.6  160.58  6314.6   161.3  6336.2  164.19  6369.7  172.38
#Mann= 7 ,-1 , 0
  4351.9     .11       0  4810.3     .11       0  4982.9     .06       0
 5017.86     .11       0  5807.2     .11       0  6220.9     .15       0
  6221.6     .11       0
#XS Ineff= 3 ,-1
  4842.9  4810.3  158.16  4875.4  4842.9  157.75  5288.1  5544.7  158.19
Permanent Ineff=
       F       F       F
Bank Sta=4982.9,5017.86
XS Rating Curve= 0 ,0
Exp/Cntr=0.3,0.1

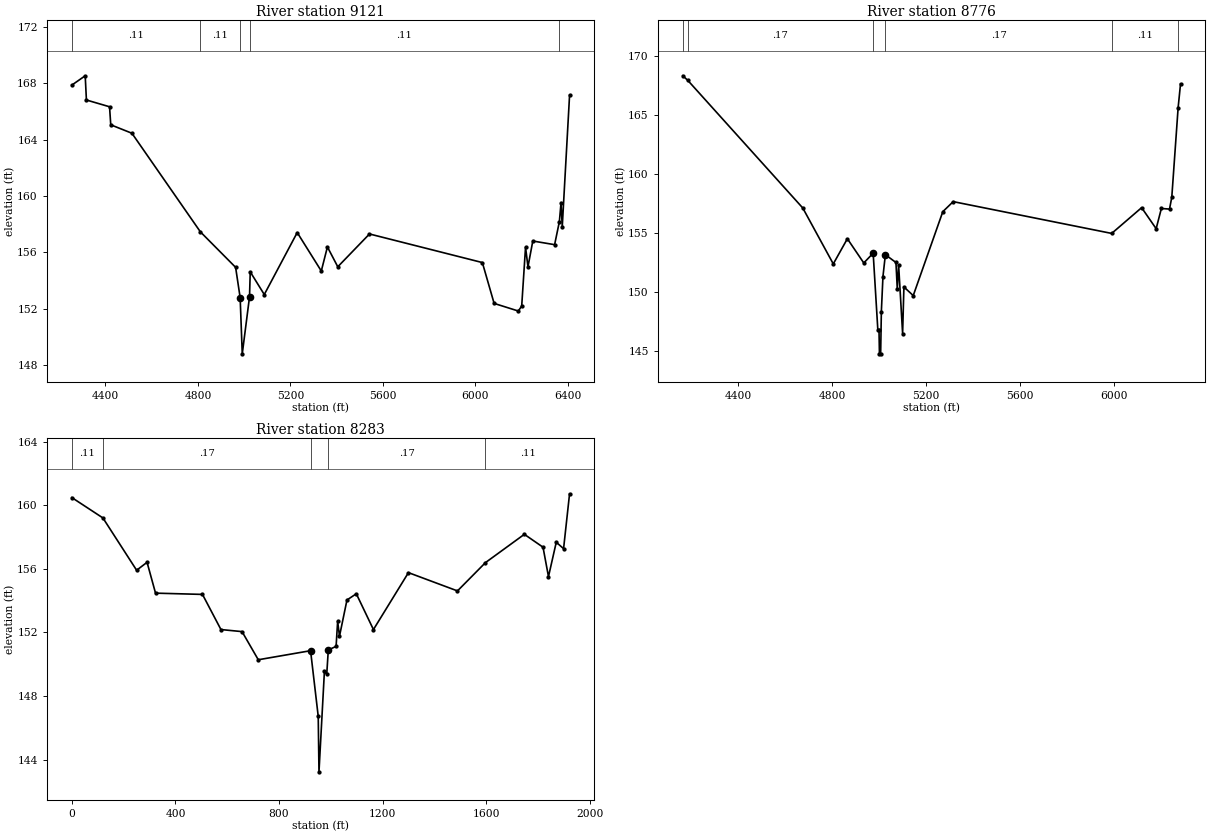
Type RM Length L Ch R = 1 ,9121    ,345,345,345
BEGIN DESCRIPTION:
LIVE OAK BRANCH 14.0
END DESCRIPTION:
XS GIS Cut Line= 3
      3821426.89     10109649.39      3820712.43     10109859.82
      3819365.69     10110266.12
#Sta/Elev= 30
  4255.2  167.87  4312.9  168.53  4318.1  166.81  4418.1  166.33  4423.3  165.05
  4514.8  164.45  4810.8  157.45  4963.1  154.93  4982.7  152.78  4991.8  148.79
 5023.15  152.83  5026.3  154.61    5087     153  5229.4   157.4  5333.5  154.67
  5359.9  156.38  5404.7  154.97  5541.8   157.3  6029.7  155.27  6080.6  152.37
  6185.1  151.83  6199.8  152.18  6216.4  156.36  6226.9  154.97  6247.8   156.8
  6342.1  156.54  6362.7  158.18  6369.9  159.53  6375.1  157.81  6406.7  167.14
#Mann= 5 ,-1 , 0
  4255.2     .11       0  4810.8     .11       0  4982.7     .06       0
 5023.15     .11       0  6362.7     .15       0
#XS Ineff= 2 , 0
       0                  5229.4       0   157.4
Permanent Ineff=
       F       T
Bank Sta=4982.7,5023.15
XS Rating Curve= 0 ,0
Exp/Cntr=0.3,0.1

Type RM Length L Ch R = 1 ,8776    ,493,493,493
BEGIN DESCRIPTION:
LIVE OAK BRANCH 13.0
END DESCRIPTION:
XS GIS Cut Line= 3
      3821389.05     10109557.82      3820552.98      10109572.3
       3819394.2     10110128.14
#Sta/Elev= 30
  4163.8  168.32    4185  167.93  4675.1  157.13  4805.1   152.4  4865.1  154.53
  4935.1  152.48  4975.1  153.31  4995.1  146.78    5000  146.78  5001.8  144.79
    5007  144.79    5010  148.37  5016.8  151.33  5027.1  153.18  5072.2  152.52
  5077.9  150.28  5083.5  152.33  5100.6  146.51  5106.1  150.45  5145.9  149.72
  5271.9  156.82  5316.2  157.67  5991.8  154.98  6119.4  157.16  6181.3  155.38
  6203.5  157.09  6238.2  157.04  6247.9  158.03    6275  165.63  6285.2  167.64
#Mann= 6 ,-1 , 0
  4163.8     .11       0    4185     .17       0  4975.1     .09       0
  5027.1     .17       0  5991.8     .11       0    6275     .15       0
#XS Ineff= 2 , 0
       0                  5316.2       0  157.67
Permanent Ineff=
       F       F
Bank Sta=4975.1,5027.1
XS Rating Curve= 0 ,0
Exp/Cntr=0.3,0.1

Type RM Length L Ch R = 1 ,8283    ,600,600,600
BEGIN DESCRIPTION:
LIVE OAK BRANCH 12.0
END DESCRIPTION:
XS GIS Cut Line= 3
      3821097.34     10109211.47      3820186.13     10109485.05
       3819378.7     10110023.63
#Sta/Elev= 30
       0  160.48   119.9   159.2   250.1  155.91   290.4  156.41   323.1  154.47
   504.4  154.39   575.7  152.18   657.2  152.05   719.9  150.28   921.8  150.85
   951.4  146.72   954.3  143.23   975.3  149.55   984.3  149.37   990.3   150.9
  1020.4  151.12  1026.4   152.7  1033.5  151.76  1062.4  154.04  1098.5  154.43
  1164.6  152.18  1299.8  155.76  1489.1  154.61  1597.2  156.39  1747.4  158.17
  1819.5  157.36  1840.6  155.51  1870.6  157.67  1898.9  157.27    1922  160.72
#Mann= 5 ,-1 , 0
       0     .11       0   119.9     .17       0   921.8     .09       0
   990.3     .17       0  1597.2     .11       0
Bank Sta=921.8,990.3
XS Rating Curve= 0 ,0
Exp/Cntr=0.3,0.1