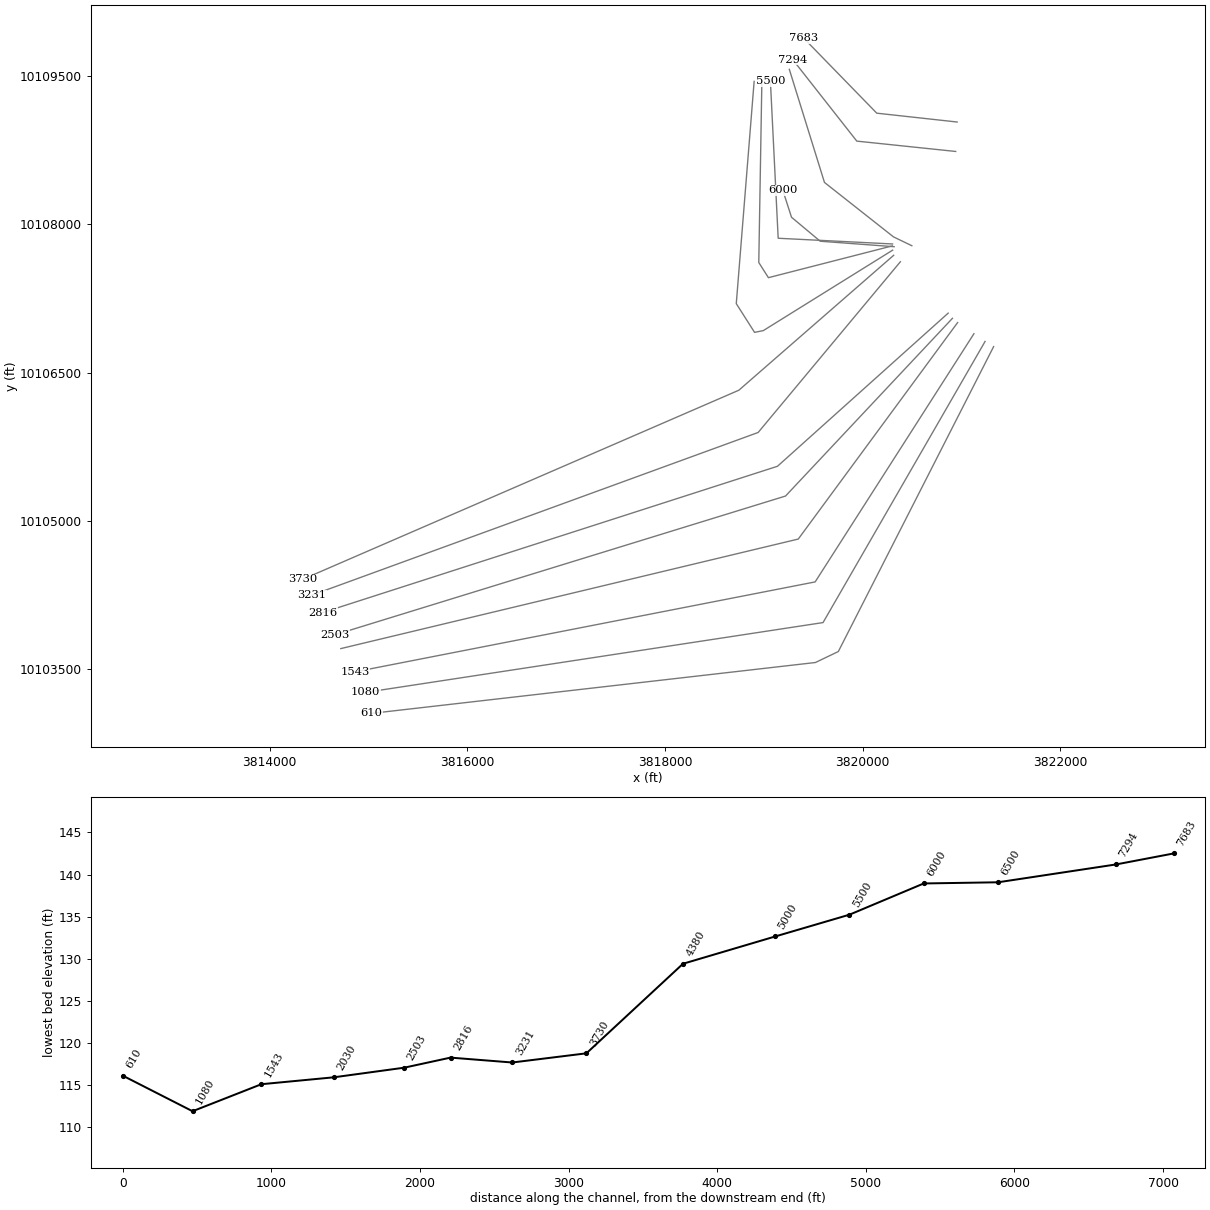
HEC-RAS study LIVE OAK BRANCH.prj: LIVE OAK BRANCH Base Level Engineering

--- LIVE OAK BRANCH.g01 (geometry) --- (continued)

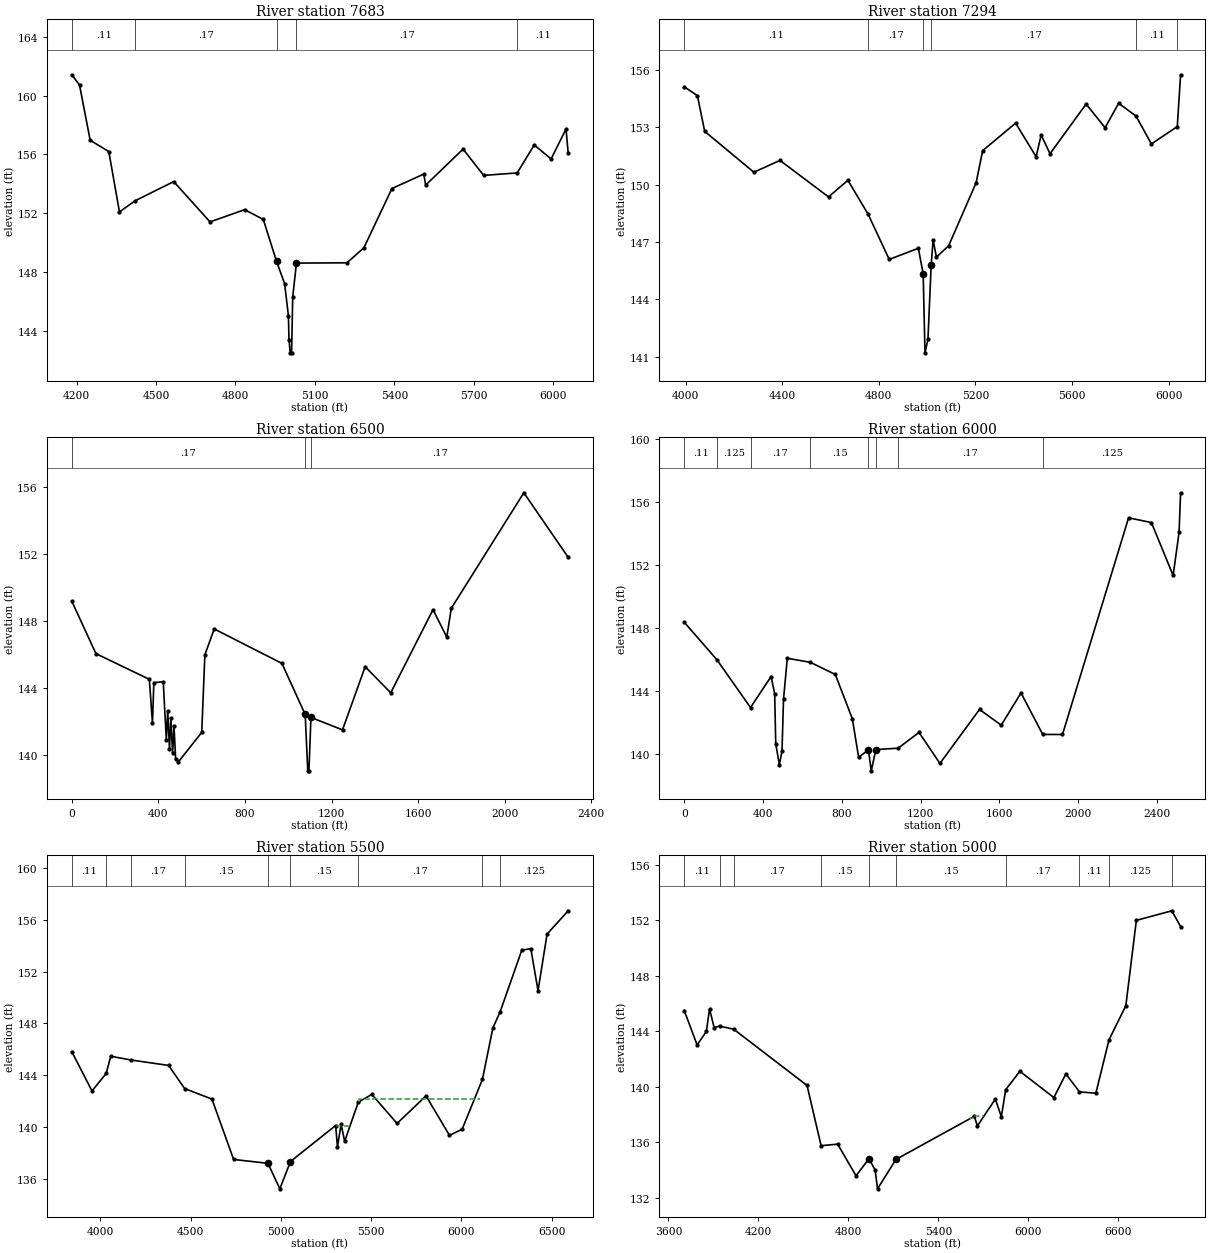
Type RM Length L Ch R = 1 ,7683    ,389,389,389
BEGIN DESCRIPTION:
LIVE OAK BRANCH 11.0
END DESCRIPTION:
XS GIS Cut Line= 3
       3820956.8      10109034.1      3820143.41     10109123.59
      3819406.29     10109880.74
#Sta/Elev= 30
  4181.7  161.41  4210.8  160.72  4251.1  156.96  4321.5  156.19  4361.7  152.09
  4421.4  152.85  4566.7  154.15  4703.8  151.41  4834.6  152.24    4905  151.58
  4955.3  148.72  4985.5  147.22    5000  145.04  5002.1  143.41  5006.7  142.51
  5011.9  142.51  5016.3  146.32  5030.4  148.61  5221.3  148.63  5285.1  149.65
  5391.1  153.68  5511.4  154.66  5518.4  153.91  5659.8  156.36  5737.5  154.57
  5864.2  154.74  5928.6  156.64  5992.2  155.69  6048.7  157.72  6056.7   156.1
#Mann= 5 ,-1 , 0
  4181.7     .11       0  4421.4     .17       0  4955.3     .09       0
  5030.4     .17       0  5864.2     .11       0
#XS Ineff= 2 ,-1
  4566.7  4341.6  154.15  4834.6  4566.7  152.24
Permanent Ineff=
       F       F
Bank Sta=4955.3,5030.4
XS Rating Curve= 0 ,0
Exp/Cntr=0.3,0.1

Type RM Length L Ch R = 1 ,7294    ,794,794,794
BEGIN DESCRIPTION:
LIVE OAK BRANCH 10.0
END DESCRIPTION:
XS GIS Cut Line= 3
      3820942.08      10108736.3      3819941.53     10108840.93
      3819292.93     10109666.15
#Sta/Elev= 30
    3994  155.12  4048.5  154.66  4078.7  152.79  4282.5  150.65  4390.4  151.27
  4591.5  149.36  4671.9  150.23  4756.1  148.44  4842.8  146.09  4963.5  146.67
  4983.6  145.33    4991   141.2  5003.3  141.91  5016.6  145.78  5024.7  147.11
  5038.3  146.21  5088.9   146.8  5202.8   150.1  5229.9  151.78  5366.4  153.22
  5451.3  151.46  5472.1   152.6  5508.9  151.62  5658.3  154.22  5736.9  152.98
    5793  154.26    5865  153.59  5928.7  152.13  6035.9  153.04  6049.6  155.75
#Mann= 6 ,-1 , 0
    3994     .11       0  4756.1     .17       0  4983.6     .09       0
  5016.6     .17       0    5865     .11       0  6035.9    .125       0
#XS Ineff= 2 , 0
       0  4671.9  150.23               0
Permanent Ineff=
       F       F
Bank Sta=4983.6,5016.6
XS Rating Curve= 0 ,0
Exp/Cntr=0.3,0.1

Type RM Length L Ch R = 1 ,6500    ,500,500,500
BEGIN DESCRIPTION:
LIVE OAK BRANCH 13.5
END DESCRIPTION:
XS GIS Cut Line= 4
      3820498.37     10107782.71      3820312.48      10107872.3
      3819614.37     10108422.97      3819258.81     10109567.09
#Sta/Elev= 30
       0  149.18   111.6  146.06   358.2  144.53   372.7  141.93     379  144.33
   422.4  144.39   436.8  140.92   443.2  142.67   451.3  140.36   457.6  142.24
   465.7  140.14   472.1  141.75   479.7  139.81   492.9  139.62   600.3  141.37
   614.8  145.99     658  147.53   970.7  145.48  1078.2  142.44  1090.1  139.08
  1095.5  139.08  1104.9  142.26  1250.6  141.52  1355.3  145.28  1473.5  143.73
  1668.8  148.68  1732.3  147.04  1753.2  148.76  2088.3  155.64  2293.1   151.8
#Mann= 3 , 0 , 0
       0     .17       0  1078.2     .09       0  1104.9     .17       0
Bank Sta=1078.2,1104.9
XS Rating Curve= 0 ,0
Exp/Cntr=0.3,0.1

Type RM Length L Ch R = 1 ,6000    ,500,500,500
BEGIN DESCRIPTION:
LIVE OAK BRANCH 12.5
END DESCRIPTION:
XS GIS Cut Line= 4
      3820319.42     10107772.71      3819571.19     10107828.14
       3819280.9     10108070.79       3819192.7     10108344.99
#Sta/Elev= 30
       0  148.38   166.1  145.99   336.4  142.96   440.9  144.93   459.1  143.83
   464.4  140.67     483  139.32   496.3  140.21     504  143.49   523.1  146.09
   640.7  145.83   766.8  145.06   853.3  142.25   885.3   139.8     935  140.27
   949.3  138.94   972.6  140.29  1085.9  140.38  1191.9  141.38  1297.9  139.41
  1498.8  142.84  1609.2  141.84  1709.5  143.89  1819.8  141.25  1920.1  141.25
  2255.6  155.01  2371.4  154.71  2481.7  151.35  2511.8  154.08  2519.6   156.6
#Mann= 8 ,-1 , 0
       0     .11       0   166.1    .125       0   336.4     .17       0
   640.7     .15       0     935     .09       0   972.6     .15       0
  1085.9     .17       0  1819.8    .125       0
Bank Sta=935,972.6
XS Rating Curve= 0 ,0
Exp/Cntr=0.3,0.1

Type RM Length L Ch R = 1 ,5500    ,500,500,500
BEGIN DESCRIPTION:
LIVE OAK BRANCH 11.5
END DESCRIPTION:
XS GIS Cut Line= 3
      3820303.34     10107800.44      3819146.18     10107858.18
      3819067.47     10109447.73
#Sta/Elev= 30
  3841.4  145.82  3953.2  142.79    4032  144.14  4057.2  145.47  4168.4  145.18
  4377.6  144.76  4466.7  142.97  4617.9  142.16    4738   137.5  4928.2   137.2
    4994  135.23    5053  137.34  5303.3  140.12  5313.3  138.45  5333.3  140.22
  5353.3   138.9  5428.7  141.92  5503.5  142.52  5643.7  140.28  5803.9  142.41
    5934  139.36  6004.1  139.83  6116.5  143.68  6174.3  147.65  6214.8  148.91
  6334.5  153.65  6384.6  153.78  6424.6  150.53  6474.7   154.9  6591.5   156.7
#Mann= 9 ,-1 , 0
  3841.4     .11       0    4032    .125       0  4168.4     .17       0
  4466.7     .15       0  4928.2     .09       0    5053     .15       0
  5428.7     .17       0  6116.5     .11       0  6214.8    .125       0
#XS Ineff= 2 ,-1
  5303.3  5383.4  140.12  5433.4  6104.2  142.14
Permanent Ineff=
       T       T
Bank Sta=4928.2,5053
XS Rating Curve= 0 ,0
Exp/Cntr=0.3,0.1

Type RM Length L Ch R = 1 ,5000    ,620,620,620
BEGIN DESCRIPTION:
LIVE OAK BRANCH 10.5
END DESCRIPTION:
XS GIS Cut Line= 4
      3820301.11     10107781.01       3819047.4     10107459.42
      3818949.89     10107612.76      3818981.14     10109446.07
#Sta/Elev= 30
  3705.7  145.49  3791.7  143.01  3853.6  143.99  3874.2  145.61  3905.2  144.26
  3941.5  144.37  4035.9  144.14  4524.6  140.09  4618.2  135.75  4728.8  135.86
  4851.2  133.58  4937.9  134.82  4978.9  133.98  4994.5  132.64  5117.4  134.76
  5640.1  137.87  5660.1  137.17  5780.1  139.11  5820.1  137.84  5849.1  139.79
  5943.7  141.11  6170.2  139.22  6250.2  140.92  6341.2  139.63  6450.2  139.53
    6538  143.38  6650.2  145.84  6720.3  151.99  6956.8  152.68  7015.3  151.54
#Mann= 10 ,-1 , 0
  3705.7     .11       0  3941.5    .125       0  4035.9     .17       0
  4618.2     .15       0  4937.9     .09       0  5117.4     .15       0
  5849.1     .17       0  6341.2     .11       0    6538    .125       0
  6956.8     .11       0
#XS Ineff= 4 ,-1
  5610.1  5640.1  137.72  5640.1  5700.1  137.87  5730.1  5750.1  138.24
  5780.1  5840.1  139.11
Permanent Ineff=
       F       F       F       F
Bank Sta=4937.9,5117.4
XS Rating Curve= 0 ,0
Exp/Cntr=0.3,0.1

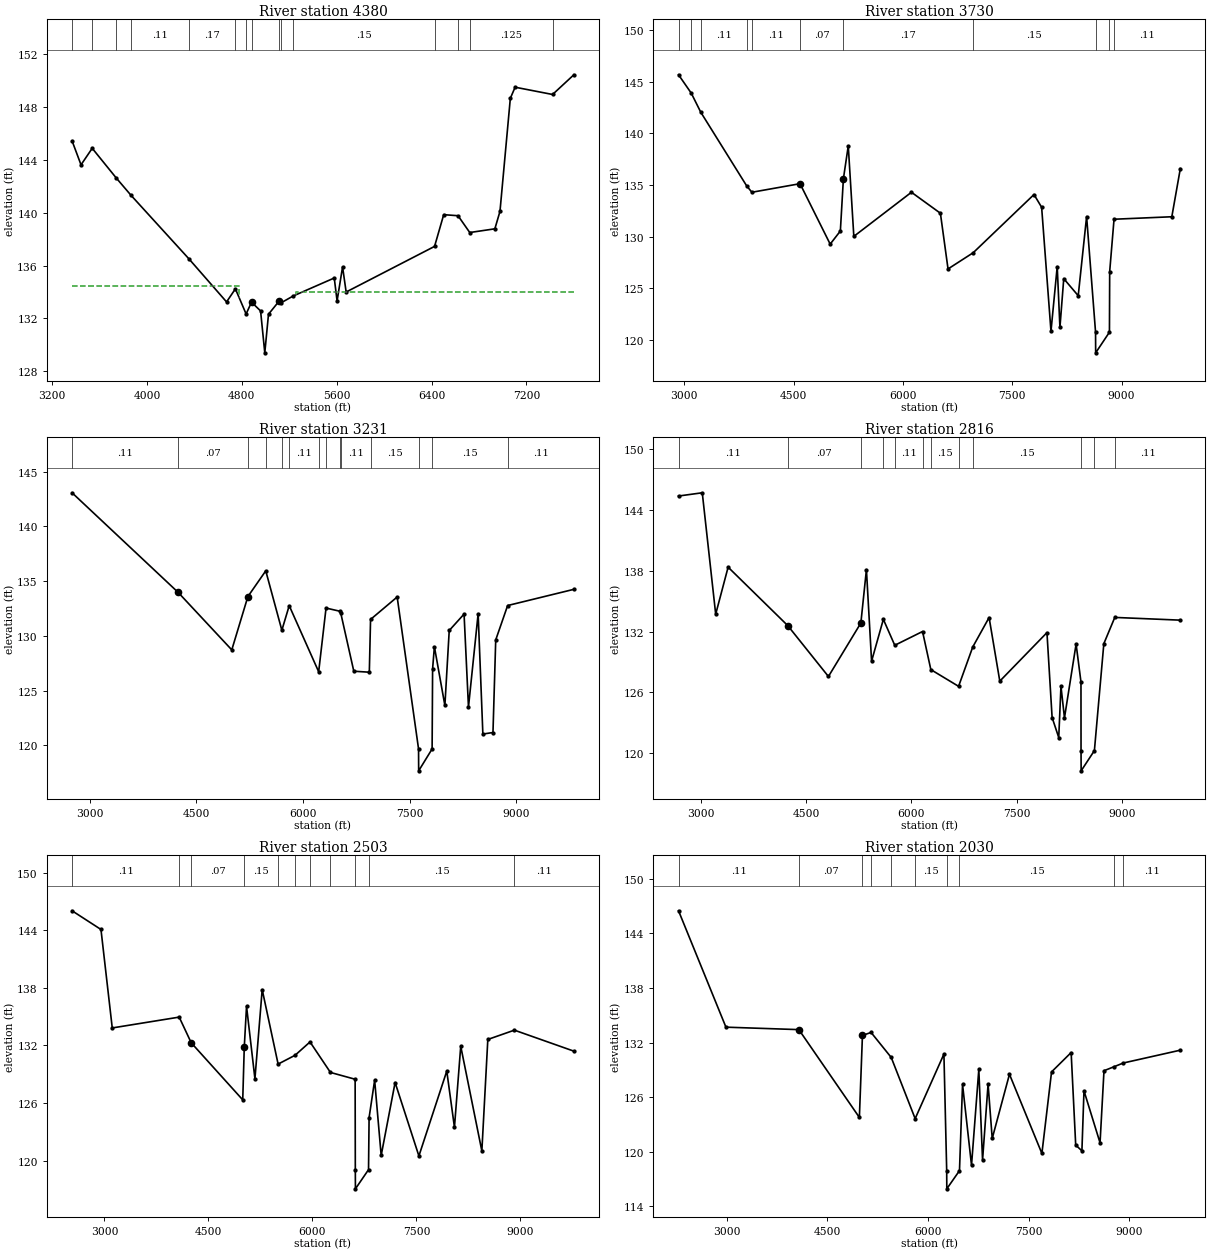
Type RM Length L Ch R = 1 ,4380    ,650,650,650
BEGIN DESCRIPTION:
LIVE OAK BRANCH 9.0
END DESCRIPTION:
XS GIS Cut Line= 5
      3820304.07     10107737.78       3818995.9     10106924.05
      3818907.34     10106905.96      3818722.19     10107196.75
      3818902.93     10109445.07
#Sta/Elev= 30
    3369  145.43  3444.5  143.62  3538.9  144.87    3742  142.62  3865.5  141.32
  4353.3  136.52  4671.8  133.25  4746.2  134.24  4836.6  132.34  4882.4  133.23
  4958.6  132.57  4994.1   129.4  5025.4  132.32  5112.8  133.29  5134.6   133.2
  5233.7   133.7  5579.8  135.06  5603.7  133.33    5650   135.9  5680.1     134
  6425.7  137.45  6502.8  139.85  6623.6  139.77  6722.5   138.5  6934.2  138.78
  6977.3   140.1  7064.6  148.65  7104.9  149.49  7420.8  148.94  7600.3  150.43
#Mann= 15 ,-1 , 0
    3369     .11       0  3538.9    .125       0    3742     .17       0
  3865.5     .11       0  4353.3     .17       0  4746.2     .11       0
  4836.6     .11       0  4882.4     .07       0  5112.8     .11       0
  5134.6     .11       0  5233.7     .15       0  6425.7     .17       0
  6623.6     .11       0  6722.5    .125       0  7420.8     .17       0
#XS Ineff= 2 , 0
       0  4778.4  134.43  5255.7       0  134.01
Permanent Ineff=
       F       F
Bank Sta=4882.4,5112.8
XS Rating Curve= 0 ,0
Exp/Cntr=0.3,0.1

Type RM Length L Ch R = 1 ,3730    ,499,499,499
BEGIN DESCRIPTION:
LIVE OAK BRANCH 8.0
END DESCRIPTION:
XS GIS Cut Line= 3
      3820314.49      10107685.7      3818748.34     10106320.87
      3814338.31     10104408.54
#Sta/Elev= 30
  2922.6  145.67  3096.4   143.9  3228.2  142.04  3856.3  134.93  3928.9   134.3
  4589.4  135.13    5003  129.28  5142.7  130.55  5184.2   135.6  5251.2  138.79
  5327.5  130.03  6117.9   134.3  6515.2  132.27  6619.9  126.88  6965.4  128.45
  7799.2  134.08    7904  132.85  8032.2  120.85  8117.8  127.11    8155  121.22
  8207.4  125.94    8406  124.29  8521.1  131.95  8643.8  120.76  8645.3  118.76
  8834.4  120.76  8837.7  126.63  8897.4  131.69  9690.1  131.93  9806.8  136.59
#Mann= 11 ,-1 , 0
  2922.6     .11       0  3096.4    .125       0  3228.2     .11       0
  3856.3     .17       0  3928.9     .11       0  4589.4     .07       0
  5184.2     .17       0  6965.4     .15       0  8643.8     .11       0
  8834.4     .15       0  8897.4     .11       0
Bank Sta=4589.4,5184.2
XS Rating Curve= 0 ,0
Exp/Cntr=0.3,0.1

Type RM Length L Ch R = 1 ,3231    ,415,415,415
BEGIN DESCRIPTION:
LIVE OAK BRANCH 7.0
END DESCRIPTION:
XS GIS Cut Line= 3
      3820382.18     10107620.35      3818943.42     10105893.34
      3814425.51     10104245.92
#Sta/Elev= 30
  2752.2  143.07  4242.5  133.98  4998.2  128.72  5224.8  133.59  5476.1  135.94
  5702.4  130.51  5805.9  132.76  6220.2  126.72  6323.8  132.54  6517.7  132.25
  6529.1  132.13  6714.3  126.77  6932.5  126.68  6949.8   131.5  7324.1  133.55
  7624.9  119.67  7626.4  117.67  7815.5  119.67  7822.4  126.99  7847.6  129.01
  7995.1  123.64  8056.2  130.49  8264.9  131.99  8326.9   123.5  8462.8  132.03
  8529.3  121.03  8671.4  121.17  8710.1  129.63  8877.6  132.77  9808.9  134.25
#Mann= 14 ,-1 , 0
  2752.2     .11       0  4242.5     .07       0  5224.8     .17       0
  5476.1    .125       0  5702.4     .15       0  5805.9     .11       0
  6220.2     .15       0  6323.8     .17       0  6517.7     .15       0
  6529.1     .11       0  6949.8     .15       0  7624.9     .12       0
  7815.5     .15       0  8877.6     .11       0
Bank Sta=4242.5,5224.8
XS Rating Curve= 0 ,0
Exp/Cntr=0.3,0.1

Type RM Length L Ch R = 1 ,2816    ,313,313,313
BEGIN DESCRIPTION:
LIVE OAK BRANCH 6.0
END DESCRIPTION:
XS GIS Cut Line= 3
      3820866.03     10107100.73      3819138.95     10105551.36
      3814537.88      10104071.2
#Sta/Elev= 30
  2679.8  145.37  3018.1  145.69  3209.5  133.71  3386.6  138.35  4235.8  132.59
  4816.7  127.56    5279  132.84  5358.3  138.11  5431.8  129.07  5599.6   133.2
  5762.4  130.64  6158.4     132  6276.6  128.24  6672.1  126.59    6874  130.47
  7107.2  133.38  7259.7   127.1    7932  131.89  8005.5  123.51    8100  121.54
  8131.6  126.59  8181.8  123.48  8347.4  130.76  8416.9  127.02  8417.8  120.25
  8419.3  118.25  8608.4  120.25  8742.9   130.8  8898.9  133.39  9833.3  133.12
#Mann= 12 ,-1 , 0
  2679.8     .11       0  4235.8     .07       0    5279     .15       0
  5599.6    .125       0  5762.4     .11       0  6158.4     .17       0
  6276.6     .15       0  6672.1     .11       0    6874     .15       0
  8417.8     .12       0  8608.4     .15       0  8898.9     .11       0
Bank Sta=4235.8,5279
XS Rating Curve= 0 ,0
Exp/Cntr=0.3,0.1

Type RM Length L Ch R = 1 ,2503    ,473,473,473
BEGIN DESCRIPTION:
LIVE OAK BRANCH 5.0
END DESCRIPTION:
XS GIS Cut Line= 3
      3820909.39     10107048.61      3819220.56      10105250.3
      3814662.06     10103846.32
#Sta/Elev= 30
    2533  146.05  2949.8   144.1  3112.5  133.83  4077.9  134.96  4251.5  132.28
  4994.4  126.33  5016.4  131.81  5049.1  136.09  5170.2  128.53  5274.9  137.83
  5504.5  130.06  5749.1  130.98  5964.6  132.37  6259.2  129.19  6615.3  128.48
    6618  119.05  6619.5  117.05  6808.6  119.05  6816.6  124.47  6896.7  128.38
  6990.9  120.53  7191.8  128.14    7535  120.48    7937  129.33  8047.7  123.47
  8138.3  131.92  8442.9     121    8529  132.63    8912   133.6  9769.8  131.41
#Mann= 11 ,-1 , 0
    2533     .11       0  4077.9     .17       0  4251.5     .07       0
  5016.4     .15       0  5504.5     .15       0  5749.1     .11       0
  5964.6     .17       0  6259.2     .15       0    6618     .12       0
  6808.6     .15       0    8912     .11       0
Bank Sta=4251.5,5016.4
XS Rating Curve= 0 ,0
Exp/Cntr=0.3,0.1

Type RM Length L Ch R = 1 ,2030    ,487,487,487
BEGIN DESCRIPTION:
LIVE OAK BRANCH 4.0
END DESCRIPTION:
XS GIS Cut Line= 3
      3820961.51     10107005.26      3819349.37     10104815.13
       3814721.5     10103706.93
#Sta/Elev= 30
  2280.5  146.49    2987  133.69  4073.8  133.42  4975.6  123.76 5021.27  132.78
  5149.9  133.11  5450.2  130.36  5806.8  123.63  6235.5  130.73  6276.9  117.91
  6278.4  115.91  6467.5  117.91  6513.1  127.39  6646.8   118.5  6755.6  129.04
  6811.3  119.07  6893.6  127.42  6955.3  121.45  7212.3  128.51  7695.6   119.8
  7839.6  128.77  8131.6   130.9  8199.5  120.72    8292  120.09  8322.9  126.69
  8562.3  120.97  8621.1   128.9  8767.6  129.33  8909.2  129.75  9758.7  131.16
#Mann= 10 ,-1 , 0
  2280.5     .11       0  4073.8     .07       0 5021.27     .15       0
  5149.9     .15       0  5450.2     .11       0  5806.8     .15       0
  6276.9     .11       0  6467.5     .15       0  8767.6     .17       0
  8909.2     .11       0
Bank Sta=4073.8,5021.27
XS Rating Curve= 0 ,0
Exp/Cntr=0.3,0.1

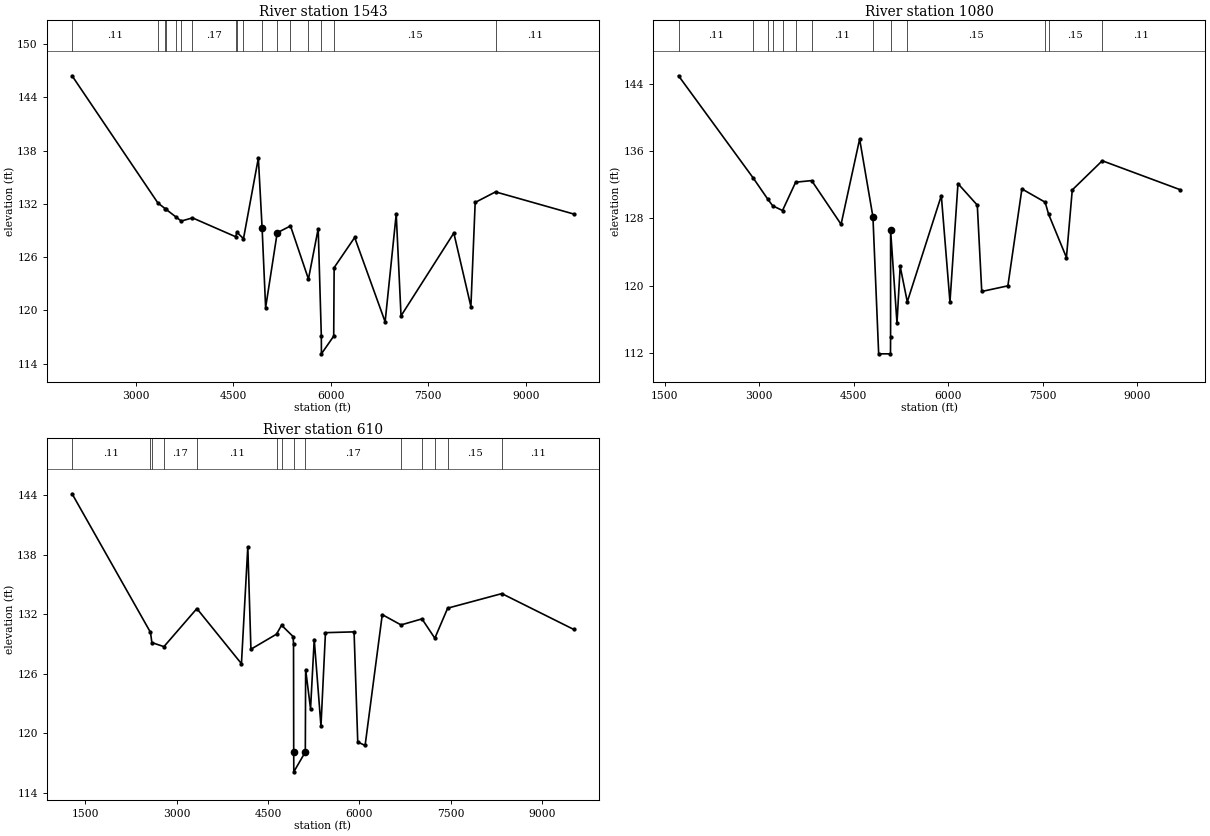
Type RM Length L Ch R = 1 ,1543    ,463,463,463
BEGIN DESCRIPTION:
LIVE OAK BRANCH 3.0
END DESCRIPTION:
XS GIS Cut Line= 3
      3821126.43     10106892.39      3819520.26     10104381.58
      3814867.79     10103472.25
#Sta/Elev= 30
  2019.4  146.44  3340.9  132.09  3452.5  131.46  3460.6  131.41  3625.3  130.48
  3699.9  130.06  3872.4  130.42  4537.4  128.29  4554.7   128.8  4657.1  128.08
  4885.8  137.16  4943.3  129.31  4997.6   120.3  5175.8  128.74  5380.3  129.51
  5656.5  123.52  5806.5   129.2  5854.7  117.09  5856.2  115.09  6045.3  117.09
  6051.9  124.81  6367.8  128.21  6836.5   118.7  7007.2  130.84  7081.1  119.37
  7893.5  128.71  8156.3  120.42  8222.2  132.16  8535.4  133.35  9740.5  130.85
#Mann= 17 ,-1 , 0
  2019.4     .11       0  3340.9     .17       0  3452.5     .11       0
  3460.6     .17       0  3625.3     .11       0  3699.9     .15       0
  3872.4     .17       0  4537.4     .15       0  4554.7     .17       0
  4657.1     .11       0  4943.3     .07       0  5175.8     .17       0
  5380.3     .11       0  5656.5     .15       0  5854.7     .11       0
  6045.3     .15       0  8535.4     .11       0
Bank Sta=4943.3,5175.8
XS Rating Curve= 0 ,0
Exp/Cntr=0.3,0.1

Type RM Length L Ch R = 1 ,1080    ,470,470,470
BEGIN DESCRIPTION:
LIVE OAK BRANCH 2.0
END DESCRIPTION:
XS GIS Cut Line= 3
      3821239.26     10106814.24      3819600.04     10103970.11
       3814972.4     10103263.98
#Sta/Elev= 30
  1717.3  144.96  2903.4  132.79  3133.8  130.28  3212.1  129.49  3367.6  128.93
  3576.1   132.3  3830.1  132.49    4297  127.29  4591.5  137.43  4802.7  128.17
  4893.6  111.88  5081.2  111.88  5082.7  113.88  5083.1  126.57  5184.3  115.53
  5234.9  122.28    5348  118.07    5888   130.7  6025.1  118.05  6152.1  132.13
  6458.9  129.57  6529.7   119.3  6944.3  119.97    7167   131.5  7535.7  129.92
  7590.5  128.49  7873.7  123.34  7966.1  131.38  8442.2  134.85  9681.2   131.4
#Mann= 13 ,-1 , 0
  1717.3     .11       0  2903.4     .17       0  3133.8     .15       0
  3212.1     .17       0  3367.6     .15       0  3576.1     .17       0
  3830.1     .11       0  4802.7     .07       0  5083.1     .12       0
    5348     .15       0  7535.7     .17       0  7590.5     .15       0
  8442.2     .11       0
Bank Sta=4802.7,5083.1
XS Rating Curve= 0 ,0
Exp/Cntr=0.3,0.1

Type RM Length L Ch R = 1 ,610     ,0,0,0
BEGIN DESCRIPTION:
LIVE OAK BRANCH 2.5
END DESCRIPTION:
XS GIS Cut Line= 4
      3821325.87     10106762.26      3819754.65     10103677.16
      3819522.95     10103566.11      3815032.64     10103051.54
#Sta/Elev= 30
  1280.9  144.16  2568.5  130.18  2591.2  129.15  2789.2  128.74  3330.1  132.58
  4061.8  127.02  4166.3  138.81  4217.5  128.48  4637.9     130  4720.4   130.9
  4909.5  129.76  4916.9  129.04  4919.9  118.11  4921.4  116.11  5110.5  118.11
  5115.9  126.42  5196.4  122.47  5256.8  129.46  5367.5  120.73  5441.3  130.15
    5911  130.23  5971.5  119.12  6092.2  118.77    6374  131.97  6681.9  130.93
  7025.8  131.54    7237  129.59  7447.5  132.62  8337.3  134.09  9519.7  130.47
#Mann= 14 ,-1 , 0
  1280.9     .11       0  2568.5     .17       0  2591.2     .15       0
  2789.2     .17       0  3330.1     .11       0  4637.9     .17       0
  4720.4     .11       0  4919.9     .09       0  5110.5     .17       0
  6681.9     .11       0  7025.8     .15       0    7237     .11       0
  7447.5     .15       0  8337.3     .11       0
Bank Sta=4919.9,5110.5
XS Rating Curve= 0 ,0
Exp/Cntr=0.3,0.1

Chan Stop Cuts=-1
Use User Specified Reach Order=0
Composite Channel Slope=5