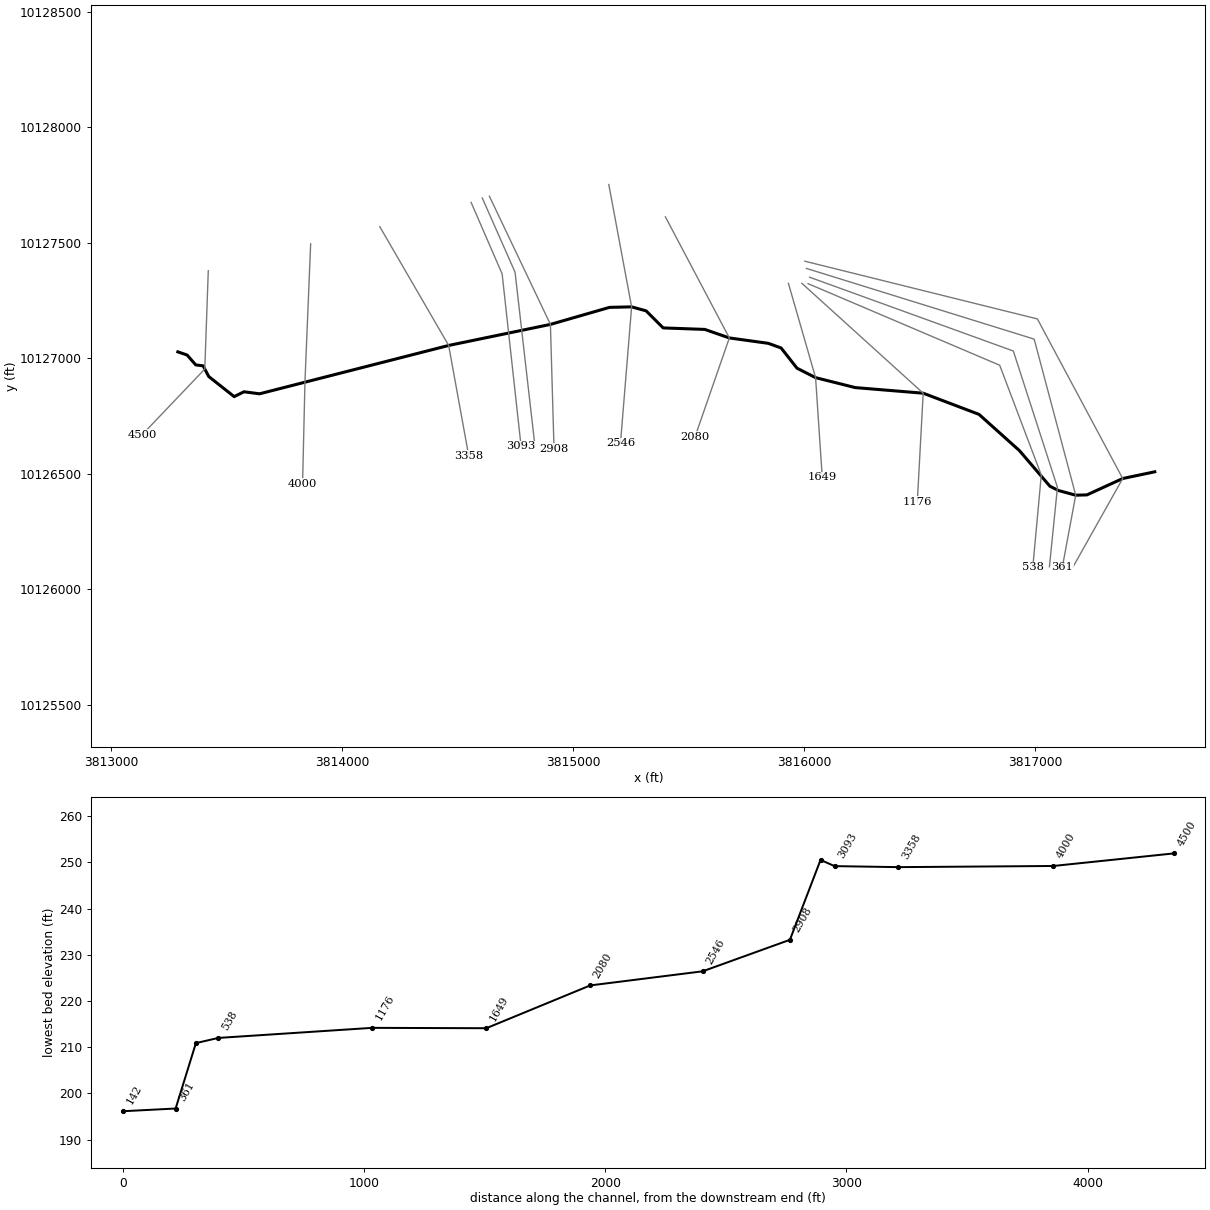
--- LOWER TRIB TO WF OF WHT OAK CRK.prj (project) ---

Proj Title=LOWER TRIB TO WF OF WHT OAK CRK Base Level Engineering
Current Plan=p01
Default Exp/Contr=0.3,0.1
English Units
Geom File=g01
Flow File=f01
Plan File=p01
Y Axis Title=Elevation
X Axis Title(PF)=Main Channel Distance
X Axis Title(XS)=Station
BEGIN DESCRIPTION:
LOWER TRIB TO WF OF WHT OAK CRK
END DESCRIPTION:
DSS Export Rating Curves= 0
DSS Export Rating Curve Sorted= 0
DSS Export Volume Flow Curves= 0
DXF OffsetX= 0
DXF OffsetY= 0
DXF ScaleX= 1
DXF ScaleY= 10

--- LOWER TRIB TO WF OF WHT OAK CRK.p01 (plan) ---

Plan Title=Multiple Run
Program Version=4.10
Short Identifier=Multiple
Geom File=g01
Flow File=f01
Subcritical Flow
K Sum by GR= 0
Std Step Tol= 0.01
Critical Tol= 0.01
Num of Std Step Trials= 20
Max Error Tol= 0.3
Flow Tol Ratio= 0.001
Split Flow NTrial= 30
Split Flow Tol= 0.02
Split Flow Ratio= 0.02
Log Output Level= 0
Friction Slope Method= 1
Unsteady Friction Slope Method= 2
Unsteady Bridges Friction Slope Method= 1
Parabolic Critical Depth
Global Vel Dist= 1 , 1 , 1
Global Log Level= 0
CheckData=True
Encroach Param=-1 ,0,0, 0
BEGIN DESCRIPTION:
Multiple Run
END DESCRIPTION:
Computation Interval=1HOUR
Output Interval=1HOUR
Run HTab= 0
Run UNet= 0
Run PostProcess= 0
Run WQNet= 0
UNET Theta= 1
UNET Theta Warmup= 1
UNET ZTol= 0.02
UNET ZSATol= 0.05
UNET MxIter= 20
UNET MaxInSteps= 0
UNET DtIC= 0
UNET DtMin= 0
UNET MaxCRTS= 20
UNET WFStab= 2
UNET SFStab= 1
UNET WFX= 1
UNET SFX= 1
UNET DSS MLevel= 4
UNET DZMax Abort= 100
UNET Convert EG Bridges= 0
UNET Use Existing IB Tables=-1
UNET Froude Reduction=False
UNET Froude Limit= 1
UNET Froude Power= 10
UNET Time Slicing=0,0, 5
UNET Junction Losses=0
Instantaneous Interval=1HOUR
Write IC File= 0
Write IC File at Sim End=0
Echo Input=False
Echo Parameters=False
Echo Output=False
Write Detailed= 0
WQ AD Non Conservative
WQ ULTIMATE=-1
WQ Max Comp Step=1HOUR
WQ Output Interval=15MIN
WQ Output Selected Increments= 0
WQ Output face flow=0
WQ Output face velocity=0
WQ Output face area=0
WQ Output face dispersion=0
WQ Output cell volume=0
WQ Output cell surface area=0
WQ Output cell continuity=0
WQ Output cumulative cell continuity=0
WQ Output face conc=0
WQ Output face dconc_dx=0
WQ Output face courant=0
WQ Output face peclet=0
WQ Output face adv mass=0
WQ Output face disp mass=0
WQ Output cell mass=0
WQ Output cell source sink temp=0
WQ Output cell source sink nsm=0
WQ Output MaxMinRange=-1
WQ Daily Max Min Mean=-1
WQ Daily Range=0
WQ Daily Time=0
WQ Create Restart=0
WQ Fixed Restart=0
WQ System Summary=0
WQ Use Fixed Temperature=0
Sorting and Armoring Iterations= 10
XS Update Threshold= 0.02
Hydraulics Update Threshold= 0.02
Energy Slope Method= 1
Volume Change Method= 0
XS Weighting Method= 0
Number of US Weighted Cross Sections= 1
Number of DS Weighted Cross Sections= 1
Upstream XS Weight=0.25
Main XS Weight=0.5
Downstream XS Weight=0.25
Number of DS XS's Weighted with US Boundary= 1
Upstream Boundary Weight= 1
Weight of XSs Associated with US Boundary= 0
Number of US XS's Weighted with DS Boundary= 1
Downstream Boundary Weight= 0.5
Weight of XSs Associated with DS Boundary= 0.5
Sediment Output Level= 4
Mass or Volume Output= 0
Output Increment Type= 1
Profile and TS Output Increment= 10
XS Output Flag= 0
XS Output Increment= 10
Disregard all LS=0
Disregard all Conn=0
Disregard all Breaches=0
Disregard all Pumps=0

--- LOWER TRIB TO WF OF WHT OAK CRK.f01 (steady flow) ---

Flow Title=Multiple
Program Version=4.10
Number of Profiles= 7
Profile Names=10-year,25-year,50-year,1pct_min,100-year,1pct_plu,500-year
River Rch & RM=LOWER TRIB TO WF,Reach-1         ,4500
     246     312     404     172     520    1570     893
River Rch & RM=LOWER TRIB TO WF,Reach-1         ,4000
     558     752    1013     451    1361    4110    2530
Boundary for River Rch & Prof#=LOWER TRIB TO WF,Reach-1         , 1
Up Type= 0
Dn Type= 3
Dn Slope=0.003
Boundary for River Rch & Prof#=LOWER TRIB TO WF,Reach-1         , 2
Up Type= 0
Dn Type= 3
Dn Slope=0.003
Boundary for River Rch & Prof#=LOWER TRIB TO WF,Reach-1         , 3
Up Type= 0
Dn Type= 3
Dn Slope=0.003
Boundary for River Rch & Prof#=LOWER TRIB TO WF,Reach-1         , 4
Up Type= 0
Dn Type= 3
Dn Slope=0.003
Boundary for River Rch & Prof#=LOWER TRIB TO WF,Reach-1         , 5
Up Type= 0
Dn Type= 3
Dn Slope=0.003
Boundary for River Rch & Prof#=LOWER TRIB TO WF,Reach-1         , 6
Up Type= 0
Dn Type= 3
Dn Slope=0.003
Boundary for River Rch & Prof#=LOWER TRIB TO WF,Reach-1         , 7
Up Type= 0
Dn Type= 3
Dn Slope=0.003
DSS Import GetInterval= 0
DSS Import GetPeak= 0
DSS Import FillOption= 0

--- LOWER TRIB TO WF OF WHT OAK CRK.g01 (geometry) ---

Geom Title=Existing Conditions
Program Version=4.10

River Reach=LOWER TRIB TO WF,Reach-1
Reach XY= 30
      3813287.82     10127027.12      3813328.01     10127013.46
      3813365.38     10126970.58      3813397.25     10126966.65
      3813421.72     10126920.33      3813531.79     10126833.29
      3813574.25     10126854.31      3813641.55     10126845.48
       3814460.6     10127054.85      3814901.14       10127146.
      3815157.21     10127219.78       3815252.7     10127221.95
      3815315.63     10127204.59      3815389.42     10127130.81
      3815569.54      10127124.3      3815675.88      10127087.4
      3815844.48     10127064.08      3815900.04     10127043.94
      3815968.79     10126956.44      3816049.34     10126915.47
      3816220.87     10126872.42      3816515.31     10126848.11
      3816756.98     10126756.44      3816931.98      10126599.5
      3817063.93     10126445.33      3817101.43     10126426.58
      3817175.73     10126406.44      3817224.34     10126407.83
       3817379.2     10126478.67      3817518.05     10126507.81

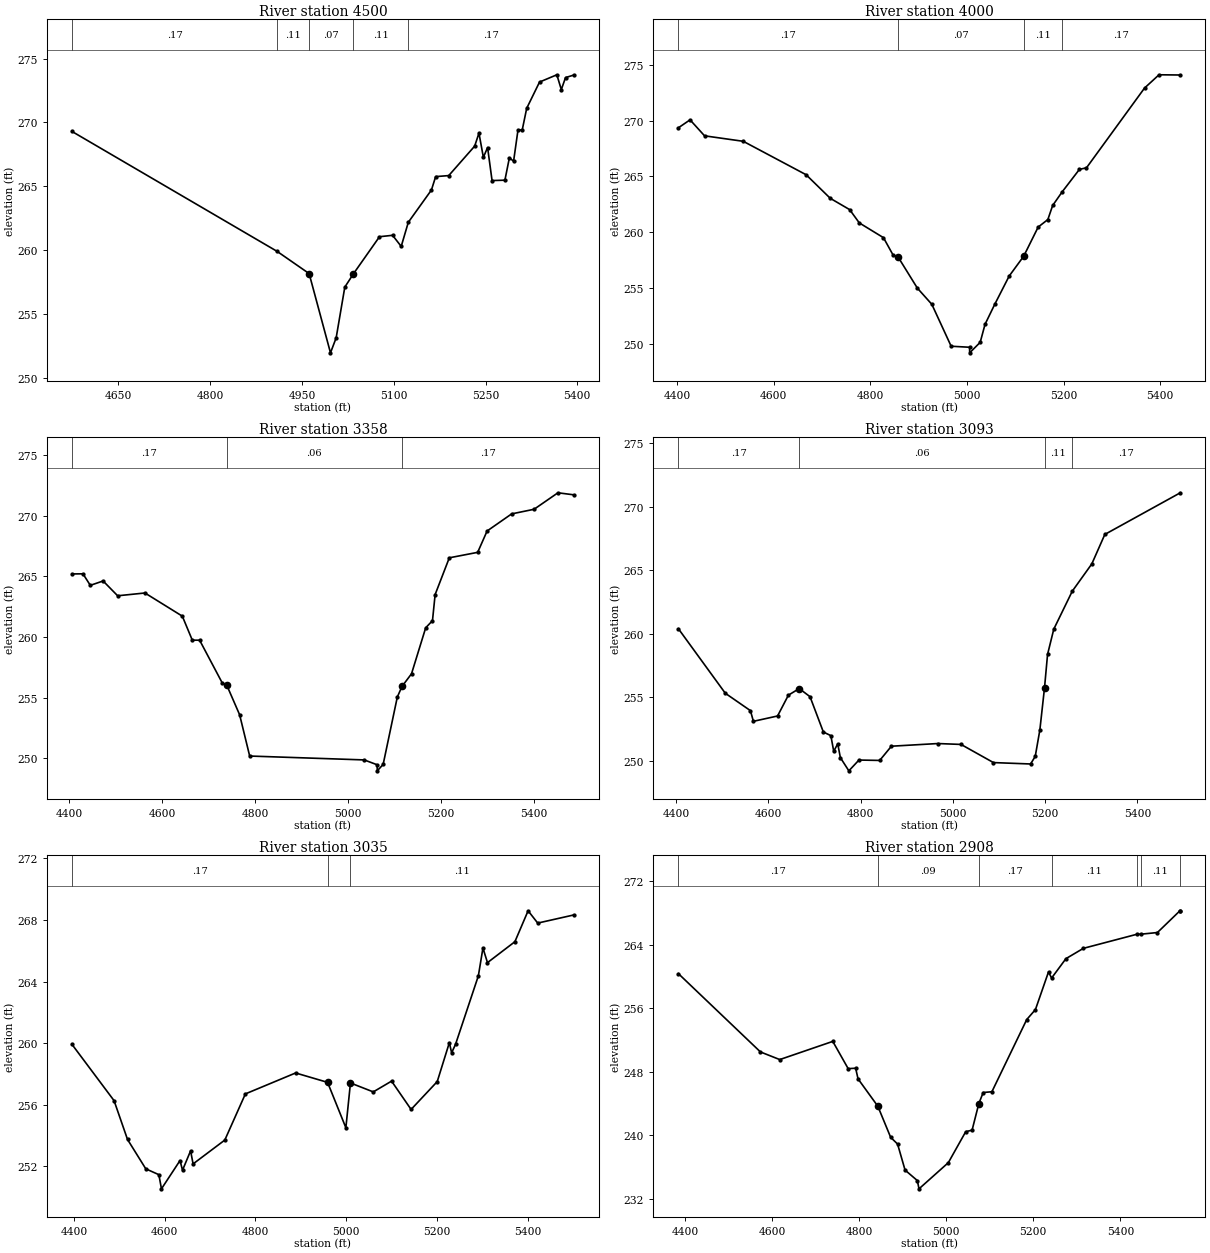
Type RM Length L Ch R = 1 ,4500    ,500,500,500
BEGIN DESCRIPTION:
LOWER TRIB TO WF OF WHT OAK CRK 9.0
END DESCRIPTION:
XS GIS Cut Line= 3
      3813419.69     10127378.51      3813404.58     10126952.78
      3813132.39     10126667.35
#Sta/Elev= 30
    4574  269.29  4909.4  259.89  4961.7  258.15  4996.6  251.94  5005.9  253.12
    5020  257.09  5034.2  258.14  5076.7  261.04  5098.1  261.15  5112.2  260.28
  5123.8  262.17  5161.6   264.7  5168.5  265.75  5189.9  265.83  5232.3  268.14
  5239.3  269.16  5246.5  267.26  5253.4  268.03  5260.7  265.44  5281.7  265.47
    5289  267.22  5295.9  266.96  5303.1  269.41    5310   269.4  5317.3   271.1
  5338.3  273.16  5366.6  273.73  5373.9  272.57  5380.8  273.51  5394.4  273.71
#Mann= 5 ,-1 , 0
    4574     .17       0  4909.4     .11       0  4961.7     .07       0
  5034.2     .11       0  5123.8     .17       0
Bank Sta=4961.7,5034.2
XS Rating Curve= 0 ,0
Exp/Cntr=0.3,0.1

Type RM Length L Ch R = 1 ,4000    ,642,642,642
BEGIN DESCRIPTION:
LOWER TRIB TO WF OF WHT OAK CRK 8.0
END DESCRIPTION:
XS GIS Cut Line= 3
      3813862.98     10127495.12       3813838.3     10126898.43
      3813827.98     10126456.95
#Sta/Elev= 30
  4402.8  269.35  4426.9  270.06  4456.9  268.63    4537  268.14  4667.1  265.15
  4717.1  263.04  4757.2  262.03  4777.2  260.84  4827.2  259.52  4847.2  257.96
  4857.2  257.81  4897.3  255.01  4927.3  253.56  4967.3  249.81  5005.4  249.72
  5005.6  249.22  5027.4  250.16  5037.4  251.77  5057.4  253.55  5087.4  256.09
  5117.4  257.86  5147.4  260.47  5167.4  261.14  5177.4   262.4  5197.1  263.62
  5232.8  265.63  5247.4  265.77  5367.5   272.9  5397.5  274.09  5441.6  274.07
#Mann= 4 ,-1 , 0
  4402.8     .17       0  4857.2     .07       0  5117.4     .11       0
  5197.1     .17       0
Bank Sta=4857.2,5117.4
XS Rating Curve= 0 ,0
Exp/Cntr=0.3,0.1

Type RM Length L Ch R = 1 ,3358    ,265,265,265
BEGIN DESCRIPTION:
LOWER TRIB TO WF OF WHT OAK CRK 7.0
END DESCRIPTION:
XS GIS Cut Line= 3
      3814162.38     10127569.03       3814460.6     10127054.85
      3814547.34     10126577.47
#Sta/Elev= 30
  4405.6   265.2  4429.3  265.21  4445.1  264.26  4472.6  264.62  4503.9   263.4
  4562.6  263.63    4643  261.72  4664.5  259.74  4680.2  259.74  4729.1   256.2
  4738.5  256.04  4766.3  253.59  4787.9  250.19  5034.3  249.87  5062.1  249.47
  5062.4  248.97    5075   249.5  5105.5  255.06  5115.6  255.93    5136  256.97
  5166.5  260.76  5181.1  261.35  5186.8   263.5  5217.3  266.53  5278.3  266.98
  5298.6  268.74  5351.4  270.15  5399.6  270.53    5451  271.89  5485.2  271.72
#Mann= 3 , 0 , 0
  4405.6     .17       0  4738.5     .06       0  5115.6     .17       0
Bank Sta=4738.5,5115.6
XS Rating Curve= 0 ,0
Exp/Cntr=0.3,0.1

Type RM Length L Ch R = 1 ,3093    ,58,58,58
BEGIN DESCRIPTION:
Mapping XS 01b009ae
END DESCRIPTION:
XS GIS Cut Line= 3
      3814557.72     10127674.35      3814692.07      10127364.6
      3814774.16     10126618.33
#Sta/Elev= 30
  4404.8  260.38  4506.5   255.3    4561  253.93  4567.4  253.09  4619.8  253.51
  4643.3  255.15  4666.8  255.67  4690.2  255.03  4719.1  252.25  4735.4  251.96
  4741.6  250.73  4750.3  251.32    4756  250.23  4774.4  249.19  4796.3  250.04
  4841.3  250.01  4866.7  251.13  4967.3  251.34  5017.6  251.27    5088  249.84
  5168.5  249.73  5178.6  250.33  5188.6  252.41  5198.7  255.73  5205.3  258.36
  5218.8  260.35  5258.9  263.34  5301.3  265.49  5329.5  267.81  5493.2  271.09
#Mann= 4 ,-1 , 0
  4404.8     .17       0  4666.8     .06       0  5198.7     .11       0
  5258.9     .17       0
#XS Ineff= 2 , 0
       0  4666.8  255.67               0
Permanent Ineff=
       F       F
Bank Sta=4666.8,5198.7
XS Rating Curve= 0 ,0
Exp/Cntr=0.3,0.1

Type RM Length L Ch R = 1 ,3035    ,127,127,127
BEGIN DESCRIPTION:
Mapping XS a5fa277b
END DESCRIPTION:
XS GIS Cut Line= 3
      3814606.23     10127693.01      3814748.04     10127372.07
      3814833.87     10126622.04
#Sta/Elev= 30
  4395.7  259.92  4488.5  256.26  4518.1  253.74  4558.4  251.83  4587.2  251.45
  4592.9  250.53  4633.8  252.37  4639.3  251.74  4657.1     253  4662.6  252.15
  4732.5   253.7  4777.8   256.7  4888.5  258.06  4958.9  257.45  4999.2   254.5
  5009.3  257.41  5059.6  256.83  5099.9  257.53  5142.9  255.69  5200.5   257.5
  5227.2  260.03  5232.2  259.37  5240.8  259.92  5291.1  264.37  5301.2  266.18
  5311.2  265.23  5371.6  266.59  5400.7   268.6  5421.9   267.8  5501.5  268.33
#Mann= 3 , 0 , 0
  4395.7     .17       0  4958.9     .06       0  5009.3     .11       0
#XS Ineff= 2 , 0
       0  4958.9  257.45  5009.3       0  257.41
Permanent Ineff=
       T       T
Bank Sta=4958.9,5009.3
XS Rating Curve= 0 ,0
Exp/Cntr=0.3,0.1

Type RM Length L Ch R = 1 ,2908    ,362,362,362
BEGIN DESCRIPTION:
LOWER TRIB TO WF OF WHT OAK CRK 6.0
END DESCRIPTION:
XS GIS Cut Line= 3
       3814636.8     10127701.18      3814901.14       10127146.
      3814916.75     10126608.52
#Sta/Elev= 30
  4385.1  260.35  4573.5  250.49  4617.8  249.53  4739.6  251.82  4774.9  248.39
  4792.1  248.44  4797.6   247.1    4843  243.66  4872.5  239.74  4888.4  238.89
  4905.6  235.61  4933.8  234.29  4937.6  233.25    5005  236.55  5044.9  240.45
  5059.5  240.64    5075  243.99    5085  245.38    5105  245.48    5185  254.57
    5205  255.83    5235  260.57  5242.1   259.8    5275  262.24  5315.1  263.54
  5438.5  265.32  5446.8  265.32  5485.1  265.53  5536.8  268.27  5537.7  268.27
#Mann= 7 ,-1 , 0
  4385.1     .17       0    4843     .09       0    5075     .17       0
  5242.1     .11       0  5438.5    .125       0  5446.8     .11       0
  5536.8    .125       0
Bank Sta=4843,5075
XS Rating Curve= 0 ,0
Exp/Cntr=0.3,0.1

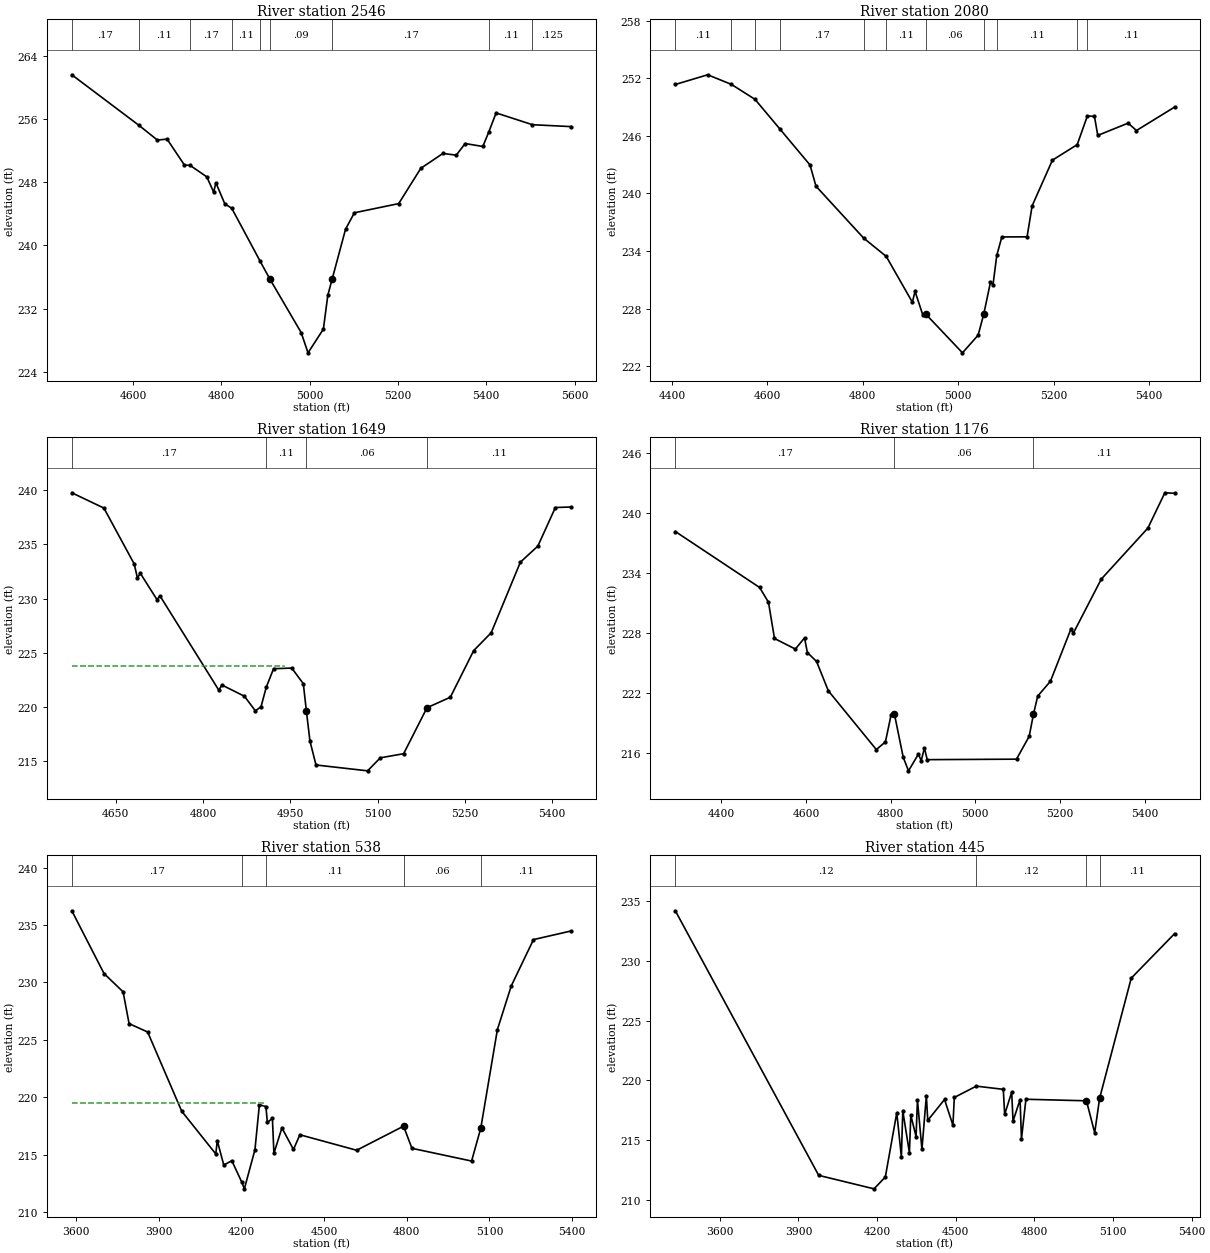
Type RM Length L Ch R = 1 ,2546    ,466,466,466
BEGIN DESCRIPTION:
LOWER TRIB TO WF OF WHT OAK CRK 5.0
END DESCRIPTION:
XS GIS Cut Line= 3
      3815153.95     10127751.73       3815252.7     10127221.95
       3815204.5     10126631.92
#Sta/Elev= 30
  4461.1  261.57  4612.7   255.2    4655  253.32  4676.9  253.44  4716.1  250.17
  4729.1  250.12  4766.9  248.67  4782.4  246.74  4787.5  247.92  4807.6  245.27
  4823.4   244.7  4887.9  237.99  4909.3   235.8  4980.6     229  4996.2  226.43
    5031  229.43    5041   233.7  5051.1   235.8  5081.2  242.05  5101.2  244.13
  5201.6  245.29  5251.7  249.75  5301.9  251.63    5332  251.41  5352.1  252.88
  5392.2  252.51  5405.6  254.33  5422.3  256.75  5504.6  255.26    5592  255.02
#Mann= 9 ,-1 , 0
  4461.1     .17       0  4612.7     .11       0  4729.1     .17       0
  4823.4     .11       0  4887.9     .17       0  4909.3     .09       0
  5051.1     .17       0  5405.6     .11       0  5504.6    .125       0
Bank Sta=4909.3,5051.1
XS Rating Curve= 0 ,0
Exp/Cntr=0.3,0.1

Type RM Length L Ch R = 1 ,2080    ,431,431,431
BEGIN DESCRIPTION:
LOWER TRIB TO WF OF WHT OAK CRK 4.0
END DESCRIPTION:
XS GIS Cut Line= 3
      3815398.93     10127611.76      3815675.88      10127087.4
      3815527.22     10126659.07
#Sta/Elev= 30
    4407  251.35  4474.8  252.36  4524.5  251.36    4574   249.8  4625.8  246.73
  4689.3  242.96  4701.8  240.75  4801.7  235.34  4849.1  233.43  4903.8  228.66
  4909.5  229.78  4925.8  227.32  4931.5  227.44  5008.9  223.38  5041.7  225.22
  5053.6 227.439  5067.6  230.75  5072.9  230.48  5080.8  233.54  5091.4  235.46
  5144.3  235.47  5154.9   238.7  5197.4  243.46  5249.4  245.08  5270.7  248.07
  5285.5  248.02  5292.5  246.04    5356  247.32  5373.6  246.55  5453.4  248.99
#Mann= 11 ,-1 , 0
    4407     .11       0  4524.5     .17       0    4574     .11       0
  4625.8     .17       0  4801.7     .11       0  4849.1     .11       0
  4931.5     .06       0  5053.6     .11       0  5080.8     .11       0
  5249.4     .17       0  5270.7     .11       0
Bank Sta=4931.5,5053.6
XS Rating Curve= 0 ,0
Exp/Cntr=0.3,0.1

Type RM Length L Ch R = 1 ,1649    ,473,473,473
BEGIN DESCRIPTION:
LOWER TRIB TO WF OF WHT OAK CRK 3.0
END DESCRIPTION:
XS GIS Cut Line= 3
      3815931.63     10127324.05      3816049.34     10126915.47
      3816078.25     10126484.24
#Sta/Elev= 30
  4574.8  239.77  4629.9  238.36    4682   233.2  4687.4  231.93  4692.6  232.33
    4721  229.92  4726.2  230.26  4827.3  221.56  4832.5  222.04  4871.3     221
  4890.1  219.65  4899.8  220.04  4908.8  221.84  4921.3  223.54  4952.5   223.6
  4972.4  222.16  4977.6  219.67  4983.8  216.86  4994.2  214.66  5082.8  214.12
  5104.6  215.32  5144.7   215.7  5184.8  219.94  5224.9  220.91    5265  225.21
  5295.1  226.86  5345.2  233.37  5375.2  234.85  5405.3  238.41  5432.2  238.46
#Mann= 4 ,-1 , 0
  4574.8     .17       0  4908.8     .11       0  4977.6     .06       0
  5184.8     .11       0
#XS Ineff= 2 , 0
       0  4938.7  223.77               0
Permanent Ineff=
       F       F
Bank Sta=4977.6,5184.8
XS Rating Curve= 0 ,0
Exp/Cntr=0.3,0.1

Type RM Length L Ch R = 1 ,1176    ,638,638,638
BEGIN DESCRIPTION:
LOWER TRIB TO WF OF WHT OAK CRK 2.0
END DESCRIPTION:
XS GIS Cut Line= 3
      3815989.94     10127324.05      3816515.31     10126848.11
      3816489.84      10126378.2
#Sta/Elev= 30
  4291.1  238.18  4490.3  232.57  4511.2  231.09  4525.4  227.46  4574.7   226.4
  4596.4  227.52  4603.1  226.05  4624.8  225.16  4652.6  222.22    4766  216.33
  4787.5   217.1  4801.1  219.84  4808.6  219.92  4829.5  215.57    4842   214.2
  4865.4  215.87  4872.1  215.22  4879.6  216.49  4886.3  215.32  5097.2  215.37
  5127.2  217.66  5137.2  219.86  5147.3  221.69  5177.3  223.17  5226.3  228.46
  5231.3  227.98  5297.5  233.41  5407.6  238.52  5447.7  242.06  5470.6  242.01
#Mann= 3 , 0 , 0
  4291.1     .17       0  4808.6     .06       0  5137.2     .11       0
#XS Ineff= 2 , 0
       0  4808.6  219.92               0
Permanent Ineff=
       F       F
Bank Sta=4808.6,5137.2
XS Rating Curve= 0 ,0
Exp/Cntr=0.3,0.1

Type RM Length L Ch R = 1 ,538     ,93,93,93
BEGIN DESCRIPTION:
Mapping XS ce95882c
END DESCRIPTION:
XS GIS Cut Line= 4
      3816016.71     10127322.44      3816846.61     10126969.12
      3817026.64     10126493.55      3816989.93     10126095.12
#Sta/Elev= 30
  3585.3  236.24  3702.2  230.77  3771.3  229.18    3793  226.41  3860.3  225.68
  3983.9  218.78  4107.5  215.06  4112.9  216.21  4136.5  214.09  4165.6  214.47
  4201.8   212.6  4211.1  212.02  4249.5  215.43  4265.6  219.34  4289.2  219.19
  4294.6   217.8  4312.8  218.16  4318.3  215.11  4347.3  217.33  4389.2  215.45
  4412.5  216.73  4618.4  215.38  4788.6  217.48  4818.8  215.55  5035.2  214.44
  5068.6  217.31  5128.8  225.89    5179  229.69  5259.7  233.73  5395.9  234.48
#Mann= 5 ,-1 , 0
  3585.3     .17       0  4201.8     .11       0  4289.2     .11       0
  4788.6     .06       0  5068.6     .11       0
#XS Ineff= 2 , 0
       0  4282.1   219.5               0
Permanent Ineff=
       F       F
Bank Sta=4788.6,5068.6
XS Rating Curve= 0 ,0
Exp/Cntr=0.3,0.1

Type RM Length L Ch R = 1 ,445     ,84,84,84
BEGIN DESCRIPTION:
Mapping XS a8bb7088
END DESCRIPTION:
XS GIS Cut Line= 4
      3816023.69      10127350.2      3816905.63     10127030.76
      3817096.61     10126440.48      3817061.88     10126096.74
#Sta/Elev= 30
  3430.6  234.21  3977.4  212.03  4188.4   210.9  4231.5  211.89  4275.2  217.28
  4292.7  213.58  4298.1  217.44  4323.4  213.92  4328.7  217.07  4348.7  215.28
    4354  218.34  4371.1  214.21    4388  218.71  4393.3  216.64  4457.3  218.39
  4489.3  216.23  4494.6  218.56  4578.5  219.51  4681.4  219.24  4686.6  217.14
  4713.4     219  4718.6  216.58  4745.4  218.38  4750.7  215.08  4767.7  218.41
  4998.5  218.28    5030   215.6  5048.7  218.49  5169.3  228.56  5334.5  232.29
#Mann= 4 ,-1 , 0
  3430.6     .12       0  4578.5     .12       0  4998.5     .06       0
  5048.7     .11       0
#XS Ineff= 2 , 0
       0  4681.4  219.24               0
Permanent Ineff=
       T       F
Bank Sta=4998.5,5048.7
XS Rating Curve= 0 ,0
Exp/Cntr=0.3,0.1

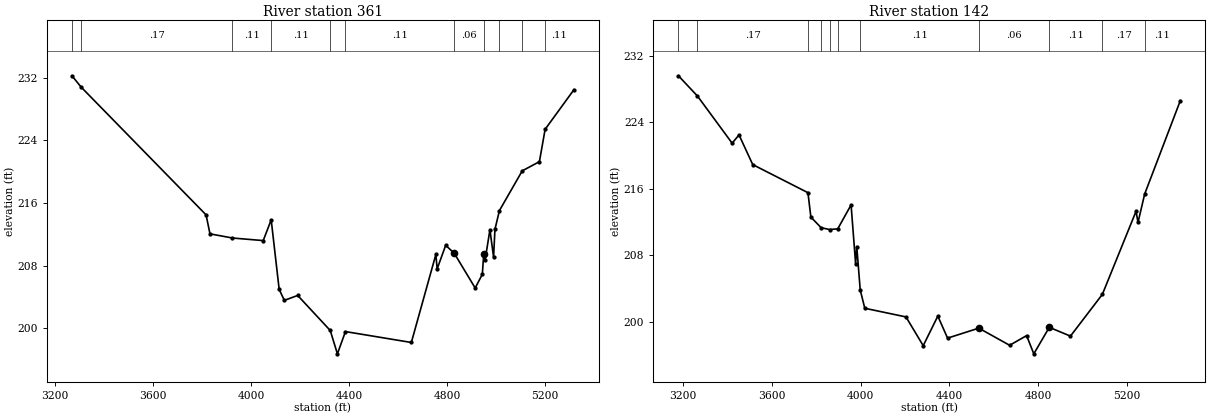
Type RM Length L Ch R = 1 ,361     ,219,219,219
BEGIN DESCRIPTION:
Mapping XS 77537cea
END DESCRIPTION:
XS GIS Cut Line= 4
      3816009.81     10127388.39       3816995.8      10127082.3
      3817175.73     10126406.44      3817117.71      10126094.7
#Sta/Elev= 30
  3268.2  232.23  3305.9  230.78  3815.8  214.48  3831.6  212.06  3923.4  211.53
    4049   211.2  4081.6  213.84  4114.1  204.98  4135.2  203.57  4189.7   204.2
  4322.6  199.73  4351.9  196.75  4384.7  199.59  4653.7   198.2  4753.8  209.43
    4759  207.59  4793.9   210.6  4828.9  209.58  4914.3  205.15  4943.5   206.9
  4949.3  209.55  4954.5  208.66  4974.5  212.59  4989.4  209.09    4995  212.63
  5013.1  215.02  5106.4   220.1  5176.5  221.27  5199.8   225.4  5317.1  230.44
#Mann= 11 ,-1 , 0
  3268.2     .11       0  3305.9     .17       0  3923.4     .11       0
  4081.6     .11       0  4322.6     .11       0  4384.7     .11       0
  4828.9     .06       0  4949.3     .11       0  5013.1     .11       0
  5106.4     .17       0  5199.8     .11       0
#XS Ineff= 1 ,-1
    4060  4793.9   210.6
Permanent Ineff=
       F
Bank Sta=4828.9,4949.3
XS Rating Curve= 0 ,0
Exp/Cntr=0.3,0.1

Type RM Length L Ch R = 1 ,142     ,0,0,0
BEGIN DESCRIPTION:
LOWER TRIB TO WF OF WHT OAK CRK 1.0
END DESCRIPTION:
XS GIS Cut Line= 4
      3816002.89     10127419.64       3817009.8     10127169.65
       3817379.2     10126478.67      3817163.52     10126094.93
#Sta/Elev= 30
    3179   229.6  3264.6  227.17  3421.1  221.49    3452  222.49  3513.8  218.92
  3762.6  215.54  3775.7  212.61  3821.9  211.33  3859.8  211.11  3896.8  211.19
  3956.9  214.07  3977.3  207.01  3982.5  209.06  3998.1  203.84  4018.7  201.64
  4204.2   200.6  4281.9  197.14  4347.7   200.7  4391.6  198.05  4532.4  199.25
  4671.2  197.19  4747.7  198.35  4780.1  196.16  4849.9  199.35  4945.2  198.29
  5088.9  203.31  5240.7   213.3  5249.6  211.97  5279.6  215.38  5440.2  226.61
#Mann= 11 ,-1 , 0
    3179     .11       0  3264.6     .17       0  3762.6     .15       0
  3821.9     .17       0  3859.8     .11       0  3896.8     .15       0
  3998.1     .11       0  4532.4     .06       0  4849.9     .11       0
  5088.9     .17       0  5279.6     .11       0
#XS Ineff= 1 ,-1
    4100  4347.7   200.7
Permanent Ineff=
       F
Bank Sta=4532.4,4849.9
XS Rating Curve= 0 ,0
Exp/Cntr=0.3,0.1

Chan Stop Cuts=-1
Use User Specified Reach Order=0
Composite Channel Slope=5