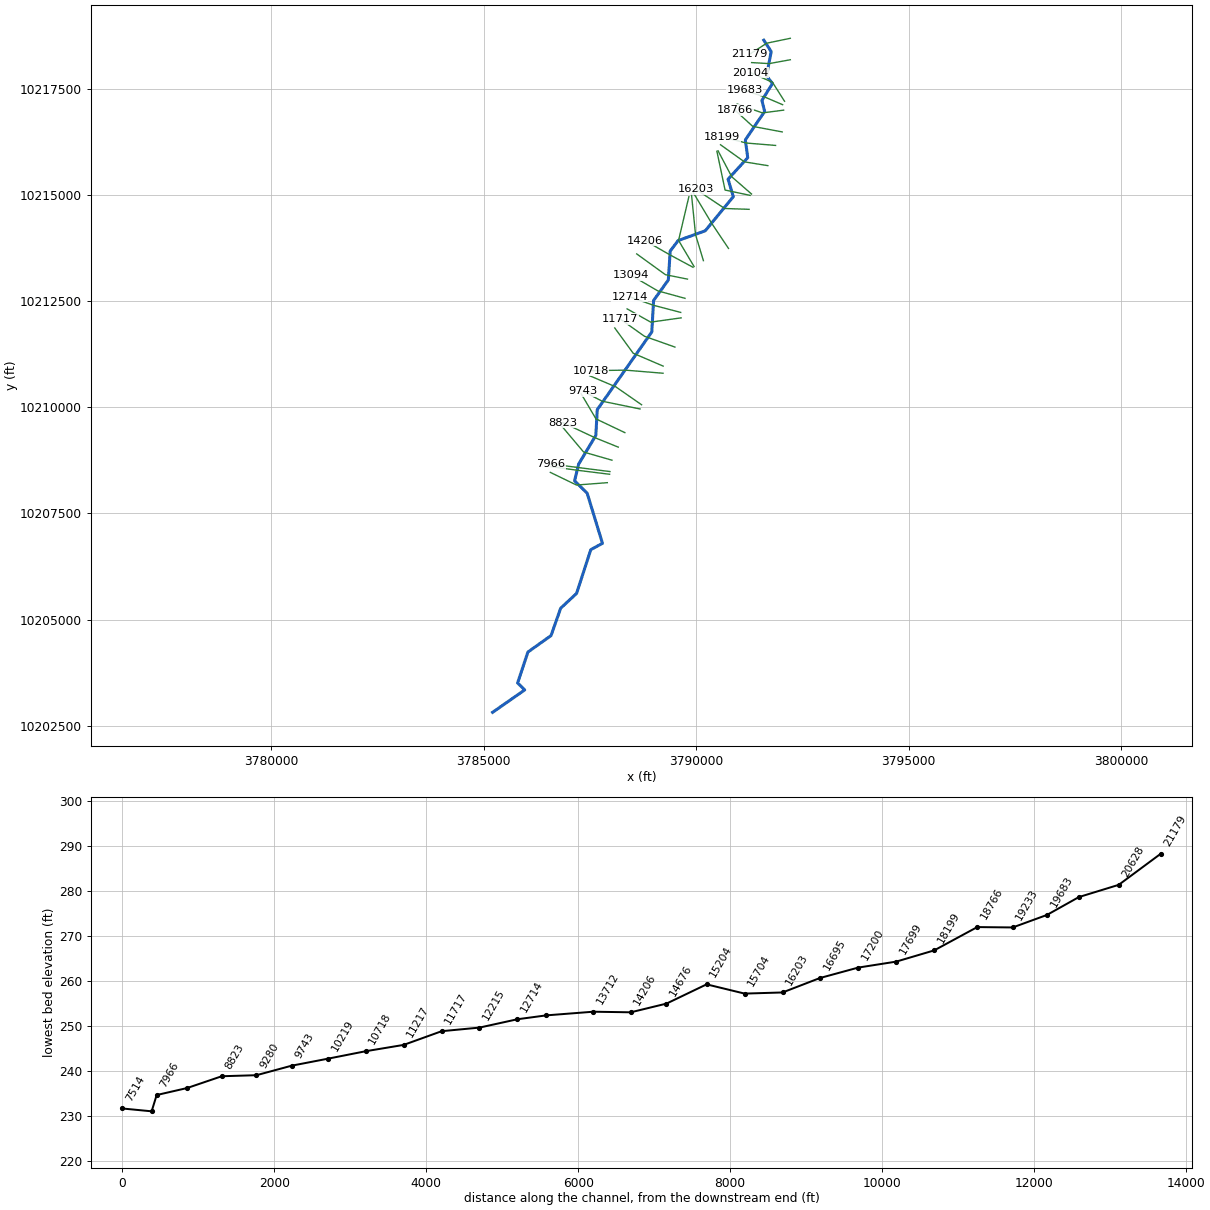
--- MAPLE BRANCH.prj (project) ---

Proj Title=MAPLE BRANCH Base Level Engineering
Current Plan=p01
Default Exp/Contr=0.3,0.1
English Units
Geom File=g01
Flow File=f01
Plan File=p01
Y Axis Title=Elevation
X Axis Title(PF)=Main Channel Distance
X Axis Title(XS)=Station
BEGIN DESCRIPTION:
MAPLE BRANCH
END DESCRIPTION:
DSS Export Rating Curves= 0
DSS Export Rating Curve Sorted= 0
DSS Export Volume Flow Curves= 0
DXF OffsetX= 0
DXF OffsetY= 0
DXF ScaleX= 1
DXF ScaleY= 10

--- MAPLE BRANCH.p01 (plan) ---

Plan Title=Multiple Run
Short Identifier=Multiple
Geom File=g01
Flow File=f01
Subcritical Flow
K Sum by GR= 0
Std Step Tol= 0.01
Critical Tol= 0.01
Num of Std Step Trials= 20
Max Error Tol= 0.3
Flow Tol Ratio= 0.001
Split Flow NTrial= 30
Split Flow Tol= 0.02
Split Flow Ratio= 0.02
Log Output Level= 0
Friction Slope Method= 1
Unsteady Friction Slope Method= 2
Unsteady Bridges Friction Slope Method= 1
Parabolic Critical Depth
Global Vel Dist=  1 , 1 , 1
Global Log Level= 0
CheckData=True
Encroach Param= -1, 0, 0, 0
BEGIN DESCRIPTION:
Multiple Run
END DESCRIPTION:

--- MAPLE BRANCH.f01 (steady flow) ---

Flow Title=Multiple
Program Version=4.10
Number of Profiles= 7
Profile Names=10-year,25-year,50-year,1pct_min,100-year,1pct_plu,500-year
River Rch & RM=MAPLE BRANCH,Reach-1         ,21179
     598     806    1086     482    1456    4397    2704
River Rch & RM=MAPLE BRANCH,Reach-1         ,20104
     832    1146    1569     706    2133    6442    4075
River Rch & RM=MAPLE BRANCH,Reach-1         ,17200
     946    1310    1797     811    2449    7396    4699
River Rch & RM=MAPLE BRANCH,Reach-1         ,14206
    1378    1941    2692    1226    3702   11180    7241
River Rch & RM=MAPLE BRANCH,Reach-1         ,10718
    1609    2282    3180    1453    4388   13252    8648
River Rch & RM=MAPLE BRANCH,Reach-1         ,7966
    1780    2529    3528    1613    4872   14713    9620
River Rch & RM=MAPLE BRANCH,Reach-1         ,1587
    1986    2833    3963    1817    5486   16567   10881
Boundary for River Rch & Prof#=MAPLE BRANCH,Reach-1         , 1
Up Type= 0
Dn Type= 3
Dn Slope=0.005
Boundary for River Rch & Prof#=MAPLE BRANCH,Reach-1         , 2
Up Type= 0
Dn Type= 3
Dn Slope=0.005
Boundary for River Rch & Prof#=MAPLE BRANCH,Reach-1         , 3
Up Type= 0
Dn Type= 3
Dn Slope=0.005
Boundary for River Rch & Prof#=MAPLE BRANCH,Reach-1         , 4
Up Type= 0
Dn Type= 3
Dn Slope=0.005
Boundary for River Rch & Prof#=MAPLE BRANCH,Reach-1         , 5
Up Type= 0
Dn Type= 3
Dn Slope=0.005
Boundary for River Rch & Prof#=MAPLE BRANCH,Reach-1         , 6
Up Type= 0
Dn Type= 3
Dn Slope=0.005
Boundary for River Rch & Prof#=MAPLE BRANCH,Reach-1         , 7
Up Type= 0
Dn Type= 3
Dn Slope=0.005
DSS Import GetInterval= 0
DSS Import GetPeak= 0
DSS Import FillOption= 0

--- MAPLE BRANCH.g01 (geometry) ---

Geom Title=Existing Conditions
Program Version=4.10

River Reach=MAPLE BRANCH    ,Reach-1
Reach XY= 30
      3791593.23     10218641.84       3791767.3     10218372.57
      3791657.84     10217800.18      3791797.57     10217621.99
      3791549.43     10217223.48      3791613.47     10216964.57
      3791159.39     10216294.43      3791215.52     10215875.34
      3790752.83     10215369.37      3790876.24     10214957.63
        3790216.     10214154.52      3789576.87     10213924.03
      3789390.32     10213677.12      3789346.33     10212997.66
      3788999.41     10212513.39      3788956.91     10211772.66
      3787673.42     10209943.61      3787639.64     10209337.14
      3787235.86     10208663.09      3787139.62     10208269.32
      3787435.82      10207976.8      3787796.05     10206796.83
      3787521.37     10206648.42      3787185.81     10205616.88
      3786811.84     10205269.15      3786584.71     10204624.44
      3786040.82      10204237.6      3785798.27      10203509.5
      3785965.44      10203345.5       3785208.7      10202817.9

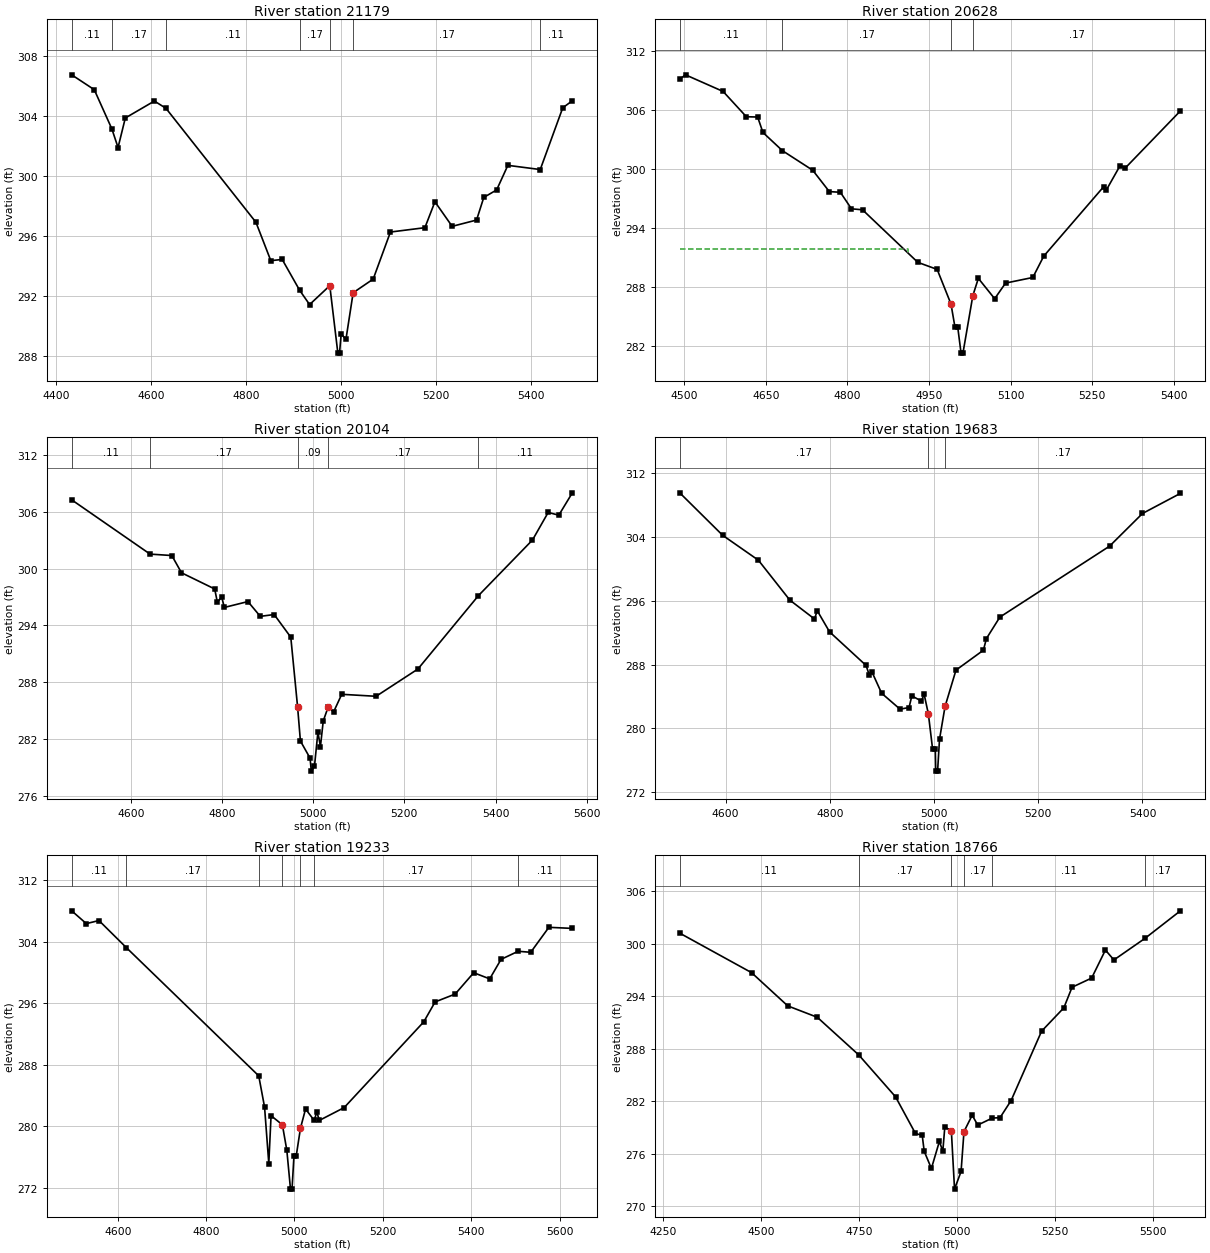
Type RM Length L Ch R = 1 ,21179   ,551,551,551
BEGIN DESCRIPTION:
MAPLE BRANCH 41.0
END DESCRIPTION:
XS GIS Cut Line= 3
      3792218.36     10218685.93      3791662.53     10218570.44
      3791253.73      10218306.5
#Sta/Elev= 30
  4432.3  306.76  4479.8  305.77  4516.9  303.15  4529.9  301.91  4545.2  303.88
  4606.4  305.01  4630.7  304.53  4820.3  296.92  4851.6  294.36  4875.6  294.44
  4912.4  292.38  4933.3  291.43  4975.8  292.69  4992.8  288.19  4996.3  288.19
  4999.8  289.48  5009.8   289.1    5025  292.22  5067.2  293.13  5103.5  296.27
  5176.1  296.56  5197.2  298.29  5233.5  296.65  5284.9  297.07  5300.1  298.58
  5327.2  299.08  5350.8  300.72    5419  300.44  5466.4  304.56  5486.6  305.03
#Mann= 7 ,-1 , 0
  4432.3     .11       0  4516.9     .17       0  4630.7     .11       0
  4912.4     .17       0  4975.8     .09       0    5025     .17       0
    5419     .11       0
#XS Ineff= 2 , 0
       0  4875.6  294.44               0
Permanent Ineff=
       F       F
Bank Sta=4975.8,5025
XS Rating Curve= 0 ,0
Exp/Cntr=0.3,0.1

Type RM Length L Ch R = 1 ,20628   ,524,524,524
BEGIN DESCRIPTION:
MAPLE BRANCH 40.0
END DESCRIPTION:
XS GIS Cut Line= 3
      3792218.31     10218180.91      3791718.54     10218089.81
      3791307.16     10218114.11
#Sta/Elev= 30
    4492  309.17  4502.6  309.61  4571.7  307.92  4614.4  305.35  4635.2  305.32
  4644.9  303.75  4680.7   301.9  4736.4  299.91  4766.9  297.74  4787.2  297.67
  4807.6  295.99  4827.9  295.89  4929.5  290.55  4965.1  289.83  4990.5  286.31
  4997.8  283.97  5002.9  283.97    5009  281.32  5012.5  281.32  5030.7  287.17
  5040.8  288.92  5070.8  286.85  5090.8  288.44  5140.9  289.01    5161  291.18
    5271  298.23    5276   297.9  5301.2  300.37  5311.2  300.16  5412.1  305.94
#Mann= 4 ,-1 , 0
    4492     .11       0  4680.7     .17       0  4990.5     .09       0
  5030.7     .17       0
#XS Ineff= 2 , 0
       0  4911.8  291.89               0
Permanent Ineff=
       F       F
Bank Sta=4990.5,5030.7
XS Rating Curve= 0 ,0
Exp/Cntr=0.3,0.1

Type RM Length L Ch R = 1 ,20104   ,421,421,421
BEGIN DESCRIPTION:
MAPLE BRANCH 39.0
END DESCRIPTION:
XS GIS Cut Line= 3
      3792082.05     10217202.95      3791798.05     10217649.97
      3791277.82     10217878.95
#Sta/Elev= 30
  4470.4  307.25  4642.3  301.52    4690  301.37  4711.2  299.55    4784  297.84
  4789.9  296.43  4799.3     297  4805.2  295.89  4856.9  296.51    4884  294.95
  4914.5  295.14  4950.9  292.75  4965.8   285.4    4972  281.79  4993.2  279.98
  4995.9  278.61  5002.8  279.11  5010.4  282.73  5015.9   281.2  5022.1  283.91
    5033  285.39  5044.7  284.85  5062.6  286.72    5138  286.51  5229.7  289.39
  5362.5  297.14    5481  303.01  5515.4  305.92  5538.7  305.63  5568.4  307.99
#Mann= 5 ,-1 , 0
  4470.4     .11       0  4642.3     .17       0  4965.8     .09       0
    5033     .17       0  5362.5     .11       0
Bank Sta=4965.8,5033
XS Rating Curve= 0 ,0
Exp/Cntr=0.3,0.1

Type RM Length L Ch R = 1 ,19683   ,450,450,450
BEGIN DESCRIPTION:
MAPLE BRANCH 38.0
END DESCRIPTION:
XS GIS Cut Line= 3
       3792036.6      10217122.8      3791587.85     10217314.56
      3791138.78     10217462.14
#Sta/Elev= 30
    4512  309.55  4594.4  304.22  4662.9   301.1  4723.3  296.09  4770.5  293.73
  4775.9  294.76  4799.5  292.11  4869.5   287.9  4875.8  286.69  4881.2  287.03
  4899.4  284.41  4934.8  282.41    4952  282.62  4957.4  284.08  4975.6  283.43
    4981  284.28  4989.1  281.81  4997.3  277.36  5002.4  277.36  5003.3  274.64
  5006.8  274.64  5010.5  278.64  5021.1  282.75  5042.1  287.31  5094.7  289.81
  5100.5  291.27  5126.3  293.96  5336.8  302.86    5400  306.96  5472.7  309.48
#Mann= 3 , 0 , 0
    4512     .17       0  4989.1     .09       0  5021.1     .17       0
Bank Sta=4989.1,5021.1
XS Rating Curve= 0 ,0
Exp/Cntr=0.3,0.1

Type RM Length L Ch R = 1 ,19233   ,467,467,467
BEGIN DESCRIPTION:
MAPLE BRANCH 37.0
END DESCRIPTION:
XS GIS Cut Line= 3
      3792060.64     10216994.52       3791560.8     10216929.15
      3790967.78     10217138.83
#Sta/Elev= 30
  4495.9  307.98    4529  306.32  4557.6  306.72  4619.5  303.21  4919.2  286.57
  4932.4  282.52    4942  275.19  4947.1   281.4  4972.7  280.22  4982.8  276.91
  4991.1  271.87  4994.6  271.87    4999  276.23  5004.2  276.23  5013.7  279.78
  5025.2  282.27  5044.6  280.79  5050.8  281.88  5056.2  280.78  5112.6  282.45
  5292.8  293.58  5318.4  296.16  5363.8  297.18  5405.8  299.95    5442  299.15
  5467.6  301.68  5506.3  302.73  5534.8   302.6  5575.9  305.84    5629   305.7
#Mann= 7 ,-1 , 0
  4495.9     .11       0  4619.5     .17       0  4919.2     .11       0
  4972.7     .07       0  5013.7     .15       0  5044.6     .17       0
  5506.3     .11       0
Bank Sta=4972.7,5013.7
XS Rating Curve= 0 ,0
Exp/Cntr=0.3,0.1

Type RM Length L Ch R = 1 ,18766   ,567,567,567
BEGIN DESCRIPTION:
MAPLE BRANCH 36.0
END DESCRIPTION:
XS GIS Cut Line= 3
      3792028.64     10216481.49      3791333.51     10216612.11
      3790912.92     10216996.08
#Sta/Elev= 30
  4292.7  301.19  4475.8  296.68  4568.2  292.88  4643.5  291.58  4749.2  287.28
    4843   282.5  4893.8  278.31  4911.1  278.09  4916.2  276.27  4934.5  274.31
  4954.9   277.4  4963.6  276.28  4968.7  279.03  4985.4  278.62  4993.5  271.95
  5010.2  273.97  5017.6  278.52  5038.5  280.39  5052.7  279.27    5090  280.07
  5109.5  280.11  5137.8  282.07  5215.5  289.99  5272.3  292.66  5293.2  295.01
  5343.2  296.06  5378.3  299.26    5400  298.13  5479.4   300.6  5569.5  303.74
#Mann= 6 ,-1 , 0
  4292.7     .11       0  4749.2     .17       0  4985.4     .09       0
  5017.6     .17       0    5090     .11       0  5479.4     .17       0
Bank Sta=4985.4,5017.6
XS Rating Curve= 0 ,0
Exp/Cntr=0.3,0.1

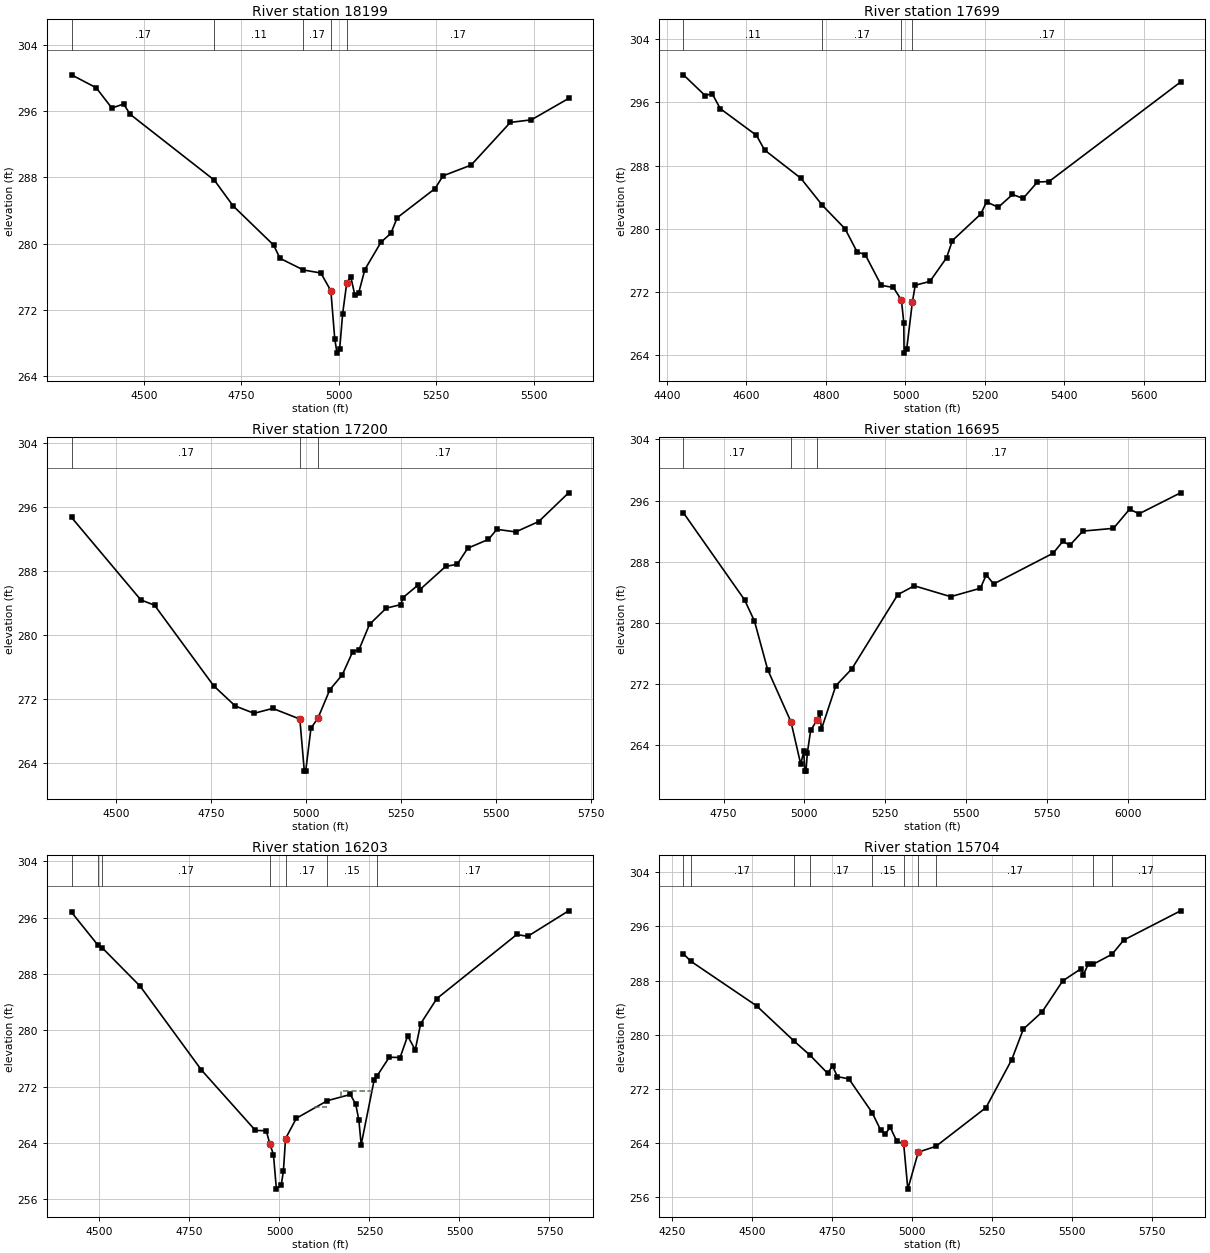
Type RM Length L Ch R = 1 ,18199   ,500,500,500
BEGIN DESCRIPTION:
MAPLE BRANCH 35.0
END DESCRIPTION:
XS GIS Cut Line= 3
      3791870.95     10216163.52      3791187.88     10216219.89
      3790615.06     10216361.26
#Sta/Elev= 30
  4314.6  300.36  4377.9   298.8  4418.1  296.35  4448.2  296.84  4465.2  295.59
    4681  287.65  4729.1  284.55  4833.2  279.81  4849.5  278.22  4909.6  276.81
  4954.2  276.45    4980  274.31    4990  268.49  4995.8  266.78  5002.6  267.28
  5010.3  271.56  5020.6  275.19  5030.9  276.02  5041.2  273.85  5051.5  274.07
  5067.3  276.87  5108.7  280.17  5133.9  281.23  5150.2  283.12  5247.2  286.63
  5267.8  288.17  5339.9  289.47  5440.5  294.62  5494.4  294.93    5590  297.51
#Mann= 5 ,-1 , 0
  4314.6     .17       0    4681     .11       0  4909.6     .17       0
    4980     .09       0  5020.6     .17       0
#XS Ineff= 2 , 0
       0  4833.2  279.81               0
Permanent Ineff=
       F       F
Bank Sta=4980,5020.6
XS Rating Curve= 0 ,0
Exp/Cntr=0.3,0.1

Type RM Length L Ch R = 1 ,17699   ,499,499,499
BEGIN DESCRIPTION:
MAPLE BRANCH 34.0
END DESCRIPTION:
XS GIS Cut Line= 3
      3791689.27      10215687.9      3791137.85     10215776.59
      3790575.03     10216179.55
#Sta/Elev= 30
  4441.5   299.5  4495.8  296.88  4513.8  297.11  4534.1  295.22  4625.2  291.84
  4645.5  289.99  4736.7  286.42    4791  282.99  4848.1  280.02  4878.5  277.08
  4898.7  276.76  4939.2  272.86  4969.6   272.6  4989.9     271  4995.8  268.16
  4996.6  264.29  5003.1  264.79  5017.4  270.73  5024.6  272.88  5061.5  273.36
  5103.4  276.35  5118.1  278.53  5189.4  281.88  5204.1  283.42  5233.6  282.74
  5269.2  284.36  5296.2  283.87  5332.1  285.94  5361.3     286  5692.2  298.59
#Mann= 4 ,-1 , 0
  4441.5     .11       0    4791     .17       0  4989.9     .09       0
  5017.4     .17       0
Bank Sta=4989.9,5017.4
XS Rating Curve= 0 ,0
Exp/Cntr=0.3,0.1

Type RM Length L Ch R = 1 ,17200   ,505,505,505
BEGIN DESCRIPTION:
MAPLE BRANCH 33.0
END DESCRIPTION:
XS GIS Cut Line= 3
      3791304.52     10215019.86      3790839.91     10215425.25
      3790516.72     10216037.03
#Sta/Elev= 30
  4383.4  294.65  4565.8  284.35  4601.9  283.69  4757.5  273.63  4814.5   271.1
  4863.9  270.19  4913.2   270.8  4984.4  269.47  4996.2  262.97  4999.8  262.97
  5013.7  268.34 5031.95  269.57  5063.4  273.14  5096.1  274.99  5123.7   277.9
  5140.1  278.13  5167.8  281.29  5211.8  283.32  5250.2  283.76  5255.8  284.63
  5294.2  286.15  5300.6  285.64  5368.5  288.54  5398.6  288.79  5426.3   290.8
    5481  291.91    5503  293.16  5552.7  292.84  5613.1  294.13  5691.9  297.72
#Mann= 3 ,-1 , 0
  4383.4     .17       0  4984.4     .09       0 5031.95     .17       0
Bank Sta=4984.4,5031.95
XS Rating Curve= 0 ,0
Exp/Cntr=0.3,0.1

Type RM Length L Ch R = 1 ,16695   ,492,492,492
BEGIN DESCRIPTION:
MAPLE BRANCH 32.0
END DESCRIPTION:
XS GIS Cut Line= 3
      3791272.42     10214987.82      3790681.91     10215113.41
      3790489.64     10216026.67
#Sta/Elev= 30
    4626   294.4  4814.8  283.04  4845.4  280.27  4886.3  273.92  4958.5  267.08
  4988.5  261.56  4997.9  263.23  5001.2  260.65  5004.8  260.65  5008.9  262.99
  5019.2  265.96  5039.6  267.38  5047.5  268.25  5052.6  266.13  5097.1  271.81
  5146.7  274.02  5288.6  283.71  5339.7  284.87  5452.2  283.45  5544.1  284.55
  5562.2   286.3    5585  285.11    5769  289.13  5799.6  290.71    5820  290.14
  5861.1  292.02  5955.6  292.38  6005.4  294.88  6034.7  294.28    6163  297.02
#Mann= 3 ,-1 , 0
    4626     .17       0  4958.5     .09       0  5039.6     .17       0
Bank Sta=4958.5,5039.6
XS Rating Curve= 0 ,0
Exp/Cntr=0.3,0.1

Type RM Length L Ch R = 1 ,16203   ,499,499,499
BEGIN DESCRIPTION:
MAPLE BRANCH 31.0
END DESCRIPTION:
XS GIS Cut Line= 3
      3791248.41     10214659.16      3790671.17     10214679.52
      3790003.77      10215126.4
#Sta/Elev= 30
  4422.4  296.77  4495.7   292.1  4508.4  291.68  4613.1  286.26  4783.2  274.37
  4933.3  265.78  4963.3  265.74  4973.3  263.87  4983.3  262.36  4991.5  257.45
    5005  258.08  5010.9  259.97  5016.9  264.62  5046.9  267.51  5133.1  270.01
    5197  270.89    5212  269.49  5220.6  267.22    5227  263.77  5263.1  272.96
  5270.7   273.5  5305.1  276.18  5335.1  276.14  5356.1   279.2  5377.2  277.22
  5392.2  280.94  5437.2  284.51  5659.4  293.61  5689.4  293.34  5803.2  296.97
#Mann= 7 ,-1 , 0
  4422.4     .17       0  4495.7     .11       0  4508.4     .17       0
  4973.3     .09       0  5016.9     .17       0  5133.1     .15       0
  5270.7     .17       0
#XS Ineff= 2 ,-1
    5098  5133.1  269.11    5170  5263.1  271.39
Permanent Ineff=
       F       F
Bank Sta=4973.3,5016.9
XS Rating Curve= 0 ,0
Exp/Cntr=0.3,0.1

Type RM Length L Ch R = 1 ,15704   ,500,500,500
BEGIN DESCRIPTION:
MAPLE BRANCH 30.0
END DESCRIPTION:
XS GIS Cut Line= 3
      3790762.04     10213740.02      3790365.22     10214332.86
      3789933.74     10215051.95
#Sta/Elev= 30
  4286.6  291.94  4309.1  290.86  4514.7  284.27  4631.9  279.06  4681.5  276.98
  4736.9  274.29  4751.9  275.43  4766.9  273.81  4802.9  273.48  4875.5  268.51
    4902  265.94    4917  265.36    4932  266.33    4953  264.24    4974  263.94
  4987.1   257.2  5019.7  262.66  5074.8  263.52  5231.2  269.24  5311.3   276.3
  5347.8  280.83  5406.1  283.35  5470.6  287.94  5528.9  289.77  5534.8  288.78
  5550.3  290.43  5565.9  290.41  5624.8  291.88  5661.1  293.97  5838.6  298.29
#Mann= 10 ,-1 , 0
  4286.6     .11       0  4309.1     .17       0  4631.9     .11       0
  4681.5     .17       0  4875.5     .15       0    4974     .09       0
  5019.7     .15       0  5074.8     .17       0  5565.9     .11       0
  5624.8     .17       0
Bank Sta=4974,5019.7
XS Rating Curve= 0 ,0
Exp/Cntr=0.3,0.1

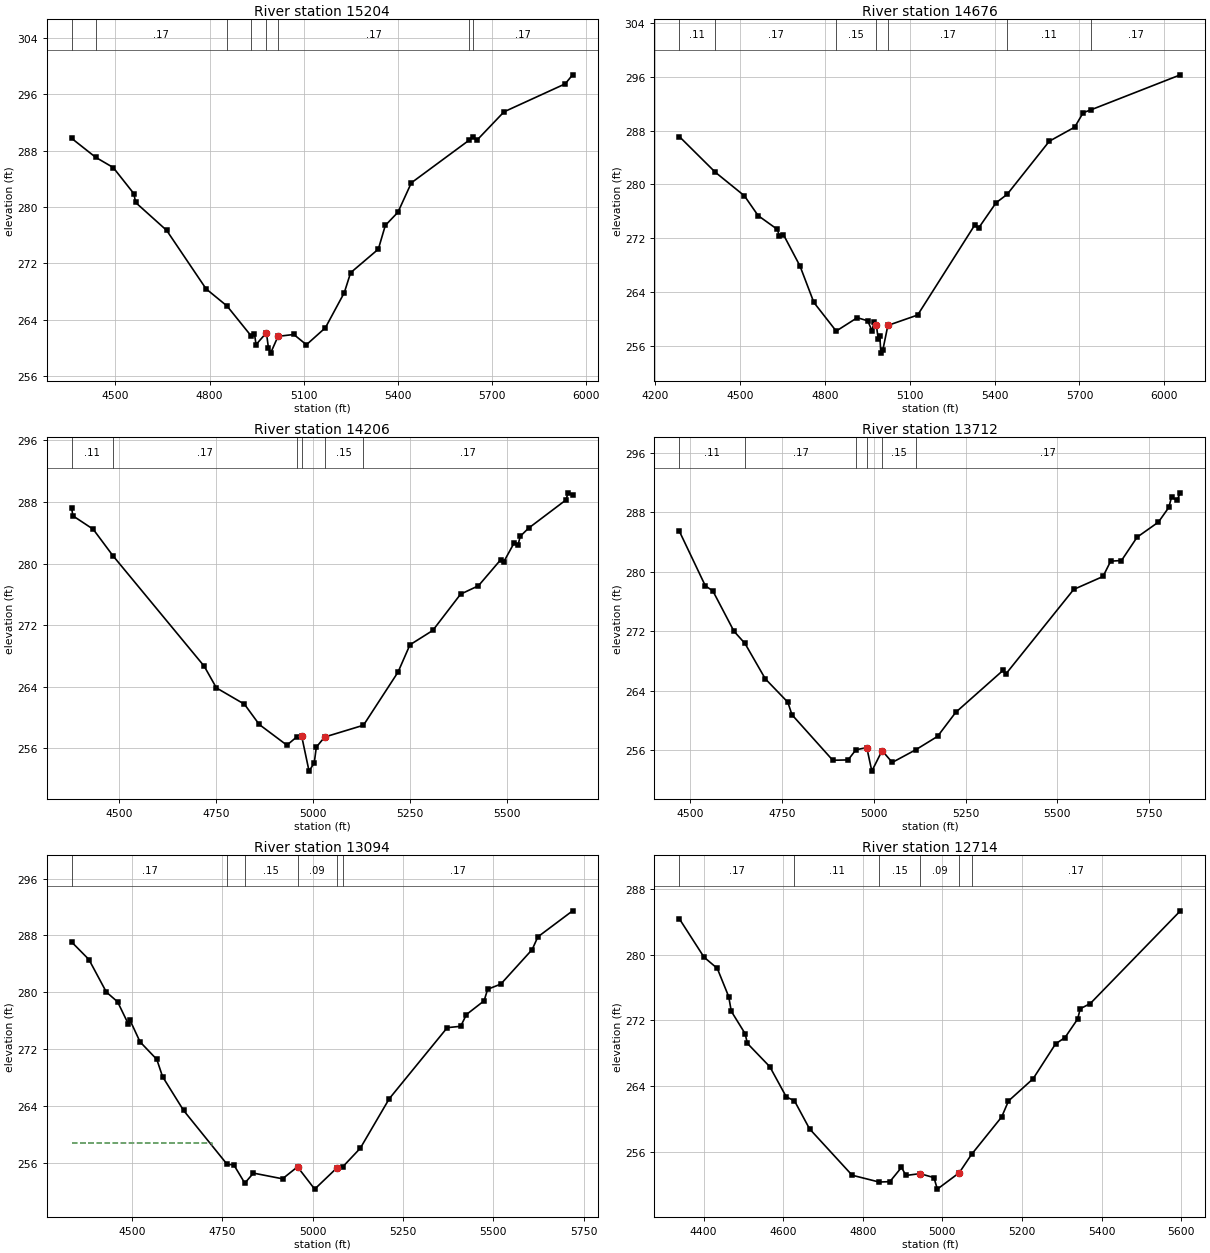
Type RM Length L Ch R = 1 ,15204   ,528,528,528
BEGIN DESCRIPTION:
MAPLE BRANCH 29.0
END DESCRIPTION:
XS GIS Cut Line= 3
      3790171.56     10213451.38      3789987.03     10214063.46
      3789890.99     10215014.53
#Sta/Elev= 30
  4360.7  289.75  4436.5  287.08  4492.9  285.61  4558.8  281.89  4564.1  280.65
    4663  276.69  4788.6  268.38  4855.4  265.94  4931.3  261.74  4942.6  262.02
  4947.8  260.46  4980.8  262.15  4987.1  260.02  4994.1  259.25  5017.7  261.63
    5068   261.9  5108.2  260.44  5168.5  262.85  5228.8  267.84  5248.9  270.67
  5337.2  274.02  5359.4  277.39  5399.6  279.26  5442.3  283.44  5626.8  289.51
  5638.2  290.01  5650.9  289.48  5737.3  293.52  5932.3   297.5  5955.9  298.78
#Mann= 8 ,-1 , 0
  4360.7     .11       0  4436.5     .17       0  4855.4     .15       0
  4931.3     .17       0  4980.8     .09       0  5017.7     .17       0
  5626.8     .11       0  5638.2     .17       0
Bank Sta=4980.8,5017.7
XS Rating Curve= 0 ,0
Exp/Cntr=0.3,0.1

Type RM Length L Ch R = 1 ,14676   ,470,470,470
BEGIN DESCRIPTION:
MAPLE BRANCH 28.0
END DESCRIPTION:
XS GIS Cut Line= 3
      3789952.47     10213312.41      3789587.13     10213926.92
      3789829.52     10214955.75
#Sta/Elev= 30
  4285.1  287.09  4411.8  281.82  4514.8  278.32  4563.4  275.38  4631.7  273.33
  4637.5  272.42  4653.1  272.54  4711.5   267.9  4760.5   262.5  4839.5  258.25
  4914.1  260.24  4951.1  259.77  4966.7  258.24  4972.5  259.61  4981.6   259.1
  4988.1  257.12  4993.9  257.45  4997.5  254.98  5004.7  255.48  5022.3  259.09
  5127.6  260.63    5329  273.94  5343.3  273.54  5404.9  277.28  5444.3  278.54
  5593.4  286.42  5683.3  288.51  5713.2  290.65  5742.1   291.1    6057  296.27
#Mann= 7 ,-1 , 0
  4285.1     .11       0  4411.8     .17       0  4839.5     .15       0
  4981.6     .09       0  5022.3     .17       0  5444.3     .11       0
  5742.1     .17       0
Bank Sta=4981.6,5022.3
XS Rating Curve= 0 ,0
Exp/Cntr=0.3,0.1

Type RM Length L Ch R = 1 ,14206   ,494,494,494
BEGIN DESCRIPTION:
MAPLE BRANCH 27.0
END DESCRIPTION:
XS GIS Cut Line= 3
      3789926.77     10213295.42      3789378.15     10213590.63
        3788797.     10213924.24
#Sta/Elev= 30
    4377  287.17  4379.9  286.21  4432.5  284.46  4483.1  281.04  4719.1  266.67
  4750.5  263.86  4822.9  261.74  4861.1  259.11  4932.5  256.42  4958.1   257.5
  4970.6  257.61  4989.7  253.05  5003.1  254.12  5008.5  256.17  5030.1  257.48
  5130.2  259.01  5219.4  265.91  5250.1  269.45  5309.1  271.32  5380.9  276.03
    5427  277.12  5484.6  280.51  5491.7  280.17  5519.2  282.69  5529.1  282.38
  5534.8  283.54  5556.4   284.6  5652.8  288.26  5658.5  289.19  5670.1  288.93
#Mann= 6 ,-1 , 0
    4377     .11       0  4483.1     .17       0  4958.1     .15       0
  4970.6     .09       0  5030.1     .15       0  5130.2     .17       0
Bank Sta=4970.6,5030.1
XS Rating Curve= 0 ,0
Exp/Cntr=0.3,0.1

Type RM Length L Ch R = 1 ,13712   ,618,618,618
BEGIN DESCRIPTION:
MAPLE BRANCH 26.0
END DESCRIPTION:
XS GIS Cut Line= 3
      3789796.89     10213016.62      3789278.82     10213120.61
      3788602.44     10213609.55
#Sta/Elev= 30
  4471.6  285.44    4542  278.12  4562.4  277.44  4619.9  272.01  4649.9  270.36
  4705.2   265.6  4766.4  262.46  4777.7  260.77  4888.8  254.64  4930.4  254.69
  4951.7  256.05  4981.3  256.35    4995  253.18    5023  255.94  5050.6  254.35
  5115.1  256.07  5173.9  257.86  5223.3  261.09  5351.8  266.73    5359  266.21
  5544.4  277.64  5624.1  279.38  5644.9  281.44  5674.4  281.53  5716.9  284.67
  5774.9   286.7  5803.2  288.68  5810.5  290.06  5825.2  289.63  5834.6  290.64
#Mann= 6 ,-1 , 0
  4471.6     .11       0  4649.9     .17       0  4951.7     .15       0
  4981.3     .09       0    5023     .15       0  5115.1     .17       0
Bank Sta=4981.3,5023
XS Rating Curve= 0 ,0
Exp/Cntr=0.3,0.1

Type RM Length L Ch R = 1 ,13094   ,380,380,380
BEGIN DESCRIPTION:
MAPLE BRANCH 25.0
END DESCRIPTION:
XS GIS Cut Line= 3
      3789740.22     10212563.88      3789097.65     10212740.12
      3788476.34     10213102.55
#Sta/Elev= 30
  4333.7  287.07  4381.3  284.62  4429.5  280.05  4460.6  278.68  4489.9  275.61
    4495  276.09  4522.8  273.05  4569.1  270.59    4585  268.17  4643.2  263.42
  4763.8  255.84    4782  255.79  4812.5  253.21  4836.3  254.62  4916.8  253.82
  4958.3   255.5  5005.8  252.37  5067.4  255.36  5082.8  255.47  5131.9  258.11
  5212.1  265.07  5372.5  275.05  5409.7  275.24  5425.5  276.89  5474.4  278.82
  5484.2  280.44  5520.7  281.17  5607.4  286.02  5623.1   287.8  5719.3  291.46
#Mann= 6 ,-1 , 0
  4333.7     .17       0  4763.8     .11       0  4812.5     .15       0
  4958.3     .09       0  5067.4     .15       0  5082.8     .17       0
#XS Ineff= 2 , 0
       0  4722.5  258.89               0
Permanent Ineff=
       F       F
Bank Sta=4958.3,5067.4
XS Rating Curve= 0 ,0
Exp/Cntr=0.3,0.1

Type RM Length L Ch R = 1 ,12714   ,499,499,499
BEGIN DESCRIPTION:
MAPLE BRANCH 24.0
END DESCRIPTION:
XS GIS Cut Line= 3
      3789637.56     10212232.69       3788998.4      10212400.4
      3788434.41      10212599.5
#Sta/Elev= 30
  4339.2  284.33  4400.9  279.69  4434.2  278.33    4463  274.89  4469.4  273.12
  4504.3  270.39  4509.8  269.22  4566.3  266.38  4607.7  262.71  4628.2  262.24
  4666.2  258.83  4773.1   253.2  4841.1  252.37    4868  252.42  4897.2  254.15
  4908.4  253.17  4943.6  253.39  4978.8  252.91  4987.3  251.51  5042.4   253.5
  5073.3  255.73    5149  260.28  5166.1  262.22    5228  264.92  5284.5  269.16
  5308.1  269.92  5339.9  272.17  5346.4  273.42  5371.8  274.06  5598.1  285.32
#Mann= 6 ,-1 , 0
  4339.2     .17       0  4628.2     .11       0  4841.1     .15       0
  4943.6     .09       0  5042.4     .15       0  5073.3     .17       0
Bank Sta=4943.6,5042.4
XS Rating Curve= 0 ,0
Exp/Cntr=0.3,0.1

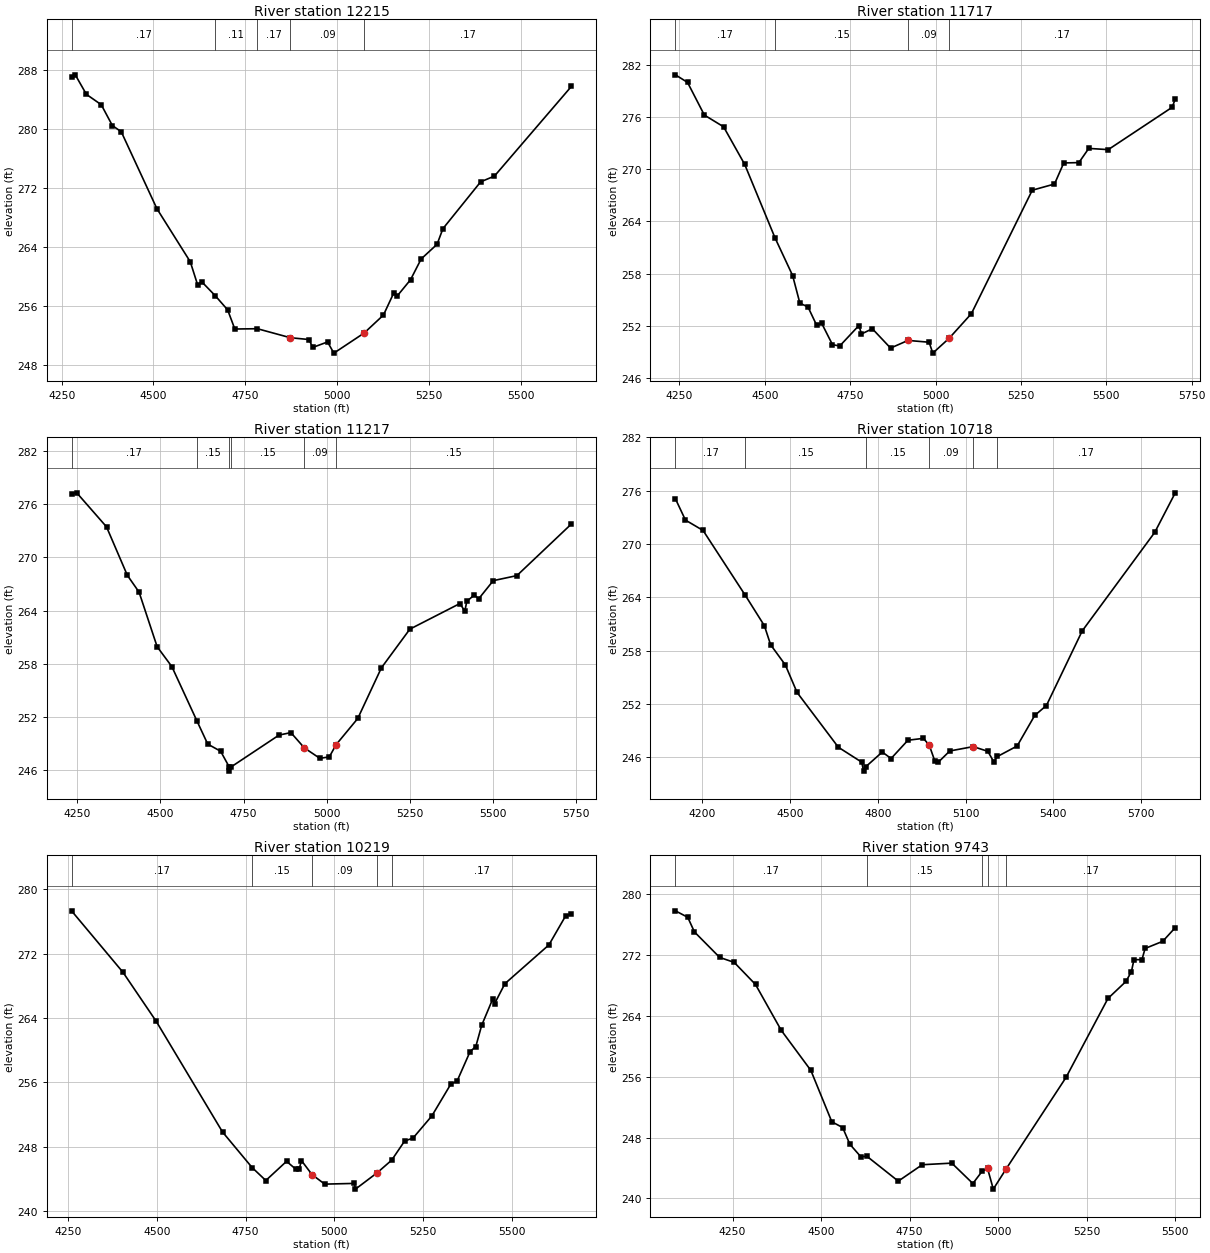
Type RM Length L Ch R = 1 ,12215   ,498,498,498
BEGIN DESCRIPTION:
MAPLE BRANCH 23.0
END DESCRIPTION:
XS GIS Cut Line= 3
        3789648.     10212104.83      3788931.98     10212003.83
      3788376.09     10212316.32
#Sta/Elev= 30
  4276.9  287.05  4287.1  287.29  4317.4  284.65  4357.8  283.25  4388.1  280.43
  4412.3  279.59  4509.3  269.19  4600.2  262.01  4620.4  258.86  4630.8  259.34
  4668.2  257.42  4701.9  255.51  4721.4  252.92  4782.9  252.96  4872.9  251.74
  4923.4   251.5  4933.5  250.43  4973.9  251.17  4991.1  249.66  5073.6  252.38
  5126.1  254.81  5153.9  257.77  5163.7   257.4  5199.8  259.58  5228.7  262.39
  5272.1  264.38    5288  266.49  5390.7  272.82  5428.3   273.6  5637.7  285.72
#Mann= 5 ,-1 , 0
  4276.9     .17       0  4668.2     .11       0  4782.9     .17       0
  4872.9     .09       0  5073.6     .17       0
#XS Ineff= 2 , 0
       0  4701.9  255.51               0
Permanent Ineff=
       F       F
Bank Sta=4872.9,5073.6
XS Rating Curve= 0 ,0
Exp/Cntr=0.3,0.1

Type RM Length L Ch R = 1 ,11717   ,500,500,500
BEGIN DESCRIPTION:
MAPLE BRANCH 22.0
END DESCRIPTION:
XS GIS Cut Line= 3
      3789501.32     10211417.31      3788783.47     10211671.71
      3788211.49      10212078.7
#Sta/Elev= 30
  4238.4  280.82  4273.9  279.95  4323.1   276.2  4379.5  274.85  4441.3  270.53
  4529.8  262.12  4581.6  257.77  4602.8   254.6  4626.6  254.16  4652.2  252.04
  4666.5   252.3  4698.3  249.83  4719.5  249.68  4775.7  252.03  4783.2  251.06
    4815  251.66  4868.4  249.44  4919.5  250.32  4981.3  250.11    4992  248.86
  5039.8  250.56    5105  253.39  5283.3  267.57  5348.4  268.28  5375.5   270.7
  5419.8  270.74  5448.7  272.37  5505.8  272.23  5692.8  277.09    5702  278.03
#Mann= 4 ,-1 , 0
  4238.4     .17       0  4529.8     .15       0  4919.5     .09       0
  5039.8     .17       0
#XS Ineff= 2 , 0
       0  4626.6  254.16               0
Permanent Ineff=
       F       F
Bank Sta=4919.5,5039.8
XS Rating Curve= 0 ,0
Exp/Cntr=0.3,0.1

Type RM Length L Ch R = 1 ,11217   ,499,499,499
BEGIN DESCRIPTION:
MAPLE BRANCH 21.0
END DESCRIPTION:
XS GIS Cut Line= 3
      3789224.64     10210968.75      3788519.18     10211271.56
      3788085.05       10211867.
#Sta/Elev= 30
  4232.3  277.21    4248  277.32  4337.6  273.47  4400.2  267.99  4435.6  266.08
    4490   259.9  4534.3  257.65  4609.8   251.5  4642.3  248.88  4681.1  248.07
  4706.6  246.32  4707.1  245.82  4713.6  246.32  4856.9   249.9  4892.6  250.18
  4933.1  248.45  4979.7  247.27  5008.2  247.43    5029  248.83  5093.9  251.78
    5165  257.51  5250.7  261.89  5401.4  264.79  5416.1  263.93  5422.2  265.04
  5444.9  265.76  5457.8  265.32  5501.8  267.38  5572.9  267.95  5736.9  273.79
#Mann= 6 ,-1 , 0
  4232.3     .17       0  4609.8     .15       0  4706.6     .12       0
  4713.6     .15       0  4933.1     .09       0    5029     .15       0
Bank Sta=4933.1,5029
XS Rating Curve= 0 ,0
Exp/Cntr=0.3,0.1

Type RM Length L Ch R = 1 ,10718   ,499,499,499
BEGIN DESCRIPTION:
MAPLE BRANCH 20.0
END DESCRIPTION:
XS GIS Cut Line= 3
      3789221.99     10210800.92      3788333.98      10210873.8
      3787517.87     10210861.07
#Sta/Elev= 30
    4109  275.09  4143.3  272.69  4203.5  271.52  4347.8  264.21  4412.8   260.8
  4434.2  258.65  4484.4  256.38  4524.5  253.28  4665.5  247.11  4745.3  245.43
  4751.8  244.42  4759.4  244.92  4815.5  246.57  4845.6  245.84  4903.2   247.9
    4956  248.11    4976  247.34  4995.5  245.51  5006.1   245.4  5046.1  246.69
  5126.1  247.18  5176.1  246.65  5196.1  245.48    5209  246.07  5276.2  247.25
  5336.2  250.69  5376.2  251.81  5498.4  260.21  5746.2  271.31  5816.2  275.76
#Mann= 6 ,-1 , 0
    4109     .17       0  4347.8     .15       0  4759.4     .15       0
    4976     .09       0  5126.1     .15       0    5209     .17       0
Bank Sta=4976,5126.1
XS Rating Curve= 0 ,0
Exp/Cntr=0.3,0.1

Type RM Length L Ch R = 1 ,10219   ,476,476,476
BEGIN DESCRIPTION:
MAPLE BRANCH 19.0
END DESCRIPTION:
XS GIS Cut Line= 3
      3788716.77     10210058.74      3788109.38     10210480.92
      3787495.41     10210741.03
#Sta/Elev= 30
  4260.3   277.3  4405.1  269.67  4498.7  263.58  4685.2  249.85  4768.4  245.44
    4807  243.83  4865.3  246.21  4892.4   245.2  4901.1  245.27  4907.2  246.31
  4936.9  244.57  4972.7  243.38    5056  243.47  5059.3  242.76  5121.2  244.82
  5161.2  246.36  5197.6  248.73  5221.3   249.1  5274.1  251.84  5327.5  255.79
  5345.1  256.16  5381.8  259.83  5397.9  260.46  5414.4  263.09  5445.3  266.34
  5450.7  265.78  5479.8  268.26  5603.6  273.07    5651   276.7  5666.8   276.9
#Mann= 5 ,-1 , 0
  4260.3     .17       0  4768.4     .15       0  4936.9     .09       0
  5121.2     .15       0  5161.2     .17       0
Bank Sta=4936.9,5121.2
XS Rating Curve= 0 ,0
Exp/Cntr=0.3,0.1

Type RM Length L Ch R = 1 ,9743    ,463,463,463
BEGIN DESCRIPTION:
MAPLE BRANCH 18.0
END DESCRIPTION:
XS GIS Cut Line= 3
      3788680.31     10209959.77      3787787.64     10210143.09
       3787344.4     10210373.83
#Sta/Elev= 30
  4088.7  277.82  4123.5  276.97  4142.3  275.05  4213.7  271.69  4254.6  271.04
  4314.8  268.13  4387.3  262.11    4471  256.83  4530.2  250.07  4560.8  249.31
  4581.2  247.11  4611.9  245.48  4629.3  245.53  4717.8  242.26  4785.4  244.42
  4868.9  244.63  4928.3  241.95  4954.9  243.58  4969.7  243.96    4986  241.21
  5022.3  243.87  5191.4  255.91  5309.7  266.29  5360.5  268.53    5376  269.83
  5383.1   271.4  5405.6  271.39  5414.6  272.87  5464.4  273.81  5499.7  275.61
#Mann= 5 ,-1 , 0
  4088.7     .17       0  4629.3     .15       0  4954.9     .17       0
  4969.7     .09       0  5022.3     .17       0
Bank Sta=4969.7,5022.3
XS Rating Curve= 0 ,0
Exp/Cntr=0.3,0.1

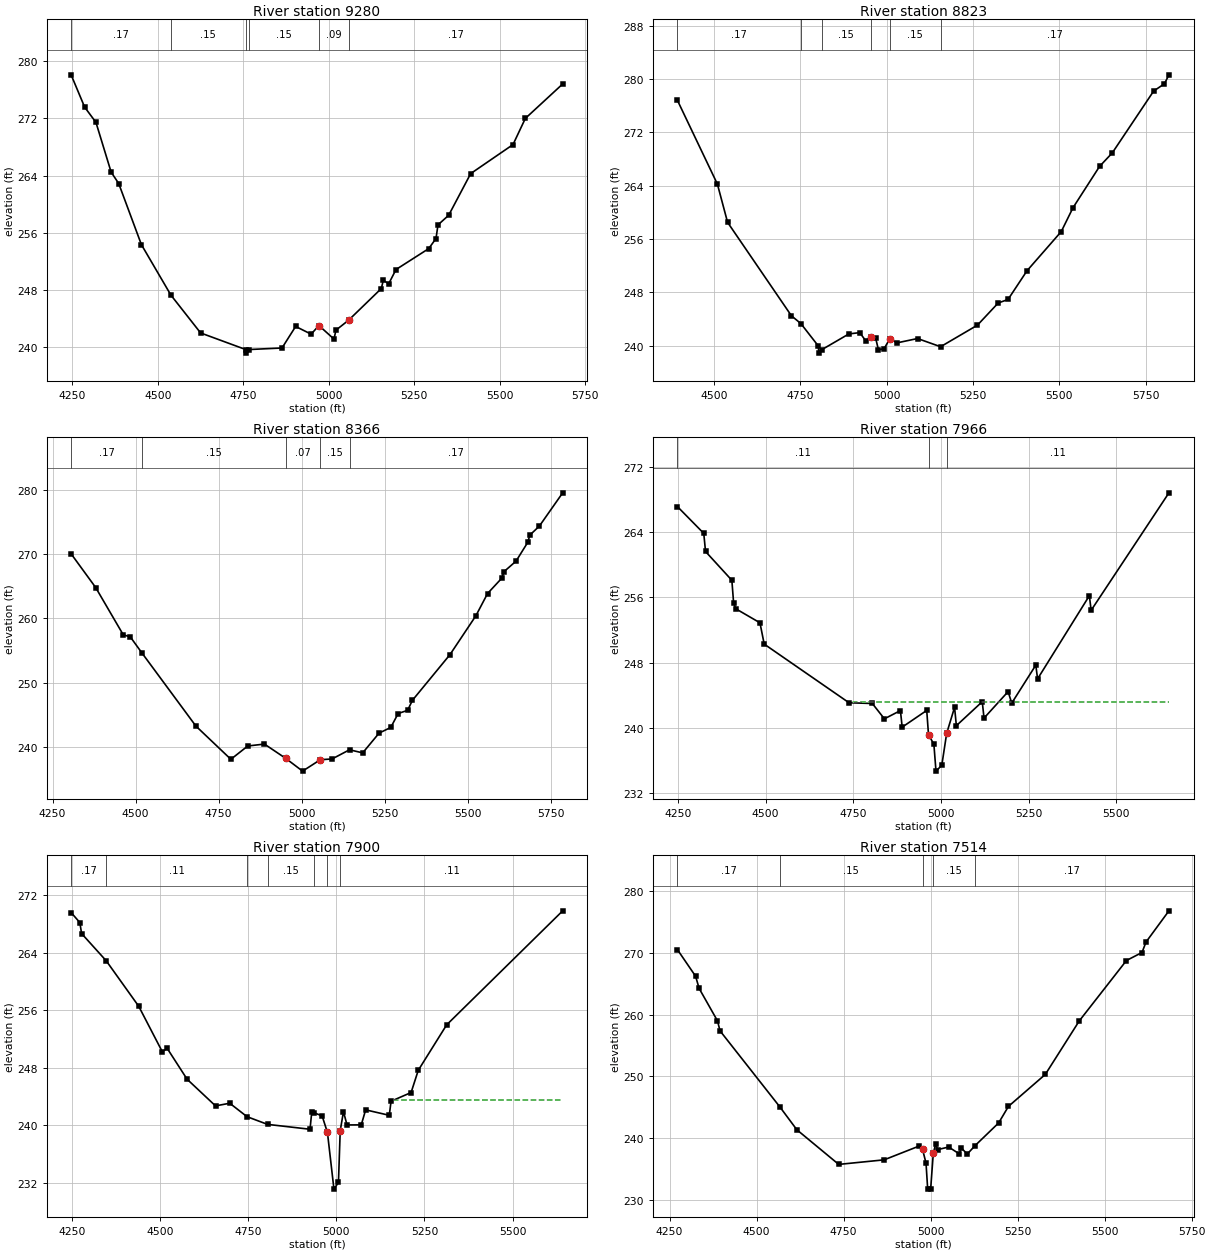
Type RM Length L Ch R = 1 ,9280    ,457,457,457
BEGIN DESCRIPTION:
MAPLE BRANCH 17.0
END DESCRIPTION:
XS GIS Cut Line= 3
       3788323.6     10209402.46      3787642.86     10209726.44
      3787295.04     10210316.33
#Sta/Elev= 30
  4246.1  278.12  4285.7  273.59  4318.8  271.45  4363.2  264.48  4385.4  262.88
  4451.8  254.31  4538.2  247.23  4625.1  241.93  4757.3   239.6  4757.8   239.1
  4765.5   239.6  4863.3  239.82  4903.2  242.84  4948.6  241.76  4971.3  242.97
  5015.4  241.07  5021.2  242.32  5058.3  243.72    5154  248.16  5159.8  249.32
  5175.5  248.82  5196.9  250.82  5292.6  253.75    5314  255.17  5319.8  257.08
  5351.1  258.43  5415.5  264.27  5539.4  268.34  5575.5  272.01  5684.8  276.84
#Mann= 6 ,-1 , 0
  4246.1     .17       0  4538.2     .15       0  4757.3     .12       0
  4765.5     .15       0  4971.3     .09       0  5058.3     .17       0
Bank Sta=4971.3,5058.3
XS Rating Curve= 0 ,0
Exp/Cntr=0.3,0.1

Type RM Length L Ch R = 1 ,8823    ,457,457,457
BEGIN DESCRIPTION:
MAPLE BRANCH 16.0
END DESCRIPTION:
XS GIS Cut Line= 3
       3788167.3     10209061.34      3787605.86     10209288.88
      3786866.05     10209636.47
#Sta/Elev= 30
  4394.2  276.83  4510.1  264.24  4539.6   258.5  4724.5  244.47  4751.7  243.31
  4802.2  239.95  4803.9  238.87  4811.8  239.37  4890.7  241.75  4922.3  241.95
  4938.9  240.76  4954.7  241.29  4968.4   241.1  4976.3  239.38  4992.5  239.52
  5008.8  240.97  5030.9  240.42  5089.6  241.06  5156.3  239.83    5263  243.07
  5323.2   246.4  5351.5  246.92  5406.6  251.24  5505.6  257.11  5539.5  260.68
  5616.5  266.89  5653.5  268.93  5773.1   278.2  5804.4   279.3  5817.4  280.64
#Mann= 6 ,-1 , 0
  4394.2     .17       0  4751.7     .15       0  4811.8     .15       0
  4954.7     .09       0  5008.8     .15       0  5156.3     .17       0
Bank Sta=4954.7,5008.8
XS Rating Curve= 0 ,0
Exp/Cntr=0.3,0.1

Type RM Length L Ch R = 1 ,8366    ,400,400,400
BEGIN DESCRIPTION:
MAPLE BRANCH 15.0
END DESCRIPTION:
XS GIS Cut Line= 3
      3788018.86     10208754.05      3787351.68     10208946.22
      3786845.37     10209547.16
#Sta/Elev= 30
  4305.7  270.06  4379.6  264.82  4462.8  257.45  4483.7  257.15    4519  254.63
  4681.4  243.26  4786.7  238.09  4837.5  240.16  4887.7  240.46    4952  238.23
  5002.6  236.25  5056.2  238.03  5091.3  238.14  5143.9  239.57  5183.6  239.09
  5233.1  242.17  5268.2  243.05  5290.3  245.21  5318.9  245.71  5333.2  247.26
  5446.3  254.37  5524.4  260.42  5559.5  263.88  5602.4  266.27  5608.9  267.28
  5645.3  268.92  5680.4  271.83    5687  272.98  5715.5  274.37  5785.8  279.55
#Mann= 5 ,-1 , 0
  4305.7     .17       0    4519     .15       0    4952     .07       0
  5056.2     .15       0  5143.9     .17       0
Bank Sta=4952,5056.2
XS Rating Curve= 0 ,0
Exp/Cntr=0.3,0.1

Type RM Length L Ch R = 1 ,7966    ,66,66,66
BEGIN DESCRIPTION:
Mapping XS 511f3720
END DESCRIPTION:
XS GIS Cut Line= 3
      3787973.48      10208486.1      3787228.04     10208580.55
      3786583.34     10208664.91
#Sta/Elev= 30
  4248.6  267.13  4323.9  263.84  4328.9  261.62    4404  258.09    4409  255.29
  4415.6  254.59  4484.1  252.88  4496.2  250.27  4738.1  243.08  4804.5  242.99
  4838.9  241.11  4884.6  242.12  4889.6  240.09  4959.6  242.14  4964.7  239.16
    4980     238    4986   234.7  5002.6  235.42 5016.42  239.32    5039  242.52
  5044.1  240.27  5117.9  243.21    5123   241.2  5191.7  244.45  5201.9  243.03
  5270.6  247.69  5275.7  246.01  5423.3   256.2  5428.4  254.41  5650.2  268.81
#Mann= 3 ,-1 , 0
  4248.6     .11       0  4964.7     .06       0 5016.42     .11       0
#XS Ineff= 3 ,-1
  4748.2  4729.4   243.2  5117.9  5191.7  243.21  5191.7  5242.2  244.45
Permanent Ineff=
       F       F       F
Bank Sta=4964.7,5016.42
XS Rating Curve= 0 ,0
Exp/Cntr=0.3,0.1

Type RM Length L Ch R = 1 ,7900    ,386,386,386
BEGIN DESCRIPTION:
MAPLE BRANCH 14.0
END DESCRIPTION:
XS GIS Cut Line= 3
      3787964.26     10208422.65      3787218.16      10208515.1
      3786581.94     10208602.49
#Sta/Elev= 30
  4248.2  269.57  4272.9  268.18  4277.9  266.65  4347.7  262.86  4439.9  256.53
  4506.6  250.22  4520.8  250.66  4577.1  246.38  4657.7  242.67    4698  243.04
    4747  241.17  4805.1   240.1  4925.7  239.42  4930.7  241.89  4936.6  241.72
    4960  241.28 4975.06  238.97  4993.5  231.09  5006.3  232.02  5011.3  239.21
  5020.5  241.87  5030.6  240.02    5071  240.03  5083.4  242.12  5150.4  241.36
  5155.5  243.32  5212.3  244.53  5232.6  247.62  5313.2  253.95  5642.2  269.81
#Mann= 7 ,-1 , 0
  4248.2     .17       0  4347.7     .11       0    4747     .17       0
  4805.1     .15       0  4936.6     .11       0 4975.06     .06       0
  5011.3     .11       0
#XS Ineff= 2 , 0
       0    4698  243.04  5161.8       0  243.48
Permanent Ineff=
       F       F
Bank Sta=4975.06,5011.3
XS Rating Curve= 0 ,0
Exp/Cntr=0.3,0.1

Type RM Length L Ch R = 1 ,7514    ,470,470,470
BEGIN DESCRIPTION:
MAPLE BRANCH 13.0
END DESCRIPTION:
XS GIS Cut Line= 3
      3787910.13     10208224.73      3787184.66     10208169.01
      3786568.16     10208466.91
#Sta/Elev= 30
  4272.4  270.58  4324.8  266.25  4334.9  264.28  4387.7  259.01    4395  257.39
  4566.7  245.07  4615.7  241.35    4736  235.73  4866.4  236.47  4966.7   238.7
  4976.7  238.19  4986.8  235.94  4991.6  231.72  5000.1  231.72  5007.6   237.5
  5014.7  239.07  5020.2  238.13    5052  238.55  5082.5  237.43    5088  238.42
  5105.1   237.4    5128  238.79  5195.5  242.46  5223.6  245.14  5329.6  250.33
    5427     259  5562.6   268.8  5607.3   270.1  5618.9   271.8  5684.7  276.86
#Mann= 5 ,-1 , 0
  4272.4     .17       0  4566.7     .15       0  4976.7     .09       0
  5007.6     .15       0    5128     .17       0
Bank Sta=4976.7,5007.6
XS Rating Curve= 0 ,0
Exp/Cntr=0.3,0.1