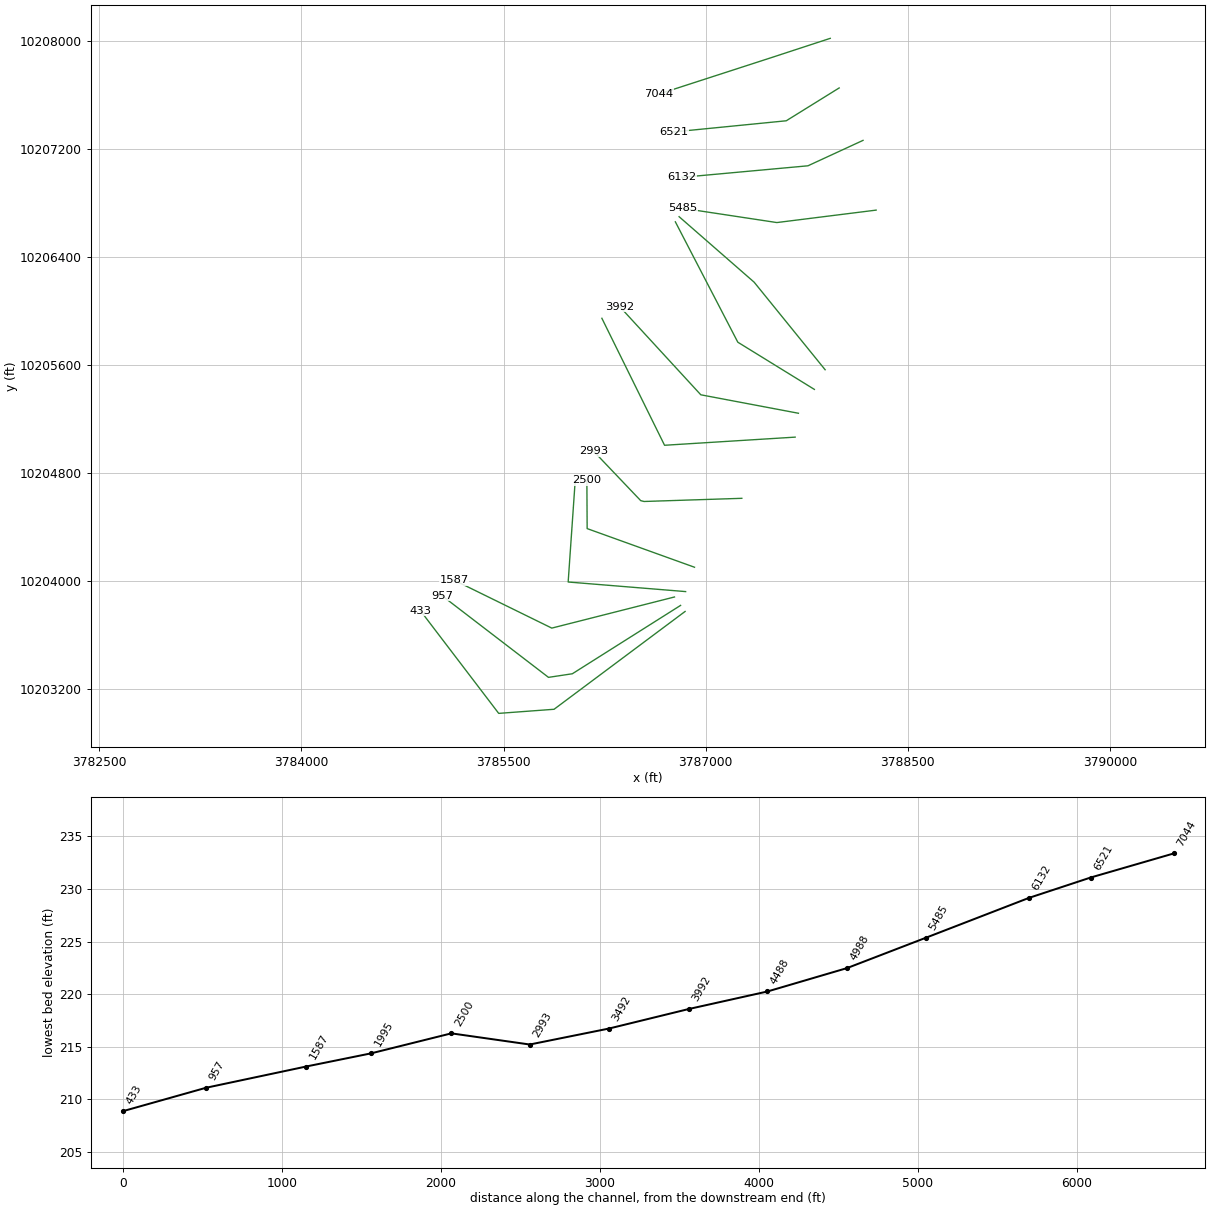
HEC-RAS study MAPLE BRANCH.prj: MAPLE BRANCH Base Level Engineering

--- MAPLE BRANCH.g01 (geometry) --- (continued)

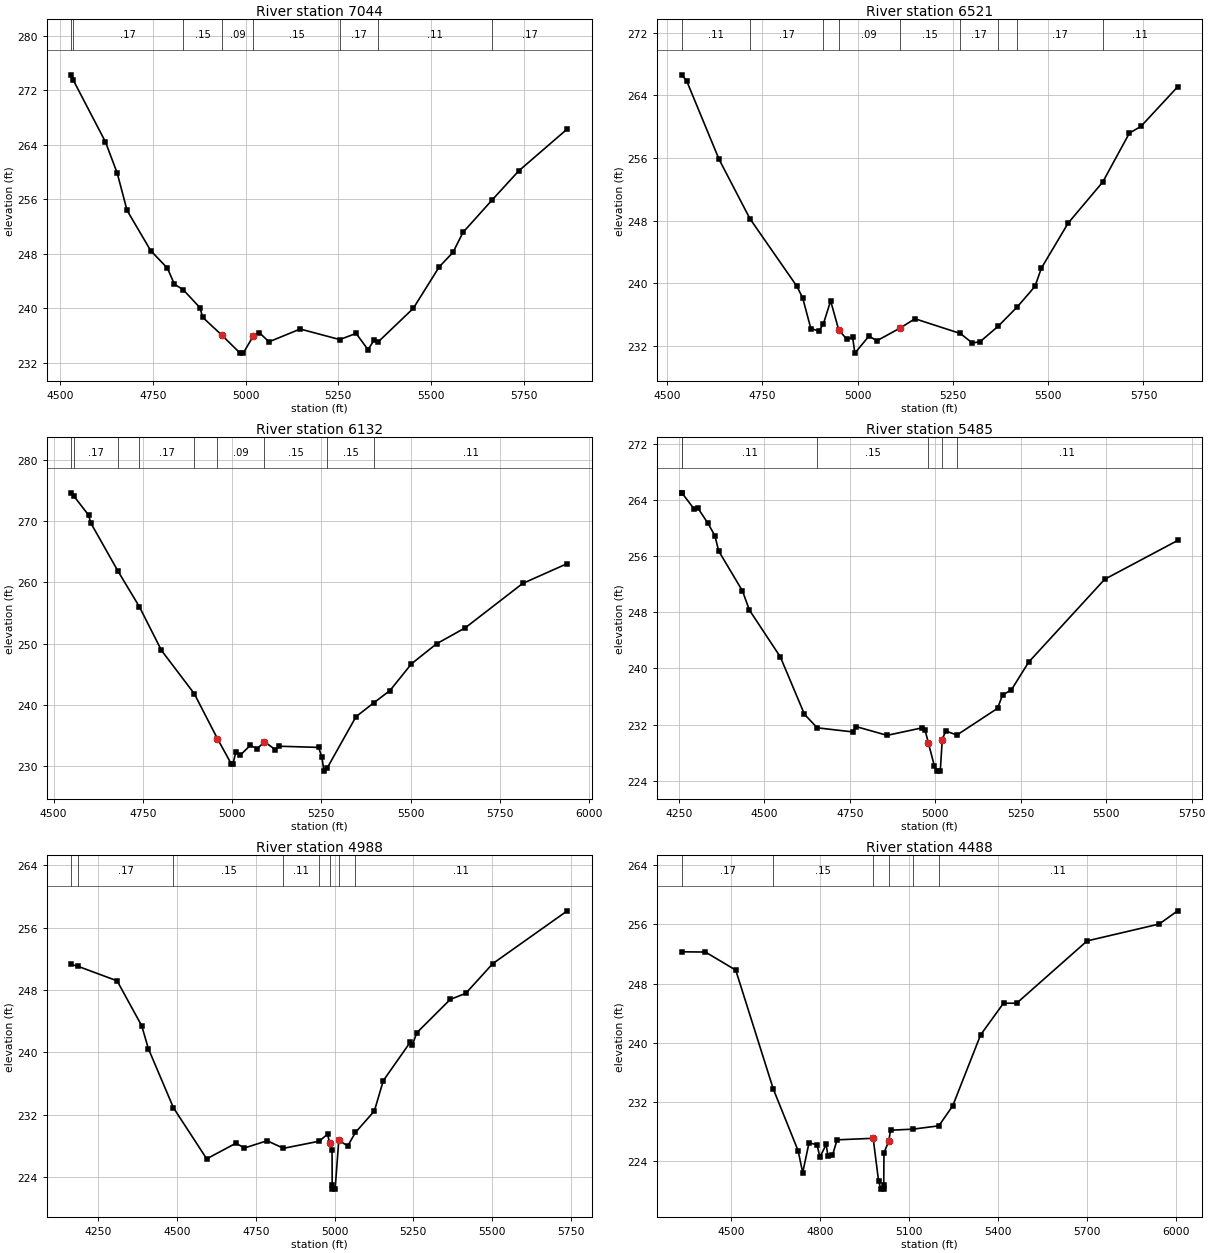
Type RM Length L Ch R = 1 ,7044    ,523,523,523
BEGIN DESCRIPTION:
MAPLE BRANCH 12.0
END DESCRIPTION:
XS GIS Cut Line= 3
      3787924.01     10208023.34        3787478.     10207877.34
      3786653.19     10207610.15
#Sta/Elev= 30
  4530.7  274.26  4536.2  273.45  4622.5  264.42  4654.3  259.82  4680.9  254.34
  4744.6  248.43  4789.7  245.85  4808.4   243.5  4831.9  242.71  4877.3  240.05
  4884.4  238.65  4935.8  236.04  4985.4  233.38  4993.9  233.38  5021.2  235.92
  5036.8  236.41  5063.2  235.04  5147.3  236.92    5254  235.37  5297.9  236.28
  5329.9   233.9    5347  235.32  5356.5  234.98  5452.1  239.96  5521.9  246.05
  5559.1  248.19  5585.9  251.11    5664  255.85    5736  260.14    5867  266.31
#Mann= 8 ,-1 , 0
  4530.7     .11       0  4536.2     .17       0  4831.9     .15       0
  4935.8     .09       0  5021.2     .15       0    5254     .17       0
  5356.5     .11       0    5664     .17       0
Bank Sta=4935.8,5021.2
XS Rating Curve= 0 ,0
Exp/Cntr=0.3,0.1

Type RM Length L Ch R = 1 ,6521    ,389,389,389
BEGIN DESCRIPTION:
MAPLE BRANCH 11.0
END DESCRIPTION:
XS GIS Cut Line= 3
      3787989.96     10207655.28      3787597.49     10207411.73
      3786761.87       10207329.
#Sta/Elev= 30
  4538.1  266.64    4551  265.88    4636  255.86  4717.2  248.26  4840.4  239.63
  4855.7  238.13    4877  234.23  4898.2  233.91  4909.8   234.8    4929  237.77
  4950.2  234.05  4971.5  232.87  4986.8  233.09  4992.5  231.09  5029.8  233.28
  5049.9  232.66  5110.2  234.26  5150.4  235.48  5269.2   233.6  5301.1  232.38
  5321.2  232.55  5368.8  234.53    5419  237.01  5465.2  239.61    5482  241.94
  5552.3   247.7  5643.1  252.95  5713.1   259.2  5743.3  260.05  5839.7  265.11
#Mann= 9 ,-1 , 0
  4538.1     .11       0  4717.2     .17       0  4909.8     .15       0
  4950.2     .09       0  5110.2     .15       0  5269.2     .17       0
  5368.8     .11       0    5419     .17       0  5643.1     .11       0
Bank Sta=4950.2,5110.2
XS Rating Curve= 0 ,0
Exp/Cntr=0.3,0.1

Type RM Length L Ch R = 1 ,6132    ,647,647,647
BEGIN DESCRIPTION:
MAPLE BRANCH 10.0
END DESCRIPTION:
XS GIS Cut Line= 3
      3788167.05     10207266.39      3787758.37     10207077.79
      3786823.29     10206992.08
#Sta/Elev= 30
  4549.9  274.65  4556.6  274.15  4598.5  270.98  4604.1  269.75  4680.4  261.86
  4740.5  256.02  4802.3  248.89  4894.1  241.82  4959.2  234.45  4997.5  230.36
  5002.8  230.36  5010.6  232.28  5022.2  231.71  5050.7  233.34  5070.8  232.84
  5090.9  233.95    5121  232.67  5132.2  233.22  5242.3  233.03  5251.6  231.47
  5257.3  229.15  5266.4  229.65  5347.2  238.05    5397  240.32  5442.4  242.33
  5502.6   246.7  5572.9  249.97  5653.2  252.58  5813.9  259.83    5939  263.08
#Mann= 9 ,-1 , 0
  4549.9     .11       0  4556.6     .17       0  4680.4     .11       0
  4740.5     .17       0  4894.1     .15       0  4959.2     .09       0
  5090.9     .15       0  5266.4     .15       0    5397     .11       0
Bank Sta=4959.2,5090.9
XS Rating Curve= 0 ,0
Exp/Cntr=0.3,0.1

Type RM Length L Ch R = 1 ,5485    ,497,497,497
BEGIN DESCRIPTION:
MAPLE BRANCH 9.0
END DESCRIPTION:
XS GIS Cut Line= 3
      3788264.23     10206749.03       3787527.9     10206656.71
       3786826.8     10206762.92
#Sta/Elev= 30
  4257.9  265.03  4258.4  265.03  4294.6   262.7  4304.6  262.91  4334.9  260.67
    4355  258.92  4366.1  256.74  4435.7  251.05  4455.8  248.34  4546.5  241.65
  4617.1  233.47  4654.5  231.54  4758.2  230.96  4768.6  231.71    4859  230.47
  4959.7  231.52  4969.8  231.26  4979.9  229.35  4997.5  226.06  5005.8  225.37
  5014.5  225.37  5020.3  229.87  5030.4   231.1    5063  230.51  5182.1  234.32
  5196.7  236.22  5222.6  236.95  5273.1   240.9  5495.6  252.71  5709.1  258.24
#Mann= 6 ,-1 , 0
  4257.9     .17       0  4258.4     .11       0  4654.5     .15       0
  4979.9     .09       0  5020.3     .15       0    5063     .11       0
Bank Sta=4979.9,5020.3
XS Rating Curve= 0 ,0
Exp/Cntr=0.3,0.1

Type RM Length L Ch R = 1 ,4988    ,500,500,500
BEGIN DESCRIPTION:
MAPLE BRANCH 8.0
END DESCRIPTION:
XS GIS Cut Line= 3
      3787885.83     10205564.97      3787359.26     10206214.42
      3786802.66     10206700.25
#Sta/Elev= 30
  4163.9  251.27  4185.8  251.02  4309.2  249.17  4387.5   243.4  4408.4  240.49
  4488.2   232.9  4593.7  226.36  4686.4  228.36  4713.7  227.75  4785.6  228.68
  4837.6  227.71    4951  228.62  4977.4  229.52  4983.8  228.44  4991.8  227.45
  4992.2  222.98  4992.7  222.48  5001.5  222.48  5013.1  228.72  5041.6  228.02
    5066  229.74  5126.1  232.49  5154.5  236.38    5240   241.3  5246.6  240.92
  5260.9  242.52  5367.2  246.79  5416.5  247.57    5502  251.37  5738.8  258.14
#Mann= 8 ,-1 , 0
  4163.9     .11       0  4185.8     .17       0  4488.2     .15       0
  4837.6     .11       0    4951     .15       0  4983.8     .09       0
  5013.1     .15       0    5066     .11       0
Bank Sta=4983.8,5013.1
XS Rating Curve= 0 ,0
Exp/Cntr=0.3,0.1

Type RM Length L Ch R = 1 ,4488    ,496,496,496
BEGIN DESCRIPTION:
MAPLE BRANCH 7.0
END DESCRIPTION:
XS GIS Cut Line= 3
      3787805.95     10205419.16      3787238.17     10205769.19
      3786774.71     10206662.18
#Sta/Elev= 30
    4333  252.28    4413  252.25  4515.3  249.81  4642.2  233.74  4725.8  225.44
  4741.2  222.48  4762.5  226.51  4789.6  226.24  4799.2  224.57  4820.4  226.29
  4826.3  224.76  4841.7  224.82  4857.1  226.91  4978.9  227.12  4997.3  221.31
  5005.3  220.26  5014.1  220.26  5014.6  220.76  5015.3  225.14  5031.8  226.78
  5037.4  228.21  5112.6  228.35  5200.5   228.8  5247.3   231.5  5341.5  241.08
  5418.7  245.35  5462.9  245.34  5700.6  253.75  5943.9  256.03  6006.1  257.81
#Mann= 6 ,-1 , 0
    4333     .17       0  4642.2     .15       0  4978.9     .09       0
  5031.8     .15       0  5112.6     .17       0  5200.5     .11       0
Bank Sta=4978.9,5031.8
XS Rating Curve= 0 ,0
Exp/Cntr=0.3,0.1

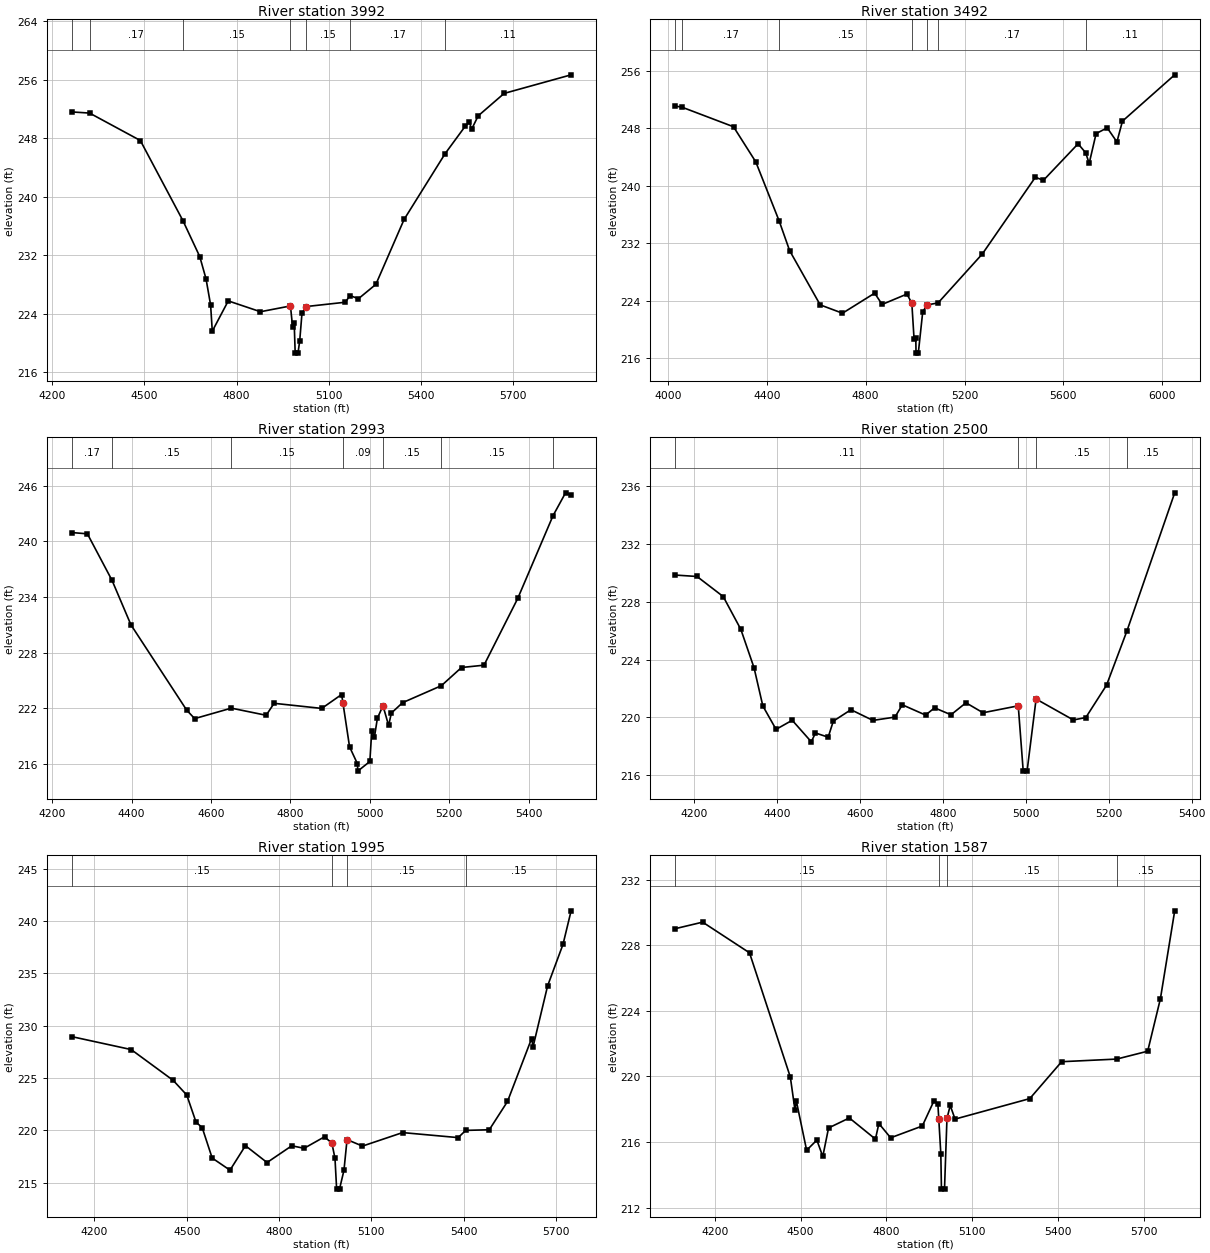
Type RM Length L Ch R = 1 ,3992    ,500,500,500
BEGIN DESCRIPTION:
MAPLE BRANCH 6.0
END DESCRIPTION:
XS GIS Cut Line= 3
       3787687.9     10205242.08      3786963.72     10205378.95
      3786362.19       10206033.
#Sta/Elev= 30
    4263  251.57  4321.8  251.41  4486.9  247.66  4625.4  236.71  4680.3  231.79
  4700.7  228.74  4715.6  225.17    4721  221.59    4773  225.73  4877.8  224.25
  4975.4  225.04  4982.5  222.12  4987.6  222.66  4990.8  218.59  4999.9  218.59
  5005.5  220.26  5012.9  224.04    5027  224.96  5154.1  225.55  5169.1  226.46
  5196.6  226.03  5253.3  227.99  5345.2  236.87  5478.6  245.86  5543.7  249.59
  5557.9  250.16  5564.7  249.18  5586.2  251.03  5670.7   254.1  5888.6  256.64
#Mann= 7 ,-1 , 0
    4263     .11       0  4321.8     .17       0  4625.4     .15       0
  4975.4     .09       0    5027     .15       0  5169.1     .17       0
  5478.6     .11       0
Bank Sta=4975.4,5027
XS Rating Curve= 0 ,0
Exp/Cntr=0.3,0.1

Type RM Length L Ch R = 1 ,3492    ,499,499,499
BEGIN DESCRIPTION:
MAPLE BRANCH 5.0
END DESCRIPTION:
XS GIS Cut Line= 3
      3787663.59       10205065.      3786694.68     10205004.61
      3786229.76     10205946.52
#Sta/Elev= 30
  4029.2  251.09  4055.5  250.96  4265.4  248.22  4355.6  243.33  4450.2  235.11
  4492.5  230.99  4616.1  223.45  4706.3  222.29  4836.5  225.08  4866.6  223.51
  4966.8  224.95  4986.8  223.71  4995.9  218.71  5002.9  218.84  5003.9  216.74
    5013  216.74  5030.9  222.46  5047.8  223.43  5093.3  223.73  5272.3  230.54
  5486.7   241.2  5519.2  240.77  5659.5  245.85    5690  244.61  5704.4  243.13
  5732.4  247.27  5777.3  248.07  5816.6  246.11    5839     249  6050.4  255.44
#Mann= 7 ,-1 , 0
  4029.2     .11       0  4055.5     .17       0  4450.2     .15       0
  4986.8     .09       0  5047.8     .15       0  5093.3     .17       0
    5690     .11       0
Bank Sta=4986.8,5047.8
XS Rating Curve= 0 ,0
Exp/Cntr=0.3,0.1

Type RM Length L Ch R = 1 ,2993    ,493,493,493
BEGIN DESCRIPTION:
MAPLE BRANCH 4.0
END DESCRIPTION:
XS GIS Cut Line= 4
      3787267.85     10204611.07      3786542.31     10204587.56
      3786517.57     10204594.05      3786167.82      10204961.1
#Sta/Elev= 30
  4248.5  240.94  4288.5   240.8  4350.6  235.78  4398.2  230.99  4538.7  221.79
  4558.7  220.88    4651  222.01  4738.8  221.24  4758.8  222.53  4878.8  221.98
  4928.9  223.48 4932.32  222.55  4948.9  217.84  4968.9     216  4969.6  215.22
    5000  216.26  5004.8  219.54  5011.7  218.93    5019  220.92  5033.1  222.27
  5047.3  220.14  5054.2  221.48  5082.5   222.6  5180.2  224.43  5230.9  226.39
  5287.6  226.64  5372.5  233.83  5461.5  242.76    5493  245.22    5507  244.97
#Mann= 7 ,-1 , 0
  4248.5     .17       0  4350.6     .15       0    4651     .15       0
 4932.32     .09       0  5033.1     .15       0  5180.2     .15       0
  5461.5     .17       0
Bank Sta=4932.32,5033.1
XS Rating Curve= 0 ,0
Exp/Cntr=0.3,0.1

Type RM Length L Ch R = 1 ,2500    ,505,505,505
BEGIN DESCRIPTION:
MAPLE BRANCH 5.5
END DESCRIPTION:
XS GIS Cut Line= 3
      3786917.05     10204099.73      3786120.48     10204386.47
      3786118.44     10204745.56
#Sta/Elev= 30
  4153.4  229.85  4206.3  229.75  4269.5  228.36    4312  226.09  4343.9  223.43
  4365.1  220.79    4397  219.17    4436   219.8    4482  218.31  4492.1  218.92
  4522.8  218.63  4535.2  219.74  4577.7  220.53  4630.8  219.79    4684  220.02
  4701.7  220.87  4757.8  220.16  4779.6  220.66  4819.2  220.18  4855.3  221.01
  4896.5  220.32  4981.5   220.8  4993.5  216.28  5002.8  216.28  5024.6  221.27
  5114.6  219.82  5144.6  219.99  5194.6  222.23  5243.8  225.98  5359.1  235.54
#Mann= 4 ,-1 , 0
  4153.4     .11       0  4981.5     .09       0  5024.6     .15       0
  5243.8     .15       0
Bank Sta=4981.5,5024.6
XS Rating Curve= 0 ,0
Exp/Cntr=0.3,0.1

Type RM Length L Ch R = 1 ,1995    ,408,408,408
BEGIN DESCRIPTION:
MAPLE BRANCH 2.0
END DESCRIPTION:
XS GIS Cut Line= 3
      3786851.06     10203919.17      3785979.65      10203990.2
      3786031.54      10204737.3
#Sta/Elev= 30
  4125.7  228.95  4319.5  227.71  4455.9  224.77  4500.1  223.37  4530.2  220.78
  4550.3  220.25  4582.7  217.35  4640.6  216.19  4690.8  218.53    4761  216.92
  4841.3  218.52  4881.4  218.28  4947.9  219.38  4971.7  218.76  4981.7  217.33
  4987.1  214.38  4996.4  214.38  5010.9  216.18  5020.9  219.11    5071  218.49
  5201.4  219.78  5381.8   219.3  5406.7  219.99  5483.1  220.05  5542.2  222.75
  5620.4  228.75  5625.4  227.99  5672.5  233.79  5722.6  237.76  5748.9  240.96
#Mann= 4 ,-1 , 0
  4125.7     .15       0  4971.7     .09       0  5020.9     .15       0
  5406.7     .15       0
Bank Sta=4971.7,5020.9
XS Rating Curve= 0 ,0
Exp/Cntr=0.3,0.1

Type RM Length L Ch R = 1 ,1587    ,630,630,630
BEGIN DESCRIPTION:
MAPLE BRANCH 1.0
END DESCRIPTION:
XS GIS Cut Line= 3
      3786768.33     10203879.17      3785858.27     10203648.28
      3785132.98     10204004.17
#Sta/Elev= 30
  4061.1  229.01  4157.3  229.41  4321.2  227.54    4464  219.96  4479.9  217.98
  4485.1  218.49  4520.9   215.5  4556.7  216.12  4577.4  215.12  4597.6  216.86
  4670.3  217.47  4761.5  216.18  4773.5  217.13  4814.7  216.26  4925.4  216.98
  4966.3  218.52  4979.8  218.33 4982.95  217.42  4990.1  215.29  4992.3  213.13
    5003  213.13  5011.6  217.44    5023  218.23  5039.9   217.4  5301.2  218.65
  5412.6   220.9    5605  221.06  5713.4  221.54  5757.9  224.74  5807.9   230.1
#Mann= 4 ,-1 , 0
  4061.1     .15       0 4982.95     .09       0  5011.6     .15       0
    5605     .15       0
Bank Sta=4982.95,5011.6
XS Rating Curve= 0 ,0
Exp/Cntr=0.3,0.1

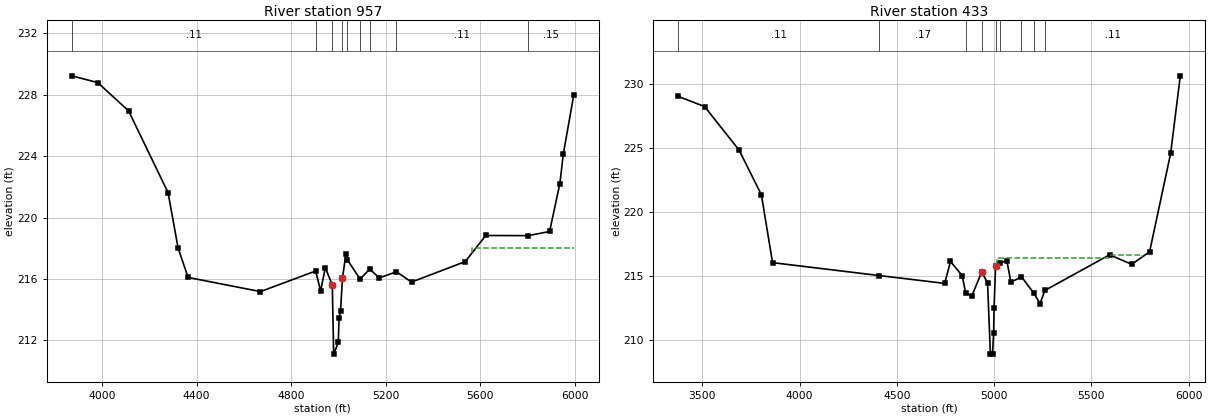
Type RM Length L Ch R = 1 ,957     ,524,524,524
BEGIN DESCRIPTION:
MAPLE BRANCH 2.5
END DESCRIPTION:
XS GIS Cut Line= 4
      3786813.47     10203816.66      3786010.64     10203309.59
      3785833.69      10203282.9      3785042.75     10203889.55
#Sta/Elev= 30
  3871.5  229.22  3981.8  228.78  4112.4  226.94  4279.5  221.62  4321.9  218.02
  4364.2   216.1  4670.6  215.18  4904.3  216.52    4925  215.22  4945.2  216.74
  4974.6   215.6  4980.3  211.11    5000  211.87  5003.1  213.43  5009.4  213.94
  5017.7  216.06  5032.2  217.64  5038.2  217.25  5092.2  215.99  5132.8  216.64
  5173.5  216.07    5246  216.47  5309.8   215.8    5537  217.13  5624.1  218.83
  5803.8  218.82  5894.2  219.09  5937.7  222.21  5952.2  224.13  5996.8     228
#Mann= 9 ,-1 , 0
  3871.5     .11       0  4904.3     .17       0  4974.6     .09       0
  5017.7     .17       0  5038.2     .15       0  5092.2     .11       0
  5132.8     .17       0    5246     .11       0  5803.8     .15       0
#XS Ineff= 2 , 0
       0                    5566       0  218.02
Permanent Ineff=
       F       F
Bank Sta=4974.6,5017.7
XS Rating Curve= 0 ,0
Exp/Cntr=0.3,0.1

Type RM Length L Ch R = 1 ,433     ,0,0,0
BEGIN DESCRIPTION:
MAPLE BRANCH 1.5
END DESCRIPTION:
XS GIS Cut Line= 4
      3786846.95     10203771.67      3785875.08     10203046.11
      3785464.34     10203015.71      3784883.86     10203777.31
#Sta/Elev= 30
  3375.3     229  3511.5   228.2    3689   224.8  3803.6  221.31  3860.9  216.02
  4410.6  215.01  4745.8   214.4  4775.9  216.11    4836  215.01    4854  213.63
  4886.2  213.44  4936.3   215.3  4966.4  214.44  4981.1  208.88  4991.9  208.88
  4997.6   210.5    5000   212.5  5007.7  215.75  5032.6  216.03  5065.9  216.15
  5086.7  214.49    5141  214.92  5204.1  213.64  5236.4  212.82    5261  213.85
  5593.9  216.63  5708.2  215.89  5799.7  216.87  5907.8  224.54  5957.6   230.6
#Mann= 9 ,-1 , 0
  3375.3     .11       0  4410.6     .17       0    4854     .15       0
  4936.3     .09       0  5007.7     .15       0  5032.6     .17       0
    5141     .15       0  5204.1     .17       0    5261     .11       0
#XS Ineff= 2 ,-1
    5016  5593.9  216.36  5593.9  5758.1  216.63
Permanent Ineff=
       T       T
Bank Sta=4936.3,5007.7
XS Rating Curve= 0 ,0
Exp/Cntr=0.3,0.1

Chan Stop Cuts=-1
Use User Specified Reach Order=0
Composite Channel Slope=5