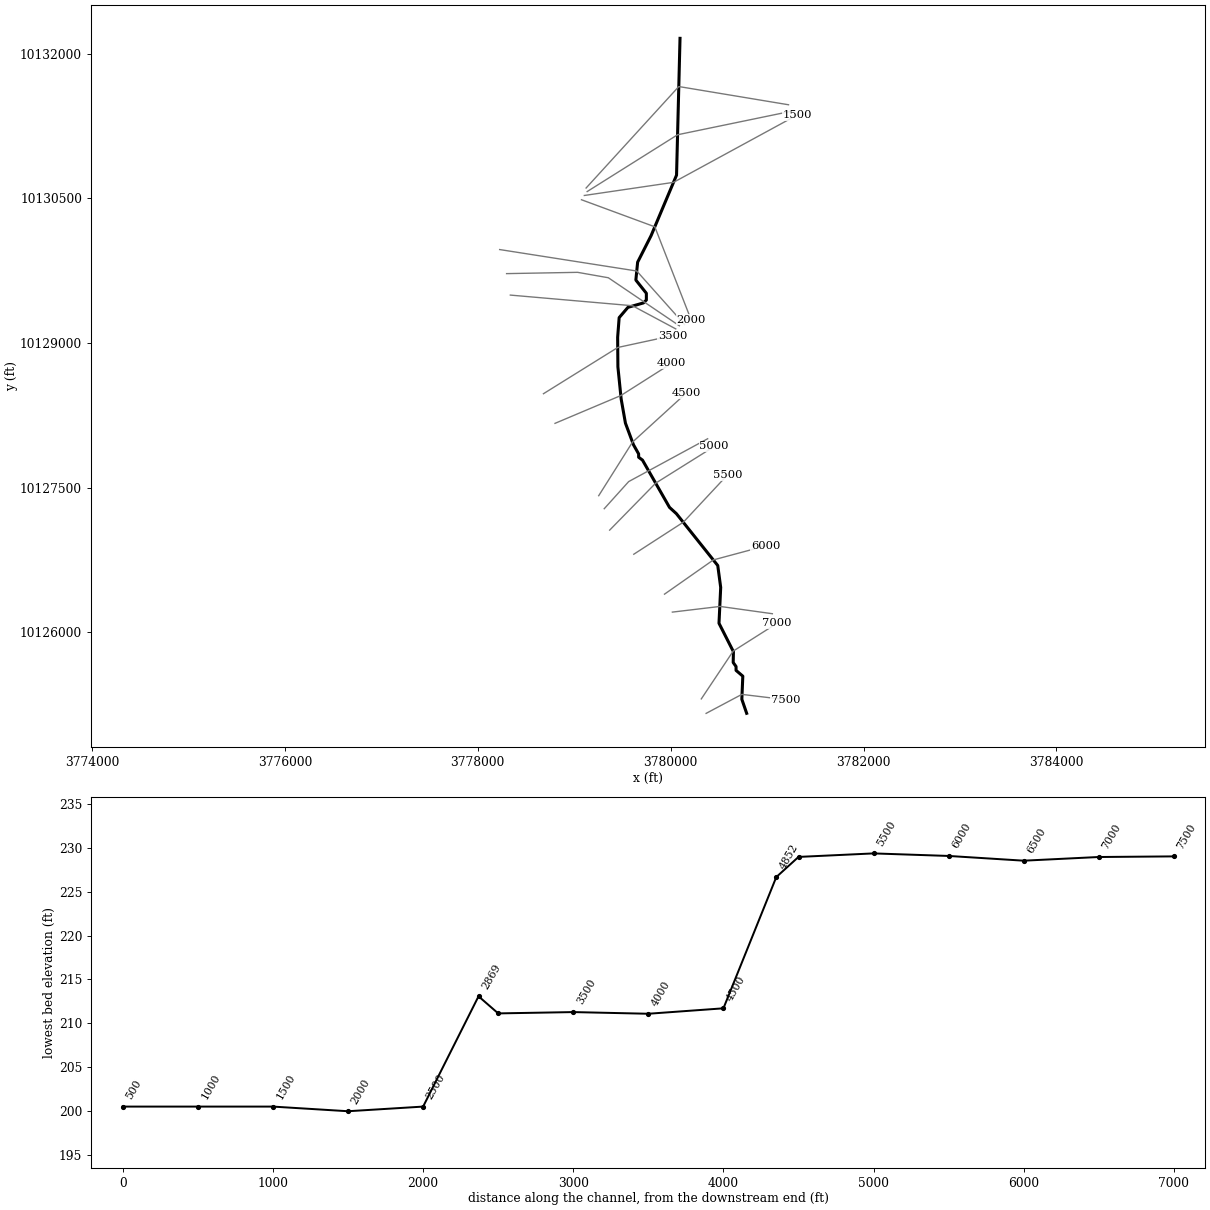
--- MARTIN CREEK TRIBUTARY NO 1.prj (project) ---

Proj Title=MARTIN CREEK TRIBUTARY NO 1 Base Level Engineering
Current Plan=p01
Default Exp/Contr=0.3,0.1
English Units
Geom File=g01
Flow File=f01
Plan File=p01
Y Axis Title=Elevation
X Axis Title(PF)=Main Channel Distance
X Axis Title(XS)=Station
BEGIN DESCRIPTION:
MARTIN CREEK TRIBUTARY NO 1
END DESCRIPTION:
DSS Export Rating Curves= 0
DSS Export Rating Curve Sorted= 0
DSS Export Volume Flow Curves= 0
DXF OffsetX= 0
DXF OffsetY= 0
DXF ScaleX= 1
DXF ScaleY= 10

--- MARTIN CREEK TRIBUTARY NO 1.p01 (plan) ---

Plan Title=Multiple Run
Short Identifier=Multiple
Geom File=g01
Flow File=f01
Subcritical Flow
K Sum by GR= 0
Std Step Tol= 0.01
Critical Tol= 0.01
Num of Std Step Trials= 20
Max Error Tol= 0.3
Flow Tol Ratio= 0.001
Split Flow NTrial= 30
Split Flow Tol= 0.02
Split Flow Ratio= 0.02
Log Output Level= 0
Friction Slope Method= 1
Unsteady Friction Slope Method= 2
Unsteady Bridges Friction Slope Method= 1
Parabolic Critical Depth
Global Vel Dist=  1 , 1 , 1
Global Log Level= 0
CheckData=True
Encroach Param= -1, 0, 0, 0
BEGIN DESCRIPTION:
Multiple Run
END DESCRIPTION:

--- MARTIN CREEK TRIBUTARY NO 1.f01 (steady flow) ---

Flow Title=Multiple
Program Version=4.10
Number of Profiles= 7
Profile Names=10-year,25-year,50-year,1pct_min,100-year,1pct_plu,500-year
River Rch & RM=MARTIN CREEK TRI,Reach-1         ,7500
     457     603     800     350    1058    3195    1907
River Rch & RM=MARTIN CREEK TRI,Reach-1         ,6500
     752    1027    1396     624    1884    5690    3550
River Rch & RM=MARTIN CREEK TRI,Reach-1         ,3000
     964    1332    1824     821    2480    7489    4739
Boundary for River Rch & Prof#=MARTIN CREEK TRI,Reach-1         , 1
Up Type= 0
Dn Type= 3
Dn Slope=0.005
Boundary for River Rch & Prof#=MARTIN CREEK TRI,Reach-1         , 2
Up Type= 0
Dn Type= 3
Dn Slope=0.005
Boundary for River Rch & Prof#=MARTIN CREEK TRI,Reach-1         , 3
Up Type= 0
Dn Type= 3
Dn Slope=0.005
Boundary for River Rch & Prof#=MARTIN CREEK TRI,Reach-1         , 4
Up Type= 0
Dn Type= 3
Dn Slope=0.005
Boundary for River Rch & Prof#=MARTIN CREEK TRI,Reach-1         , 5
Up Type= 0
Dn Type= 3
Dn Slope=0.005
Boundary for River Rch & Prof#=MARTIN CREEK TRI,Reach-1         , 6
Up Type= 0
Dn Type= 3
Dn Slope=0.005
Boundary for River Rch & Prof#=MARTIN CREEK TRI,Reach-1         , 7
Up Type= 0
Dn Type= 3
Dn Slope=0.005
DSS Import GetInterval= 0
DSS Import GetPeak= 0
DSS Import FillOption= 0

--- MARTIN CREEK TRIBUTARY NO 1.g01 (geometry) ---

Geom Title=Existing Conditions
Program Version=4.10

River Reach=MARTIN CREEK TRI,Reach-1
Reach XY= 30
      3780788.23     10125161.84      3780738.23     10125306.84
      3780748.23     10125546.84      3780678.23     10125606.84
      3780678.23     10125646.84      3780648.46     10125688.53
      3780651.07     10125800.51       3780501.3     10126095.28
      3780518.97     10126466.87      3780488.45     10126694.08
      3780059.64     10127231.66      3779988.23     10127296.84
      3779708.23     10127786.84      3779668.23     10127816.84
      3779668.23     10127851.02      3779614.61     10127946.35
      3779531.28      10128170.3      3779487.01      10128420.3
      3779453.15     10128753.64      3779450.55     10129060.93
      3779466.17     10129264.05      3779557.32     10129370.83
      3779718.23     10129416.84      3779748.23     10129446.84
      3779748.23     10129516.84      3779639.32     10129653.74
      3779657.78     10129839.18      3779796.84     10130113.24
       3780061.2     10130741.63      3780097.22     10132159.99

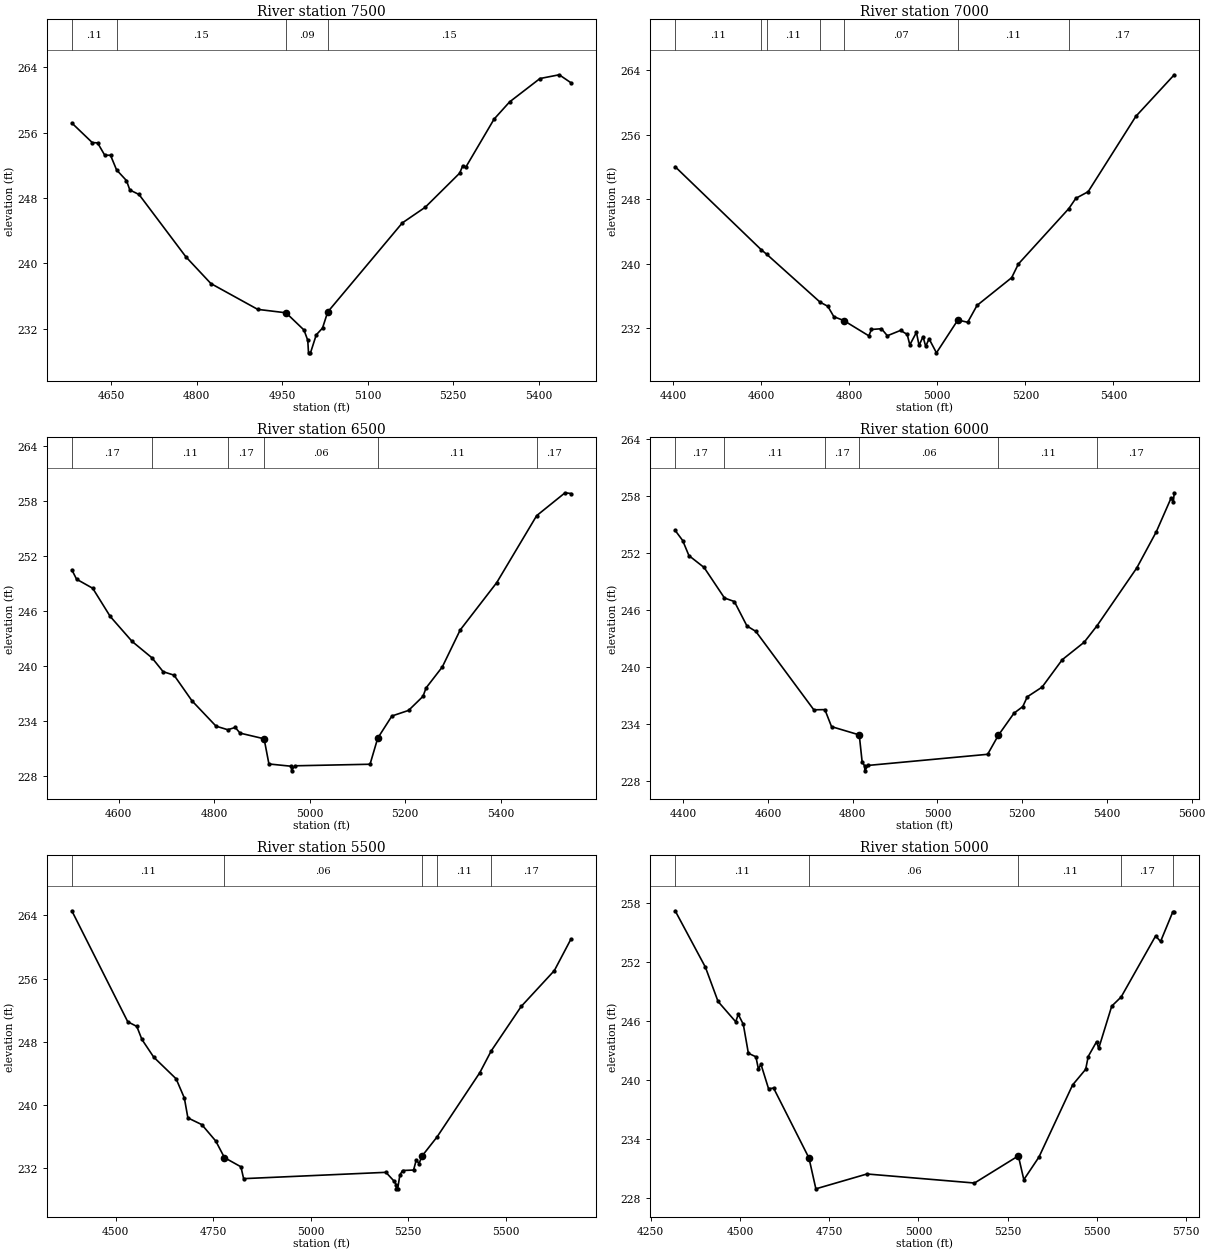
Type RM Length L Ch R = 1 ,7500    ,500,500,500
BEGIN DESCRIPTION:
MARTIN CREEK TRIBUTARY NO 1 15.0
END DESCRIPTION:
XS GIS Cut Line= 3
      3780367.85     10125161.07      3780738.23     10125358.06
      3781191.75     10125303.45
#Sta/Elev= 30
  4580.5  257.17  4616.3  254.78  4625.8  254.73  4638.3  253.23  4648.5  253.22
  4659.1  251.43  4676.5  250.12  4682.4  248.97  4698.5  248.42  4780.8  240.79
  4824.7  237.52  4906.9  234.36  4956.6  233.94  4988.2  231.83  4994.8  230.57
  4996.1  229.04  4999.6  229.04  5009.7  231.24  5020.7  232.07  5029.8  234.04
  5160.8  244.94  5201.1  246.86  5261.5  251.03    5267  251.95  5272.1  251.74
  5321.9  257.64  5349.2  259.75  5402.5  262.61  5436.3  263.07  5456.8   262.1
#Mann= 4 ,-1 , 0
  4580.5     .11       0  4659.1     .15       0  4956.6     .09       0
  5029.8     .15       0
Bank Sta=4956.6,5029.8
XS Rating Curve= 0 ,0
Exp/Cntr=0.3,0.1

Type RM Length L Ch R = 1 ,7000    ,500,500,500
BEGIN DESCRIPTION:
MARTIN CREEK TRIBUTARY NO 1 14.0
END DESCRIPTION:
XS GIS Cut Line= 3
      3780317.88     10125311.11       3780648.6     10125806.69
      3781103.04     10126095.03
#Sta/Elev= 30
  4404.2  252.05  4600.1  241.74  4612.3  241.19  4733.6  235.25  4751.1  234.74
  4764.8  233.45  4787.2  232.98  4844.2  231.08  4850.3  231.87    4873  231.96
  4886.3  231.09  4916.3  231.75  4931.4  231.26  4937.4  229.96  4952.4  231.51
  4958.4  229.89  4967.4  230.98  4973.4  229.78  4981.2   230.7  4997.9  228.97
  5046.5  233.04  5068.9  232.76  5090.1  234.85  5168.8  238.29  5184.1  239.99
  5298.7  246.86  5314.6  248.13  5342.6  248.95  5450.9  258.29  5538.2  263.45
#Mann= 7 ,-1 , 0
  4404.2     .11       0  4600.1     .15       0  4612.3     .11       0
  4733.6     .15       0  4787.2     .07       0  5046.5     .11       0
  5298.7     .17       0
Bank Sta=4787.2,5046.5
XS Rating Curve= 0 ,0
Exp/Cntr=0.3,0.1

Type RM Length L Ch R = 1 ,6500    ,500,500,500
BEGIN DESCRIPTION:
MARTIN CREEK TRIBUTARY NO 1 13.0
END DESCRIPTION:
XS GIS Cut Line= 3
      3780017.87     10126211.07      3780512.69     10126269.91
      3781054.54     10126194.33
#Sta/Elev= 30
  4501.7  250.51  4511.7  249.48  4545.5  248.49  4582.2  245.41  4628.1  242.68
  4669.7  240.89    4693  239.38  4715.8     239  4753.4   236.2  4803.8  233.43
  4828.4  233.04  4844.1  233.29  4854.1  232.67  4904.5  232.05  4914.6   229.3
  4961.7  229.05  4961.9  228.55  4968.7   229.1  5126.4  229.27  5142.5  232.12
  5172.2  234.54  5207.1  235.15  5237.4  236.69  5243.7   237.6  5277.8   239.9
  5315.2  243.93  5391.8  249.11  5475.4  256.42  5534.9  258.92  5547.1  258.84
#Mann= 6 ,-1 , 0
  4501.7     .17       0  4669.7     .11       0  4828.4     .17       0
  4904.5     .06       0  5142.5     .11       0  5475.4     .17       0
Bank Sta=4904.5,5142.5
XS Rating Curve= 0 ,0
Exp/Cntr=0.3,0.1

Type RM Length L Ch R = 1 ,6000    ,500,500,500
BEGIN DESCRIPTION:
MARTIN CREEK TRIBUTARY NO 1 12.0
END DESCRIPTION:
XS GIS Cut Line= 3
      3779936.51      10126397.2      3780443.28      10126752.3
      3780983.09     10126897.13
#Sta/Elev= 30
  4381.2  254.38  4398.9  253.32  4413.7  251.73  4449.5  250.48  4497.6  247.27
  4520.9   246.9  4550.6  244.33  4571.5  243.76  4708.4  235.51  4734.5  235.53
  4750.2  233.74  4815.6  232.87  4822.4  230.04  4828.4  229.59  4828.7  229.09
  4836.5  229.66  5118.6  230.83 5143.84  232.83  5180.7  235.15  5201.5  235.85
  5212.2  236.88  5247.1   237.9  5294.6  240.78  5346.4  242.62  5376.5  244.34
  5470.6  250.44  5516.7  254.25  5551.6   257.8  5556.7  257.33  5558.9  258.34
#Mann= 6 ,-1 , 0
  4381.2     .17       0  4497.6     .11       0  4734.5     .17       0
  4815.6     .06       0 5143.84     .11       0  5376.5     .17       0
Bank Sta=4815.6,5143.84
XS Rating Curve= 0 ,0
Exp/Cntr=0.3,0.1

Type RM Length L Ch R = 1 ,5500    ,500,500,500
BEGIN DESCRIPTION:
MARTIN CREEK TRIBUTARY NO 1 11.0
END DESCRIPTION:
XS GIS Cut Line= 3
      3779617.86     10126811.07      3780132.43     10127143.85
      3780587.56     10127631.58
#Sta/Elev= 30
  4387.2  264.58  4530.7  250.53  4553.9  249.94    4567  248.29  4597.3  246.05
  4654.7  243.31  4675.8  240.88  4684.9  238.36  4720.6  237.51  4756.4  235.43
  4778.7  233.33  4820.9  232.17  4827.8  230.67  5192.8  231.47  5214.3  230.32
  5219.2  229.88  5219.4  229.38  5222.9  229.38  5228.5  231.12  5235.3   231.7
  5263.7  231.76  5270.5  233.02  5277.9  232.58  5284.7  233.49  5323.9  235.95
  5433.7   244.1  5462.8  246.84  5539.7  252.47  5624.7  257.01  5667.1  260.98
#Mann= 5 ,-1 , 0
  4387.2     .11       0  4778.7     .06       0  5284.7     .11       0
  5323.9     .11       0  5462.8     .17       0
#XS Ineff= 2 , 0
       0                  5270.5       0  233.02
Permanent Ineff=
       F       F
Bank Sta=4778.7,5284.7
XS Rating Curve= 0 ,0
Exp/Cntr=0.3,0.1

Type RM Length L Ch R = 1 ,5000    ,148,148,148
BEGIN DESCRIPTION:
MARTIN CREEK TRIBUTARY NO 1 10.0
END DESCRIPTION:
XS GIS Cut Line= 3
      3779367.88      10127061.1      3779844.72     10127547.99
      3780452.11     10127928.44
#Sta/Elev= 30
  4318.5  257.24  4403.3   251.5  4438.7  248.02  4488.1  245.96  4495.3  246.71
  4509.4   245.7  4523.6  242.76  4544.7   242.4  4551.8  241.14  4558.8  241.65
  4580.1  239.16  4594.3  239.22  4693.3  232.12  4712.7  228.98  4855.9  230.49
  5157.1  229.57    5280  232.33  5295.3  229.91  5337.7  232.21    5432  239.54
  5468.6  241.13  5475.7  242.43  5499.2  243.94  5505.1  243.26  5541.6  247.55
    5568  248.48  5664.5  254.68  5678.4  254.12  5712.6  257.12  5716.7  257.08
#Mann= 5 ,-1 , 0
  4318.5     .11       0  4693.3     .06       0    5280     .11       0
    5568     .17       0  5712.6     .11       0
#XS Ineff= 2 , 0
       0                    5280       0  232.33
Permanent Ineff=
       F       F
Bank Sta=4693.3,5280
XS Rating Curve= 0 ,0
Exp/Cntr=0.3,0.1

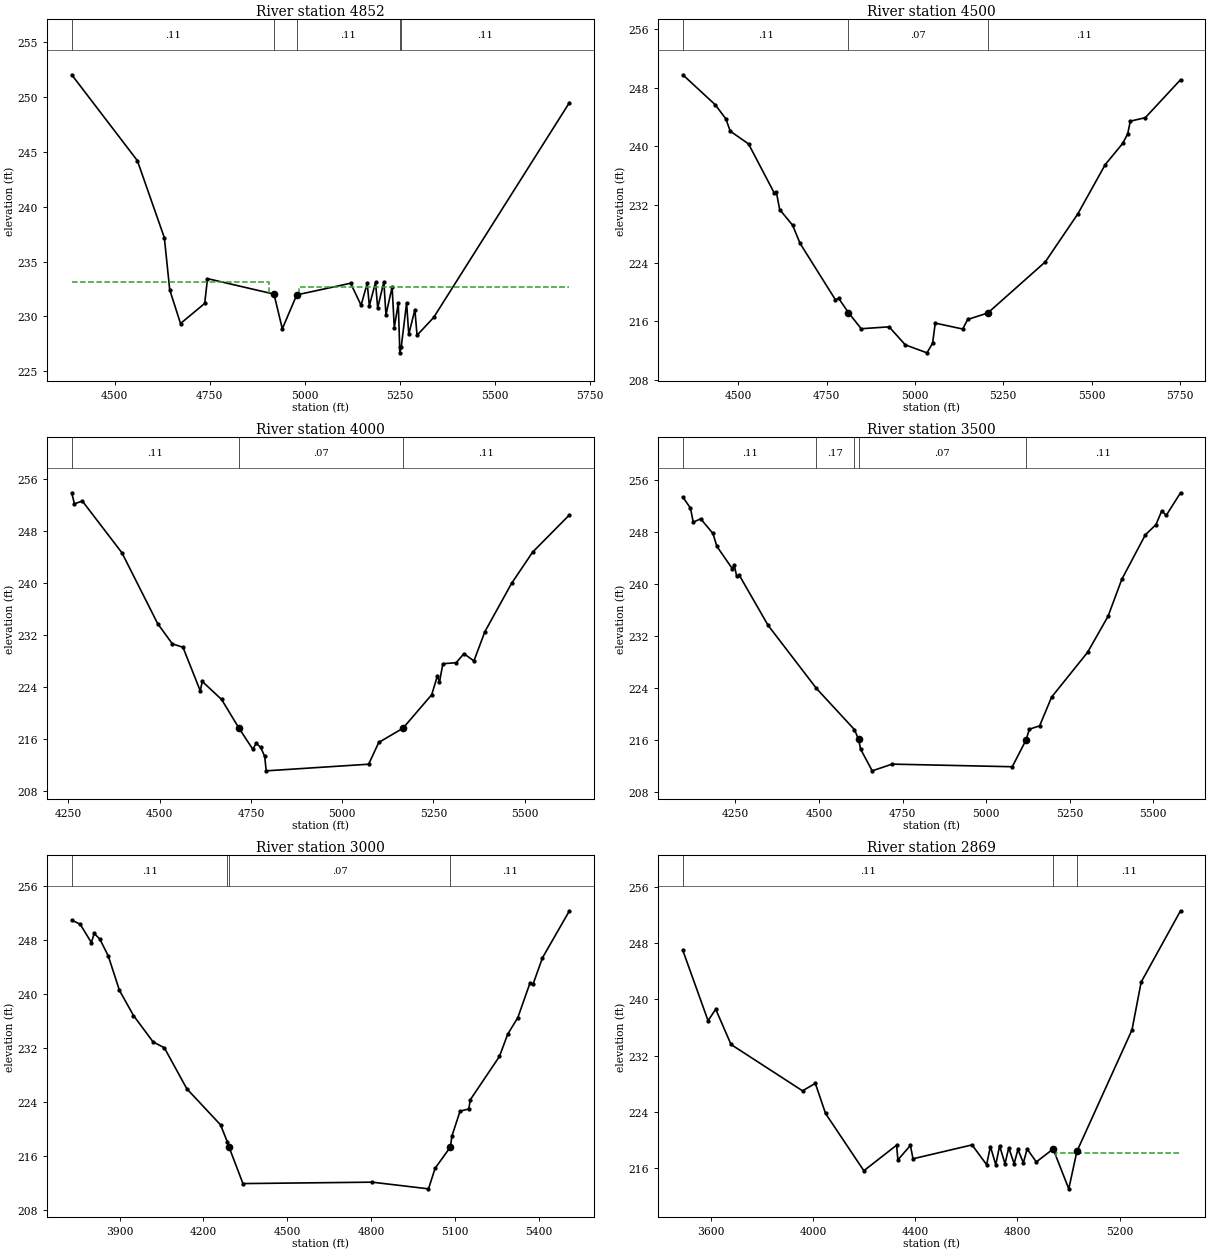
Type RM Length L Ch R = 1 ,4852    ,352,352,352
BEGIN DESCRIPTION:
Mapping XS 43e500a9
END DESCRIPTION:
XS GIS Cut Line= 3
      3779311.46     10127283.06       3779564.9     10127564.27
      3780383.57      10128008.3
#Sta/Elev= 30
  4386.5  252.01  4559.2  244.19  4630.2  237.17  4644.4  232.42  4672.8  229.35
  4736.4  231.18  4743.8  233.44  4918.8  232.03  4940.7  228.87  4978.7  231.96
  5120.4  233.02    5148  231.02  5164.1     233  5169.8  230.98    5186  233.09
  5191.7  230.77  5207.9  233.14  5213.5  230.15  5229.7  232.67  5235.4  228.98
  5245.9  231.19  5249.6  227.18  5249.8  226.68  5253.6  227.18  5267.8  231.23
  5273.5  228.37  5289.6  230.61  5295.3  228.28    5339   229.9  5696.4  249.48
#Mann= 5 ,-1 , 0
  4386.5     .11       0  4918.8     .07       0  4978.7     .11       0
  5249.6     .11       0  5253.6     .11       0
#XS Ineff= 2 , 0
       0  4904.9  233.17  4984.6       0  232.67
Permanent Ineff=
       T       T
Bank Sta=4918.8,4978.7
XS Rating Curve= 0 ,0
Exp/Cntr=0.3,0.1

Type RM Length L Ch R = 1 ,4500    ,500,500,500
BEGIN DESCRIPTION:
MARTIN CREEK TRIBUTARY NO 1 9.0
END DESCRIPTION:
XS GIS Cut Line= 3
       3779254.2       10127418.      3779604.52     10127973.46
      3780159.94     10128479.98
#Sta/Elev= 30
  4343.3  249.77    4435  245.67  4465.2  243.73  4477.4  242.06  4529.2  240.31
  4602.2  233.57  4608.1  233.68  4617.4  231.32  4653.9  229.19  4675.1  226.69
  4775.2  218.97  4784.4  219.16  4811.7  217.23  4848.1  215.01    4927  215.27
  4972.9   212.8  5034.2  211.71  5050.1  213.03  5057.6  215.78  5135.3  214.97
  5149.4  216.28  5206.2  217.16    5369  224.16  5460.9  230.72  5538.6  237.47
  5587.9  240.37  5602.1  241.68  5609.6  243.42  5652.1   243.9  5751.7  249.09
#Mann= 3 ,-1 , 0
  4343.3     .11       0  4811.7     .07       0  5206.2     .11       0
#XS Ineff= 2 , 0
       0  4784.4  219.16               0
Permanent Ineff=
       F       F
Bank Sta=4811.7,5206.2
XS Rating Curve= 0 ,0
Exp/Cntr=0.3,0.1

Type RM Length L Ch R = 1 ,4000    ,500,500,500
BEGIN DESCRIPTION:
MARTIN CREEK TRIBUTARY NO 1 8.0
END DESCRIPTION:
XS GIS Cut Line= 3
      3778801.12     10128168.05      3779483.36      10128456.2
      3780008.69     10128789.79
#Sta/Elev= 30
  4259.4  253.89  4266.7  252.19  4288.4  252.62    4397  244.64  4494.7  233.75
  4534.9  230.64    4564  230.11  4611.4  223.39  4616.8  224.85  4669.7  222.08
  4717.1  217.68  4755.2  214.41  4764.5  215.32  4776.9  214.69  4787.8  213.31
  4791.9  211.09  5072.4  212.11  5100.1  215.46  5166.4  217.65  5245.2  222.81
  5260.5  225.67  5266.4  224.76  5275.7  227.58  5312.1  227.73  5333.3  229.12
  5360.7  228.01  5390.9  232.53  5463.8  239.94  5521.4  244.75  5622.3  250.49
#Mann= 3 ,-1 , 0
  4259.4     .11       0  4717.1     .07       0  5166.4     .11       0
Bank Sta=4717.1,5166.4
XS Rating Curve= 0 ,0
Exp/Cntr=0.3,0.1

Type RM Length L Ch R = 1 ,3500    ,500,500,500
BEGIN DESCRIPTION:
MARTIN CREEK TRIBUTARY NO 1 7.0
END DESCRIPTION:
XS GIS Cut Line= 3
      3778681.33     10128475.34      3779451.45     10128954.66
      3780019.73     10129077.48
#Sta/Elev= 30
  4092.9  253.32  4115.7  251.62  4124.1  249.46  4146.4  249.97    4183  247.72
  4194.8  245.74  4240.9  242.32  4246.7   242.9  4253.7   241.2  4262.1  241.28
  4347.9  233.62  4492.5  223.93    4606  217.62  4618.6  216.11  4624.5  214.62
  4659.3  211.28  4718.9  212.31  5078.2  211.91  5119.1  215.99  5129.3  217.67
    5160  218.19  5195.9  222.61  5303.2  229.46  5364.6     235  5405.6  240.67
  5476.1  247.51  5507.9  249.08  5525.3  251.19  5538.6   250.5  5581.4  253.97
#Mann= 5 ,-1 , 0
  4092.9     .11       0  4492.5     .17       0    4606     .11       0
  4618.6     .07       0  5119.1     .11       0
Bank Sta=4618.6,5119.1
XS Rating Curve= 0 ,0
Exp/Cntr=0.3,0.1

Type RM Length L Ch R = 1 ,3000    ,131,131,131
BEGIN DESCRIPTION:
MARTIN CREEK TRIBUTARY NO 1 6.0
END DESCRIPTION:
XS GIS Cut Line= 3
       3778337.9     10129497.95        3779604.     10129387.63
      3780052.86     10129147.61
#Sta/Elev= 30
  3729.1     251  3759.2   250.4  3799.3  247.67  3809.4  249.03  3829.4  248.19
  3859.5  245.72  3899.7  240.58  3949.9  236.85  4020.1  232.93  4060.3  232.06
  4140.6  225.98  4261.1  220.63  4285.9  218.06  4291.2  217.37  4341.4  211.91
  4803.1  212.12  5004.9  211.13  5028.6  214.18  5083.1  217.33  5088.8  218.98
  5117.8  222.65  5148.9  222.99  5154.6  224.36  5258.7  230.78  5287.9  234.05
  5324.5  236.55  5368.4  241.73  5378.6  241.47  5412.6  245.42    5509  252.39
#Mann= 4 ,-1 , 0
  3729.1     .11       0  4285.9     .17       0  4291.2     .07       0
  5083.1     .11       0
Bank Sta=4291.2,5083.1
XS Rating Curve= 0 ,0
Exp/Cntr=0.3,0.1

Type RM Length L Ch R = 1 ,2869    ,369,369,369
BEGIN DESCRIPTION:
Mapping XS eb33f8b2
END DESCRIPTION:
XS GIS Cut Line= 4
      3778299.08     10129720.48      3779035.42     10129733.87
      3779354.07     10129677.64      3780090.42     10129179.59
#Sta/Elev= 30
  3489.9  246.95  3588.7  236.96  3618.7  238.59  3678.7  233.58  3958.7     227
  4008.8  228.06  4048.8  223.78  4198.8  215.65    4327  219.28  4332.1  217.19
  4381.1  219.25  4391.3  217.35  4622.5  219.32  4679.5  216.51  4694.4  219.09
  4715.4   216.5  4730.4  219.19  4751.4  216.65  4766.3   218.9  4787.3  216.66
  4802.3  218.68  4823.3  216.77  4838.3  218.74  4874.2   216.9  4940.1  218.74
  5001.3  213.08    5033  218.39  5248.8  235.65  5284.7  242.44  5438.9  252.57
#Mann= 3 ,-1 , 0
  3489.9     .11       0  4940.1     .07       0    5033     .11       0
#XS Ineff= 2 ,-1
  4952.9  4940.1  218.14  4940.1  4148.8  218.74
Permanent Ineff=
       F       F
Bank Sta=4940.1,5033
XS Rating Curve= 0 ,0
Exp/Cntr=0.3,0.1

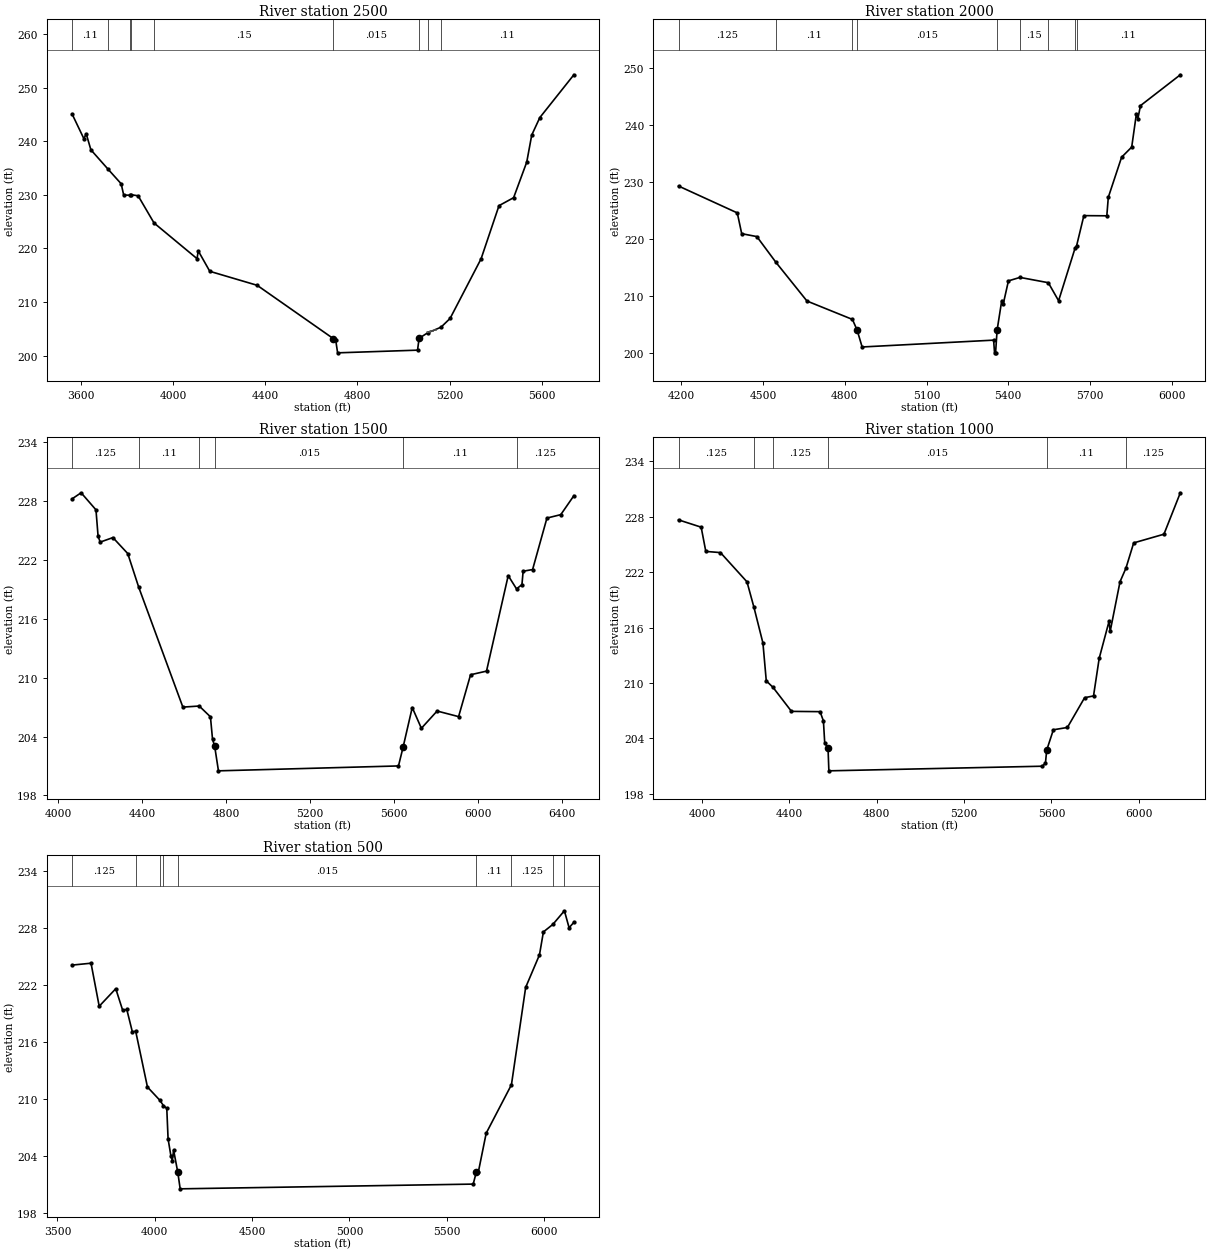
Type RM Length L Ch R = 1 ,2500    ,500,500,500
BEGIN DESCRIPTION:
MARTIN CREEK TRIBUTARY NO 1 5.0
END DESCRIPTION:
XS GIS Cut Line= 3
      3778227.17     10129970.07      3779648.65     10129747.51
      3780141.22      10129195.8
#Sta/Elev= 30
  3561.2  245.07  3612.5  240.45  3622.6  241.37  3642.9  238.38  3716.1  234.83
  3774.4  232.04  3785.3  229.94  3811.7  229.91  3816.5  230.01    3848   229.8
    3917  224.73  4103.8  218.07  4108.9  219.53  4159.1  215.71  4364.7   213.1
  4695.5  203.15  4705.7  202.87    4714   200.5    5061     201  5067.7  203.21
    5105  204.24  5162.8  205.28  5202.3  206.92  5336.9  218.05  5414.6  227.96
  5478.1  229.45    5535  236.08  5556.7  241.13  5591.8  244.39  5739.6  252.38
#Mann= 9 ,-1 , 0
  3561.2     .11       0  3716.1    .125       0  3811.7     .11       0
  3816.5    .125       0    3917     .15       0  4695.5    .015       0
  5067.7     .11       0    5105    .125       0  5162.8     .11       0
#XS Ineff= 3 ,-1
  5102.8    5117  204.39    5117  5131.2  204.53  5131.2  5145.4  204.75
Permanent Ineff=
       F       F       F
Bank Sta=4695.5,5067.7
XS Rating Curve= 0 ,0
Exp/Cntr=0.3,0.1

Type RM Length L Ch R = 1 ,2000    ,500,500,500
BEGIN DESCRIPTION:
MARTIN CREEK TRIBUTARY NO 1 4.0
END DESCRIPTION:
XS GIS Cut Line= 3
      3779075.53     10130486.44      3779835.83     10130205.93
      3780211.05     10129244.77
#Sta/Elev= 30
  4189.6  229.27  4405.3  224.55  4421.5   220.9  4477.1  220.39  4547.3  215.86
  4661.1  209.07    4828  205.84 4845.28  203.96  4863.6     201  5346.3   202.2
  5349.8  199.97  5353.5  199.97 5359.17  203.96  5376.2  209.15  5381.5   208.5
  5400.7  212.61  5443.1  213.22  5547.1  212.29  5584.9  209.12  5645.9  218.44
    5651  218.78  5677.7  224.07  5761.9  224.04  5767.4  227.29  5816.2  234.33
  5853.3  236.11  5870.6  241.98  5875.9  241.09  5885.5  243.39  6031.8  248.81
#Mann= 9 ,-1 , 0
  4189.6    .125       0  4547.3     .11       0    4828    .125       0
 4845.28    .015       0 5359.17     .11       0  5443.1     .15       0
  5547.1    .125       0  5645.9     .15       0    5651     .11       0
Bank Sta=4845.28,5359.17
XS Rating Curve= 0 ,0
Exp/Cntr=0.3,0.1

Type RM Length L Ch R = 1 ,1500    ,500,500,500
BEGIN DESCRIPTION:
MARTIN CREEK TRIBUTARY NO 1 3.0
END DESCRIPTION:
XS GIS Cut Line= 3
      3779105.09      10130530.7      3780029.72      10130666.8
      3781310.66     10131364.25
#Sta/Elev= 30
  4065.4  228.24  4108.6  228.86  4179.4  227.12  4189.5  224.42  4199.6  223.83
  4260.2  224.29    4331  222.66  4383.4  219.22  4593.8     207  4671.8  207.11
  4725.3  206.01  4735.3  203.72  4745.4  203.02  4763.5   200.5  5622.1     201
    5644  202.91  5687.7  206.96  5731.3  204.84  5806.3   206.6  5908.8  206.03
  5965.9   210.3  6041.9  210.67  6145.4  220.41    6185  219.06  6210.9  219.49
  6216.6  220.86  6261.7  221.03  6330.1  226.28  6396.1  226.63  6458.5  228.56
#Mann= 6 ,-1 , 0
  4065.4    .125       0  4383.4     .11       0  4671.8    .125       0
  4745.4    .015       0    5644     .11       0    6185    .125       0
Bank Sta=4745.4,5644
XS Rating Curve= 0 ,0
Exp/Cntr=0.3,0.1

Type RM Length L Ch R = 1 ,1000    ,500,500,500
BEGIN DESCRIPTION:
MARTIN CREEK TRIBUTARY NO 1 2.0
END DESCRIPTION:
XS GIS Cut Line= 3
      3779134.56     10130571.28      3780071.83     10131160.32
       3781236.9     10131401.15
#Sta/Elev= 30
    3893  227.64  3996.6  226.85  4017.8  224.23    4085   224.1  4206.3  220.94
  4238.2  218.18  4279.3  214.32  4294.6  210.23  4325.4  209.53    4410  206.93
  4540.8   206.9  4556.1   205.9    4562  203.56  4577.3  202.93  4581.1   200.5
  5557.6     201  5572.4  201.33    5578  202.73  5608.6  204.94  5672.8  205.19
  5751.6  208.41  5792.4   208.6  5818.4  212.67  5863.5  216.67  5868.6  215.58
  5913.7  220.95  5940.8  222.42  5976.2  225.15  6114.7  226.09  6189.7  230.57
#Mann= 6 ,-1 , 0
    3893    .125       0  4238.2     .11       0  4325.4    .125       0
  4577.3    .015       0    5578     .11       0  5940.8    .125       0
Bank Sta=4577.3,5578
XS Rating Curve= 0 ,0
Exp/Cntr=0.3,0.1

Type RM Length L Ch R = 1 ,500     ,0,0,0
BEGIN DESCRIPTION:
MARTIN CREEK TRIBUTARY NO 1 1.0
END DESCRIPTION:
XS GIS Cut Line= 3
      3779123.48     10130608.14      3780084.53     10131660.15
      3781222.15     10131471.24
#Sta/Elev= 30
  3575.1   224.1  3672.5   224.3  3714.5  219.76  3799.6  221.61  3835.3  219.32
  3856.3  219.42  3884.7  217.07    3902  217.12  3962.4  211.24  4025.7  209.85
  4044.6  209.28  4061.7  208.98  4068.4  205.77  4082.6  204.01    4090  203.47
  4096.8  204.58  4118.4  202.23  4130.5   200.5  5636.1     201  5652.1  202.27
  5662.3  202.26  5702.8  206.37  5832.5  211.48  5905.6  221.75  5976.5  225.18
  5996.7   227.6  6045.6   228.4  6104.6  229.83  6128.7  228.04  6153.2  228.61
#Mann= 9 ,-1 , 0
  3575.1    .125       0    3902     .11       0  4025.7    .125       0
  4044.6     .11       0  4118.4    .015       0  5652.1     .11       0
  5832.5    .125       0  6045.6     .11       0  6104.6    .125       0
Bank Sta=4118.4,5652.1
XS Rating Curve= 0 ,0
Exp/Cntr=0.3,0.1

Chan Stop Cuts=-1
Use User Specified Reach Order=0
Composite Channel Slope=5