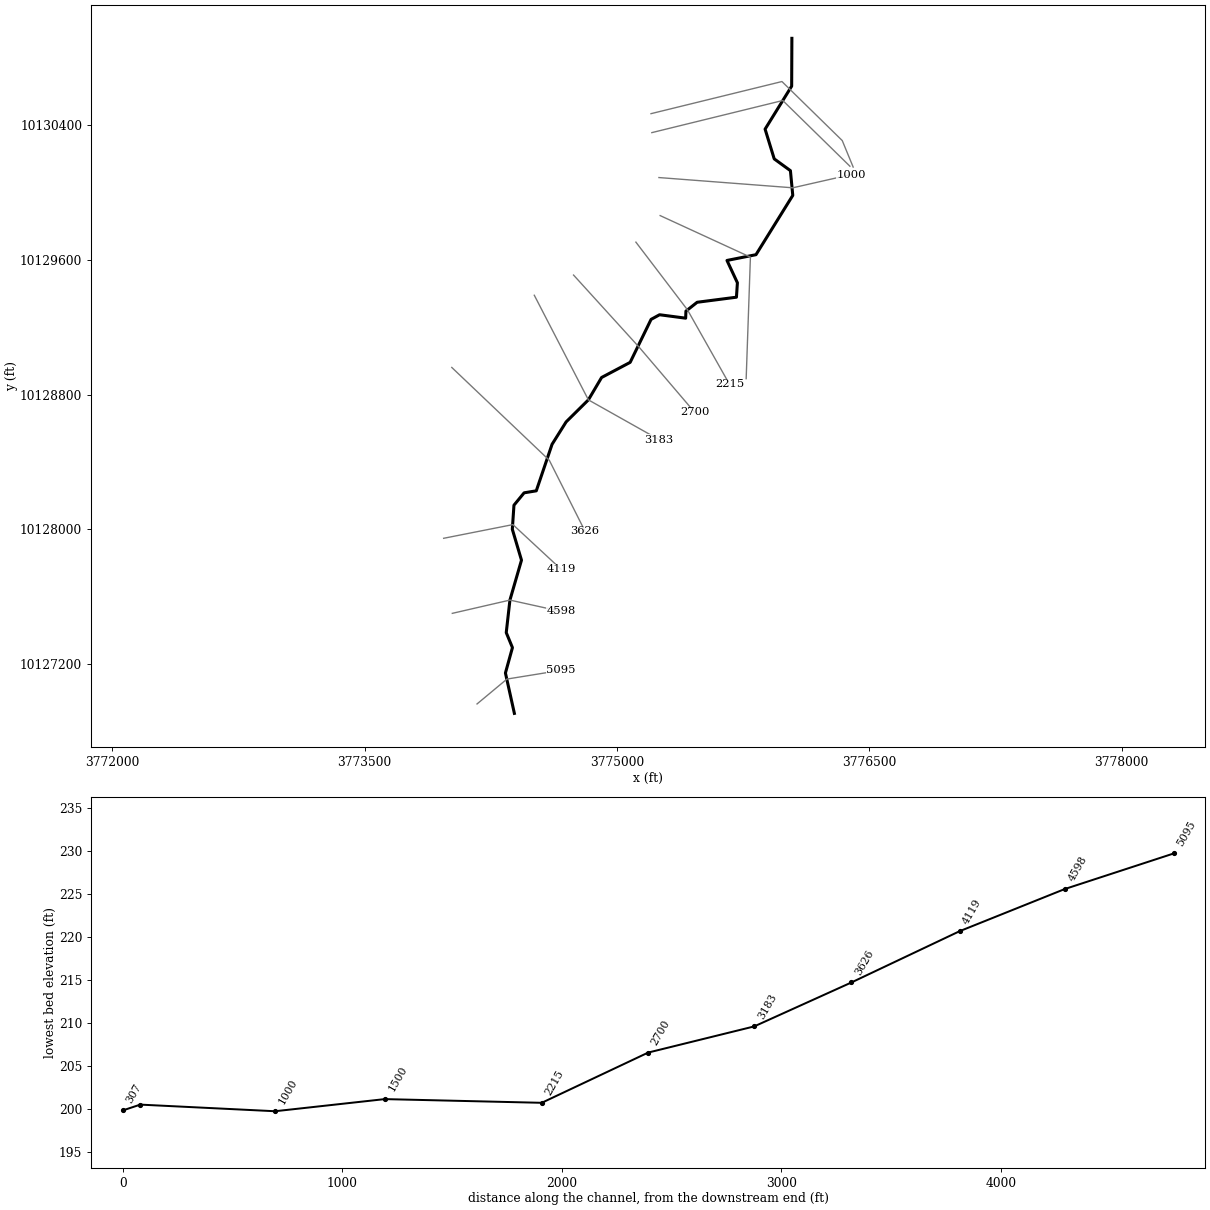
--- MARTIN CREEK TRIBUTARY NO 2.prj (project) ---

Proj Title=MARTIN CREEK TRIBUTARY NO 2 Base Level Engineering
Current Plan=p01
Default Exp/Contr=0.3,0.1
English Units
Geom File=g01
Flow File=f01
Plan File=p01
Y Axis Title=Elevation
X Axis Title(PF)=Main Channel Distance
X Axis Title(XS)=Station
BEGIN DESCRIPTION:
MARTIN CREEK TRIBUTARY NO 2
END DESCRIPTION:
DSS Export Rating Curves= 0
DSS Export Rating Curve Sorted= 0
DSS Export Volume Flow Curves= 0
DXF OffsetX= 0
DXF OffsetY= 0
DXF ScaleX= 1
DXF ScaleY= 10

--- MARTIN CREEK TRIBUTARY NO 2.p01 (plan) ---

Plan Title=Multiple Run
Short Identifier=Multiple
Geom File=g01
Flow File=f01
Subcritical Flow
K Sum by GR= 0
Std Step Tol= 0.01
Critical Tol= 0.01
Num of Std Step Trials= 20
Max Error Tol= 0.3
Flow Tol Ratio= 0.001
Split Flow NTrial= 30
Split Flow Tol= 0.02
Split Flow Ratio= 0.02
Log Output Level= 0
Friction Slope Method= 1
Unsteady Friction Slope Method= 2
Unsteady Bridges Friction Slope Method= 1
Parabolic Critical Depth
Global Vel Dist=  1 , 1 , 1
Global Log Level= 0
CheckData=True
Encroach Param= -1, 0, 0, 0
BEGIN DESCRIPTION:
Multiple Run
END DESCRIPTION:

--- MARTIN CREEK TRIBUTARY NO 2.f01 (steady flow) ---

Flow Title=Multiple
Program Version=4.10
Number of Profiles= 7
Profile Names=10-year,25-year,50-year,1pct_min,100-year,1pct_plu,500-year
River Rch & RM=MARTIN CREEK TRI,Reach-1         ,5095
     584     783    1052     465    1404    4240    2582
River Rch & RM=MARTIN CREEK TRI,Reach-1         ,1000
     932    1289    1768     796    2404    7260    4599
Boundary for River Rch & Prof#=MARTIN CREEK TRI,Reach-1         , 1
Up Type= 0
Dn Type= 3
Dn Slope=0.009
Boundary for River Rch & Prof#=MARTIN CREEK TRI,Reach-1         , 2
Up Type= 0
Dn Type= 3
Dn Slope=0.009
Boundary for River Rch & Prof#=MARTIN CREEK TRI,Reach-1         , 3
Up Type= 0
Dn Type= 3
Dn Slope=0.009
Boundary for River Rch & Prof#=MARTIN CREEK TRI,Reach-1         , 4
Up Type= 0
Dn Type= 3
Dn Slope=0.009
Boundary for River Rch & Prof#=MARTIN CREEK TRI,Reach-1         , 5
Up Type= 0
Dn Type= 3
Dn Slope=0.009
Boundary for River Rch & Prof#=MARTIN CREEK TRI,Reach-1         , 6
Up Type= 0
Dn Type= 3
Dn Slope=0.009
Boundary for River Rch & Prof#=MARTIN CREEK TRI,Reach-1         , 7
Up Type= 0
Dn Type= 3
Dn Slope=0.009
DSS Import GetInterval= 0
DSS Import GetPeak= 0
DSS Import FillOption= 0

--- MARTIN CREEK TRIBUTARY NO 2.g01 (geometry) ---

Geom Title=Existing Conditions
Program Version=4.10

River Reach=MARTIN CREEK TRI,Reach-1
Reach XY= 30
      3774389.85     10126905.11      3774336.66     10127145.14
      3774378.33     10127295.83      3774341.52     10127385.07
       3774363.4     10127578.47      3774432.14     10127815.63
      3774377.64      10127999.3      3774387.36     10128142.36
      3774447.77     10128215.97        3774520.     10128227.77
      3774613.75     10128504.16      3774697.43      10128637.5
      3774829.72      10128768.4      3774908.19     10128901.39
      3775077.98     10128991.32       3775202.3     10129246.74
      3775252.82     10129274.34      3775407.79     10129253.93
      3775409.41     10129295.68      3775476.08     10129348.44
      3775709.65     10129378.63      3775715.37     10129464.32
      3775653.45     10129597.03      3775825.75     10129631.27
      3776044.48     10129983.61      3776030.48     10130130.65
       3775934.2     10130200.67      3775879.93     10130377.48
      3776037.88     10130632.81      3776039.14     10130917.12

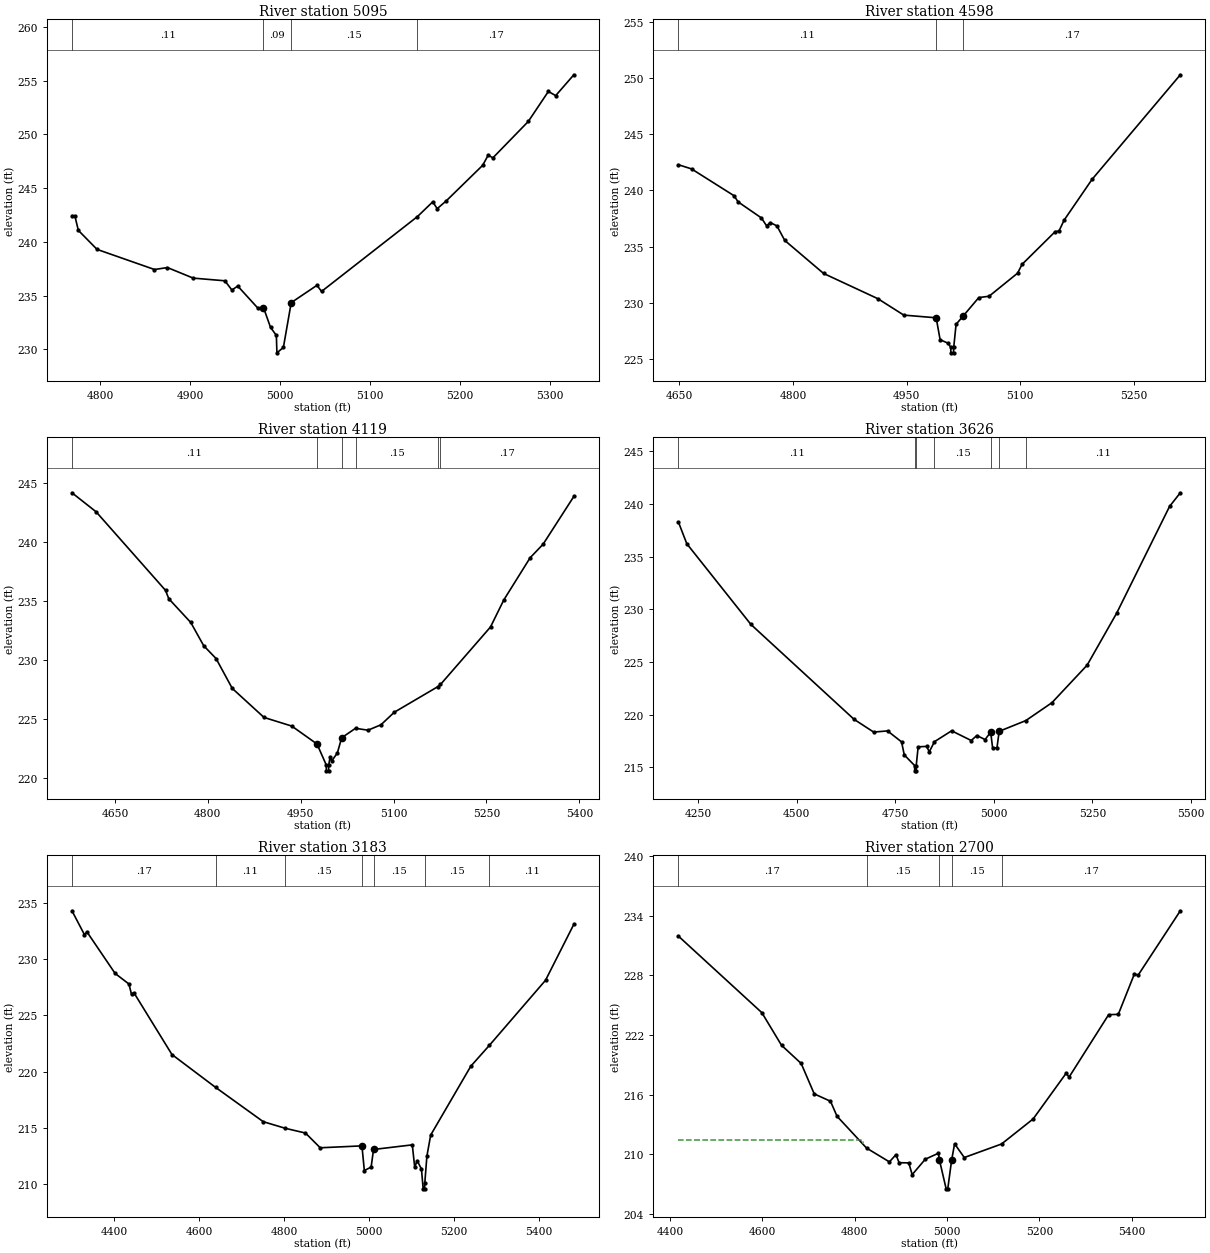
Type RM Length L Ch R = 1 ,5095    ,497,497,497
BEGIN DESCRIPTION:
MARTIN CREEK TRIBUTARY NO 2 10.0
END DESCRIPTION:
XS GIS Cut Line= 3
      3774167.88      10126961.1      3774345.69     10127109.02
      3774667.81     10127161.07
#Sta/Elev= 30
  4768.7  242.43  4771.9  242.43  4775.8  241.07  4796.6   239.3  4860.4  237.43
  4874.8  237.61  4903.4  236.63  4938.6  236.38  4946.4  235.52  4952.9  235.89
    4975  233.86  4981.5  233.89  4989.3  232.05  4995.8   231.3  4996.4  229.68
  5003.6  230.18  5012.3  234.35  5040.9  235.96    5046  235.39  5152.5  242.35
  5169.5  243.72  5174.5  243.09  5184.5  243.81    5225  247.12  5231.2  248.07
  5236.3  247.81  5275.7   251.2    5298  253.99  5306.1   253.6  5326.3  255.54
#Mann= 4 ,-1 , 0
  4768.7     .11       0  4981.5     .09       0  5012.3     .15       0
  5152.5     .17       0
Bank Sta=4981.5,5012.3
XS Rating Curve= 0 ,0
Exp/Cntr=0.3,0.1

Type RM Length L Ch R = 1 ,4598    ,479,479,479
BEGIN DESCRIPTION:
MARTIN CREEK TRIBUTARY NO 2 9.0
END DESCRIPTION:
XS GIS Cut Line= 3
      3774020.96     10127499.62       3774363.4     10127578.47
      3774667.83     10127511.08
#Sta/Elev= 30
  4648.6  242.29  4665.9  241.92  4722.1  239.53  4727.5  238.98  4758.3  237.55
    4765  236.86  4770.1  237.14  4778.8  236.84  4789.1  235.55  4840.4  232.61
  4912.2  230.36  4946.4   228.9  4989.2  228.66  4994.4  226.71  5004.8   226.4
  5008.4  226.04  5008.6  225.54  5012.1  225.54  5012.4  226.04  5015.5  228.08
    5025  228.83  5045.5  230.46  5059.1  230.58  5096.7  232.63  5102.7  233.42
  5146.4  236.33  5151.5  236.39  5158.2  237.35  5195.1  240.98  5311.8   250.3
#Mann= 3 ,-1 , 0
  4648.6     .11       0  4989.2     .09       0    5025     .17       0
Bank Sta=4989.2,5025
XS Rating Curve= 0 ,0
Exp/Cntr=0.3,0.1

Type RM Length L Ch R = 1 ,4119    ,493,493,493
BEGIN DESCRIPTION:
MARTIN CREEK TRIBUTARY NO 2 8.0
END DESCRIPTION:
XS GIS Cut Line= 3
      3773969.58     10127945.68      3774381.11     10128027.08
      3774667.83     10127761.09
#Sta/Elev= 30
  4580.5  244.18  4619.5  242.57  4731.6  235.92  4736.9  235.21  4772.4   233.2
  4793.3  231.23  4813.2  230.15  4839.4  227.62  4890.7  225.16  4935.5  224.43
  4976.3  222.91  4991.2  221.14  4991.4  220.64  4994.9  220.64  4995.2  221.14
  4997.4   221.8    5000  221.47  5009.2  222.16  5016.1  223.44  5038.5  224.24
  5058.6  224.08  5079.6  224.54  5101.1   225.6  5170.9  227.75  5175.7  227.95
  5256.5  232.82    5278  235.11  5320.5  238.68  5341.5  239.83  5391.1  243.87
#Mann= 6 ,-1 , 0
  4580.5     .11       0  4976.3     .06       0  5016.1     .11       0
  5038.5     .15       0  5170.9     .11       0  5175.7     .17       0
Bank Sta=4976.3,5016.1
XS Rating Curve= 0 ,0
Exp/Cntr=0.3,0.1

Type RM Length L Ch R = 1 ,3626    ,443,443,443
BEGIN DESCRIPTION:
MARTIN CREEK TRIBUTARY NO 2 7.0
END DESCRIPTION:
XS GIS Cut Line= 3
      3774017.83     10128961.09      3774597.43     10128409.37
      3774810.17      10127986.8
#Sta/Elev= 30
  4199.8   238.3  4221.1  236.24  4383.7  228.58  4645.4  219.57  4695.1  218.36
  4730.3  218.47  4765.9  217.43  4772.8  216.19  4799.1  215.18  4799.3  214.68
  4802.8  214.68  4803.1  215.18    4808  216.96  4829.4     217  4836.3  216.49
  4849.4  217.45  4892.9  218.48  4942.6  217.56  4956.8  218.03  4977.8  217.65
    4992  218.35  4996.8  216.89  5007.9  216.85  5013.5  218.43  5081.1  219.45
  5147.4  221.15  5236.6  224.71  5311.6  229.65  5445.9  239.79  5473.1  241.08
#Mann= 7 ,-1 , 0
  4199.8     .11       0  4799.1     .12       0  4803.1     .11       0
  4849.4     .15       0    4992     .09       0  5013.5     .15       0
  5081.1     .11       0
Bank Sta=4992,5013.5
XS Rating Curve= 0 ,0
Exp/Cntr=0.3,0.1

Type RM Length L Ch R = 1 ,3183    ,483,483,483
BEGIN DESCRIPTION:
MARTIN CREEK TRIBUTARY NO 2 6.0
END DESCRIPTION:
XS GIS Cut Line= 3
       3774508.2     10129390.19      3774829.72      10128768.4
       3775249.3      10128532.4
#Sta/Elev= 30
    4300  234.29  4329.5  232.16  4335.2  232.42  4401.6  228.72  4434.1  227.78
  4440.2  226.86  4445.9     227  4535.4  221.51  4638.1  218.59  4750.3  215.54
  4802.4  214.95  4849.7  214.53  4884.4  213.22  4982.6  213.39  4988.2   211.2
  5004.2   211.5  5009.9  213.07  5101.1  213.48  5106.8  211.49  5112.6  212.07
  5122.7  211.33  5126.7  209.57  5130.2  209.57  5130.5  210.07  5135.5  212.48
  5144.4  214.35  5238.8  220.47  5282.4  222.32  5414.7  228.11  5481.4  233.09
#Mann= 7 ,-1 , 0
    4300     .17       0  4638.1     .11       0  4802.4     .15       0
  4982.6     .09       0  5009.9     .15       0  5130.5     .15       0
  5282.4     .11       0
Bank Sta=4982.6,5009.9
XS Rating Curve= 0 ,0
Exp/Cntr=0.3,0.1

Type RM Length L Ch R = 1 ,2700    ,485,485,485
BEGIN DESCRIPTION:
MARTIN CREEK TRIBUTARY NO 2 5.0
END DESCRIPTION:
XS GIS Cut Line= 3
      3774741.55     10129510.22      3775133.03     10129079.55
        3775461.     10128694.89
#Sta/Elev= 30
    4418  231.95  4598.8  224.25  4641.4  220.97    4684  219.14  4712.3  216.08
  4747.5  215.34  4761.7  213.83  4825.7  210.63  4875.2  209.24  4889.4  209.97
  4896.1  209.16  4917.1  209.14  4924.5  207.96  4952.9  209.51  4981.3  210.11
  4983.7   209.4  4998.1  206.53  5001.6  206.53  5009.9  209.39  5016.4  211.06
  5037.4  209.68  5118.1  211.04  5186.6  213.56    5258  218.15  5264.6  217.78
  5350.2  224.05  5371.1  224.08  5406.2  228.17  5413.9  228.01  5505.5   234.5
#Mann= 5 ,-1 , 0
    4418     .17       0  4825.7     .15       0  4983.7     .09       0
  5009.9     .15       0  5118.1     .17       0
#XS Ineff= 2 , 0
       0  4818.4  211.42               0
Permanent Ineff=
       F       F
Bank Sta=4983.7,5009.9
XS Rating Curve= 0 ,0
Exp/Cntr=0.3,0.1

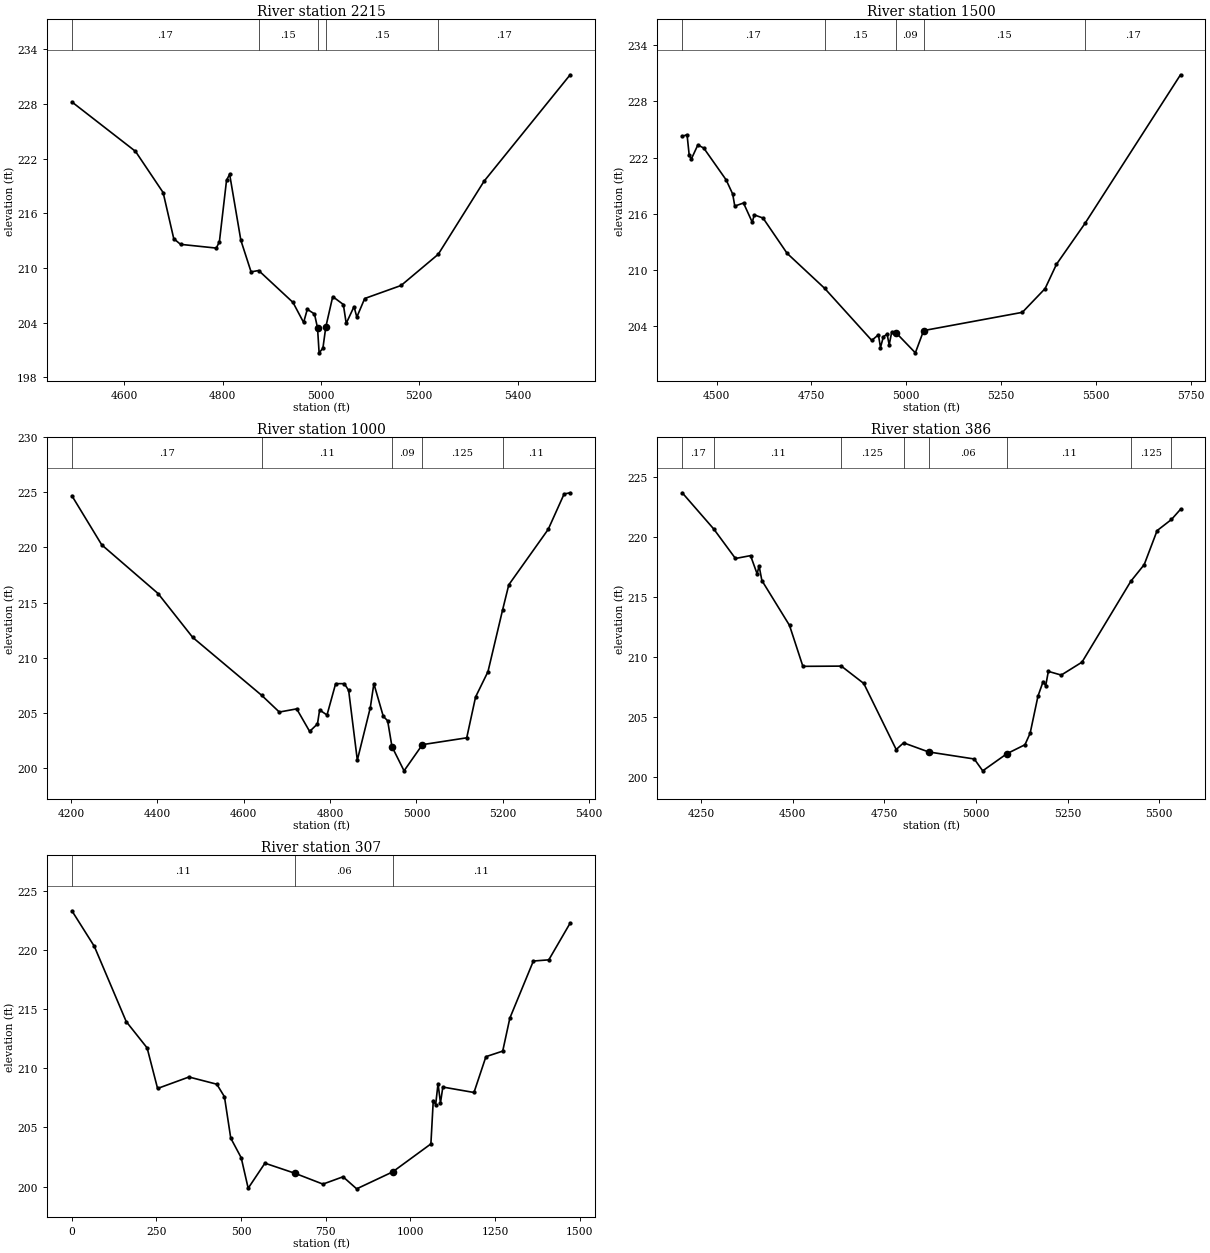
Type RM Length L Ch R = 1 ,2215    ,715,715,715
BEGIN DESCRIPTION:
MARTIN CREEK TRIBUTARY NO 2 4.0
END DESCRIPTION:
XS GIS Cut Line= 3
      3775112.08     10129705.82       3775418.8     10129303.13
      3775667.92     10128861.78
#Sta/Elev= 30
  4493.8  228.21  4623.1  222.79  4679.3  218.27  4700.9  213.21  4714.7  212.59
  4787.4  212.18  4793.7  212.88  4808.2  219.62  4814.5  220.28  4837.3  213.04
  4858.1  209.57  4873.5  209.72  4943.3  206.22  4964.9  204.02  4972.4  205.47
    4987  204.95  4993.2  203.43  4996.4  200.69  5004.1  201.19 5010.05  203.54
  5024.1  206.86  5045.7  205.99  5051.5  203.92  5067.4  205.76  5073.1  204.61
  5089.1  206.65  5163.1  208.08  5238.6   211.5  5331.7  219.51  5506.8  231.19
#Mann= 5 ,-1 , 0
  4493.8     .17       0  4873.5     .15       0  4993.2     .09       0
 5010.05     .15       0  5238.6     .17       0
#XS Ineff= 2 , 0
       0  4814.5  220.28               0
Permanent Ineff=
       T       F
Bank Sta=4993.2,5010.05
XS Rating Curve= 0 ,0
Exp/Cntr=0.3,0.1

Type RM Length L Ch R = 1 ,1500    ,500,500,500
BEGIN DESCRIPTION:
MARTIN CREEK TRIBUTARY NO 2 3.0
END DESCRIPTION:
XS GIS Cut Line= 3
      3775256.22     10129863.63      3775792.73     10129616.74
      3775767.48     10128894.38
#Sta/Elev= 30
  4409.4  224.26  4422.1  224.45  4427.6  222.31  4433.2  221.83  4450.6  223.35
  4466.2  223.01    4525  219.62  4542.4   218.1  4547.9  216.81  4570.9  217.14
  4593.9  215.09  4599.4  215.87  4622.4  215.53  4685.8  211.76  4784.7  208.02
    4909  202.45  4926.5  203.05    4932  201.69  4939.6  202.84  4949.4  203.12
  4954.9  201.98  4961.6  203.34  4972.4  203.29  5023.9  201.12  5045.7   203.5
  5305.9  205.45  5365.9  207.99  5395.9  210.59  5470.9  214.95  5722.8  230.85
#Mann= 5 ,-1 , 0
  4409.4     .17       0  4784.7     .15       0  4972.4     .09       0
  5045.7     .15       0  5470.9     .17       0
Bank Sta=4972.4,5045.7
XS Rating Curve= 0 ,0
Exp/Cntr=0.3,0.1

Type RM Length L Ch R = 1 ,1000    ,614,614,614
BEGIN DESCRIPTION:
MARTIN CREEK TRIBUTARY NO 2 2.0
END DESCRIPTION:
XS GIS Cut Line= 3
      3775248.91      10130089.7      3776044.48     10130028.79
      3776391.46      10130107.5
#Sta/Elev= 30
  4202.1   224.7  4271.2  220.24  4401.6  215.82  4481.9  211.83  4641.8  206.56
  4682.4  205.05  4722.6  205.34  4752.6  203.29  4770.7  203.97  4775.7  205.24
  4792.8  204.78  4812.8  207.63  4832.9  207.63  4842.9  207.02    4863  200.68
  4893.1  205.46  4901.3  207.63  4923.1  204.66  4933.2  204.26  4943.2  201.91
  4971.2  199.71  5013.7  202.09  5116.3  202.71  5136.8  206.42  5165.5  208.72
  5199.2   214.3  5213.7  216.61    5305  221.65  5341.8  224.86  5355.8  224.97
#Mann= 5 ,-1 , 0
  4202.1     .17       0  4641.8     .11       0  4943.2     .09       0
  5013.7    .125       0  5199.2     .11       0
#XS Ineff= 2 , 0
       0  4901.3  207.63               0
Permanent Ineff=
       F       F
Bank Sta=4943.2,5013.7
XS Rating Curve= 0 ,0
Exp/Cntr=0.3,0.1

Type RM Length L Ch R = 1 ,386     ,79,79,79
BEGIN DESCRIPTION:
MARTIN CREEK TRIBUTARY NO 2 1.0
END DESCRIPTION:
XS GIS Cut Line= 3
      3775206.85     10130356.73      3775984.97     10130547.65
      3776383.94      10130157.1
#Sta/Elev= 30
  4198.8  223.71  4284.9  220.68    4344  218.22  4385.2  218.46  4403.2  216.93
  4408.4  217.61  4416.1  216.38  4491.5  212.63    4528  209.21  4632.9  209.23
  4694.1  207.78  4782.6  202.26  4802.7  202.82  4870.9  202.06  4995.6  201.47
  5018.7  200.48  5084.5  201.91  5133.9  202.66  5148.1  203.63  5169.4  206.72
  5183.5  207.94  5190.5  207.59  5197.7  208.79  5232.9  208.48  5289.5  209.56
  5422.8  216.32  5459.3  217.71  5494.5  220.55  5533.7  221.48  5558.3  222.33
#Mann= 8 ,-1 , 0
  4198.8     .17       0  4284.9     .11       0  4632.9    .125       0
  4802.7     .11       0  4870.9     .06       0  5084.5     .11       0
  5422.8    .125       0  5533.7     .11       0
Bank Sta=4870.9,5084.5
XS Rating Curve= 0 ,0
Exp/Cntr=0.3,0.1

Type RM Length L Ch R = 1 ,307     ,0,0,0
XS GIS Cut Line= 4
      3775201.96     10130469.41      3775980.07     10130660.33
       3776338.5     10130309.47       3776403.4     10130152.08
#Sta/Elev= 30
       0  223.33    66.3  220.32   160.5  213.96   222.3  211.73   253.2   208.3
   345.9  209.27   428.2  208.66   450.8   207.6   469.4   204.1   500.3  202.44
   520.9  199.86   570.4  201.98   658.7  201.13   741.8  200.21   801.2  200.83
   841.5  199.81   947.6  201.24  1060.8  203.61  1067.8  207.28  1074.9  206.94
  1081.9  208.71  1089.1  207.08  1096.1  208.42  1188.1  207.96  1223.4  210.99
    1273  211.46  1294.1  214.25  1363.6  219.08  1409.2  219.18  1472.3  222.29
#Mann= 3 , 0 , 0
       0     .11       0   658.7     .06       0   947.6     .11       0
Bank Sta=658.7,947.6
XS Rating Curve= 0 ,0
Exp/Cntr=0.3,0.1

Chan Stop Cuts=-1
Use User Specified Reach Order=0
Composite Channel Slope=5