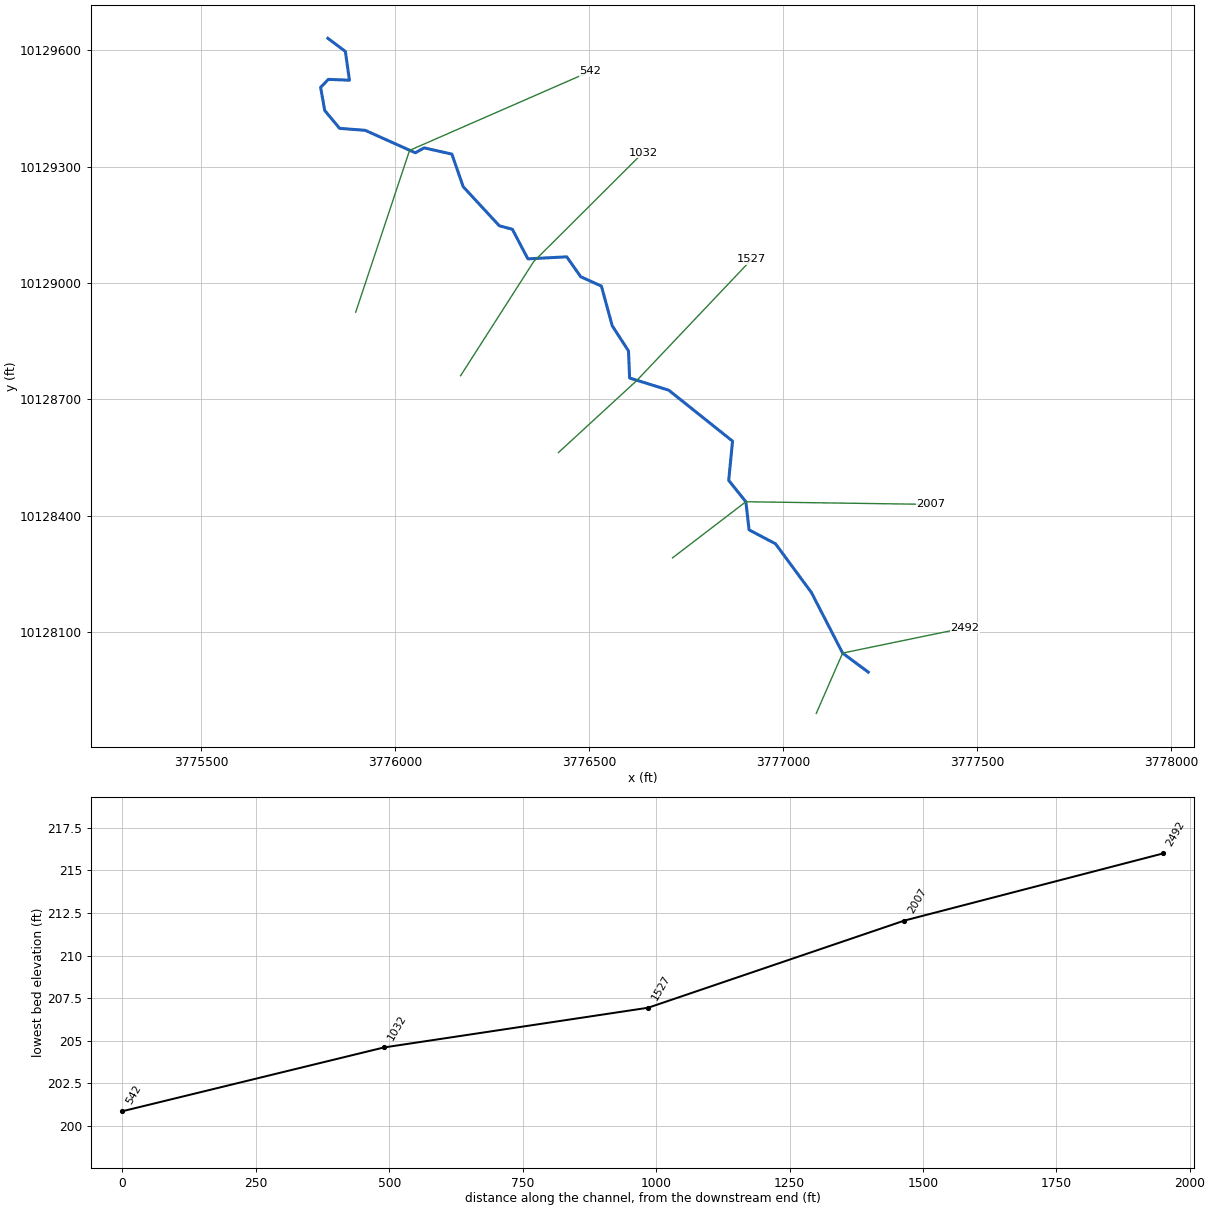
--- MARTIN CREEK TRIBUTARY NO 2_1.prj (project) ---

Proj Title=MARTIN CREEK TRIBUTARY NO 2_1 Base Level Engineering
Current Plan=p01
Default Exp/Contr=0.3,0.1
English Units
Geom File=g01
Flow File=f01
Plan File=p01
Y Axis Title=Elevation
X Axis Title(PF)=Main Channel Distance
X Axis Title(XS)=Station
BEGIN DESCRIPTION:
MARTIN CREEK TRIBUTARY NO 2_1
END DESCRIPTION:
DSS Export Rating Curves= 0
DSS Export Rating Curve Sorted= 0
DSS Export Volume Flow Curves= 0
DXF OffsetX= 0
DXF OffsetY= 0
DXF ScaleX= 1
DXF ScaleY= 10

--- MARTIN CREEK TRIBUTARY NO 2_1.p01 (plan) ---

Plan Title=Multiple Run
Short Identifier=Multiple
Geom File=g01
Flow File=f01
Subcritical Flow
K Sum by GR= 0
Std Step Tol= 0.01
Critical Tol= 0.01
Num of Std Step Trials= 20
Max Error Tol= 0.3
Flow Tol Ratio= 0.001
Split Flow NTrial= 30
Split Flow Tol= 0.02
Split Flow Ratio= 0.02
Log Output Level= 0
Friction Slope Method= 1
Unsteady Friction Slope Method= 2
Unsteady Bridges Friction Slope Method= 1
Parabolic Critical Depth
Global Vel Dist=  1 , 1 , 1
Global Log Level= 0
CheckData=True
Encroach Param= -1, 0, 0, 0
BEGIN DESCRIPTION:
Multiple Run
END DESCRIPTION:

--- MARTIN CREEK TRIBUTARY NO 2_1.f01 (steady flow) ---

Flow Title=Multiple
Program Version=4.10
Number of Profiles= 7
Profile Names=10-year,25-year,50-year,1pct_min,100-year,1pct_plu,500-year
River Rch & RM=MARTIN CREEK TRI,Reach-1         ,2492
     379     495     652     284     857    2588    1524
River Rch & RM=MARTIN CREEK TRI,Reach-1         ,2007
     456     603     802     351    1061    3204    1916
Boundary for River Rch & Prof#=MARTIN CREEK TRI,Reach-1         , 1
Up Type= 0
Dn Type= 3
Dn Slope=0.015
Boundary for River Rch & Prof#=MARTIN CREEK TRI,Reach-1         , 2
Up Type= 0
Dn Type= 3
Dn Slope=0.015
Boundary for River Rch & Prof#=MARTIN CREEK TRI,Reach-1         , 3
Up Type= 0
Dn Type= 3
Dn Slope=0.015
Boundary for River Rch & Prof#=MARTIN CREEK TRI,Reach-1         , 4
Up Type= 0
Dn Type= 3
Dn Slope=0.015
Boundary for River Rch & Prof#=MARTIN CREEK TRI,Reach-1         , 5
Up Type= 0
Dn Type= 3
Dn Slope=0.015
Boundary for River Rch & Prof#=MARTIN CREEK TRI,Reach-1         , 6
Up Type= 0
Dn Type= 3
Dn Slope=0.015
Boundary for River Rch & Prof#=MARTIN CREEK TRI,Reach-1         , 7
Up Type= 0
Dn Type= 3
Dn Slope=0.015
DSS Import GetInterval= 0
DSS Import GetPeak= 0
DSS Import FillOption= 0

--- MARTIN CREEK TRIBUTARY NO 2_1.g01 (geometry) ---

Geom Title=Existing Conditions
Program Version=4.10

River Reach=MARTIN CREEK TRI,Reach-1
Reach XY= 30
      3777218.47     10127996.75      3777152.49     10128045.88
      3777071.94     10128202.25      3776979.49     10128327.69
      3776911.35     10128363.71       3776903.1     10128436.19
      3776858.83     10128491.32      3776868.82     10128592.44
      3776704.51     10128723.78      3776603.47     10128755.29
      3776600.61     10128825.08      3776558.68     10128889.93
      3776530.82     10128992.27      3776477.43     10129016.49
      3776441.49     10129067.78      3776341.23     10129062.58
      3776301.34     10129138.81      3776267.67     10129147.86
      3776174.62     10129248.51       3776145.4     10129332.64
      3776073.98     10129348.79      3776051.17     10129336.12
      3775921.92     10129394.05      3775856.03     10129399.11
      3775817.66     10129445.09      3775807.16     10129504.83
      3775827.07     10129525.47      3775881.37     10129523.29
      3775870.87     10129597.51      3775825.75     10129631.27

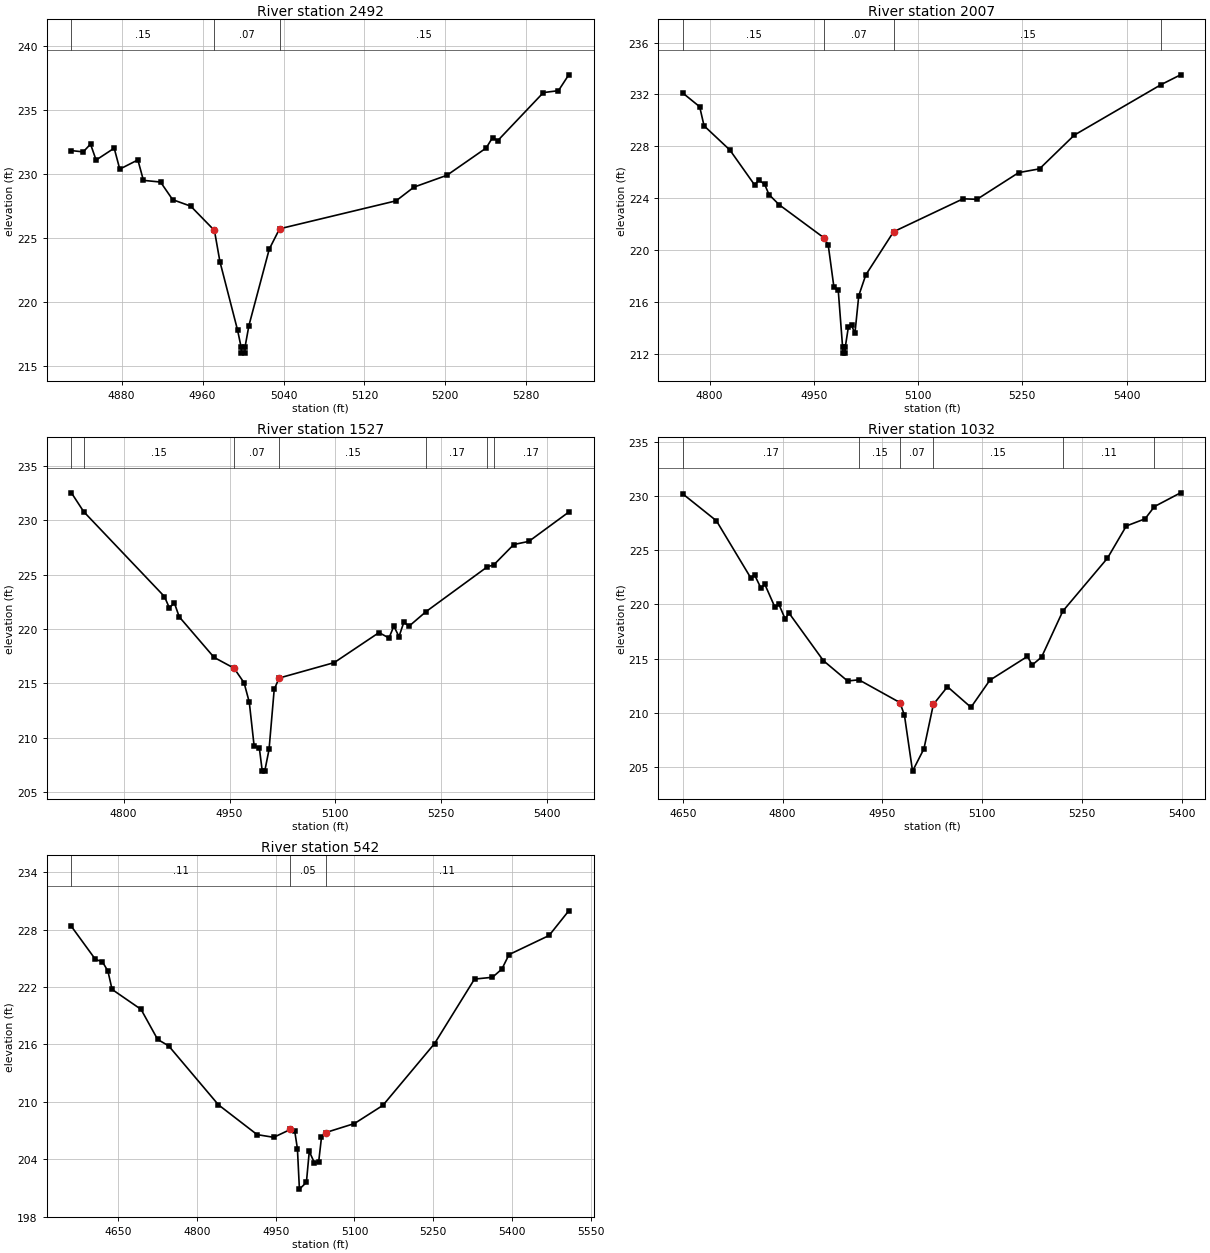
Type RM Length L Ch R = 1 ,2492    ,485,485,485
BEGIN DESCRIPTION:
MARTIN CREEK TRIBUTARY NO 2_1 5.0
END DESCRIPTION:
XS GIS Cut Line= 3
      3777084.54     10127890.38      3777152.49     10128045.88
      3777467.83     10128111.07
#Sta/Elev= 30
  4830.3  231.84    4842  231.74  4849.2  232.35  4854.7   231.1  4872.6  232.03
  4878.1  230.39    4896  231.11  4901.5  229.51  4918.4  229.38  4930.4     228
  4948.3  227.49  4971.7  225.59  4977.1  223.16  4994.6  217.78    4998  216.49
  4998.3  215.99  5001.8  215.99    5002  216.49  5005.8  218.15  5025.9  224.13
  5036.1  225.72  5151.3  227.91  5168.9  228.98  5201.6  229.91  5240.3  232.04
  5246.7  232.86  5251.8  232.62  5296.9  236.38  5311.8  236.53    5322  237.77
#Mann= 3 ,-1 , 0
  4830.3     .15       0  4971.7     .07       0  5036.1     .15       0
Bank Sta=4971.7,5036.1
XS Rating Curve= 0 ,0
Exp/Cntr=0.3,0.1

Type RM Length L Ch R = 1 ,2007    ,480,480,480
BEGIN DESCRIPTION:
MARTIN CREEK TRIBUTARY NO 2_1 4.0
END DESCRIPTION:
XS GIS Cut Line= 3
      3776714.26     10128291.51       3776903.1     10128436.19
      3777380.75     10128429.32
#Sta/Elev= 30
  4762.1  232.08  4785.8  231.05  4792.1  229.58  4829.3  227.71  4864.7  225.03
    4871  225.38  4879.2  225.08  4885.5  224.28    4900   223.5  4964.4  220.95
  4970.7  220.41  4978.9  217.16  4985.2  216.88  4991.4  212.55  4991.6  212.05
  4995.1  212.05  4995.4  212.55  4999.7  214.04  5004.3  214.19  5009.2  213.58
  5014.7  216.48  5024.8  218.08  5064.8  221.41  5164.8  223.95  5184.8  223.91
  5244.8  225.97  5274.8  226.26  5324.8  228.86  5449.9  232.76  5477.7  233.51
#Mann= 4 ,-1 , 0
  4762.1     .15       0  4964.4     .07       0  5064.8     .15       0
  5449.9     .17       0
Bank Sta=4964.4,5064.8
XS Rating Curve= 0 ,0
Exp/Cntr=0.3,0.1

Type RM Length L Ch R = 1 ,1527    ,495,495,495
BEGIN DESCRIPTION:
MARTIN CREEK TRIBUTARY NO 2_1 3.0
END DESCRIPTION:
XS GIS Cut Line= 3
      3776420.04     10128563.02       3776621.7     10128748.52
      3776917.87     10129061.09
#Sta/Elev= 30
    4726  232.51  4743.4  230.78  4857.8  222.98  4864.6  221.96    4872  222.37
  4878.7  221.12  4928.1  217.39  4956.4   216.4  4970.6  215.06    4978  213.27
  4984.8  209.28  4992.2  209.08  4996.4  206.94  4999.9  206.94    5006  208.93
  5013.3  214.44  5020.2  215.49  5098.3  216.91  5161.8  219.67  5175.9  219.17
  5182.8  220.26  5190.1   219.3    5197  220.63  5204.2  220.25  5228.5   221.6
  5315.4  225.72  5324.2  225.88  5352.7  227.76  5374.1  228.05  5430.6  230.74
#Mann= 7 ,-1 , 0
    4726     .11       0  4743.4     .15       0  4956.4     .07       0
  5020.2     .15       0  5228.5     .17       0  5315.4     .11       0
  5324.2     .17       0
Bank Sta=4956.4,5020.2
XS Rating Curve= 0 ,0
Exp/Cntr=0.3,0.1

Type RM Length L Ch R = 1 ,1032    ,490,490,490
BEGIN DESCRIPTION:
MARTIN CREEK TRIBUTARY NO 2_1 2.0
END DESCRIPTION:
XS GIS Cut Line= 3
      3776167.84     10128761.05      3776356.08     10129055.29
      3776637.91     10129336.32
#Sta/Elev= 30
  4650.7  230.17  4700.6  227.72  4752.2  222.45  4758.1   222.7  4767.4  221.52
  4773.4  221.85  4788.6  219.73  4794.5  220.01  4803.8  218.67  4809.7   219.2
  4861.3  214.81  4897.7  212.93  4914.7  213.04  4976.3  210.94  4983.1  209.78
  4995.3  204.61  5012.4  206.67  5026.6  210.77  5047.8   212.4  5083.1   210.5
  5111.4     213    5168   215.2    5175   214.4  5189.2  215.14  5221.1  219.38
  5288.2  224.27  5316.5  227.24  5344.7   227.9  5358.7  229.03    5398   230.3
#Mann= 6 ,-1 , 0
  4650.7     .17       0  4914.7     .15       0  4976.3     .07       0
  5026.6     .15       0  5221.1     .11       0  5358.7     .17       0
#XS Ineff= 2 , 0
       0                  5047.8       0   212.4
Permanent Ineff=
       F       F
Bank Sta=4976.3,5026.6
XS Rating Curve= 0 ,0
Exp/Cntr=0.3,0.1

Type RM Length L Ch R = 1 ,542     ,0,0,0
BEGIN DESCRIPTION:
MARTIN CREEK TRIBUTARY NO 2_1 1.0
END DESCRIPTION:
XS GIS Cut Line= 3
      3775897.52     10128925.06      3776036.33     10129342.28
      3776502.21     10129546.05
#Sta/Elev= 30
  4560.3  228.35  4606.2  224.89  4619.3  224.66  4629.9  223.68  4637.8  221.76
  4693.1  219.67  4724.7  216.53  4745.8  215.85  4840.6  209.69  4914.4  206.57
    4946  206.29  4977.7  207.11    4986  206.96  4991.2  205.09    4995  200.87
  5008.3  201.57  5013.8  204.82  5023.5  203.63  5031.7  203.71  5037.1   206.3
  5045.3  206.79  5099.9  207.73  5154.1  209.63  5252.7   216.1  5328.8  222.84
  5363.1  223.03    5381  223.89  5394.6   225.4    5471   227.4  5508.5  229.98
#Mann= 3 , 0 , 0
  4560.3     .11       0  4977.7     .05       0  5045.3     .11       0
Bank Sta=4977.7,5045.3
XS Rating Curve= 0 ,0
Exp/Cntr=0.3,0.1

Chan Stop Cuts=-1
Use User Specified Reach Order=0
Composite Channel Slope=5