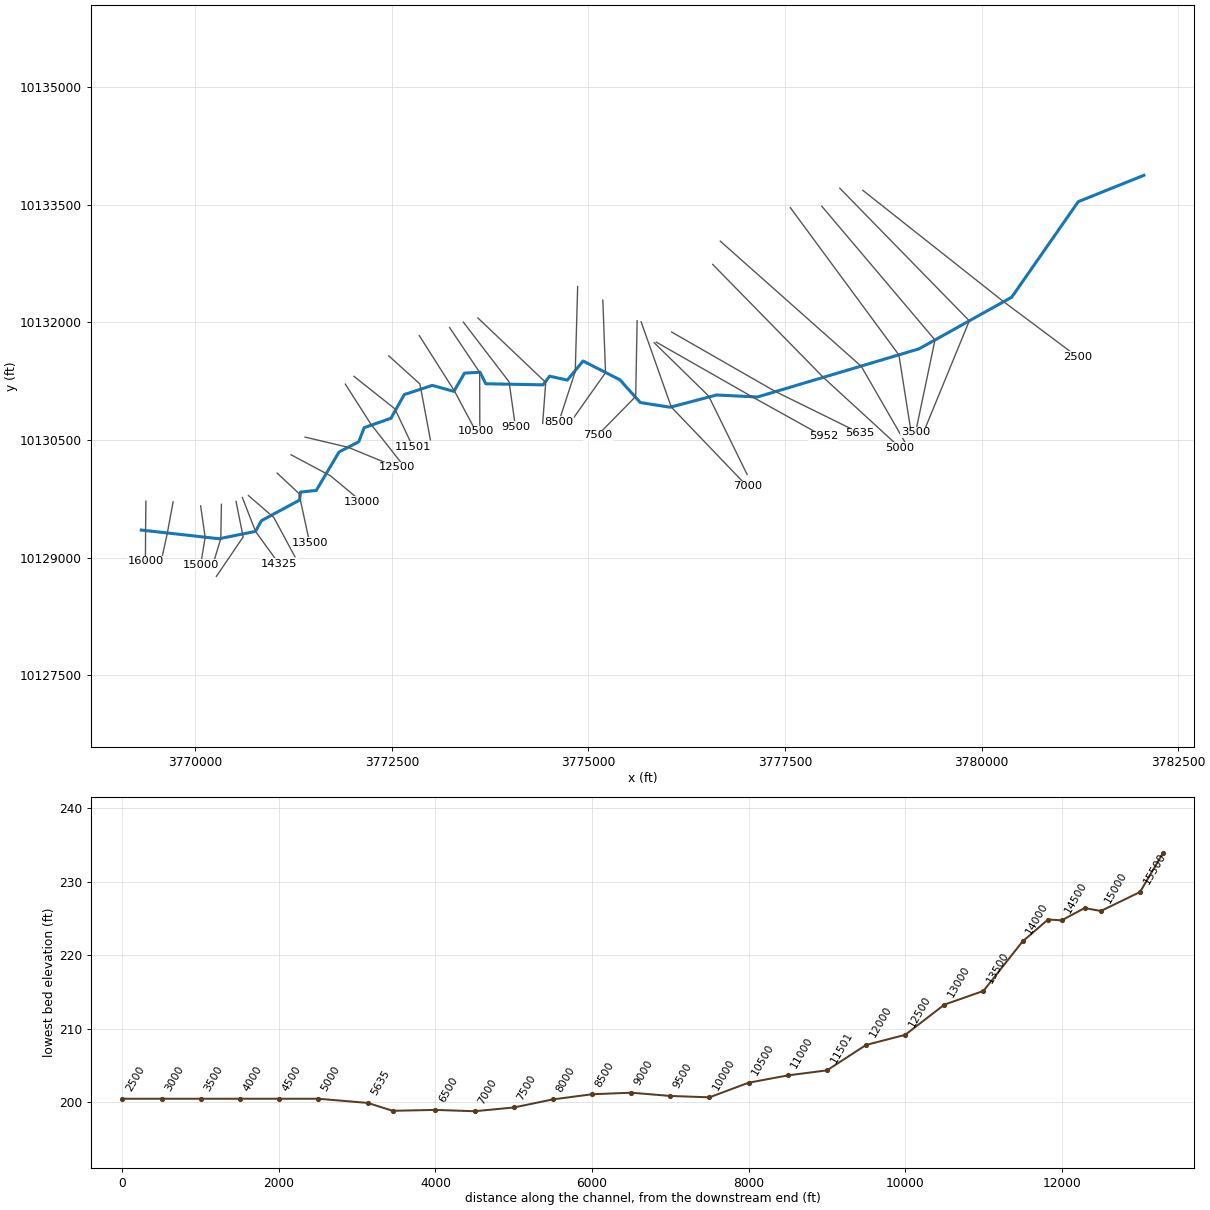
--- MARTIN CREEK.prj (project) ---

Proj Title=MARTIN CREEK Base Level Engineering
Current Plan=p01
Default Exp/Contr=0.3,0.1
English Units
Geom File=g01
Flow File=f01
Plan File=p01
Y Axis Title=Elevation
X Axis Title(PF)=Main Channel Distance
X Axis Title(XS)=Station
BEGIN DESCRIPTION:
MARTIN CREEK
END DESCRIPTION:
DSS Export Rating Curves= 0
DSS Export Rating Curve Sorted= 0
DSS Export Volume Flow Curves= 0
DXF OffsetX= 0
DXF OffsetY= 0
DXF ScaleX= 1
DXF ScaleY= 10

--- MARTIN CREEK.p01 (plan) ---

Plan Title=Multiple Run
Short Identifier=Multiple
Geom File=g01
Flow File=f01
Subcritical Flow
K Sum by GR= 0
Std Step Tol= 0.01
Critical Tol= 0.01
Num of Std Step Trials= 20
Max Error Tol= 0.3
Flow Tol Ratio= 0.001
Split Flow NTrial= 30
Split Flow Tol= 0.02
Split Flow Ratio= 0.02
Log Output Level= 0
Friction Slope Method= 1
Unsteady Friction Slope Method= 2
Unsteady Bridges Friction Slope Method= 1
Parabolic Critical Depth
Global Vel Dist=  1 , 1 , 1
Global Log Level= 0
CheckData=True
Encroach Param= -1, 0, 0, 0
BEGIN DESCRIPTION:
Multiple Run
END DESCRIPTION:

--- MARTIN CREEK.f01 (steady flow) ---

Flow Title=Multiple
Program Version=4.10
Number of Profiles= 7
Profile Names=10-year,25-year,50-year,1pct_min,100-year,1pct_plu,500-year
River Rch & RM=MARTIN CREEK,Reach-1         ,16000
     936    1315    1822     831    2509    7577    4921
River Rch & RM=MARTIN CREEK,Reach-1         ,15500
     936    1315    1822     831    2509    7577    4921
River Rch & RM=MARTIN CREEK,Reach-1         ,13500
    1268    1794    2497    1142    3448   10413    6801
River Rch & RM=MARTIN CREEK,Reach-1         ,7000
    1965    2824    3972    1831    5529   16697   11091
River Rch & RM=MARTIN CREEK,Reach-1         ,2500
    2430    3502    4932    2275    6871   20750   13801
Boundary for River Rch & Prof#=MARTIN CREEK,Reach-1         , 1
Up Type= 0
Dn Type= 3
Dn Slope=0.005
Boundary for River Rch & Prof#=MARTIN CREEK,Reach-1         , 2
Up Type= 0
Dn Type= 3
Dn Slope=0.005
Boundary for River Rch & Prof#=MARTIN CREEK,Reach-1         , 3
Up Type= 0
Dn Type= 3
Dn Slope=0.005
Boundary for River Rch & Prof#=MARTIN CREEK,Reach-1         , 4
Up Type= 0
Dn Type= 3
Dn Slope=0.005
Boundary for River Rch & Prof#=MARTIN CREEK,Reach-1         , 5
Up Type= 0
Dn Type= 3
Dn Slope=0.005
Boundary for River Rch & Prof#=MARTIN CREEK,Reach-1         , 6
Up Type= 0
Dn Type= 3
Dn Slope=0.005
Boundary for River Rch & Prof#=MARTIN CREEK,Reach-1         , 7
Up Type= 0
Dn Type= 3
Dn Slope=0.005
DSS Import GetInterval= 0
DSS Import GetPeak= 0
DSS Import FillOption= 0

--- MARTIN CREEK.g01 (geometry) ---

Geom Title=Existing Conditions
Program Version=4.10

River Reach=MARTIN CREEK    ,Reach-1
Reach XY= 30
      3769313.23     10129351.84      3770301.94     10129241.01
      3770765.92     10129335.15      3770842.13     10129471.88
      3771325.76     10129733.91      3771337.52     10129835.82
      3771538.23     10129856.84      3771828.23     10130346.84
      3772078.23     10130476.84      3772148.23     10130656.84
      3772488.23     10130776.84      3772658.42     10131079.05
      3773013.98     10131195.47      3773288.57     10131119.54
      3773424.43     10131352.41       3773621.7      10131363.3
      3773694.36     10131216.54      3774422.09     10131202.44
      3774506.13       10131313.      3774731.86     10131263.36
      3774932.32     10131506.24      3775401.02     10131266.35
      3775659.14      10130977.2      3776039.14     10130917.12
      3776629.78      10131073.3      3777149.66      10131047.9
      3779206.38      10131662.1      3780383.67     10132320.09
      3781229.43     10133536.85      3782064.29     10133873.32

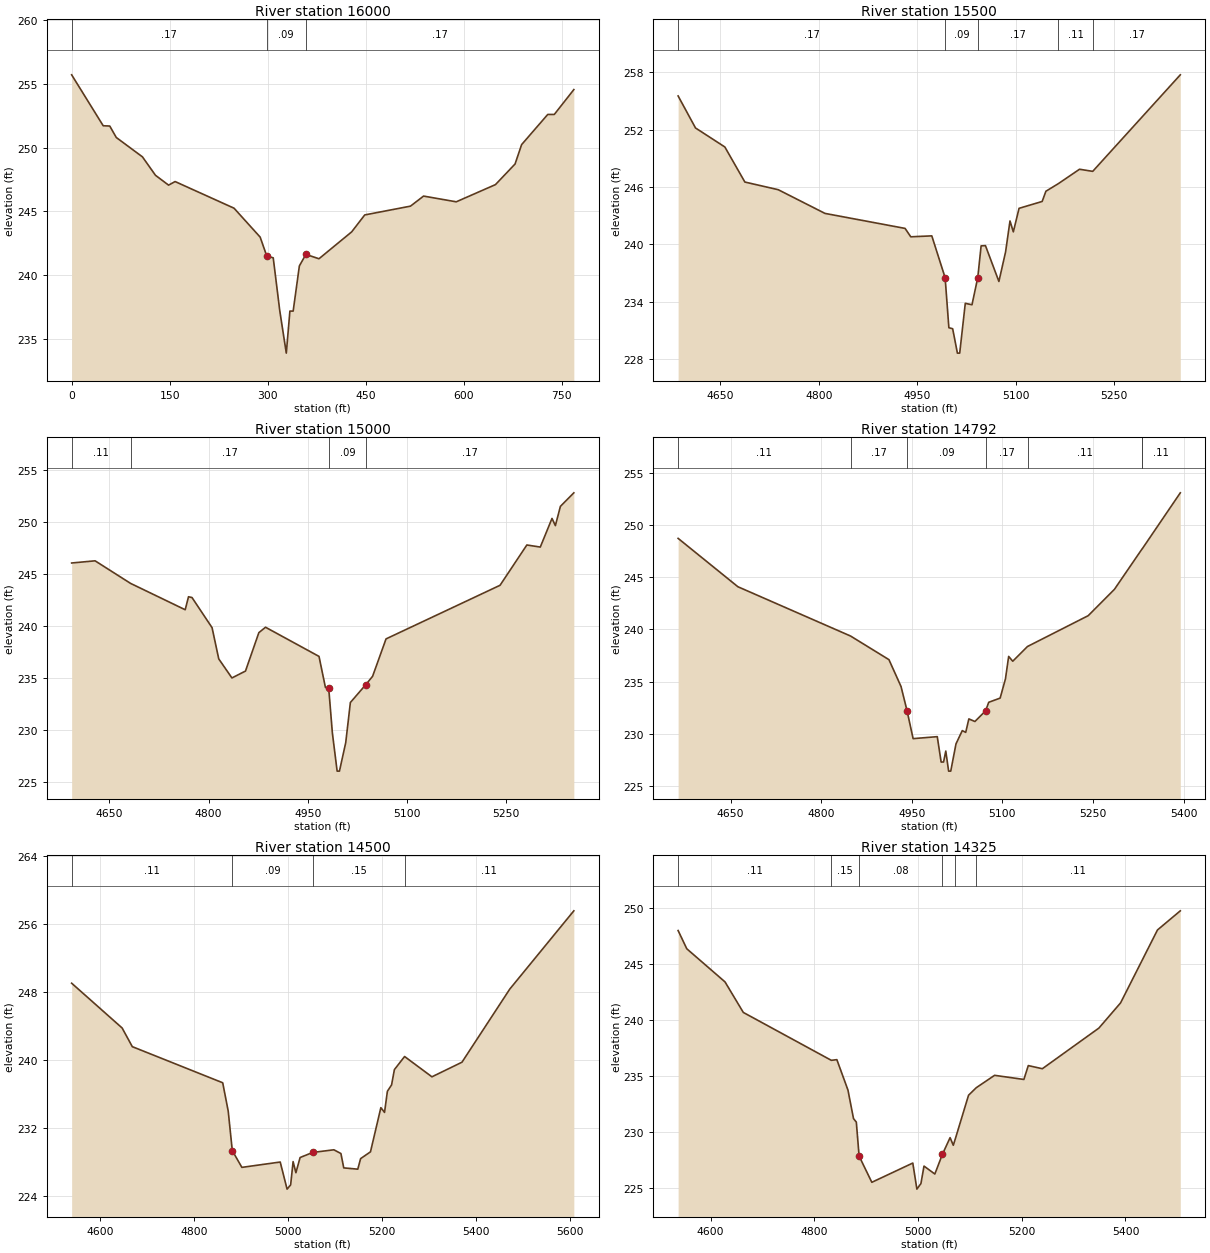
Type RM Length L Ch R = 1 ,16000   ,291,291,291
XS GIS Cut Line= 3
      3769371.96     10129719.41      3769368.19     10129384.89
      3769365.44     10128951.18
#Sta/Elev= 30
       0  255.71    48.3  251.71    58.3  251.69    68.3  250.79   108.3  249.27
   128.3  247.82   148.3  247.05   158.3  247.33   248.4  245.24   288.4  242.97
   298.4   241.5   308.4  241.34   318.4  237.19   328.4  233.86   333.9  237.16
   338.9  237.16   348.4  240.71   358.4  241.61   378.4  241.27   428.4  243.38
   448.4  244.71   518.4   245.4   538.4  246.19   588.4  245.74   648.4  247.09
   678.4  248.71   688.4  250.23   728.4   252.6   738.4   252.6   768.3  254.55
#Mann= 3 , 0 , 0
       0     .17       0   298.4     .09       0   358.4     .17       0
Bank Sta=298.4,358.4
XS Rating Curve= 0 ,0
Exp/Cntr=0.3,0.1

Type RM Length L Ch R = 1 ,15500   ,500,500,500
BEGIN DESCRIPTION:
MARTIN CREEK 31.0
END DESCRIPTION:
XS GIS Cut Line= 3
      3769717.85     10129711.06      3769642.61     10129303.65
      3769567.86     10128961.11
#Sta/Elev= 30
  4585.7  255.52  4612.2  252.17  4656.9  250.18  4687.4  246.51  4738.2  245.71
  4809.4  243.23  4931.4  241.66  4940.1  240.78  4972.1  240.88  4992.4   236.5
  4998.1  231.27  5003.9  231.16  5011.1  228.61  5014.6  228.61  5023.1  233.82
  5033.3  233.67  5042.1  236.51  5047.2  239.83  5053.8  239.86  5074.3  236.11
  5084.5  239.21  5091.2  242.44  5096.3   241.3    5105  243.76  5140.2  244.48
  5145.9  245.55    5165  246.35  5197.1  247.85  5217.2  247.63  5350.6  257.73
#Mann= 5 ,-1 , 0
  4585.7     .17       0  4992.4     .09       0  5042.1     .17       0
    5165     .11       0  5217.2     .17       0
#XS Ineff= 2 , 0
       0  4931.4  241.66  5091.2       0  242.44
Permanent Ineff=
       F       F
Bank Sta=4992.4,5042.1
XS Rating Curve= 0 ,0
Exp/Cntr=0.3,0.1

Type RM Length L Ch R = 1 ,15000   ,208,208,208
BEGIN DESCRIPTION:
MARTIN CREEK 30.0
END DESCRIPTION:
XS GIS Cut Line= 3
      3770067.85     10129661.11      3770125.51     10129258.31
      3770067.85     10128911.07
#Sta/Elev= 30
  4593.1  246.02  4628.5  246.23  4682.2  244.06  4764.7  241.53  4769.7  242.78
    4775   242.7  4805.3  239.81  4815.4  236.81  4835.3  234.98  4855.8  235.64
    4876  239.33  4886.1  239.85  4966.9  237.05  4976.6  234.07  4981.6  233.98
  4987.1   229.7  4994.3  226.03  4997.8  226.03  5007.3  228.77  5014.3  232.62
  5037.8  234.35  5047.9  235.14  5068.2  238.73  5240.5  243.88    5281  247.75
  5301.3  247.55    5319   250.3  5324.1  249.61  5331.7  251.46    5352  252.76
#Mann= 4 ,-1 , 0
  4593.1     .11       0  4682.2     .17       0  4981.6     .09       0
  5037.8     .17       0
#XS Ineff= 2 , 0
       0  4886.1  239.85               0
Permanent Ineff=
       T       F
Bank Sta=4981.6,5037.8
XS Rating Curve= 0 ,0
Exp/Cntr=0.3,0.1

Type RM Length L Ch R = 1 ,14792   ,292,292,292
BEGIN DESCRIPTION:
Mapping XS 7a0a14bd
END DESCRIPTION:
XS GIS Cut Line= 3
      3770332.26     10129680.08      3770324.36     10129243.25
      3770210.03     10128865.58
#Sta/Elev= 30
  4563.1  248.71  4662.1  244.08  4848.7  239.36  4912.2   237.1  4932.2  234.53
  4942.2   232.2  4952.2  229.54  4992.2  229.73  4998.6   227.3  5002.6   227.3
  5006.3  228.35    5011  226.43  5014.5  226.43  5023.2  229.04  5033.6  230.31
  5039.3  230.14  5044.5  231.43  5054.5  231.18  5072.2   232.2  5077.4  233.02
  5096.3  233.42  5105.1  235.26  5110.4  237.41  5117.2  236.95  5141.6  238.36
  5242.1  241.31  5285.5  243.83  5331.3   247.7  5331.7  247.72  5394.6  253.07
#Mann= 7 ,-1 , 0
  4563.1     .11       0  4848.7     .17       0  4942.2     .09       0
  5072.2     .17       0  5141.6     .11       0  5331.3     .17       0
  5331.7     .11       0
Bank Sta=4942.2,5072.2
XS Rating Curve= 0 ,0
Exp/Cntr=0.3,0.1

Type RM Length L Ch R = 1 ,14500   ,175,175,175
BEGIN DESCRIPTION:
MARTIN CREEK 29.0
END DESCRIPTION:
XS GIS Cut Line= 3
      3770518.29     10129716.38      3770608.64     10129264.02
      3770267.87      10128761.1
#Sta/Elev= 30
  4538.7     249  4646.1  243.73  4667.8  241.53  4860.2  237.28  4871.9  233.95
  4880.6  229.29    4901  227.32  4982.6  227.95  4997.2  224.76  5004.8  225.26
    5010     228    5016  226.69  5024.9  228.48  5051.9  229.08  5096.8  229.39
  5111.8  228.95  5117.8  227.26  5147.7  227.11  5153.7  228.35  5174.7  229.15
  5196.8  234.35  5204.6  233.79  5210.7  236.28  5219.6  237.03  5225.6  238.83
  5247.3  240.37  5305.5  237.98  5369.4   239.7  5471.2  248.31  5607.5  257.52
#Mann= 4 ,-1 , 0
  4538.7     .11       0  4880.6     .09       0  5051.9     .15       0
  5247.3     .11       0
Bank Sta=4880.6,5051.9
XS Rating Curve= 0 ,0
Exp/Cntr=0.3,0.1

Type RM Length L Ch R = 1 ,14325   ,325,325,325
BEGIN DESCRIPTION:
Mapping XS 8dce1990
END DESCRIPTION:
XS GIS Cut Line= 3
      3770598.65     10129766.45      3770765.92     10129335.15
      3771062.34     10128925.44
#Sta/Elev= 30
  4537.4  247.98  4554.1  246.35  4627.8  243.39  4663.1  240.66  4832.8  236.38
  4843.5  236.44  4864.9  233.72  4875.6  231.17    4881  230.86  4886.4  227.82
  4910.9  225.48  4989.9   227.2  4997.8  224.87  5005.6  225.37  5011.5  226.93
  5032.4  226.22  5047.1  227.99  5061.8  229.47    5068  228.79    5072  229.38
  5097.4  233.26  5112.2  233.93  5147.6  235.04  5204.1  234.67  5212.6  235.91
  5239.7  235.63  5348.7  239.26  5390.5  241.51  5461.7  248.03  5505.7  249.74
#Mann= 6 ,-1 , 0
  4537.4     .11       0  4832.8     .15       0  4886.4     .08       0
  5047.1     .15       0    5072     .15       0  5112.2     .11       0
Bank Sta=4886.4,5047.1
XS Rating Curve= 0 ,0
Exp/Cntr=0.3,0.1

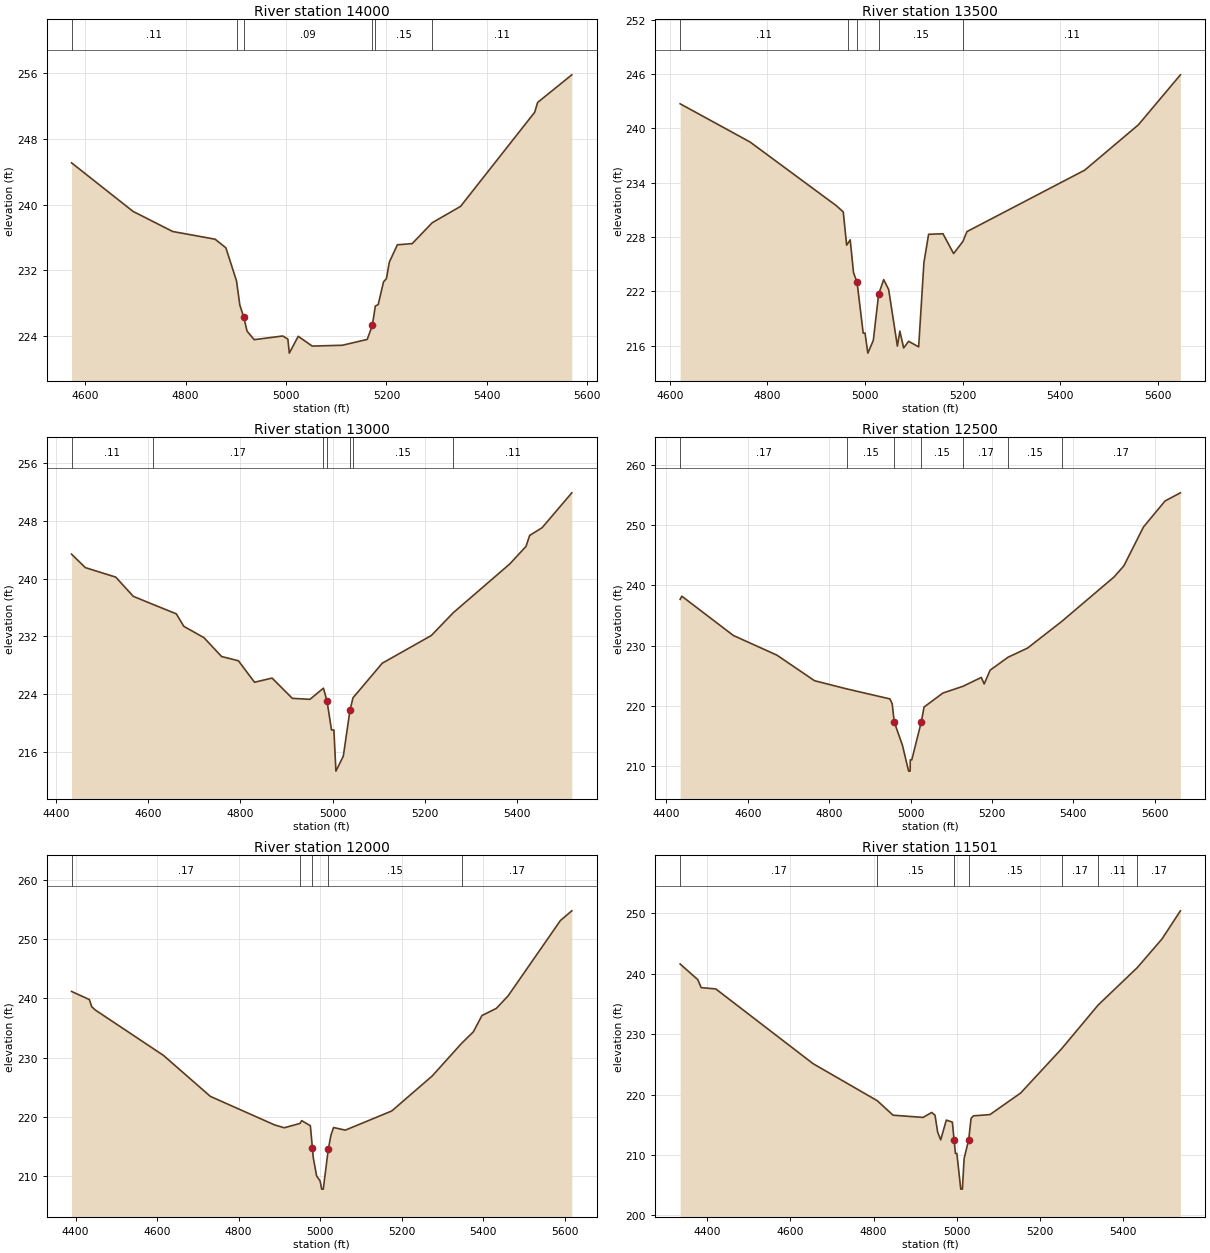
Type RM Length L Ch R = 1 ,14000   ,500,500,500
BEGIN DESCRIPTION:
MARTIN CREEK 28.0
END DESCRIPTION:
XS GIS Cut Line= 3
      3770675.36     10129791.96      3770998.49     10129512.38
      3771267.86     10129011.06
#Sta/Elev= 30
  4572.7  245.09  4695.2  239.17  4774.1  236.72  4858.6  235.78  4880.1  234.73
  4901.3  230.69  4907.9  227.74  4915.6   226.3  4922.2  224.58  4936.4  223.53
  4993.4  223.98  5003.6   223.6  5006.4  221.89  5024.2  223.94    5052  222.75
  5112.1  222.85  5161.6  223.56  5171.8  225.27  5177.8  227.63  5183.5  227.81
  5194.1  230.58  5199.8  230.97  5205.8  233.01  5221.7   235.1  5251.2  235.24
  5291.1  237.79  5347.5  239.78  5495.2  251.26    5501  252.45  5569.1  255.82
#Mann= 6 ,-1 , 0
  4572.7     .11       0  4901.3     .12       0  4915.6     .09       0
  5171.8     .15       0  5177.8     .15       0  5291.1     .11       0
Bank Sta=4915.6,5171.8
XS Rating Curve= 0 ,0
Exp/Cntr=0.3,0.1

Type RM Length L Ch R = 1 ,13500   ,500,500,500
BEGIN DESCRIPTION:
MARTIN CREEK 27.0
END DESCRIPTION:
XS GIS Cut Line= 3
      3771041.74     10130077.01      3771318.35     10129818.36
      3771454.75     10129187.03
#Sta/Elev= 30
  4621.3  242.71  4764.4  238.49  4941.2  231.45  4955.4  230.76  4962.3  227.09
  4964.7  227.28  4969.6  227.68  4976.4  224.05  4983.7  222.98  4996.2  217.37
    5000  217.37  5005.7  215.16  5016.9  216.56  5027.9  221.68  5038.2  223.28
  5048.4  222.18  5066.2  215.94  5071.3  217.59  5079.1  215.73  5089.3  216.47
  5109.8  215.85  5120.6  225.18  5130.2  228.29  5159.6  228.35  5181.4  226.16
  5200.4   227.5  5208.8  228.59    5450  235.38  5559.9  240.39  5645.9  245.91
#Mann= 5 ,-1 , 0
  4621.3     .11       0  4964.7     .17       0  4983.7     .09       0
  5027.9     .15       0  5200.4     .11       0
Bank Sta=4983.7,5027.9
XS Rating Curve= 0 ,0
Exp/Cntr=0.3,0.1

Type RM Length L Ch R = 1 ,13000   ,500,500,500
BEGIN DESCRIPTION:
MARTIN CREEK 26.0
END DESCRIPTION:
XS GIS Cut Line= 3
      3771217.84     10130311.08      3771718.23     10130044.02
      3772117.82      10129711.1
#Sta/Elev= 30
  4432.8  243.39  4462.9  241.52  4528.8  240.21    4567  237.54  4609.7  236.42
  4660.5  235.11  4676.8  233.38  4720.7   231.8  4758.9  229.19  4795.5   228.6
  4830.5  225.62  4868.7   226.2  4912.6  223.39  4950.9  223.25  4980.3   224.8
  4988.2  222.97  4997.8     219    5003     219  5007.4  213.29  5023.5  215.37
  5037.9  221.71  5044.4  223.45  5108.1  228.26  5214.9  232.11  5262.5  235.27
  5385.4  242.04  5420.6  244.47  5428.4  245.98  5455.7  247.07  5520.1   251.9
#Mann= 7 ,-1 , 0
  4432.8     .11       0  4609.7     .17       0  4980.3     .15       0
  4988.2     .09       0  5037.9     .12       0  5044.4     .15       0
  5262.5     .11       0
#XS Ineff= 2 , 0
       0  4868.7   226.2               0
Permanent Ineff=
       F       F
Bank Sta=4988.2,5037.9
XS Rating Curve= 0 ,0
Exp/Cntr=0.3,0.1

Type RM Length L Ch R = 1 ,12500   ,500,500,500
BEGIN DESCRIPTION:
MARTIN CREEK 25.0
END DESCRIPTION:
XS GIS Cut Line= 3
      3771396.56     10130536.49      3771947.15     10130405.77
      3772559.81     10130152.62
#Sta/Elev= 30
  4434.1  237.65  4438.2  238.18  4564.8  231.67  4671.8  228.41  4764.3  224.17
  4843.8  222.81  4949.3  221.16  4954.9  220.36  4960.1  217.31  4980.2  213.46
  4995.3  209.19    4999  209.19  4999.2  209.69  4999.3  211.06  5003.1  211.06
  5026.6  217.39  5033.2  219.81  5079.8  222.14  5128.5  223.24  5173.9  224.72
  5180.9  223.63  5195.5  225.92  5239.2  228.05  5287.4  229.58  5371.3  233.99
  5500.3  241.39  5524.2  243.23  5572.1  249.64  5625.3  253.97  5662.9  255.31
#Mann= 7 ,-1 , 0
  4434.1     .17       0  4843.8     .15       0  4960.1     .09       0
  5026.6     .15       0  5128.5     .17       0  5239.2     .15       0
  5371.3     .17       0
#XS Ineff= 2 , 0
       0                  5173.9       0  224.72
Permanent Ineff=
       F       F
Bank Sta=4960.1,5026.6
XS Rating Curve= 0 ,0
Exp/Cntr=0.3,0.1

Type RM Length L Ch R = 1 ,12000   ,499,499,499
BEGIN DESCRIPTION:
MARTIN CREEK 24.0
END DESCRIPTION:
XS GIS Cut Line= 3
       3771908.4     10131211.22      3772236.29     10130696.84
      3772617.85     10130211.08
#Sta/Elev= 30
    4390  241.15  4433.6  239.79  4439.5  238.57  4448.8     238  4615.5  230.37
  4730.7  223.45  4888.3  218.64    4912  218.16  4950.6  218.89  4954.9  219.36
  4976.1   218.5 4981.12  214.72  4983.1  213.18  4991.3  210.06    5000  209.18
  5003.9  207.81  5007.8  207.81  5020.1  214.56  5026.6   216.9    5033   218.2
  5061.9  217.76  5175.8  220.99  5275.2   226.9  5347.1  232.39  5376.1  234.34
  5397.2  237.09  5432.4  238.29  5461.3   240.4  5589.7  253.11  5617.7  254.75
#Mann= 5 ,-1 , 0
    4390     .17       0  4950.6     .15       0 4981.12     .09       0
  5020.1     .15       0  5347.1     .17       0
Bank Sta=4981.12,5020.1
XS Rating Curve= 0 ,0
Exp/Cntr=0.3,0.1

Type RM Length L Ch R = 1 ,11501   ,501,501,501
BEGIN DESCRIPTION:
MARTIN CREEK 23.0
END DESCRIPTION:
XS GIS Cut Line= 3
      3772017.86     10131311.06      3772538.23     10130896.84
      3772767.85     10130411.08
#Sta/Elev= 30
  4334.9  241.63  4377.3  239.04  4385.4  237.72  4420.6   237.5  4654.4  225.13
  4808.6     219  4846.6   216.6  4918.7  216.23  4939.5  217.05  4947.5   216.6
  4953.9  213.77  4961.2  212.52  4974.7  215.79  4989.2  215.45 4993.36  212.51
  4996.6  210.27    5000  210.27  5009.4  204.36  5013.3  204.36  5017.4  209.41
  5028.5  212.55  5034.1  216.06  5039.7  216.49  5079.6   216.7  5153.5  220.28
  5251.6  227.58  5339.5  234.83  5433.7  241.03  5493.1  245.78  5537.3  250.43
#Mann= 7 ,-1 , 0
  4334.9     .17       0  4808.6     .15       0 4993.36     .09       0
  5028.5     .15       0  5251.6     .17       0  5339.5     .11       0
  5433.7     .17       0
Bank Sta=4993.36,5028.5
XS Rating Curve= 0 ,0
Exp/Cntr=0.3,0.1

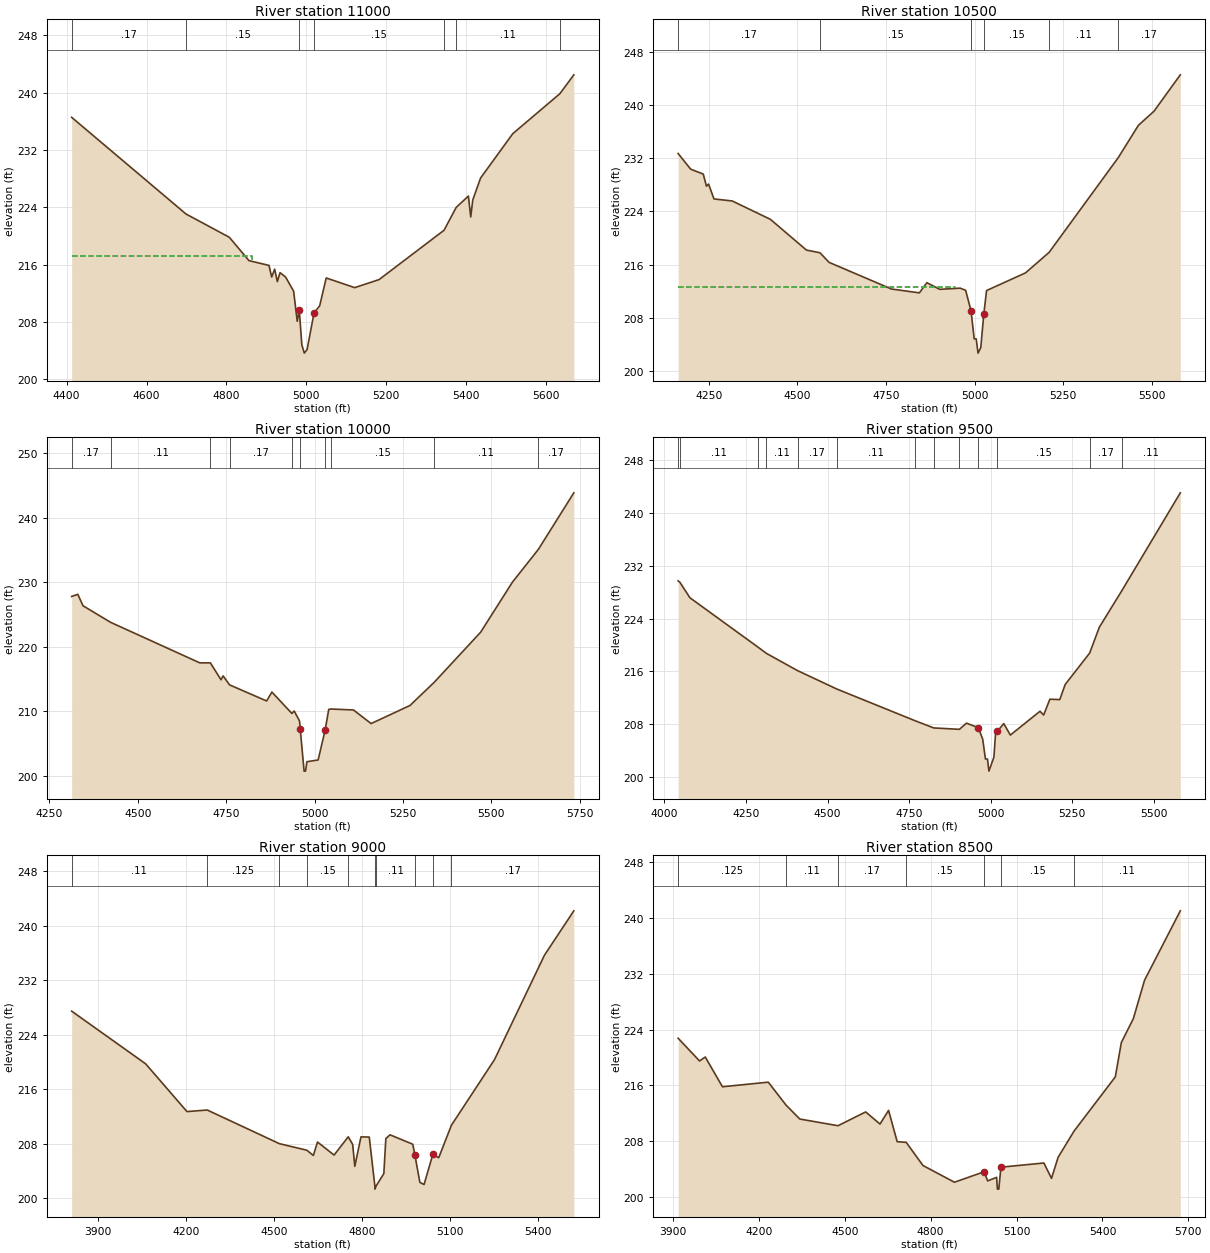
Type RM Length L Ch R = 1 ,11000   ,500,500,500
BEGIN DESCRIPTION:
MARTIN CREEK 22.0
END DESCRIPTION:
XS GIS Cut Line= 4
      3772460.99      10131571.8      3772854.77     10131215.16
      3772866.88     10131160.26      3772990.27     10130501.62
#Sta/Elev= 30
  4412.5  236.58  4698.8  223.09  4807.3  219.84  4856.6  216.58  4906.7  215.91
  4913.4  214.29  4920.9  215.39  4927.6  213.65  4934.4   214.9  4948.4  214.28
  4968.4  212.31  4977.4  208.12  4982.6  209.64  4988.9  204.84  4995.1  203.67
  5002.1  204.17  5019.5  209.29  5033.6  210.27    5050  214.16  5121.3  212.81
  5182.3  213.93  5345.1  220.82  5375.5  224.01  5406.1  225.59  5411.9  222.68
    5417  225.05  5436.7  228.12  5517.1  234.29  5635.2  239.88  5670.1  242.51
#Mann= 7 ,-1 , 0
  4412.5     .17       0  4698.8     .15       0  4982.6     .09       0
  5019.5     .15       0  5345.1     .17       0  5375.5     .11       0
  5635.2     .17       0
#XS Ineff= 2 , 0
       0  4864.1   217.2               0
Permanent Ineff=
       F       F
Bank Sta=4982.6,5019.5
XS Rating Curve= 0 ,0
Exp/Cntr=0.3,0.1

Type RM Length L Ch R = 1 ,10500   ,500,500,500
BEGIN DESCRIPTION:
MARTIN CREEK 21.0
END DESCRIPTION:
XS GIS Cut Line= 3
      3772848.39     10131831.04       3773296.1     10131124.09
      3773567.83     10130611.11
#Sta/Elev= 30
  4163.2  232.73  4198.7  230.37  4234.2  229.63  4243.2   227.8  4249.1  228.13
  4264.4  225.89  4316.1  225.58  4423.6  222.82  4525.4  218.19  4563.5  217.79
  4589.3  216.34  4765.3  212.33  4844.1  211.75  4865.3  213.28  4901.7  212.28
  4959.3  212.46  4974.6  212.14  4989.9  209.06  4998.8  204.83  5004.5  204.83
  5009.7  202.68  5017.4  203.51    5026  208.59  5033.7   212.1  5143.7  214.76
  5210.3  217.85  5405.6  232.12  5462.4  236.98  5506.4   239.1  5580.5  244.57
#Mann= 6 ,-1 , 0
  4163.2     .17       0  4563.5     .15       0  4989.9     .09       0
    5026     .15       0  5210.3     .11       0  5405.6     .17       0
#XS Ineff= 2 , 0
       0  4944.4  212.62               0
Permanent Ineff=
       F       F
Bank Sta=4989.9,5026
XS Rating Curve= 0 ,0
Exp/Cntr=0.3,0.1

Type RM Length L Ch R = 1 ,10000   ,500,500,500
BEGIN DESCRIPTION:
MARTIN CREEK 20.0
END DESCRIPTION:
XS GIS Cut Line= 3
      3773234.54     10131932.46      3773616.84      10131361.3
      3773618.66      10130627.5
#Sta/Elev= 30
  4312.7   227.8    4330  228.13    4345  226.35    4423  223.78  4675.4  217.49
  4705.3  217.49  4735.3  214.87  4741.3  215.47  4759.7  214.07  4864.4  211.58
  4879.4  212.96  4935.9  209.64  4942.5  210.02  4957.5  208.48 4959.44   207.3
  4970.5  200.69  4974.5  200.69  4978.5  202.15  5010.2  202.42  5030.2   207.1
  5040.2  210.27  5046.9  210.33  5110.2  210.18  5160.2  208.07  5270.2  210.88
  5338.6  214.47  5470.2  222.26  5560.2  230.03  5633.5  235.11  5733.8  243.88
#Mann= 10 ,-1 , 0
  4312.7     .17       0    4423     .11       0  4705.3     .15       0
  4759.7     .17       0  4935.9     .11       0 4959.44     .07       0
  5030.2     .15       0  5046.9     .15       0  5338.6     .11       0
  5633.5     .17       0
#XS Ineff= 2 , 0
       0  4879.4  212.96               0
Permanent Ineff=
       F       F
Bank Sta=4959.44,5030.2
XS Rating Curve= 0 ,0
Exp/Cntr=0.3,0.1

Type RM Length L Ch R = 1 ,9500    ,500,500,500
BEGIN DESCRIPTION:
MARTIN CREEK 19.0
END DESCRIPTION:
XS GIS Cut Line= 3
      3773409.04     10132002.24      3773990.68     10131241.02
      3774072.02     10130665.23
#Sta/Elev= 30
    4042  229.74  4047.5  229.52  4078.1  227.18  4287.9  219.65  4312.3  218.75
    4408  216.13  4528.2  213.34  4768.6  208.52  4825.7  207.43  4904.3  207.22
    4926  208.16  4962.2  207.47  4975.8  205.72  4984.1  202.73  4990.4  202.71
  4994.8  200.88    5010  202.98  5015.3  206.66  5020.4   206.9  5040.3  208.09
  5060.5  206.35  5151.4  209.96  5162.6  209.39  5181.7  211.79    5212  211.73
  5228.6  214.02  5303.7  218.79  5333.2   222.7  5402.4  228.26  5581.5  243.09
#Mann= 13 ,-1 , 0
    4042    .125       0  4047.5     .11       0  4287.9     .17       0
  4312.3     .11       0    4408     .17       0  4528.2     .11       0
  4768.6     .17       0  4825.7     .15       0  4904.3     .17       0
  4962.2     .09       0  5020.4     .15       0  5303.7     .17       0
  5402.4     .11       0
Bank Sta=4962.2,5020.4
XS Rating Curve= 0 ,0
Exp/Cntr=0.3,0.1

Type RM Length L Ch R = 1 ,9000    ,500,500,500
BEGIN DESCRIPTION:
MARTIN CREEK 18.0
END DESCRIPTION:
XS GIS Cut Line= 3
      3773594.64     10132054.69      3774456.96     10131233.46
      3774417.85     10130711.03
#Sta/Elev= 30
  3809.2  227.44  4061.8  219.71    4203   212.7  4272.1  212.93  4518.6  207.99
  4612.3  207.03  4634.5  206.26  4648.7  208.23  4705.3  206.32  4753.7     209
  4768.8  207.87    4776  204.66  4797.1  208.99  4825.4  208.96  4844.4  201.82
  4844.8  201.32  4849.2  201.82  4875.1  203.59    4882  208.74  4896.2  209.29
  4973.9  207.91  4981.1  206.38  4998.1  202.32  5012.4  201.99  5042.5  206.42
  5062.6  205.93  5105.7  210.68  5253.1  220.33  5423.6  235.65  5523.9  242.16
#Mann= 10 ,-1 , 0
  3809.2     .11       0  4272.1    .125       0  4518.6     .17       0
  4612.3     .15       0  4753.7     .11       0  4844.4     .08       0
  4849.2     .11       0  4981.1     .07       0  5042.5     .17       0
  5105.7     .17       0
#XS Ineff= 2 , 0
       0  4896.2  209.29               0
Permanent Ineff=
       T       F
Bank Sta=4981.1,5042.5
XS Rating Curve= 0 ,0
Exp/Cntr=0.3,0.1

Type RM Length L Ch R = 1 ,8500    ,500,500,500
BEGIN DESCRIPTION:
MARTIN CREEK 17.0
END DESCRIPTION:
XS GIS Cut Line= 3
      3774863.17     10132455.91      3774832.43     10131374.24
      3774624.99     10130735.17
#Sta/Elev= 30
  3917.9  222.77  3992.8   219.5  4012.8  220.07  4072.8   215.8  4232.9  216.46
  4294.6  213.18  4342.9  211.17  4476.4  210.21    4573  212.19    4623  210.45
    4653  212.41    4683  207.92  4714.6  207.82  4773.1   204.5  4883.1   202.1
  4986.6   203.6  4999.1  202.29  5030.3   202.8  5033.2  201.11    5038  201.11
  5045.4  204.26  5195.4  204.86  5222.1  202.66  5245.1  205.68    5301  209.45
  5444.9  217.22  5465.9  222.14    5508  225.59    5547  231.09  5671.9  241.05
#Mann= 7 ,-1 , 0
  3917.9    .125       0  4294.6     .11       0  4476.4     .17       0
  4714.6     .15       0  4986.6     .09       0  5045.4     .15       0
    5301     .11       0
Bank Sta=4986.6,5045.4
XS Rating Curve= 0 ,0
Exp/Cntr=0.3,0.1

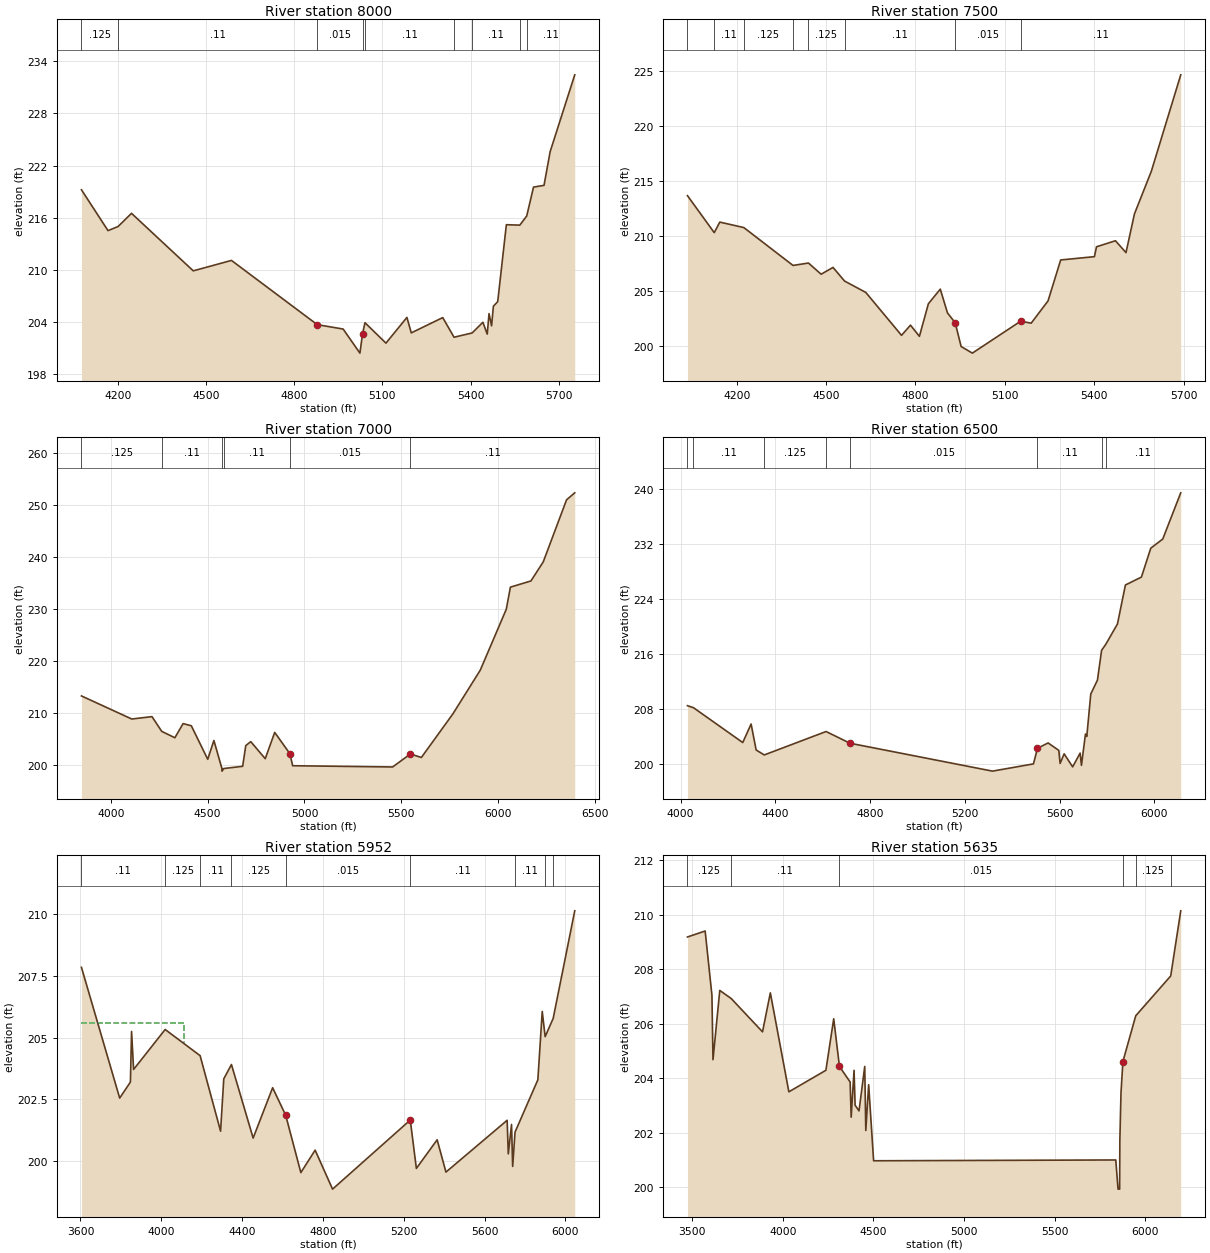
Type RM Length L Ch R = 1 ,8000    ,500,500,500
BEGIN DESCRIPTION:
MARTIN CREEK 16.0
END DESCRIPTION:
XS GIS Cut Line= 3
      3775183.07      10132281.4      3775217.52     10131357.44
      3774782.31     10130740.87
#Sta/Elev= 30
  4075.4  219.21  4165.8  214.51  4200.1  214.98  4245.8   216.5    4456  209.88
  4586.1  211.08    4878  203.69  4966.3  203.18  5023.4  200.41  5032.3  202.64
  5040.6  203.91    5112  201.56  5183.4  204.52  5198.2  202.74  5305.3   204.5
  5343.8  202.24  5405.3  202.73    5442  203.96  5456.8   202.6  5462.9  204.96
  5471.6  203.55  5477.7   205.8  5492.5  206.34  5521.9  215.19  5567.6  215.14
  5591.2  216.19  5614.4  219.52  5650.1  219.72    5671   223.6  5754.7  232.44
#Mann= 9 ,-1 , 0
  4075.4    .125       0  4200.1     .11       0    4878    .015       0
  5032.3    .065       0  5040.6     .11       0  5343.8    .125       0
  5405.3     .11       0  5567.6    .125       0  5591.2     .11       0
#XS Ineff= 2 , 0
       0                  5477.7       0   205.8
Permanent Ineff=
       F       F
Bank Sta=4878,5032.3
XS Rating Curve= 0 ,0
Exp/Cntr=0.3,0.1

Type RM Length L Ch R = 1 ,7500    ,500,500,500
BEGIN DESCRIPTION:
MARTIN CREEK 15.0
END DESCRIPTION:
XS GIS Cut Line= 3
       3775619.3     10132019.68      3775601.09     10131054.35
      3775117.88      10130561.1
#Sta/Elev= 30
  4034.5  213.66  4124.4  210.29  4143.1  211.25  4223.8  210.75  4388.9   207.3
  4440.7  207.52  4483.2   206.5  4523.2  207.12  4561.8  205.88  4633.2  204.84
  4753.2  200.93  4783.2  201.86  4813.2  200.84  4843.3  203.81  4883.3  205.14
  4907.3  202.98  4933.3  202.07  4953.3  199.91  4990.9  199.31  5153.1  202.22
  5188.4  202.04    5245  204.07  5287.4   207.8  5400.6   208.1  5407.7     209
  5471.3  209.55  5506.7  208.47    5535  211.99  5591.6  215.87  5690.5  224.67
#Mann= 8 ,-1 , 0
  4034.5    .125       0  4124.4     .11       0  4223.8    .125       0
  4388.9     .11       0  4440.7    .125       0  4561.8     .11       0
  4933.3    .015       0  5153.1     .11       0
#XS Ineff= 2 , 0
       0  4883.3  205.14               0
Permanent Ineff=
       T       F
Bank Sta=4933.3,5153.1
XS Rating Curve= 0 ,0
Exp/Cntr=0.3,0.1

Type RM Length L Ch R = 1 ,7000    ,500,500,500
BEGIN DESCRIPTION:
MARTIN CREEK 14.0
END DESCRIPTION:
XS GIS Cut Line= 3
      3775670.37     10132006.02      3776053.66     10130919.97
      3777017.82      10129911.1
#Sta/Elev= 30
  3848.3  213.29  4108.1  208.84  4212.6   209.3  4262.8  206.46  4330.7  205.23
  4373.2  207.96  4415.6  207.54  4500.4  201.08  4532.2   204.7  4573.7   199.3
  4574.2   198.8  4583.2   199.3  4680.7  199.73  4696.8  203.72  4722.5  204.48
  4797.3   201.2  4846.2  206.26  4924.6  202.16    4939  199.84  5454.9   199.6
  5546.8   202.1  5603.5  201.43  5766.1  209.82  5907.6  218.25  6041.9  229.98
  6063.3  234.25  6169.3  235.44  6232.8  239.11  6353.2  251.07  6395.5  252.42
#Mann= 6 ,-1 , 0
  3848.3    .125       0  4262.8     .11       0  4573.7     .09       0
  4583.2     .11       0  4924.6    .015       0  5546.8     .11       0
#XS Ineff= 2 , 0
       0  4846.2  206.26               0
Permanent Ineff=
       T       F
Bank Sta=4924.6,5546.8
XS Rating Curve= 0 ,0
Exp/Cntr=0.3,0.1

Type RM Length L Ch R = 1 ,6500    ,548,548,548
BEGIN DESCRIPTION:
MARTIN CREEK 13.0
END DESCRIPTION:
XS GIS Cut Line= 3
      3775836.26     10131739.61       3776529.3     10131059.79
      3777017.85     10130061.08
#Sta/Elev= 30
  4029.2  208.48  4054.5  208.19  4262.6  203.13  4297.9  205.82  4319.2  202.05
  4353.4  201.33  4614.4  204.73  4715.3  203.03    5317  198.98    5490  200.03
  5506.9   202.3  5551.9  203.07    5597  201.99  5602.5   200.1  5619.5  201.49
  5655.4   199.6    5687   201.6  5692.6  199.82  5709.5  204.37  5715.1  204.01
    5732  210.18  5760.1  212.19  5777.6  216.52  5794.8  217.36  5844.6  220.34
  5878.2     226  5945.8  227.15  5985.2  231.34  6035.8  232.67  6111.8  239.38
#Mann= 8 ,-1 , 0
  4029.2    .125       0  4054.5     .11       0  4353.4    .125       0
  4614.4     .11       0  4715.3    .015       0  5506.9     .11       0
  5777.6    .125       0  5794.8     .11       0
#XS Ineff= 2 , 0
       0  4297.9  205.82               0
Permanent Ineff=
       F       F
Bank Sta=4715.3,5506.9
XS Rating Curve= 0 ,0
Exp/Cntr=0.3,0.1

Type RM Length L Ch R = 1 ,5952    ,317,317,317
BEGIN DESCRIPTION:
MARTIN CREEK 12.0
END DESCRIPTION:
XS GIS Cut Line= 3
      3775863.55     10131746.88      3777074.73     10131054.73
        3777989.     10130545.34
#Sta/Elev= 30
    3605  207.85  3794.2  202.55  3847.3   203.2    3853  205.25  3863.1  203.71
  4019.3  205.33  4192.3  204.27  4293.6  201.21  4309.4  203.33  4347.4  203.91
  4454.8  200.93  4551.3  202.97  4616.1  201.85  4690.9  199.53  4761.7  200.44
  4847.9  198.86  5232.5  201.66  5262.7   199.7  5365.6  200.86  5409.1  199.55
    5712  201.65  5717.7  200.29  5733.7  201.48  5739.4  199.78    5751  201.17
    5864  203.29  5885.7  206.06  5900.1  205.04  5939.9  205.78  6046.6  210.14
#Mann= 9 ,-1 , 0
    3605     .11       0  4019.3    .125       0  4192.3     .11       0
  4347.4    .125       0  4616.1    .015       0  5232.5     .11       0
    5751     .11       0  5900.1    .125       0  5939.9     .11       0
#XS Ineff= 2 , 0
       0  4110.7  205.58  5885.7       0  206.06
Permanent Ineff=
       F       F
Bank Sta=4616.1,5232.5
XS Rating Curve= 0 ,0
Exp/Cntr=0.3,0.1

Type RM Length L Ch R = 1 ,5635    ,635,635,635
BEGIN DESCRIPTION:
MARTIN CREEK 11.0
END DESCRIPTION:
XS GIS Cut Line= 3
      3776058.89     10131875.11      3777381.93     10131115.28
      3778453.39     10130587.26
#Sta/Elev= 30
  3474.3  209.18  3571.9   209.4  3609.3  207.04  3615.1  204.68  3652.5  207.22
  3715.9  206.92  3888.2   205.7  3931.4  207.13  4033.5   203.5  4237.7  204.29
  4280.8  206.18  4312.4  204.43  4371.4  203.86  4377.1  202.57    4393  204.29
  4398.7  203.01  4420.3   202.8  4451.9  204.43  4457.7  202.08  4473.5  203.76
  4500.8  200.97  5836.2     201  5848.7  199.93  5857.5  199.93  5858.7  201.72
    5865  203.47  5875.5  204.61  5946.3  206.29  6139.1  207.75  6194.5  210.14
#Mann= 6 ,-1 , 0
  3474.3    .125       0  3715.9     .11       0  4312.4    .015       0
  5875.5     .15       0  5946.3    .125       0  6139.1     .15       0
#XS Ineff= 2 , 0
       0  4280.8  206.18               0
Permanent Ineff=
       F       F
Bank Sta=4312.4,5875.5
XS Rating Curve= 0 ,0
Exp/Cntr=0.3,0.1

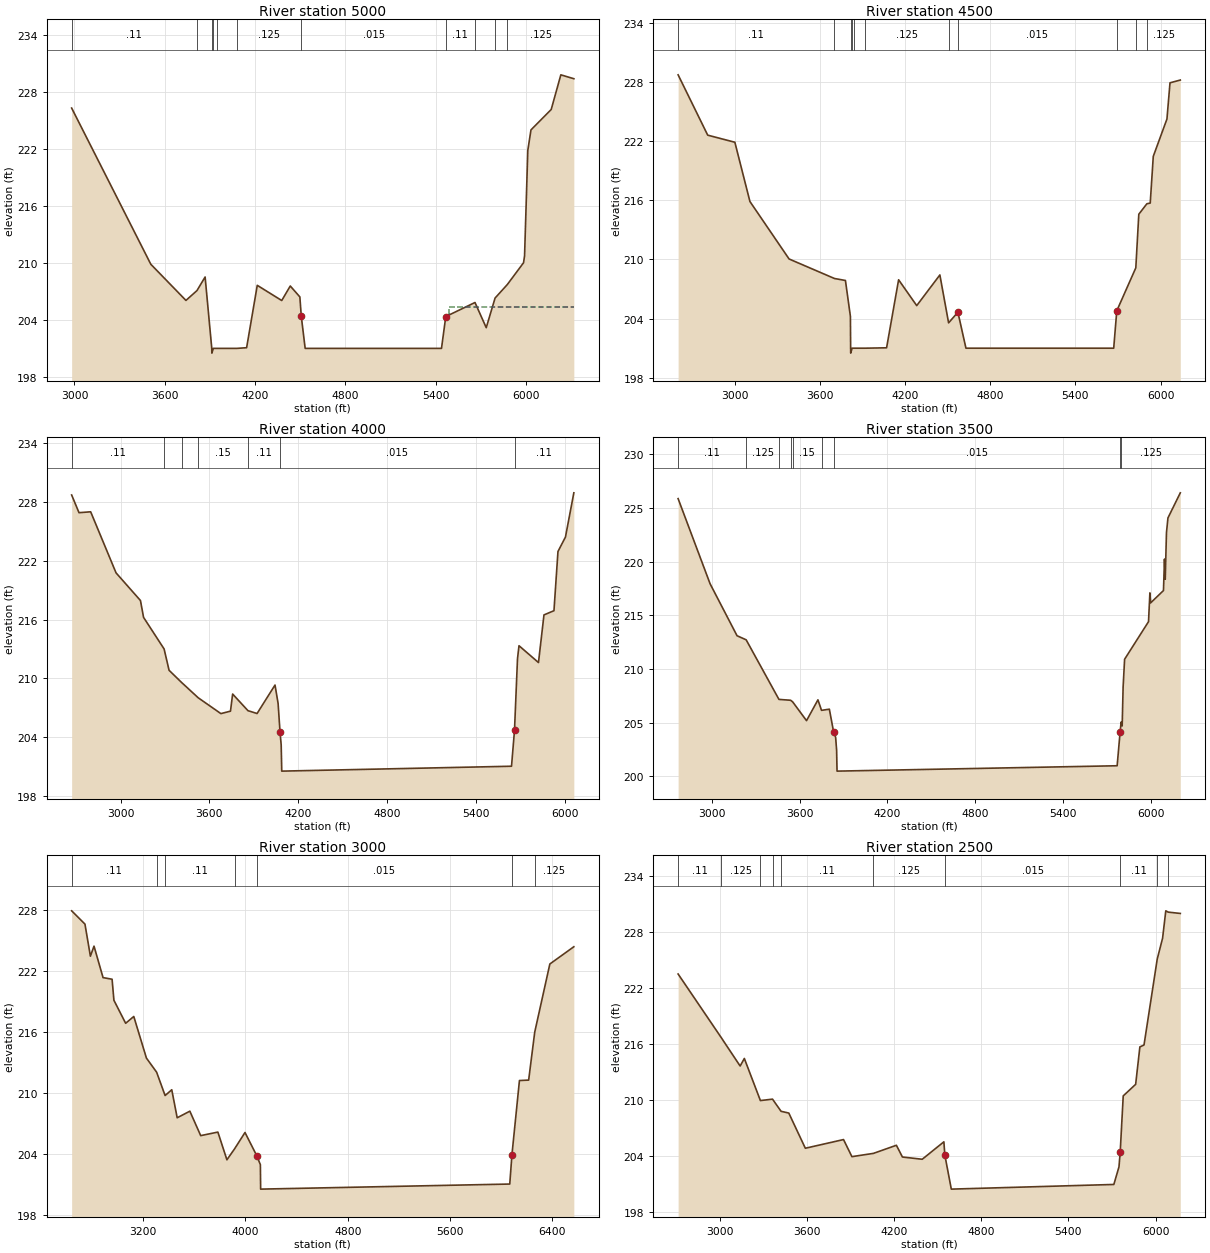
Type RM Length L Ch R = 1 ,5000    ,500,500,500
BEGIN DESCRIPTION:
MARTIN CREEK 10.0
END DESCRIPTION:
XS GIS Cut Line= 3
      3776580.65     10132737.51      3777991.66      10131293.7
      3778961.36     10130402.38
#Sta/Elev= 30
  2981.2  226.31  3507.1  209.86  3740.5  206.05  3813.8  207.09  3867.8  208.52
    3912     201  3912.5   200.5  3922.4     201  3946.3     201  4078.8     201
  4143.5  201.07  4214.2  207.64  4376.8  206.04  4433.4  207.57  4497.1  206.42
  4506.5  204.39  4532.4     201    5438     201  5466.4  204.35  5660.5  205.83
  5735.2  203.18  5793.9   206.3  5875.1  207.72  5983.1  210.02  5989.8  210.75
  6011.4  221.86  6032.4  224.01  6166.8  226.16  6230.8  229.81  6317.1   229.4
#Mann= 11 ,-1 , 0
  2981.2     .11       0  3813.8    .125       0    3912     .08       0
  3922.4    .125       0  3946.3     .15       0  4078.8    .125       0
  4506.5    .015       0  5466.4     .11       0  5660.5    .125       0
  5793.9     .15       0  5875.1    .125       0
#XS Ineff= 2 , 0
       0  4433.4  207.57  5487.4       0  205.39
Permanent Ineff=
       F       F
Bank Sta=4506.5,5466.4
XS Rating Curve= 0 ,0
Exp/Cntr=0.3,0.1

Type RM Length L Ch R = 1 ,4500    ,500,500,500
BEGIN DESCRIPTION:
MARTIN CREEK 9.0
END DESCRIPTION:
XS GIS Cut Line= 3
      3776676.62     10133034.33      3778470.14     10131438.81
      3779037.76     10130450.98
#Sta/Elev= 30
  2599.5  228.73  2808.1  222.61  2999.5  221.89  3105.7  215.88  3381.7  210.05
  3701.6  208.07  3778.9  207.87    3814  204.22  3815.5     201    3816   200.5
  3825.9     201  3838.7     201  3913.3     201    4069  201.04  4153.7  207.94
  4281.4  205.32  4444.5  208.43  4506.1  203.57  4571.6  204.65  4628.4     201
  5669.9     201  5691.5  204.79  5825.7  209.15  5846.8  214.59  5903.7  215.65
  5927.3  215.72  5948.8  220.46  6045.2  224.25  6066.7  227.92  6139.3   228.2
#Mann= 11 ,-1 , 0
  2599.5     .11       0  3701.6    .125       0  3815.5     .08       0
  3825.9    .125       0  3838.7     .15       0  3913.3    .125       0
  4506.1     .11       0  4571.6    .015       0  5691.5     .11       0
  5825.7     .15       0  5903.7    .125       0
Bank Sta=4571.6,5691.5
XS Rating Curve= 0 ,0
Exp/Cntr=0.3,0.1

Type RM Length L Ch R = 1 ,4000    ,500,500,500
BEGIN DESCRIPTION:
MARTIN CREEK 8.0
END DESCRIPTION:
XS GIS Cut Line= 3
      3777567.84     10133461.09      3778948.62     10131583.92
      3779114.01     10130535.18
#Sta/Elev= 30
  2669.7  228.73  2719.4  226.92  2798.2  227.01  2969.5  220.77  3134.5  217.94
  3155.4  216.22  3294.1  212.99  3327.7  210.81  3412.5  209.56  3524.4     208
  3677.7  206.38  3742.5  206.63  3757.1  208.38  3860.6  206.68  3922.2  206.39
  4043.3   209.3  4064.2  207.42    4077  204.54    4085  203.17  4088.8   200.5
  5640.7     201  5660.9  204.66  5681.2  211.99  5691.3  213.32  5822.9   211.6
    5860  216.47  5927.5   216.9  5954.5  222.95  6005.1  224.43  6061.7  228.95
#Mann= 7 ,-1 , 0
  2669.7     .11       0  3294.1     .15       0  3412.5    .125       0
  3524.4     .15       0  3860.6     .11       0    4077    .015       0
  5660.9     .11       0
Bank Sta=4077,5660.9
XS Rating Curve= 0 ,0
Exp/Cntr=0.3,0.1

Type RM Length L Ch R = 1 ,3500    ,500,500,500
BEGIN DESCRIPTION:
MARTIN CREEK 7.0
END DESCRIPTION:
XS GIS Cut Line= 3
       3777968.3     10133478.77      3779407.71     10131774.62
      3779161.01     10130598.52
#Sta/Elev= 30
  2769.3  225.88  2987.8  217.95  3172.1  213.11  3234.4  212.73  3458.5  207.18
  3538.2   207.1  3552.3  206.95    3647   205.2    3725  207.14  3749.5  206.16
    3803  206.27  3831.6  204.19  3845.9  203.65  3852.7  202.44  3855.5   200.5
    5770     201  5790.4  204.15  5797.2  205.07  5804.4  204.71  5810.8  208.32
    5821  210.92  5984.5  214.42  5993.8   217.1  5998.9  216.17  6086.7  217.32
  6093.6  220.25  6098.7  218.37  6107.1  222.71  6117.3  224.08  6201.7  226.42
#Mann= 9 ,-1 , 0
  2769.3     .11       0  3234.4    .125       0  3458.5     .15       0
  3538.2    .125       0  3552.3     .15       0  3749.5     .11       0
  3831.6    .015       0  5790.4     .11       0  5797.2    .125       0
Bank Sta=3831.6,5790.4
XS Rating Curve= 0 ,0
Exp/Cntr=0.3,0.1

Type RM Length L Ch R = 1 ,3000    ,500,500,500
BEGIN DESCRIPTION:
MARTIN CREEK 6.0
END DESCRIPTION:
XS GIS Cut Line= 3
      3778197.51      10133707.9      3779844.17     10132018.56
      3779249.58     10130567.35
#Sta/Elev= 30
  2640.9  227.92    2745  226.61  2787.5  223.45  2815.8  224.44  2886.5  221.34
  2957.2  221.18  2971.4  219.11  3063.2  216.84  3126.8  217.51  3225.8  213.41
  3305.5  212.02  3371.8  209.72  3423.8  210.29  3466.3  207.53  3565.3  208.18
  3650.2  205.77  3784.5  206.12  3855.2  203.39  3915.6  204.48  3996.6  206.08
  4088.7  203.79  4116.8  202.91  4118.9   200.5  6067.2     201  6084.1  203.87
  6142.9   211.2  6214.9  211.24  6262.5  215.97  6380.6  222.68  6568.3  224.38
#Mann= 7 ,-1 , 0
  2640.9     .11       0  3305.5    .125       0  3371.8     .11       0
  3915.6    .125       0  4088.7    .015       0  6084.1     .11       0
  6262.5    .125       0
Bank Sta=4088.7,6084.1
XS Rating Curve= 0 ,0
Exp/Cntr=0.3,0.1

Type RM Length L Ch R = 1 ,2500    ,500,500,500
BEGIN DESCRIPTION:
MARTIN CREEK 5.0
END DESCRIPTION:
XS GIS Cut Line= 3
      3778489.27     10133682.02      3780280.63      10132262.5
      3781217.82     10131561.09
#Sta/Elev= 30
  2714.4  223.55  3009.3  216.78  3141.3  213.69  3170.2   214.5  3280.7  209.99
  3364.2  210.14  3422.8  208.84  3476.2  208.65    3590  204.88  3852.8  205.81
  3910.5  203.98  4058.7  204.33  4216.6   205.2  4258.2  203.94  4394.5   203.7
  4543.5  205.57  4549.9  204.16  4594.6   200.5  5713.2     201  5748.6  202.89
    5757  204.47  5777.8  210.49  5863.3  211.73  5892.4  215.74  5920.8  215.94
  6011.7  225.14  6048.7  227.39  6070.7  230.32  6087.8  230.18  6170.6  230.04
#Mann= 10 ,-1 , 0
  2714.4     .11       0  3009.3    .125       0  3280.7     .11       0
  3364.2    .125       0  3422.8     .11       0  4058.7    .125       0
  4549.9    .015       0    5757     .11       0  6011.7    .125       0
  6087.8     .11       0
#XS Ineff= 2 , 0
       0  4543.5  205.57               0
Permanent Ineff=
       F       F
Bank Sta=4549.9,5757
XS Rating Curve= 0 ,0
Exp/Cntr=0.3,0.1