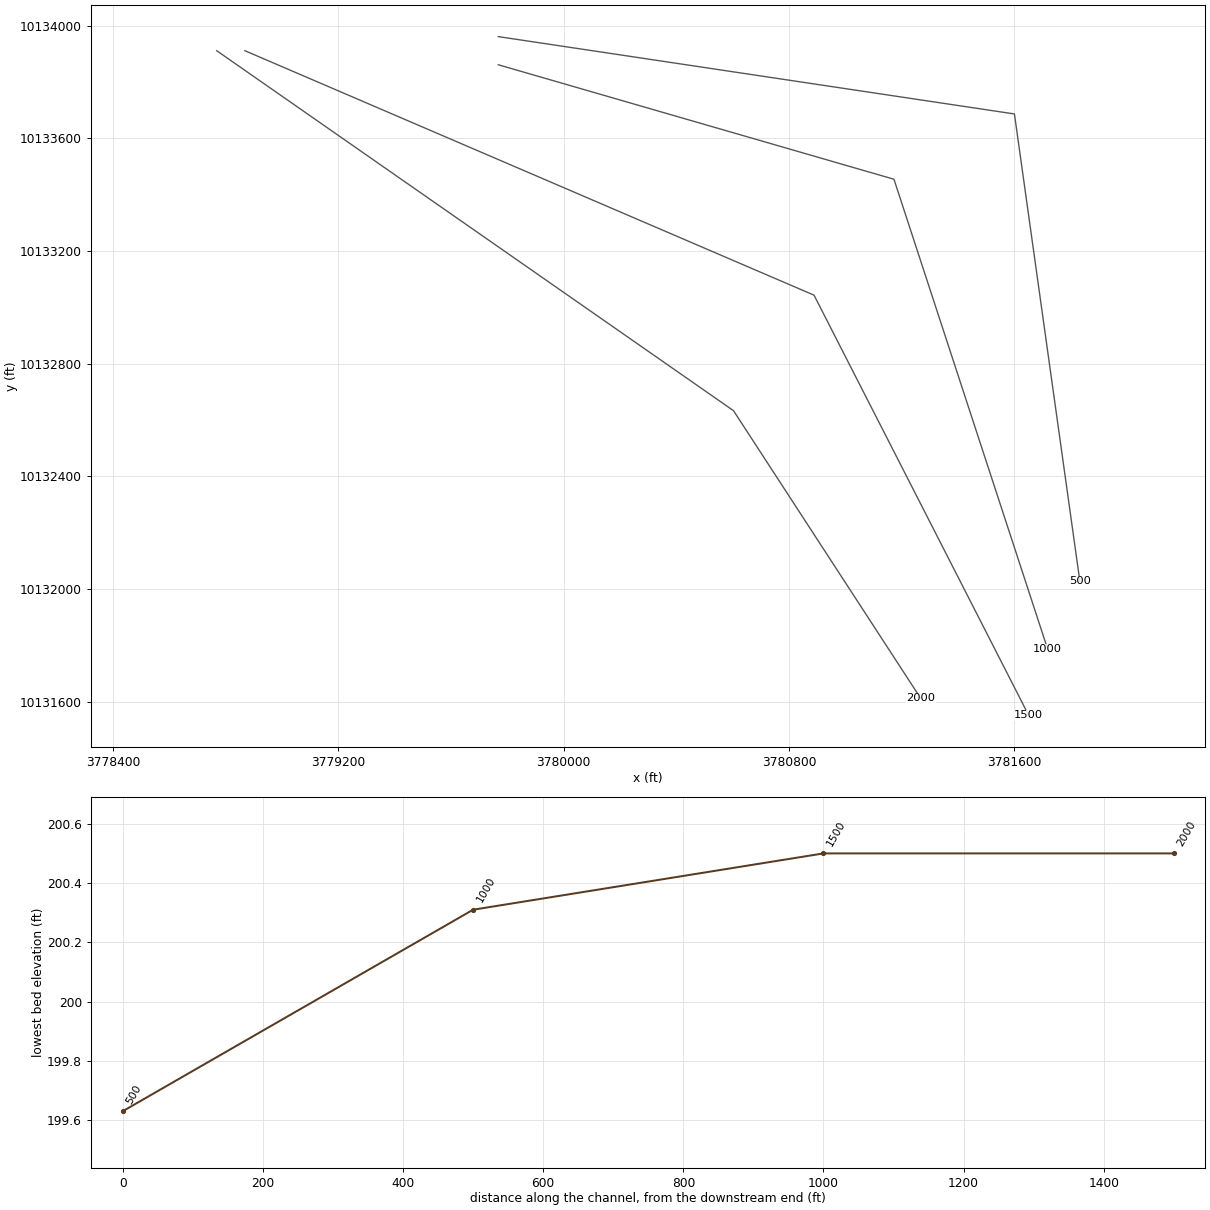
HEC-RAS study MARTIN CREEK.prj: MARTIN CREEK Base Level Engineering

--- MARTIN CREEK.g01 (geometry) --- (continued)

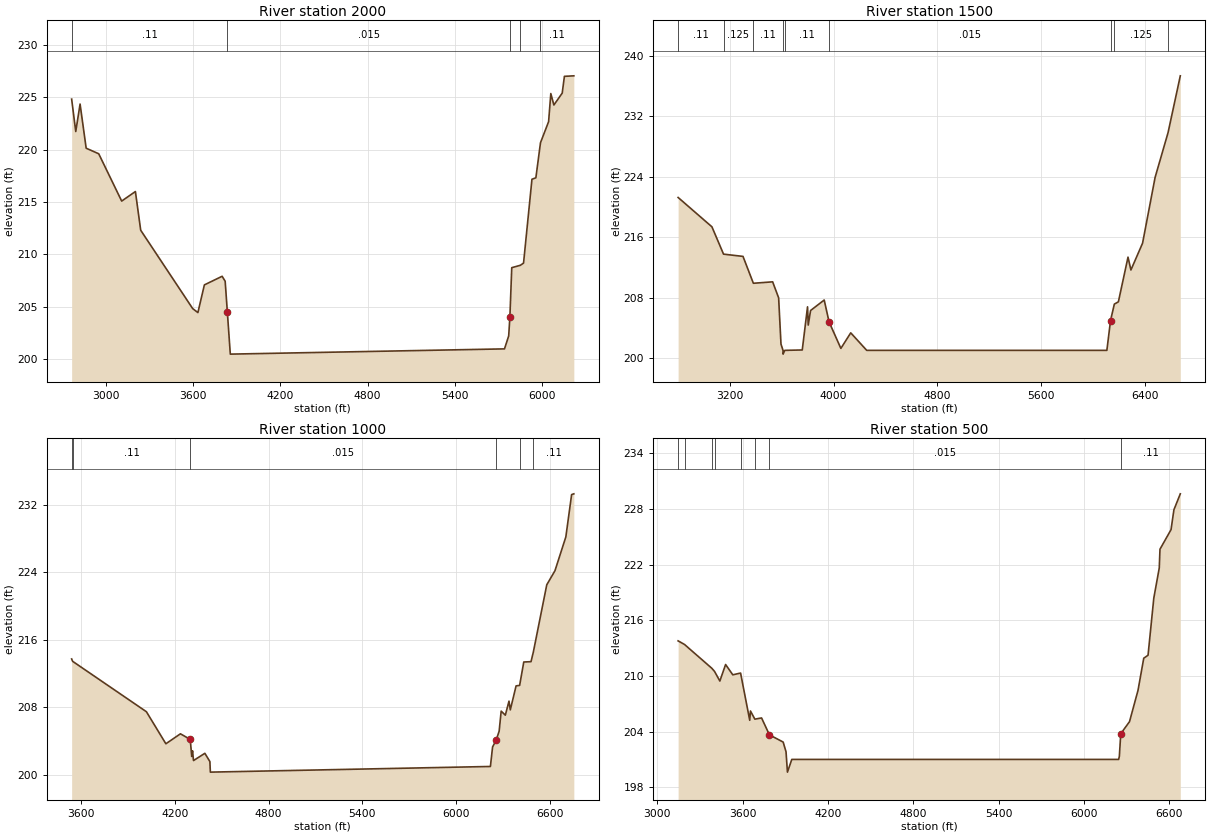
Type RM Length L Ch R = 1 ,2000    ,500,500,500
BEGIN DESCRIPTION:
MARTIN CREEK 4.0
END DESCRIPTION:
XS GIS Cut Line= 3
      3778767.88     10133911.05      3780602.97     10132632.81
      3781267.84     10131611.09
#Sta/Elev= 30
  2763.6  224.81  2791.9  221.72  2821.6  224.34  2863.5  220.13  2949.9   219.6
  3107.8  215.09  3202.3     216  3238.7  212.31  3596.5  204.84  3632.3  204.46
  3676.8   207.1    3799  207.92  3819.9  207.45  3834.7  204.56  3855.3   200.5
  5741.8     201  5770.7  202.23    5779 204.046  5791.8  208.74  5851.2  208.97
    5873  209.18  5930.8  217.17  5957.8  217.31  5989.5  220.65  6045.4  222.66
  6060.6  225.34  6081.7  224.25    6139  225.38  6154.1  226.98    6219  227.03
#Mann= 5 ,-1 , 0
  2763.6     .11       0  3834.7    .015       0    5779     .11       0
  5851.2    .125       0  5989.5     .11       0
Bank Sta=3834.7,5779
XS Rating Curve= 0 ,0
Exp/Cntr=0.3,0.1

Type RM Length L Ch R = 1 ,1500    ,500,500,500
BEGIN DESCRIPTION:
MARTIN CREEK 3.0
END DESCRIPTION:
XS GIS Cut Line= 3
      3778867.85     10133911.07       3780888.9     10133042.99
      3781650.74     10131551.83
#Sta/Elev= 30
  2800.4  221.26  3061.3  217.37  3150.8  213.75    3301  213.45  3380.9  209.89
  3529.6  210.08  3575.9  207.96    3594  201.83  3609.7     201  3610.2   200.5
  3623.6     201  3758.1  201.05  3798.8  206.77  3804.2  204.35  3822.3  206.28
  3927.4  207.67  3964.9  204.77    4056  201.26  4132.1  203.32  4255.4     201
    6108     201  6136.3  204.95  6165.6  207.13  6196.8  207.43  6271.1  213.35
  6293.5  211.65  6383.4   215.2  6480.1  223.92    6580  229.85  6674.5  237.38
#Mann= 9 ,-1 , 0
  2800.4     .11       0  3150.8    .125       0  3380.9     .11       0
  3609.7     .08       0  3623.6     .11       0  3964.9    .015       0
  6136.3     .11       0  6165.6    .125       0    6580     .11       0
#XS Ineff= 2 , 0
       0  3927.4  207.67               0
Permanent Ineff=
       T       F
Bank Sta=3964.9,6136.3
XS Rating Curve= 0 ,0
Exp/Cntr=0.3,0.1

Type RM Length L Ch R = 1 ,1000    ,500,500,500
BEGIN DESCRIPTION:
MARTIN CREEK 2.0
END DESCRIPTION:
XS GIS Cut Line= 3
      3779767.85     10133861.07      3781172.73     10133454.62
      3781718.46      10131786.2
#Sta/Elev= 30
  3537.5  213.72  3543.9  213.44  4016.4  207.47  4141.3  203.67  4234.5  204.85
  4297.4  204.19  4306.9  202.17  4312.1  202.84  4318.3  201.68  4391.1  202.54
  4423.3  201.56  4426.3  200.31  6220.8  200.98  6234.7  203.29    6258  204.12
  6276.8  205.16  6289.8  207.54  6316.4  207.06  6339.9  208.72  6348.3  207.69
  6385.4  210.53  6408.1  210.59  6434.6  213.36    6481   213.4  6495.9  214.54
  6581.9  222.51  6634.5  224.18  6704.1  228.18  6741.2   233.2  6755.4  233.29
#Mann= 6 ,-1 , 0
  3537.5    .125       0  3543.9     .11       0  4297.4    .015       0
    6258     .11       0  6408.1    .125       0  6495.9     .11       0
Bank Sta=4297.4,6258
XS Rating Curve= 0 ,0
Exp/Cntr=0.3,0.1

Type RM Length L Ch R = 1 ,500     ,0,0,0
BEGIN DESCRIPTION:
MARTIN CREEK 1.0
END DESCRIPTION:
XS GIS Cut Line= 3
      3779767.81     10133961.08      3781600.54     10133686.42
      3781832.93     10132026.61
#Sta/Elev= 30
  3146.8  213.78  3191.9  213.39  3383.3  210.83  3402.7  210.49  3440.1  209.45
  3480.5  211.23  3531.1  210.12  3585.8  210.31  3650.1  205.22  3655.2  206.22
  3686.2  205.34  3733.3  205.47  3788.4  203.65    3885  202.87  3905.2  201.82
  3915.1  199.63  3945.7     201  6242.5     201  6247.6  201.32  6257.5  203.77
    6319  205.07  6378.7  208.44  6419.1  211.91  6449.3  212.23  6489.7  218.38
  6528.1  221.64  6533.2  223.66  6610.9  225.77  6631.1  227.91    6676  229.63
#Mann= 8 ,-1 , 0
  3146.8    .125       0  3191.9     .11       0  3383.3     .15       0
  3402.7     .11       0  3585.8     .15       0  3686.2     .17       0
  3788.4    .015       0  6257.5     .11       0
Bank Sta=3788.4,6257.5
XS Rating Curve= 0 ,0
Exp/Cntr=0.3,0.1

Chan Stop Cuts=-1
Use User Specified Reach Order=0
Composite Channel Slope=5