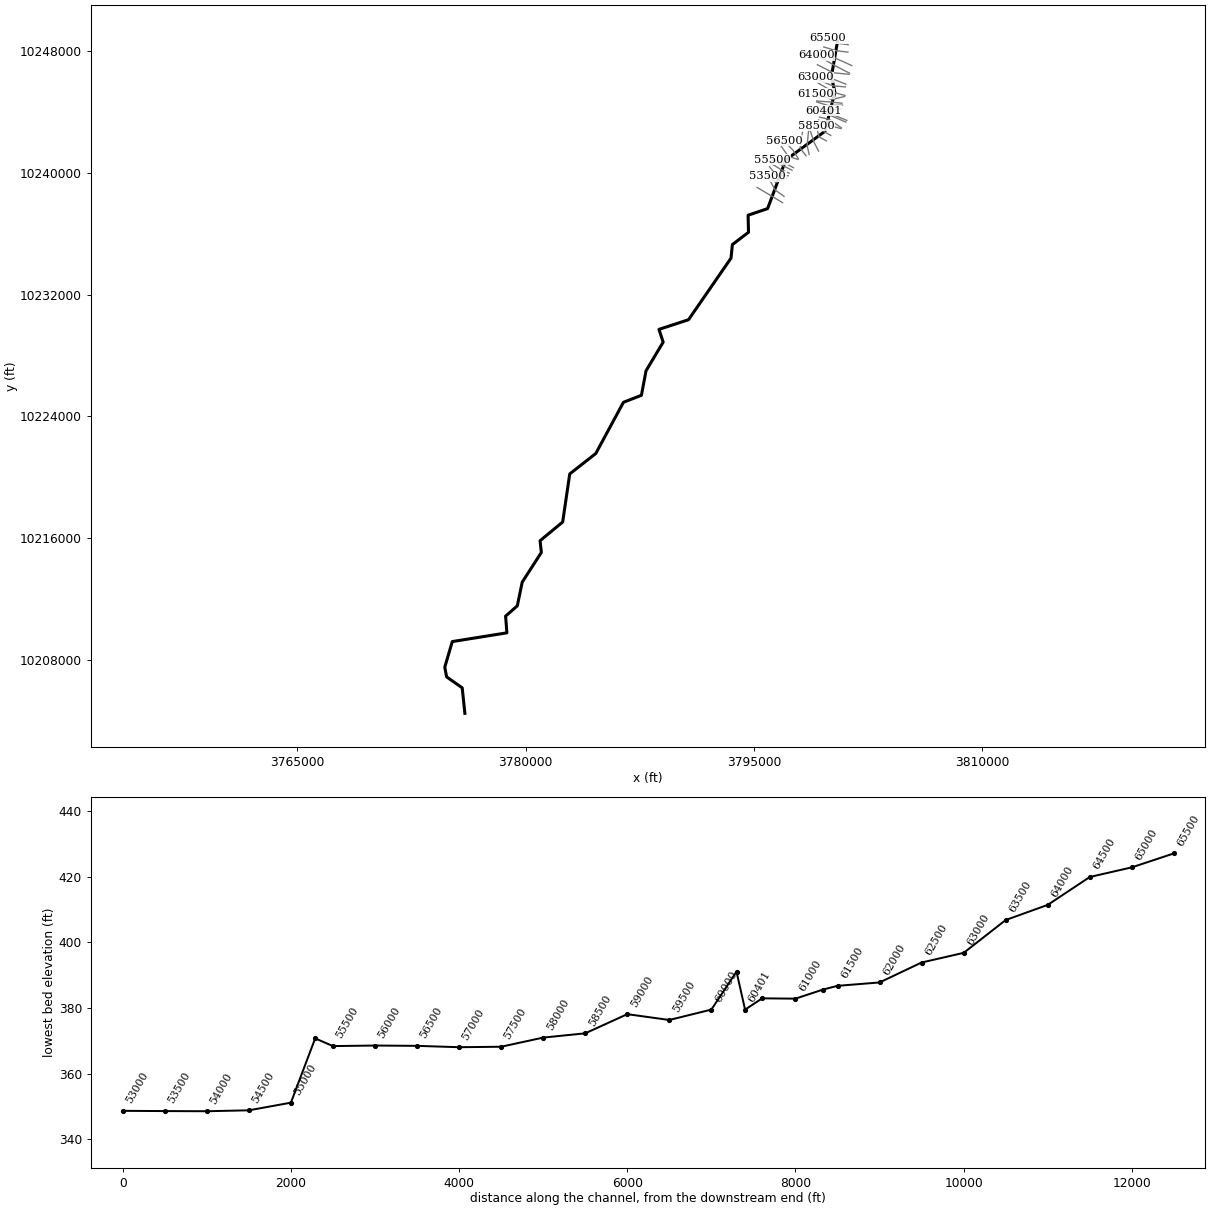
--- MCDONALD CREEK.prj (project) ---

Proj Title=MCDONALD CREEK Base Level Engineering
Current Plan=p01
Default Exp/Contr=0.3,0.1
English Units
Geom File=g01
Flow File=f01
Plan File=p01
Y Axis Title=Elevation
X Axis Title(PF)=Main Channel Distance
X Axis Title(XS)=Station
BEGIN DESCRIPTION:
MCDONALD CREEK
END DESCRIPTION:
DSS Export Rating Curves= 0
DSS Export Rating Curve Sorted= 0
DSS Export Volume Flow Curves= 0
DXF OffsetX= 0
DXF OffsetY= 0
DXF ScaleX= 1
DXF ScaleY= 10

--- MCDONALD CREEK.p01 (plan) ---

Plan Title=Multiple Run
Short Identifier=Multiple
Geom File=g01
Flow File=f01
Subcritical Flow
K Sum by GR= 0
Std Step Tol= 0.01
Critical Tol= 0.01
Num of Std Step Trials= 20
Max Error Tol= 0.3
Flow Tol Ratio= 0.001
Split Flow NTrial= 30
Split Flow Tol= 0.02
Split Flow Ratio= 0.02
Log Output Level= 0
Friction Slope Method= 1
Unsteady Friction Slope Method= 2
Unsteady Bridges Friction Slope Method= 1
Parabolic Critical Depth
Global Vel Dist=  1 , 1 , 1
Global Log Level= 0
CheckData=True
Encroach Param= -1, 0, 0, 0
BEGIN DESCRIPTION:
Multiple Run
END DESCRIPTION:

--- MCDONALD CREEK.f01 (steady flow) ---

Flow Title=Multiple
Program Version=4.10
Number of Profiles= 7
Profile Names=10-year,25-year,50-year,1pct_min,100-year,1pct_plu,500-year
River Rch & RM=MCDONALD CREEK,Reach-1         ,65500
     298     384     503     217     655    1978    1151
River Rch & RM=MCDONALD CREEK,Reach-1         ,64500
     834    1145    1564     703    2122    6408    4033
River Rch & RM=MCDONALD CREEK,Reach-1         ,56500
    1314    1848    2563    1167    3524   10642    6894
River Rch & RM=MCDONALD CREEK,Reach-1         ,52500
    1693    2406    3359    1538    4645   14028    9192
River Rch & RM=MCDONALD CREEK,Reach-1         ,46500
    1994    2848    3989    1832    5532   16706   11006
River Rch & RM=MCDONALD CREEK,Reach-1         ,41871
    2247    3219    4518    2077    6273   18944   12511
River Rch & RM=MCDONALD CREEK,Reach-1         ,39096
    2485    3579    5040    2325    7021   21203   14099
River Rch & RM=MCDONALD CREEK,Reach-1         ,32702
    2653    3835    5413    2501    7554   22813   15229
River Rch & RM=MCDONALD CREEK,Reach-1         ,29211
    2794    4034    5690    2626    7930   23948   15946
River Rch & RM=MCDONALD CREEK,Reach-1         ,23234
    3060    4435    6271    2901    8761   26458   17697
River Rch & RM=MCDONALD CREEK,Reach-1         ,17283
    3213    4661    6595    3052    9218   27838   18643
River Rch & RM=MCDONALD CREEK,Reach-1         ,13791
    3189    4599    6481    2986    9018   27234   18075
River Rch & RM=MCDONALD CREEK,Reach-1         ,8242
    3346    4832    6815    3142    9490   28659   19046
Boundary for River Rch & Prof#=MCDONALD CREEK,Reach-1         , 1
Up Type= 0
Dn Type= 3
Dn Slope=0.005
Boundary for River Rch & Prof#=MCDONALD CREEK,Reach-1         , 2
Up Type= 0
Dn Type= 3
Dn Slope=0.005
Boundary for River Rch & Prof#=MCDONALD CREEK,Reach-1         , 3
Up Type= 0
Dn Type= 3
Dn Slope=0.005
Boundary for River Rch & Prof#=MCDONALD CREEK,Reach-1         , 4
Up Type= 0
Dn Type= 3
Dn Slope=0.005
Boundary for River Rch & Prof#=MCDONALD CREEK,Reach-1         , 5
Up Type= 0
Dn Type= 3
Dn Slope=0.005
Boundary for River Rch & Prof#=MCDONALD CREEK,Reach-1         , 6
Up Type= 0
Dn Type= 3
Dn Slope=0.005
Boundary for River Rch & Prof#=MCDONALD CREEK,Reach-1         , 7
Up Type= 0
Dn Type= 3
Dn Slope=0.005
DSS Import GetInterval= 0
DSS Import GetPeak= 0
DSS Import FillOption= 0

--- MCDONALD CREEK.g01 (geometry) ---

Geom Title=Existing Conditions
Program Version=4.10

River Reach=MCDONALD CREEK  ,Reach-1
Reach XY= 30
      3800492.73     10248678.48      3800085.71     10246334.59
      3800313.57     10245312.45      3799661.23     10242736.93
      3797089.65     10240854.38       3795896.8     10237656.94
      3794615.32     10237222.68      3794642.49     10236102.14
      3793582.65     10235290.96      3793494.69     10234404.69
      3790701.91      10230353.7      3788761.84     10229719.23
      3789037.02     10228880.26       3787911.1      10226997.6
      3787609.08     10225386.82      3786427.25     10224925.83
      3784612.46     10221561.33       3782900.9     10220217.69
      3782436.34     10217057.44      3780951.03      10215827.6
      3781036.91     10215058.58      3779780.53     10213106.96
        3779456.     10211546.77      3778687.98     10210869.83
      3778773.92     10209773.74      3775187.14     10209198.51
      3774693.91     10207519.91      3774814.57     10206877.55
      3775837.93     10206158.44       3776013.8     10204479.56

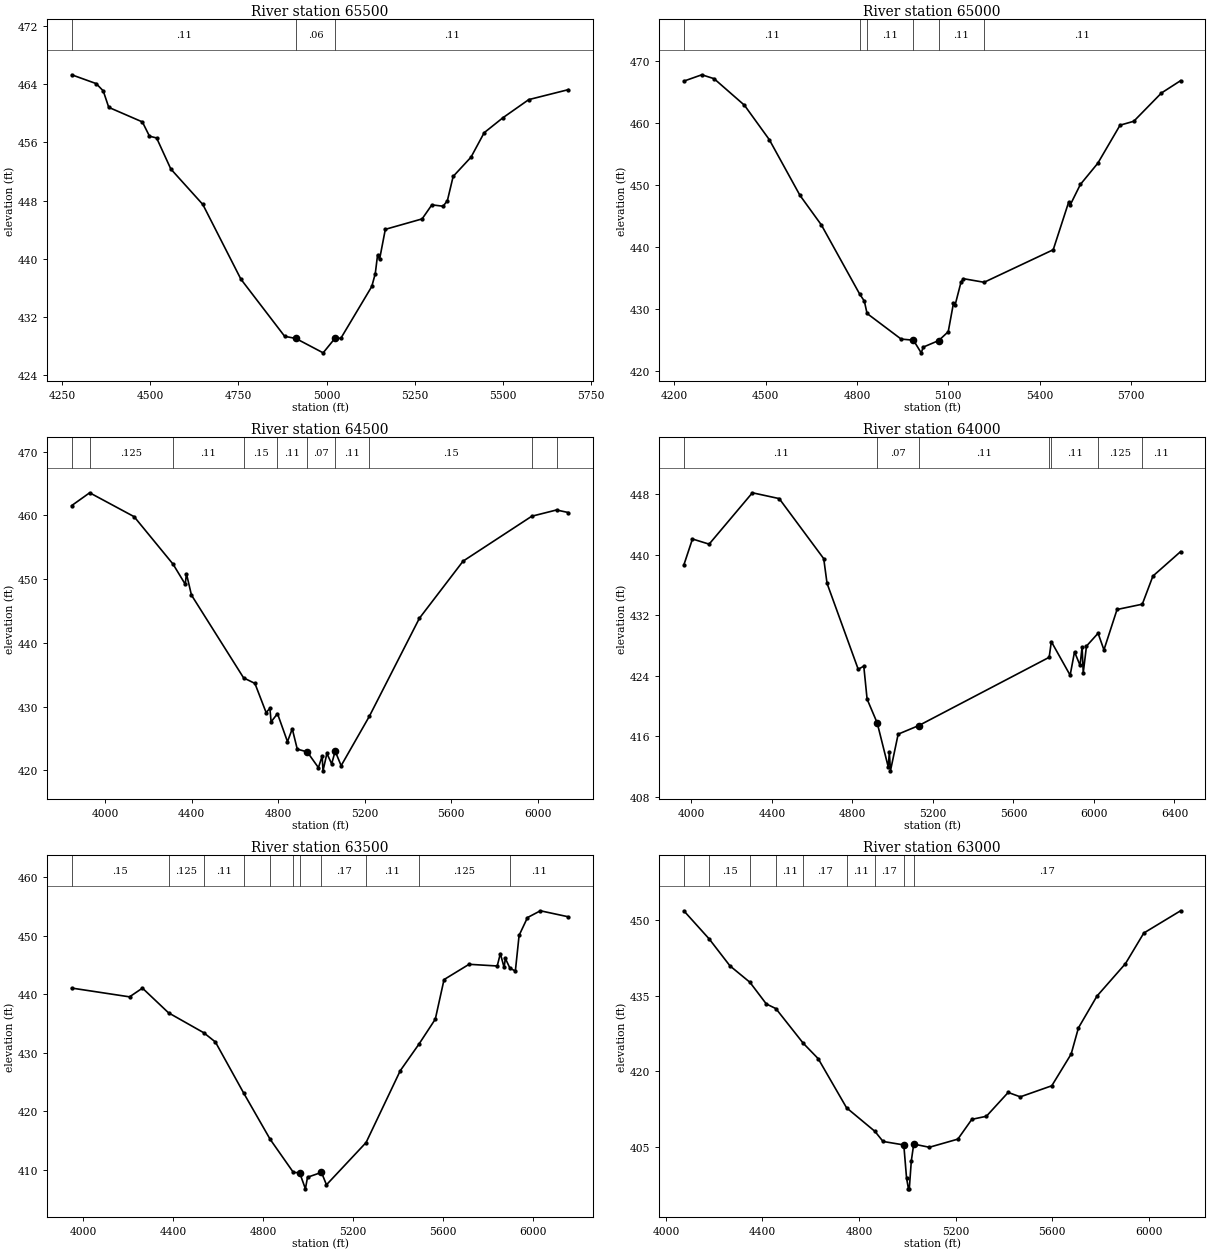
Type RM Length L Ch R = 1 ,65500   ,500,500,500
BEGIN DESCRIPTION:
MCDONALD CREEK 129.0
END DESCRIPTION:
XS GIS Cut Line= 3
       3801186.6     10248432.06      3800470.01     10248528.07
      3799863.68     10248848.73
#Sta/Elev= 30
    4277  465.26  4346.4  464.05  4366.5  463.05  4382.1  460.79  4477.5  458.79
  4497.7  456.83  4517.9  456.59  4558.2  452.33    4649  447.46    4757  437.21
  4881.1  429.37    4913  429.07  4990.3   427.1  5025.1  429.17  5040.3  429.08
  5128.3  436.21  5138.2  437.98  5144.7  440.53  5150.3  439.92  5166.7  444.05
    5271  445.48  5298.7  447.41  5330.5  447.22  5342.7  447.98  5359.1  451.31
  5409.7  453.95  5447.1  457.31  5500.2  459.36  5573.5  461.85  5685.9  463.22
#Mann= 3 , 0 , 0
    4277     .11       0    4913     .06       0  5025.1     .11       0
Bank Sta=4913,5025.1
XS Rating Curve= 0 ,0
Exp/Cntr=0.3,0.1

Type RM Length L Ch R = 1 ,65000   ,500,500,500
BEGIN DESCRIPTION:
MCDONALD CREEK 128.0
END DESCRIPTION:
XS GIS Cut Line= 3
      3801176.22     10247942.47      3800413.54     10248031.87
       3799587.6     10248281.03
#Sta/Elev= 30
  4232.1  466.68  4290.9   467.7  4331.1  467.07  4430.8  462.79  4512.4  457.24
  4613.1  448.25  4683.5  443.47  4808.9  432.35  4824.5  431.19  4833.4   429.2
  4945.2  425.07  4985.6  424.89  5011.1  422.85  5018.1  423.78  5068.6  424.83
  5099.9  426.26    5117  430.84  5122.2  430.51  5141.7  434.23    5150  434.81
  5217.7  434.23  5444.6  439.48  5495.5  447.19  5500.7  446.74  5533.7  450.01
  5590.9  453.43    5664  459.57    5709   460.2  5799.8  464.76  5862.7  466.75
#Mann= 6 ,-1 , 0
  4232.1     .11       0  4808.9    .125       0  4833.4     .11       0
  4985.6     .06       0  5068.6     .11       0  5217.7     .11       0
Bank Sta=4985.6,5068.6
XS Rating Curve= 0 ,0
Exp/Cntr=0.3,0.1

Type RM Length L Ch R = 1 ,64500   ,500,500,500
BEGIN DESCRIPTION:
MCDONALD CREEK 127.0
END DESCRIPTION:
XS GIS Cut Line= 3
      3801426.17     10247057.06       3800375.2     10247533.94
      3799368.84     10248072.71
#Sta/Elev= 30
  3845.9  461.54  3929.1  463.55  4134.5   459.8  4314.6  452.34  4370.8  449.19
  4376.3  450.85  4399.4   447.5  4640.5   434.5  4692.8  433.63  4744.5  429.06
  4762.1  429.72  4767.6  427.59  4797.1  428.89  4843.3  424.49  4865.4   426.5
  4888.5  423.32  4934.6  422.88  4986.3  420.41  5003.6  422.23  5007.5  419.91
  5025.5  422.64  5047.5     421  5063.7     423  5091.3  420.72  5221.2  428.44
  5452.9  443.85  5654.9  452.82  5972.4  459.87  6086.7  460.85  6141.5  460.45
#Mann= 10 ,-1 , 0
  3845.9     .11       0  3929.1    .125       0  4314.6     .11       0
  4640.5     .15       0  4797.1     .11       0  4934.6     .07       0
  5063.7     .11       0  5221.2     .15       0  5972.4    .125       0
  6086.7     .11       0
Bank Sta=4934.6,5063.7
XS Rating Curve= 0 ,0
Exp/Cntr=0.3,0.1

Type RM Length L Ch R = 1 ,64000   ,500,500,500
BEGIN DESCRIPTION:
MCDONALD CREEK 126.0
END DESCRIPTION:
XS GIS Cut Line= 3
      3801279.73       10246556.      3800359.76     10247034.36
      3799111.24     10247732.18
#Sta/Elev= 30
  3963.1  438.65  4005.6  442.06  4088.4  441.38  4303.3  448.17  4436.5   447.4
  4657.6  439.46  4674.1   436.2  4828.9  424.84  4856.6  425.25  4873.1  420.89
  4923.3  417.74    4978  411.93  4983.6  413.87  4989.1  411.41  5027.4  416.26
  5130.2   417.4  5777.5  426.42  5788.3  428.49  5881.7  424.05  5903.4  427.14
  5930.9  425.36  5941.1  427.78  5946.8  424.37  5962.8   427.9  6020.5   429.6
  6049.6   427.4  6114.7  432.74  6240.1  433.44  6292.9  437.16  6430.3  440.39
#Mann= 7 ,-1 , 0
  3963.1     .11       0  4923.3     .07       0  5130.2     .11       0
  5777.5    .125       0  5788.3     .11       0  6020.5    .125       0
  6240.1     .11       0
Bank Sta=4923.3,5130.2
XS Rating Curve= 0 ,0
Exp/Cntr=0.3,0.1

Type RM Length L Ch R = 1 ,63500   ,500,500,500
BEGIN DESCRIPTION:
MCDONALD CREEK 125.0
END DESCRIPTION:
XS GIS Cut Line= 3
      3801243.85     10246484.15       3800197.7     10246590.09
      3799165.74     10247114.36
#Sta/Elev= 30
  3948.5  441.08  4205.8  439.58  4263.2  441.07  4379.3  436.85  4535.9  433.45
  4587.7  431.87  4714.3  423.09  4831.4  415.24  4934.4   409.6  4962.4  409.53
    4988  406.79  4997.4  408.77  5059.4   409.6  5081.7  407.48  5257.9   414.7
  5409.9  426.97  5492.7  431.49  5565.7  435.77  5604.6  442.53  5715.9  445.14
  5841.1  444.85    5855  446.96  5871.7  444.61  5877.3  446.14  5897.8  444.47
  5921.8  443.99  5938.4  450.08  5975.7  453.12  6033.1  454.28  6157.5  453.25
#Mann= 11 ,-1 , 0
  3948.5     .15       0  4379.3    .125       0  4535.9     .11       0
  4714.3     .17       0  4831.4     .11       0  4934.4     .15       0
  4962.4     .09       0  5059.4     .17       0  5257.9     .11       0
  5492.7    .125       0  5897.8     .11       0
Bank Sta=4962.4,5059.4
XS Rating Curve= 0 ,0
Exp/Cntr=0.3,0.1

Type RM Length L Ch R = 1 ,63000   ,500,500,500
BEGIN DESCRIPTION:
MCDONALD CREEK 124.0
END DESCRIPTION:
XS GIS Cut Line= 3
      3801035.52     10245838.32      3800174.49     10246178.26
        3799046.     10246275.81
#Sta/Elev= 30
  4074.3  451.74  4179.1  446.19  4265.3  440.86  4347.7  437.63  4415.8  433.34
  4455.4  432.42    4569  425.56  4630.8  422.52  4748.5   412.8    4866  408.14
  4899.6  406.15  4985.6  405.46    4997  398.93  5004.9  396.78  5008.4  396.78
  5016.7  402.28  5026.7  405.63  5091.4     405  5209.6  406.61  5267.6  410.52
  5327.9  411.13  5418.2  415.84  5468.4  414.97  5598.9  417.16  5679.2  423.43
  5709.3   428.6    5786  434.88  5904.3  441.31  5980.3  447.36  6132.7  451.76
#Mann= 9 ,-1 , 0
  4074.3    .125       0  4179.1     .15       0  4347.7    .125       0
  4455.4     .11       0    4569     .17       0  4748.5     .11       0
    4866     .17       0  4985.6     .07       0  5026.7     .17       0
Bank Sta=4985.6,5026.7
XS Rating Curve= 0 ,0
Exp/Cntr=0.3,0.1

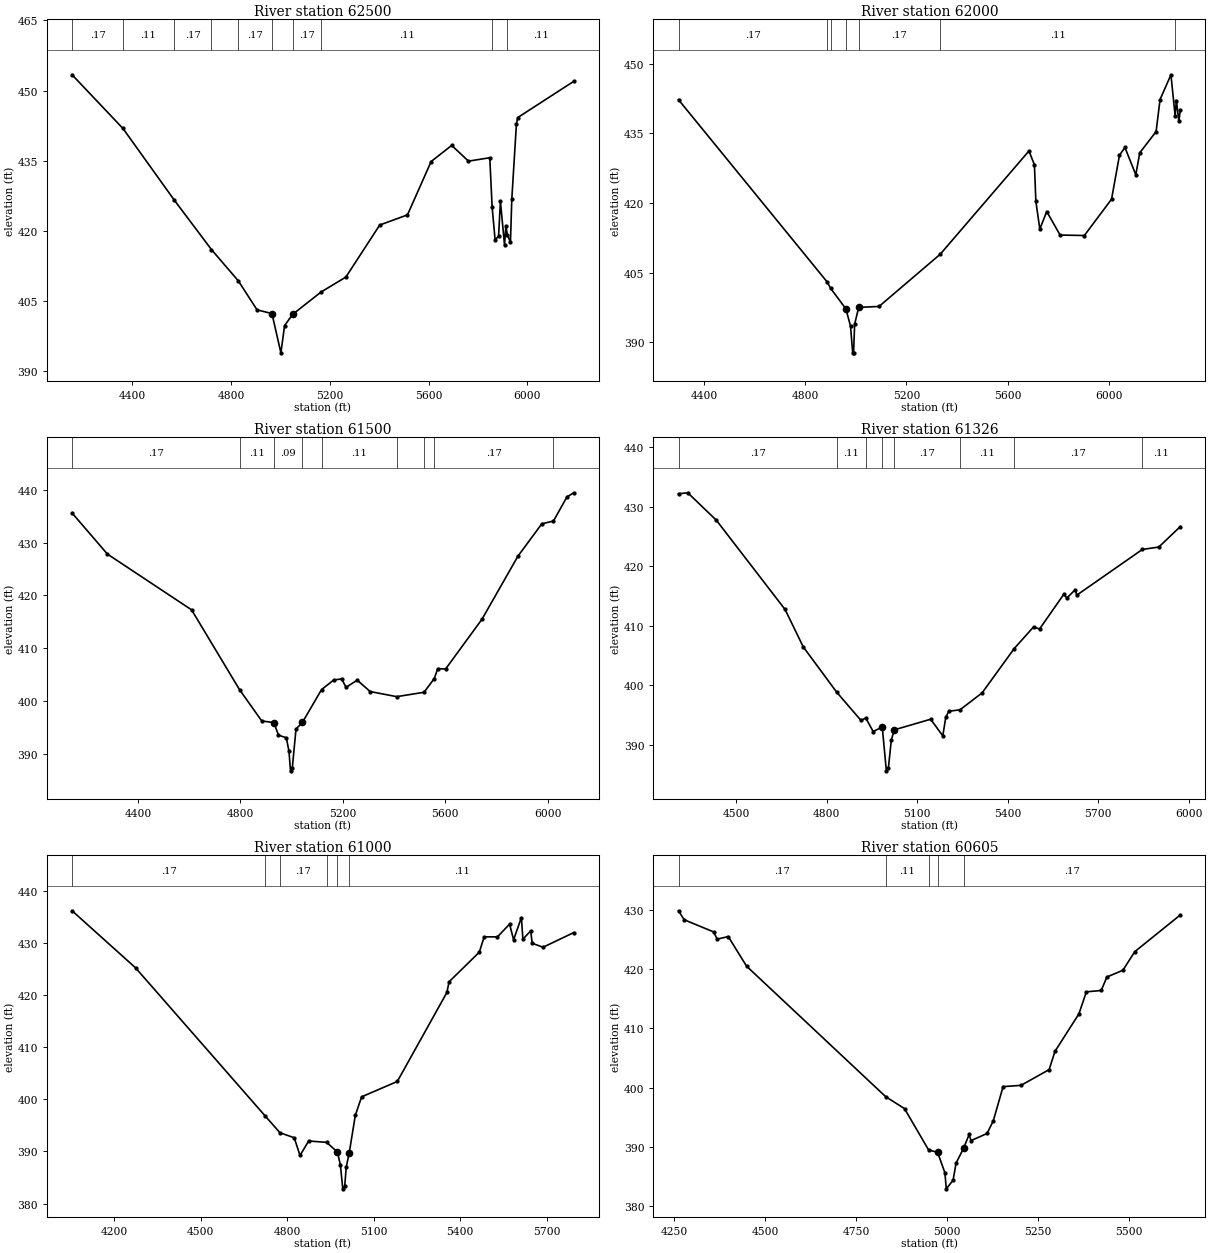
Type RM Length L Ch R = 1 ,62500   ,500,500,500
BEGIN DESCRIPTION:
MCDONALD CREEK 123.0
END DESCRIPTION:
XS GIS Cut Line= 3
      3801004.28     10245656.02      3800163.26     10245733.72
      3799062.25     10246181.79
#Sta/Elev= 30
  4155.4  453.37  4361.7  441.87  4568.3  426.63  4720.3  415.94  4828.8  409.27
    4905  403.04  4965.3  402.25  5001.6  393.84  5016.6  399.68    5049  402.07
  5163.8  406.84    5265  410.07    5402   421.2  5514.5  423.38  5610.4   434.8
  5693.7  438.25  5761.6  434.88    5848  435.61  5857.6  424.99  5869.6     418
  5883.7  418.85  5891.1  426.26  5907.8  416.91  5913.2  421.01  5919.5  419.08
  5931.8   417.5  5937.2  426.72  5955.9  442.79  5961.3  444.21  6188.7  451.98
#Mann= 10 ,-1 , 0
  4155.4     .17       0  4361.7     .11       0  4568.3     .17       0
  4720.3     .11       0  4828.8     .17       0  4965.3     .09       0
    5049     .17       0  5163.8     .11       0  5857.6     .17       0
  5919.5     .11       0
Bank Sta=4965.3,5049
XS Rating Curve= 0 ,0
Exp/Cntr=0.3,0.1

Type RM Length L Ch R = 1 ,62000   ,500,500,500
BEGIN DESCRIPTION:
MCDONALD CREEK 122.0
END DESCRIPTION:
XS GIS Cut Line= 3
      3800973.05     10245093.52      3800297.65     10245277.08
      3799193.02     10245926.13
#Sta/Elev= 30
  4300.1  442.21  4886.6  403.03  4900.9  401.61  4960.8  397.23  4979.1   393.5
  4987.7  387.76  4991.2  387.76  4995.4  393.94  5011.4  397.54  5091.7  397.74
  5333.4  408.98  5683.6  431.19  5705.1  428.23  5710.9  420.33  5726.5  414.39
  5753.8  418.16  5806.6   413.1  5902.3     413  6009.7  420.82    6041  430.28
  6062.5  431.94  6105.4  426.07  6121.1   430.8  6185.5  435.35  6201.2  442.26
  6244.1  447.58  6260.7  438.77  6265.6  442.04  6275.4  437.55  6281.2  440.08
#Mann= 7 ,-1 , 0
  4300.1     .17       0  4886.6     .11       0  4900.9     .17       0
  4960.8     .09       0  5011.4     .17       0  5333.4     .11       0
  6260.7     .17       0
Bank Sta=4960.8,5011.4
XS Rating Curve= 0 ,0
Exp/Cntr=0.3,0.1

Type RM Length L Ch R = 1 ,61500   ,174,174,174
BEGIN DESCRIPTION:
MCDONALD CREEK 121.0
END DESCRIPTION:
XS GIS Cut Line= 3
      3800952.23     10245025.81      3800117.64     10244829.81
      3799082.68     10245208.01
#Sta/Elev= 30
  4142.7   435.6  4280.7  427.81  4609.4  417.24  4796.5  402.12  4883.4  396.18
  4930.9  395.87  4948.4   393.5  4979.2  392.99  4989.5  390.47  4995.6  386.73
  5002.5  387.23    5017  394.65  5042.2  395.92  5116.8  402.13  5164.4  403.95
  5194.9  404.15  5212.7  402.56    5256  403.92  5306.4  401.76  5410.3  400.79
  5516.9  401.62  5556.9  404.22  5570.6   406.1  5601.1  406.03  5743.2  415.47
  5883.5  427.41  5976.8  433.55  6022.2  434.07  6075.1  438.66  6101.9  439.43
#Mann= 9 ,-1 , 0
  4142.7     .17       0  4796.5     .11       0  4930.9     .09       0
  5042.2     .17       0  5116.8     .11       0  5410.3     .17       0
  5516.9     .11       0  5556.9     .17       0  6022.2     .11       0
Bank Sta=4930.9,5042.2
XS Rating Curve= 0 ,0
Exp/Cntr=0.3,0.1

Type RM Length L Ch R = 1 ,61326   ,326,326,326
BEGIN DESCRIPTION:
Mapping XS 09a701aa
END DESCRIPTION:
XS GIS Cut Line= 3
       3800778.7     10244582.09      3800092.22     10244660.11
      3799122.63     10244731.38
#Sta/Elev= 30
  4309.1  432.19  4339.7  432.35  4434.3  427.74  4662.2  412.72  4722.6  406.42
  4833.3  398.81  4913.8  394.06  4929.7  394.47  4954.1  392.19  4984.3  392.95
  4997.9  385.58  5004.7  386.08  5014.4   390.8  5024.4  392.48  5144.8  394.26
  5184.9  391.46  5194.9   394.6  5204.9   395.6  5242.1  395.85  5315.2  398.69
  5421.5  406.14  5485.6  409.78  5505.7  409.44  5585.9  415.27    5596  414.64
    5624  416.05    5629  415.13  5846.4  422.82  5900.8  423.22  5972.2  426.67
#Mann= 8 ,-1 , 0
  4309.1     .17       0  4833.3     .11       0  4929.7     .17       0
  4984.3     .09       0  5024.4     .17       0  5242.1     .11       0
  5421.5     .17       0  5846.4     .11       0
Bank Sta=4984.3,5024.4
XS Rating Curve= 0 ,0
Exp/Cntr=0.3,0.1

Type RM Length L Ch R = 1 ,61000   ,395,395,395
BEGIN DESCRIPTION:
MCDONALD CREEK 120.0
END DESCRIPTION:
XS GIS Cut Line= 3
      3800817.87     10244461.07      3799872.89     10244429.69
      3799115.32     10244669.76
#Sta/Elev= 30
  4054.5  436.26  4274.6   425.3  4725.2  396.76  4775.5   393.6  4824.9  392.64
    4845  389.23    4875  392.02  4937.2  391.75    4975  389.88    4985  387.39
  4993.3  382.82    5000  383.32  5005.3     387  5015.8  389.78  5036.8  396.94
  5058.6   400.5  5182.5  403.46  5354.4  420.56  5361.9  422.61  5466.9  428.31
  5483.6  431.25  5529.8  431.25  5571.8   433.7  5585.7  430.68  5612.7  434.96
    5618   430.8    5645   432.4  5650.2  430.02  5687.8  429.25  5794.7  432.08
#Mann= 6 ,-1 , 0
  4054.5     .17       0  4725.2     .11       0  4775.5     .17       0
  4937.2     .11       0    4975     .06       0  5015.8     .11       0
Bank Sta=4975,5015.8
XS Rating Curve= 0 ,0
Exp/Cntr=0.3,0.1

Type RM Length L Ch R = 1 ,60605   ,204,204,204
BEGIN DESCRIPTION:
Mapping XS 92eee6e3
END DESCRIPTION:
XS GIS Cut Line= 3
      3800723.14     10244214.03      3799991.96     10244113.24
      3799365.45     10244248.76
#Sta/Elev= 30
  4261.9  429.85  4277.3  428.34  4358.1  426.29  4368.2  425.06  4398.5   425.5
  4448.9   420.5  4831.3  398.47    4883  396.46  4949.3  389.47  4973.9  389.09
    4994  385.62  4997.8  382.92  5016.5  384.38  5024.7  387.27  5045.1  389.74
  5060.6   392.1  5065.7  391.06  5109.8  392.26    5127  394.41  5153.9  400.17
  5203.2  400.39  5280.4  403.04  5296.5  406.13  5362.3  412.45  5382.8  416.17
  5423.7   416.4  5439.1  418.67  5483.2  419.81  5515.8  422.95    5641  429.15
#Mann= 5 ,-1 , 0
  4261.9     .17       0  4831.3     .11       0  4949.3     .17       0
  4973.9     .09       0  5045.1     .17       0
Bank Sta=4973.9,5045.1
XS Rating Curve= 0 ,0
Exp/Cntr=0.3,0.1

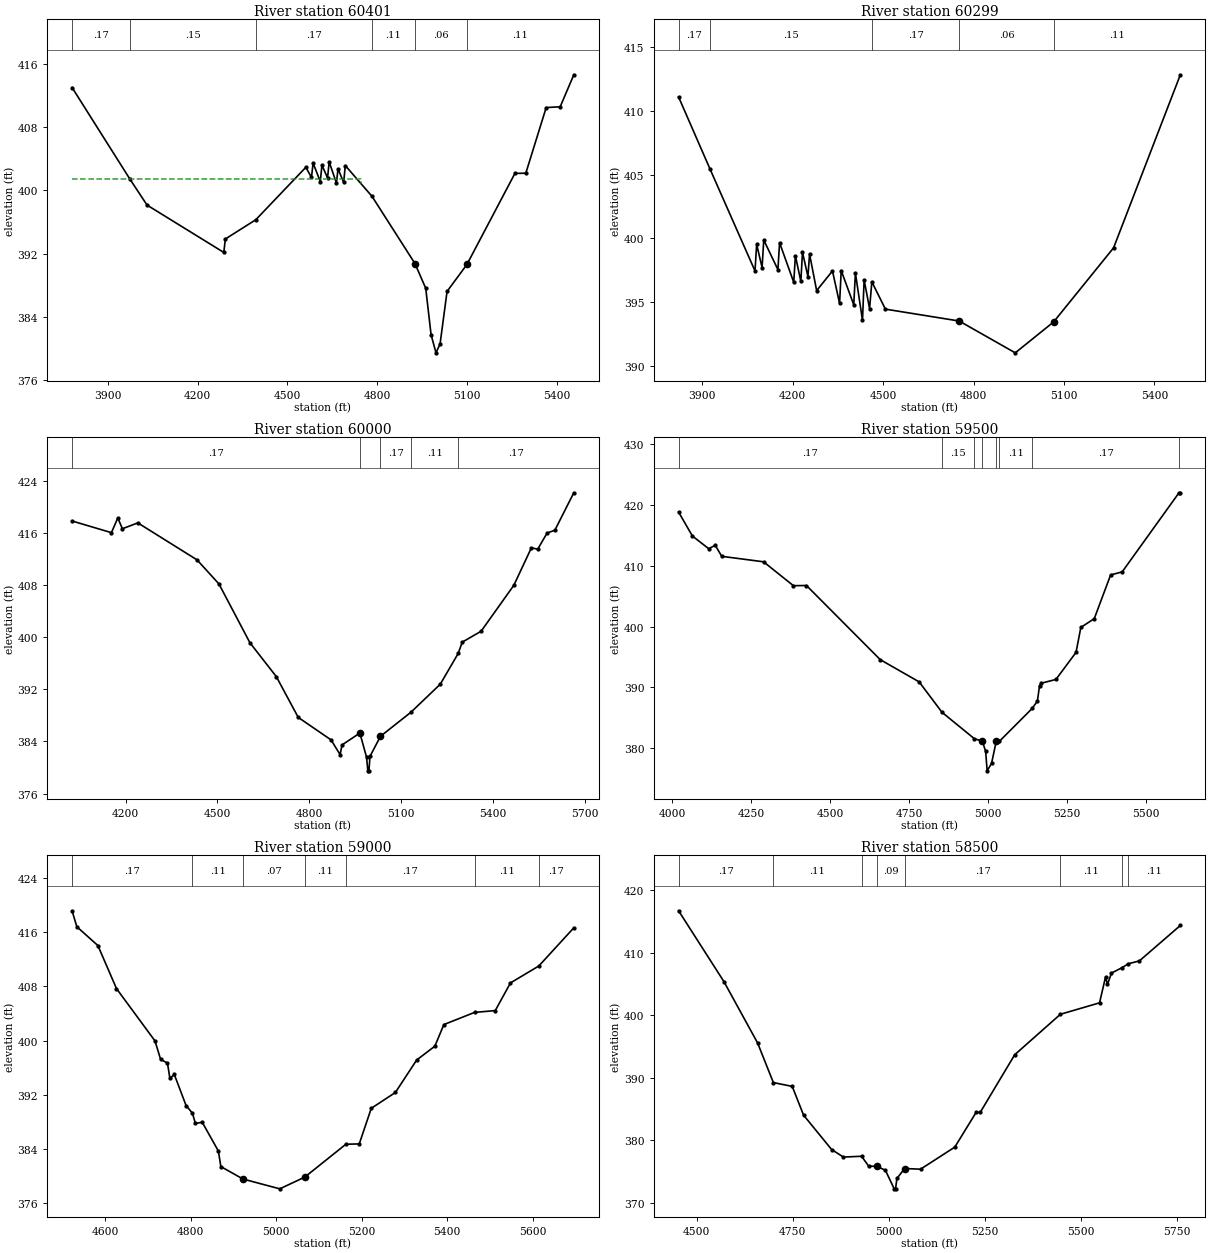
Type RM Length L Ch R = 1 ,60401   ,102,102,102
BEGIN DESCRIPTION:
MCDONALD CREEK 119.0
END DESCRIPTION:
XS GIS Cut Line= 3
      3801100.23     10243455.95      3799969.17     10243910.82
      3799551.06     10244094.31
#Sta/Elev= 30
  3780.9  413.01  3974.5  401.41  4031.4  398.15  4287.6  392.17  4292.9  393.87
  4394.5   396.3  4561.7  402.93  4580.5  401.65  4585.9  403.46    4610  401.12
  4615.4   403.2  4634.2  401.59  4639.6  403.61  4663.8  400.94  4669.2  402.73
    4688  401.01  4693.4  403.15  4782.6  399.26    4926  390.77  4962.1  387.64
  4979.9  381.78  4996.3  379.48    5010  380.61  5033.3  387.24  5099.7  390.65
    5260  402.16  5296.3  402.18  5364.4  410.48  5411.1  410.57  5456.6  414.62
#Mann= 6 ,-1 , 0
  3780.9     .17       0  3974.5     .15       0  4394.5     .17       0
  4782.6     .11       0    4926     .06       0  5099.7     .11       0
#XS Ineff= 2 , 0
       0  4747.1  401.41               0
Permanent Ineff=
       F       F
Bank Sta=4926,5099.7
XS Rating Curve= 0 ,0
Exp/Cntr=0.3,0.1

Type RM Length L Ch R = 1 ,60299   ,299,299,299
BEGIN DESCRIPTION:
Mapping XS b84d844e
END DESCRIPTION:
XS GIS Cut Line= 3
      3801032.83     10243344.52      3799950.93     10243810.71
       3799497.2     10243986.34
#Sta/Elev= 30
  3821.5  411.07    3926  405.42    4075  397.46  4080.5  399.54  4098.5  397.72
    4104  399.88    4151  397.56  4156.5  399.67  4203.5  396.57    4209  398.65
  4227.1  396.64  4232.5  398.93  4250.6  397.02    4256  398.78  4279.5  395.92
    4332  397.46  4355.6  394.92    4361  397.49  4402.6  394.81  4408.1  397.29
  4431.6  393.59    4437  396.76  4455.1  394.51  4462.6  396.61  4507.6  394.47
  4752.5  393.54  4938.4  391.05  5065.8  393.47  5264.7  399.27  5486.1  412.81
#Mann= 5 ,-1 , 0
  3821.5     .17       0    3926     .15       0  4462.6     .17       0
  4752.5     .06       0  5065.8     .11       0
#XS Ineff= 2 , 0
       0                  5065.8       0  393.47
Permanent Ineff=
       F       F
Bank Sta=4752.5,5065.8
XS Rating Curve= 0 ,0
Exp/Cntr=0.3,0.1

Type RM Length L Ch R = 1 ,60000   ,500,500,500
BEGIN DESCRIPTION:
MCDONALD CREEK 118.0
END DESCRIPTION:
XS GIS Cut Line= 3
      3800745.44     10242960.48      3799948.99       10243522.
      3799303.02     10243669.97
#Sta/Elev= 30
  4025.5  417.83  4153.9  416.04  4174.8   418.3  4189.6  416.64  4240.1  417.54
  4433.4  411.86  4504.8  408.17  4605.8  399.15    4692  393.95  4763.5  387.69
  4870.6  384.24  4900.2  381.97  4906.3  383.46  4964.7  385.29  4986.4  381.58
  4990.7  379.49  4994.2  379.49  4997.6  381.71  5031.9  384.79  5131.2  388.48
  5226.9  392.78  5285.4   397.5  5298.7  399.24  5360.2  400.91    5467  407.96
  5524.4  413.72  5544.9   413.5  5575.7  415.99  5600.9  416.41  5662.7  422.16
#Mann= 5 ,-1 , 0
  4025.5     .17       0  4964.7     .09       0  5031.9     .17       0
  5131.2     .11       0  5285.4     .17       0
Bank Sta=4964.7,5031.9
XS Rating Curve= 0 ,0
Exp/Cntr=0.3,0.1

Type RM Length L Ch R = 1 ,59500   ,500,500,500
BEGIN DESCRIPTION:
MCDONALD CREEK 117.0
END DESCRIPTION:
XS GIS Cut Line= 3
      3800710.33      10242919.4      3799760.03     10243159.25
      3799244.37     10243482.31
#Sta/Elev= 30
  4019.9  418.79  4063.7  414.86  4115.3  412.78  4135.9  413.34  4156.5  411.53
  4288.9  410.63  4383.4  406.71  4424.7  406.74  4658.4  394.57  4781.6  390.92
  4853.9  385.93  4956.7  381.58  4981.6   381.2  4992.1   379.5  4996.8  376.32
  5010.7  377.53    5026  381.25  5035.1  381.14  5139.4  386.56    5156  387.78
  5162.7   390.3  5168.6  390.71  5214.6  391.32  5278.2  395.76  5293.5  399.86
    5336   401.3  5387.8  408.47  5424.4  408.98  5604.3  421.96  5608.5  421.96
#Mann= 8 ,-1 , 0
  4019.9     .17       0  4853.9     .15       0  4956.7     .17       0
  4981.6     .09       0    5026     .17       0  5035.1     .11       0
  5139.4     .17       0  5604.3     .11       0
#XS Ineff= 2 , 0
       0                  5110.9       0     385
Permanent Ineff=
       F       F
Bank Sta=4981.6,5026
XS Rating Curve= 0 ,0
Exp/Cntr=0.3,0.1

Type RM Length L Ch R = 1 ,59000   ,500,500,500
BEGIN DESCRIPTION:
MCDONALD CREEK 116.0
END DESCRIPTION:
XS GIS Cut Line= 3
      3800047.65     10242467.91      3799630.19     10242698.68
      3799153.73     10243206.43
#Sta/Elev= 30
    4523  419.18  4534.2  416.82  4583.4  414.04  4626.9  407.68    4717  399.94
    4730  397.23  4746.1  396.67  4751.8   394.4  4762.1  394.99  4789.6   390.4
  4804.5  389.27  4811.4  387.75  4827.4  387.93  4865.2  383.67  4870.9  381.38
  4922.7  379.54  5008.7  378.09  5067.1  379.82  5163.3  384.68  5194.6  384.73
  5222.7  389.99  5279.1  392.33  5328.9  397.13  5371.4  399.17  5392.4  402.36
  5464.1  404.16  5512.6  404.43  5548.2  408.52  5614.5  411.02  5696.3  416.66
#Mann= 7 ,-1 , 0
    4523     .17       0  4804.5     .11       0  4922.7     .07       0
  5067.1     .11       0  5163.3     .17       0  5464.1     .11       0
  5614.5     .17       0
Bank Sta=4922.7,5067.1
XS Rating Curve= 0 ,0
Exp/Cntr=0.3,0.1

Type RM Length L Ch R = 1 ,58500   ,500,500,500
BEGIN DESCRIPTION:
MCDONALD CREEK 115.0
END DESCRIPTION:
XS GIS Cut Line= 3
      3799757.42     10242110.19      3799276.96     10242371.67
      3799083.07     10243104.14
#Sta/Elev= 30
    4453  416.71    4571  405.37  4658.4  395.58  4699.4  389.24  4748.5  388.63
    4778  384.03    4851  378.53  4881.6  377.33  4928.9  377.46  4947.1  375.88
    4969  375.84  4990.8  375.21  5013.7  372.25  5017.2  372.25  5020.7  373.91
  5040.8   375.5  5082.1  375.39  5171.2  378.92    5227  384.51  5237.3  384.47
    5327  393.69  5445.8  400.16  5547.6  401.99  5563.2  406.12  5568.3  404.94
  5578.7  406.75  5606.6  407.63  5622.9  408.25  5651.1  408.69  5757.7  414.36
#Mann= 8 ,-1 , 0
    4453     .17       0  4699.4     .11       0  4928.9     .17       0
    4969     .09       0  5040.8     .17       0  5445.8     .11       0
  5606.6     .17       0  5622.9     .11       0
Bank Sta=4969,5040.8
XS Rating Curve= 0 ,0
Exp/Cntr=0.3,0.1

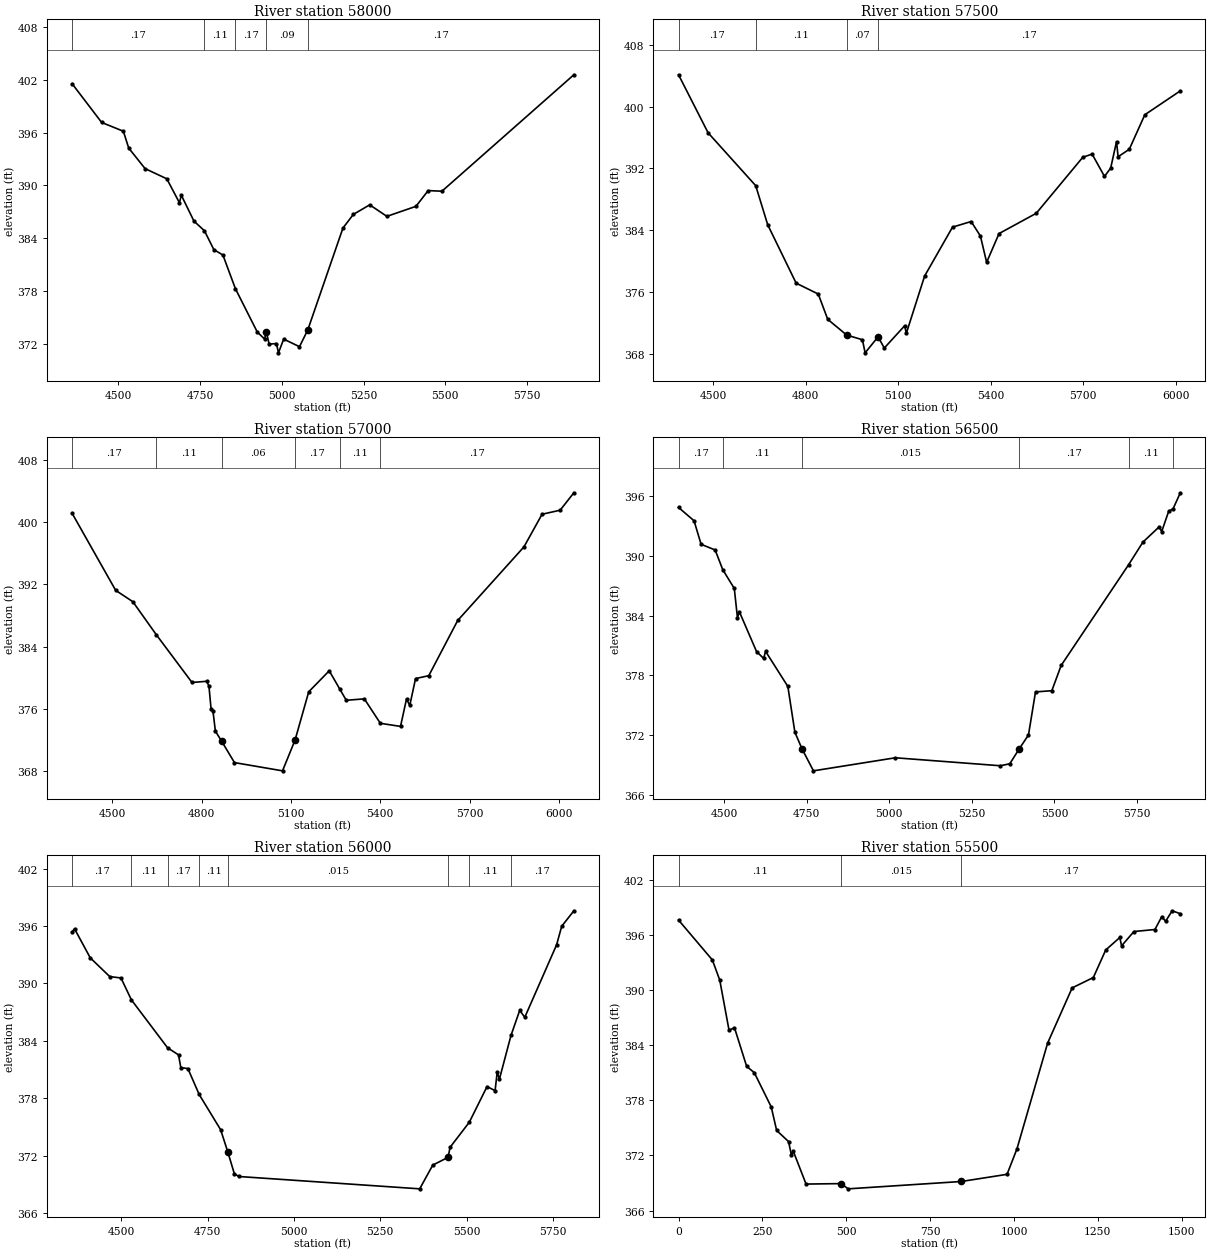
Type RM Length L Ch R = 1 ,58000   ,500,500,500
BEGIN DESCRIPTION:
MCDONALD CREEK 114.0
END DESCRIPTION:
XS GIS Cut Line= 3
      3799244.36     10241435.81      3798949.97     10242005.54
      3798672.73     10242854.53
#Sta/Elev= 30
  4358.7  401.56  4449.1  397.15  4515.5  396.15    4532  394.23    4582   391.9
  4648.4  390.74  4687.1  388.01  4692.7  388.88  4731.4  385.93  4763.5  384.83
  4792.2  382.69    4820  382.07  4858.1  378.25  4925.1  373.31  4947.2  372.53
  4952.9  373.32  4961.2  371.94  4983.7  372.01  4989.8  370.95  5005.8  372.51
  5054.1  371.65  5079.5  373.56    5187  385.14  5218.8  386.69  5268.8  387.78
  5321.4  386.47  5410.2  387.61  5447.6   389.4  5489.7  389.33  5893.1  402.57
#Mann= 5 ,-1 , 0
  4358.7     .17       0  4763.5     .11       0  4858.1     .17       0
  4952.9     .09       0  5079.5     .17       0
Bank Sta=4952.9,5079.5
XS Rating Curve= 0 ,0
Exp/Cntr=0.3,0.1

Type RM Length L Ch R = 1 ,57500   ,500,500,500
BEGIN DESCRIPTION:
MCDONALD CREEK 113.0
END DESCRIPTION:
XS GIS Cut Line= 3
      3798622.76     10241218.92      3798490.47     10241816.56
      3798593.45     10242825.61
#Sta/Elev= 30
  4387.9  404.11  4483.7  396.61  4638.1  389.77  4676.9  384.72  4769.1  377.17
  4840.8  375.76  4871.5  372.49  4932.9  370.46    4984  369.85  4992.6  368.16
  5034.7  370.23  5054.8  368.78    5121  371.67  5126.1  370.67  5185.5  378.09
  5275.9  384.41  5336.3  385.14  5366.4  383.26  5386.5  379.86  5426.7  383.58
  5547.3   386.2  5698.1  393.44  5728.3  393.86  5768.5  390.97  5788.6  392.05
  5807.5  395.47  5812.6  393.51  5848.9  394.48  5899.2  398.94  6014.3  402.03
#Mann= 4 ,-1 , 0
  4387.9     .17       0  4638.1     .11       0  4932.9     .07       0
  5034.7     .17       0
Bank Sta=4932.9,5034.7
XS Rating Curve= 0 ,0
Exp/Cntr=0.3,0.1

Type RM Length L Ch R = 1 ,57000   ,500,500,500
BEGIN DESCRIPTION:
MCDONALD CREEK 112.0
END DESCRIPTION:
XS GIS Cut Line= 3
      3798423.41     10241130.91      3798028.92     10241628.25
      3798185.82     10242666.67
#Sta/Elev= 30
  4365.2  401.13  4511.6  391.22  4569.3  389.76  4648.2  385.51  4767.9  379.38
  4817.6  379.53  4824.9  378.89    4832  375.96  4838.4  375.67  4846.5  373.12
  4867.3  371.84  4910.5  369.08  5071.9  368.02  5114.1  371.99  5159.9  378.18
  5228.8  380.88  5263.5  378.57    5286  377.09  5346.7  377.27  5400.4  374.13
  5468.1  373.73  5488.3  377.26  5499.2  376.42  5518.6  379.88    5563  380.25
  5660.2  387.35  5882.7  396.81  5943.4     401  6004.1  401.52  6050.2  403.76
#Mann= 6 ,-1 , 0
  4365.2     .17       0  4648.2     .11       0  4867.3     .06       0
  5114.1     .17       0  5263.5     .11       0  5400.4     .17       0
#XS Ineff= 2 , 0
       0                  5159.9       0  378.18
Permanent Ineff=
       F       F
Bank Sta=4867.3,5114.1
XS Rating Curve= 0 ,0
Exp/Cntr=0.3,0.1

Type RM Length L Ch R = 1 ,56500   ,500,500,500
BEGIN DESCRIPTION:
MCDONALD CREEK 111.0
END DESCRIPTION:
XS GIS Cut Line= 3
      3797919.12     10240928.61      3797584.35     10241471.84
      3796973.06     10242106.26
#Sta/Elev= 30
  4361.9  394.86  4408.9  393.52  4430.2  391.16  4472.8  390.59  4495.8  388.61
  4530.7  386.73  4540.3  383.78  4546.1  384.39  4598.2  380.39  4619.5  379.71
  4625.4  380.42  4692.8   376.9  4714.1  372.31  4735.4  370.66  4770.3  368.43
  5018.2  369.74  5336.4  368.94  5364.7  369.14    5393  370.62  5421.3  372.03
  5442.6  376.35    5492  376.47  5520.3  379.01  5724.2   389.1  5767.8  391.38
  5817.5  392.93  5824.4  392.42  5845.8  394.48  5858.9  394.71    5881  396.33
#Mann= 6 ,-1 , 0
  4361.9     .17       0  4495.8     .11       0  4735.4    .015       0
    5393     .17       0  5724.2     .11       0  5858.9     .17       0
Bank Sta=4735.4,5393
XS Rating Curve= 0 ,0
Exp/Cntr=0.3,0.1

Type RM Length L Ch R = 1 ,56000   ,500,500,500
BEGIN DESCRIPTION:
MCDONALD CREEK 110.0
END DESCRIPTION:
XS GIS Cut Line= 3
      3797878.05     10240893.45      3797265.67      10241087.2
      3796793.48     10241746.32
#Sta/Elev= 30
  4357.7  395.39  4364.8  395.71  4410.4  392.67  4466.9  390.71  4499.3  390.57
  4529.5  388.28  4634.3  383.27    4666  382.53  4672.6   381.2  4693.1   381.1
  4725.8  378.39  4787.9  374.71  4808.9  372.36  4827.6  370.11  4840.4  369.82
  5364.4  368.53  5402.2  371.01  5446.4  371.82  5452.5  372.88    5508  375.49
  5559.4  379.22  5582.7  378.79  5588.9  380.76  5595.2  379.99  5628.8  384.57
    5654  387.18  5668.7  386.46  5760.8  394.03  5775.6  395.97  5810.8  397.59
#Mann= 8 ,-1 , 0
  4357.7     .17       0  4529.5     .11       0  4634.3     .17       0
  4725.8     .11       0  4808.9    .015       0  5446.4     .17       0
    5508     .11       0  5628.8     .17       0
Bank Sta=4808.9,5446.4
XS Rating Curve= 0 ,0
Exp/Cntr=0.3,0.1

Type RM Length L Ch R = 1 ,55500   ,211,211,211
XS GIS Cut Line= 3
      3797596.72     10240345.44      3796999.55     10240666.77
      3796204.18     10240857.31
#Sta/Elev= 30
       0  397.64   100.9  393.29     123  391.08   150.5  385.65   166.8  385.91
   203.1   381.7   225.8  381.02   276.3  377.29   292.5  374.72     328  373.51
   336.4  372.06     342  372.47   380.2  368.88     484  368.93   505.9  368.36
     843  369.16   979.4  369.94  1008.9  372.71  1100.4  384.24  1173.5  390.25
  1236.7  391.38  1273.6  394.38  1315.6  395.74  1320.8  394.83  1357.7  396.39
  1420.3  396.61  1440.8  398.02    1452   397.5  1471.7  398.65    1496  398.33
#Mann= 3 , 0 , 0
       0     .11       0     484    .015       0     843     .17       0
Bank Sta=484,843
XS Rating Curve= 0 ,0
Exp/Cntr=0.3,0.1

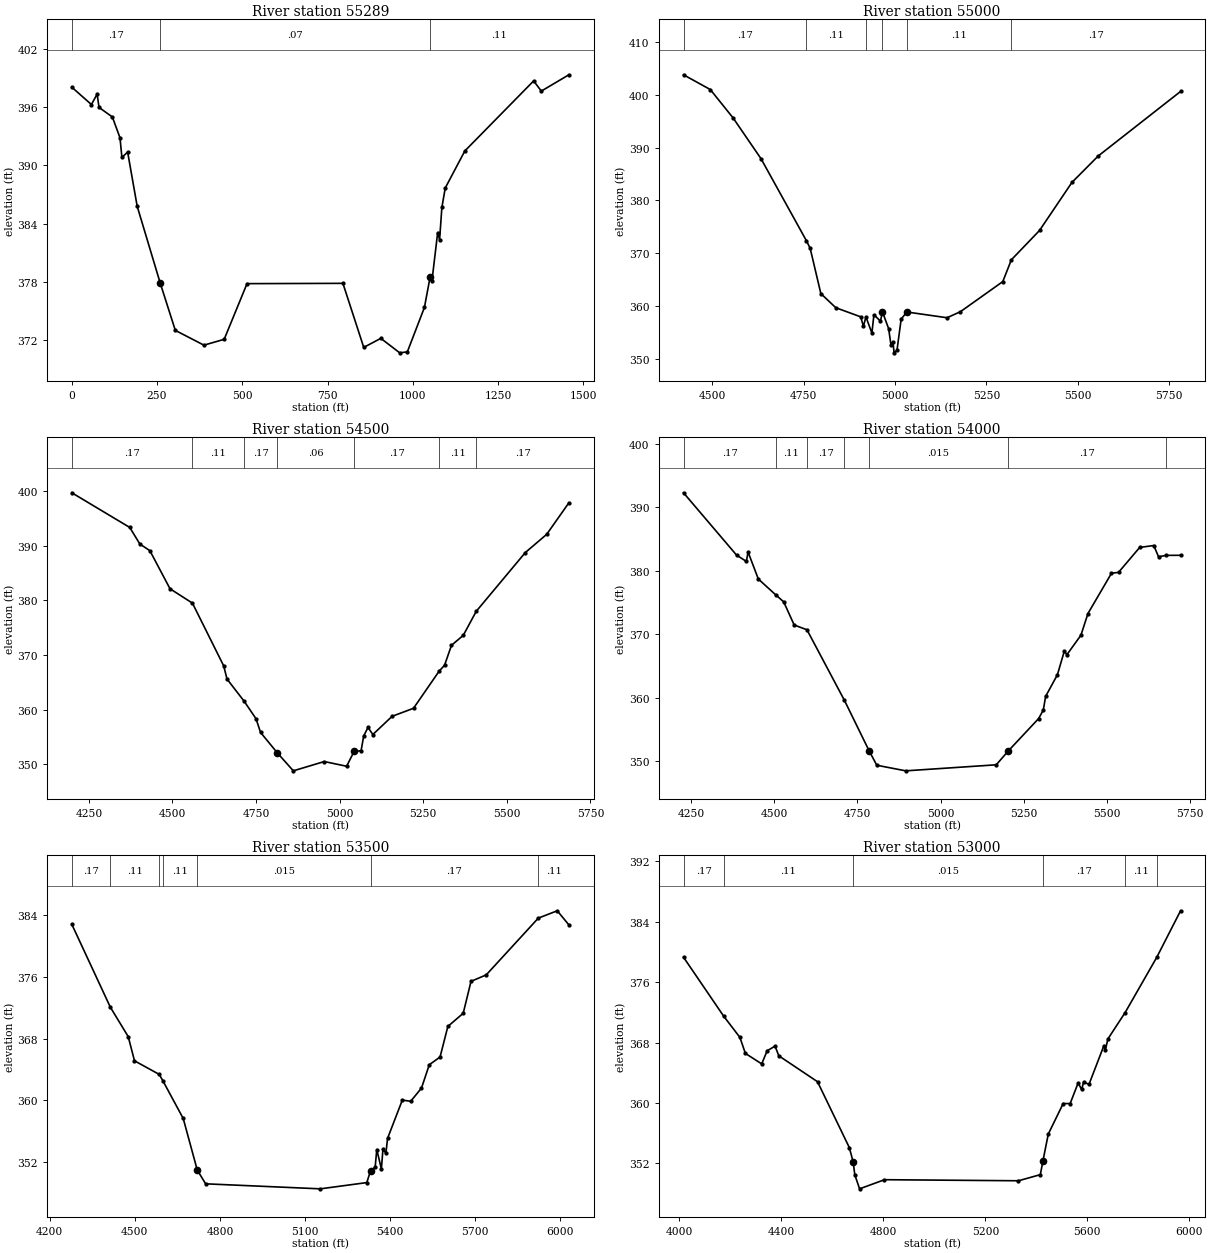
Type RM Length L Ch R = 1 ,55289   ,289,289,289
XS GIS Cut Line= 3
      3797497.76     10240182.24      3796908.04     10240476.25
      3796195.68     10240838.49
#Sta/Elev= 30
       0  398.04    57.4  396.26    74.2  397.33    79.8  395.96   118.9  394.98
   141.3  392.83   146.9  390.81   163.7  391.37   191.7  385.79   258.8  377.94
   303.6  373.02   387.5   371.5   446.9   372.1   513.9  377.83   795.2  377.86
   856.3  371.27   906.4   372.2   961.9  370.71   984.2  370.81  1034.3  375.38
  1050.9  378.49  1056.5  378.15  1073.2  383.09  1078.8  382.35  1085.5  385.67
  1095.4  387.67  1152.8  391.48  1354.7  398.69  1377.2  397.64  1458.1  399.32
#Mann= 3 , 0 , 0
       0     .17       0   258.8     .07       0  1050.9     .11       0
Bank Sta=258.8,1050.9
XS Rating Curve= 0 ,0
Exp/Cntr=0.3,0.1

Type RM Length L Ch R = 1 ,55000   ,500,500,500
BEGIN DESCRIPTION:
MCDONALD CREEK 108.0
END DESCRIPTION:
XS GIS Cut Line= 3
      3797312.18     10239987.49      3796781.69     10240220.23
      3796115.97     10240629.57
#Sta/Elev= 30
  4420.7   403.8  4494.1     401  4556.5  395.62  4632.9   387.9  4757.4  372.33
  4767.5  370.91  4796.7  362.34  4837.6  359.66  4905.9  357.93  4913.2  356.14
  4920.2  357.91  4936.5  354.85    4942  358.33  4959.9  357.12  4965.4  358.88
  4982.3  355.69  4988.7  352.62  4994.2  353.21  4997.1  351.11  5005.2  351.61
  5016.6   357.5  5032.1  358.85  5142.2  357.76  5178.9  358.91  5294.8  364.61
  5318.3  368.74  5395.4   374.3  5484.2  383.41  5556.2  388.42  5781.5  400.64
#Mann= 6 ,-1 , 0
  4420.7     .17       0  4757.4     .11       0  4920.2     .17       0
  4965.4     .07       0  5032.1     .11       0  5318.3     .17       0
Bank Sta=4965.4,5032.1
XS Rating Curve= 0 ,0
Exp/Cntr=0.3,0.1

Type RM Length L Ch R = 1 ,54500   ,500,500,500
BEGIN DESCRIPTION:
MCDONALD CREEK 107.0
END DESCRIPTION:
XS GIS Cut Line= 3
      3797250.62      10239814.5       3796452.1     10239874.81
       3796022.5     10240409.25
#Sta/Elev= 30
  4199.2  399.68  4372.5  393.33  4402.6   390.3  4432.6  389.08  4492.8  382.11
  4559.9  379.48  4653.3     368  4663.3  365.58  4714.8   361.5  4749.9  358.33
  4763.6  355.81  4814.2  352.04  4861.6  348.78  4954.1  350.48    5021  349.62
  5043.4  352.35  5064.2  352.45  5072.2   355.2    5085  356.72  5099.4  355.43
    5157  358.76    5221  360.23  5297.9  367.05  5313.8   368.1  5334.6  371.76
  5369.8  373.58  5408.6  377.98  5555.4  388.74  5619.4  392.08  5685.7  397.85
#Mann= 7 ,-1 , 0
  4199.2     .17       0  4559.9     .11       0  4714.8     .17       0
  4814.2     .06       0  5043.4     .17       0  5297.9     .11       0
  5408.6     .17       0
Bank Sta=4814.2,5043.4
XS Rating Curve= 0 ,0
Exp/Cntr=0.3,0.1

Type RM Length L Ch R = 1 ,54000   ,500,500,500
BEGIN DESCRIPTION:
MCDONALD CREEK 106.0
END DESCRIPTION:
XS GIS Cut Line= 3
      3797136.25     10239667.89      3796420.16     10239376.51
      3795916.61     10239893.65
#Sta/Elev= 30
  4226.9  392.26  4386.3  382.46  4415.8  381.46  4421.2  382.92  4451.9  378.69
    4505  376.16  4528.2   375.1  4559.8  371.45  4598.2   370.7  4710.9  359.59
    4785  351.67  4808.2  349.38  4895.2   348.5  5167.5  349.45  5202.8  351.58
  5294.8  356.72    5309  358.07    5316  360.22  5351.4  363.62  5372.5   367.4
  5379.7  366.76  5422.1  369.84  5443.3  373.26    5514  379.59  5535.3  379.74
  5598.9  383.66  5641.3  383.96  5655.5   382.2  5679.3  382.41  5721.8  382.42
#Mann= 7 ,-1 , 0
  4226.9     .17       0    4505     .11       0  4598.2     .17       0
  4710.9     .11       0    4785    .015       0  5202.8     .17       0
  5679.3     .11       0
Bank Sta=4785,5202.8
XS Rating Curve= 0 ,0
Exp/Cntr=0.3,0.1

Type RM Length L Ch R = 1 ,53500   ,500,500,500
BEGIN DESCRIPTION:
MCDONALD CREEK 105.0
END DESCRIPTION:
XS GIS Cut Line= 3
      3796977.94      10238462.9      3796389.53     10238881.64
      3795896.64     10239787.08
#Sta/Elev= 30
  4277.8   382.8  4413.8  372.06  4476.7  368.26  4498.8  365.13  4586.1  363.37
  4599.1  362.53  4670.7  357.66  4720.2  350.98  4749.7   349.2  5154.2  348.55
  5318.2  349.36  5331.5  350.92  5347.6  351.34  5353.3  353.64  5369.5  351.14
  5375.2   353.7  5385.6  353.16  5391.3  355.08  5443.4  360.04    5473  359.89
    5511   361.6  5538.5  364.62  5576.5  365.62    5604  369.58  5658.2  371.29
  5685.7  375.42  5739.4  376.26  5923.1  383.61  5989.9  384.56  6030.9  382.73
#Mann= 7 ,-1 , 0
  4277.8     .17       0  4413.8     .11       0  4586.1     .17       0
  4599.1     .11       0  4720.2    .015       0  5331.5     .17       0
  5923.1     .11       0
#XS Ineff= 2 , 0
       0                  5353.3       0  353.64
Permanent Ineff=
       F       F
Bank Sta=4720.2,5331.5
XS Rating Curve= 0 ,0
Exp/Cntr=0.3,0.1

Type RM Length L Ch R = 1 ,53000   ,500,500,500
BEGIN DESCRIPTION:
MCDONALD CREEK 104.0
END DESCRIPTION:
XS GIS Cut Line= 3
      3796878.29     10238049.47      3796035.01     10238556.74
      3795204.12     10239049.28
#Sta/Elev= 30
  4015.9   379.3  4173.1  371.51  4237.2  368.68  4258.6  366.56  4322.7  365.17
  4344.1  366.91  4375.1  367.52  4389.8  366.24  4541.6  362.81  4666.5  354.08
  4681.6  352.17  4687.9  350.48  4706.7  348.62  4804.4  349.83    5330  349.69
  5415.8   350.5  5425.6  352.26    5447  355.88  5505.5  359.92  5532.7  359.91
    5564  362.64  5577.9  361.78  5585.4  362.75  5606.8  362.47  5665.3   367.6
  5671.1  367.03  5680.9  368.48  5748.3  371.96  5872.4  379.28  5965.9  385.45
#Mann= 6 ,-1 , 0
  4015.9     .17       0  4173.1     .11       0  4681.6    .015       0
  5425.6     .17       0  5748.3     .11       0  5872.4     .17       0
Bank Sta=4681.6,5425.6
XS Rating Curve= 0 ,0
Exp/Cntr=0.3,0.1