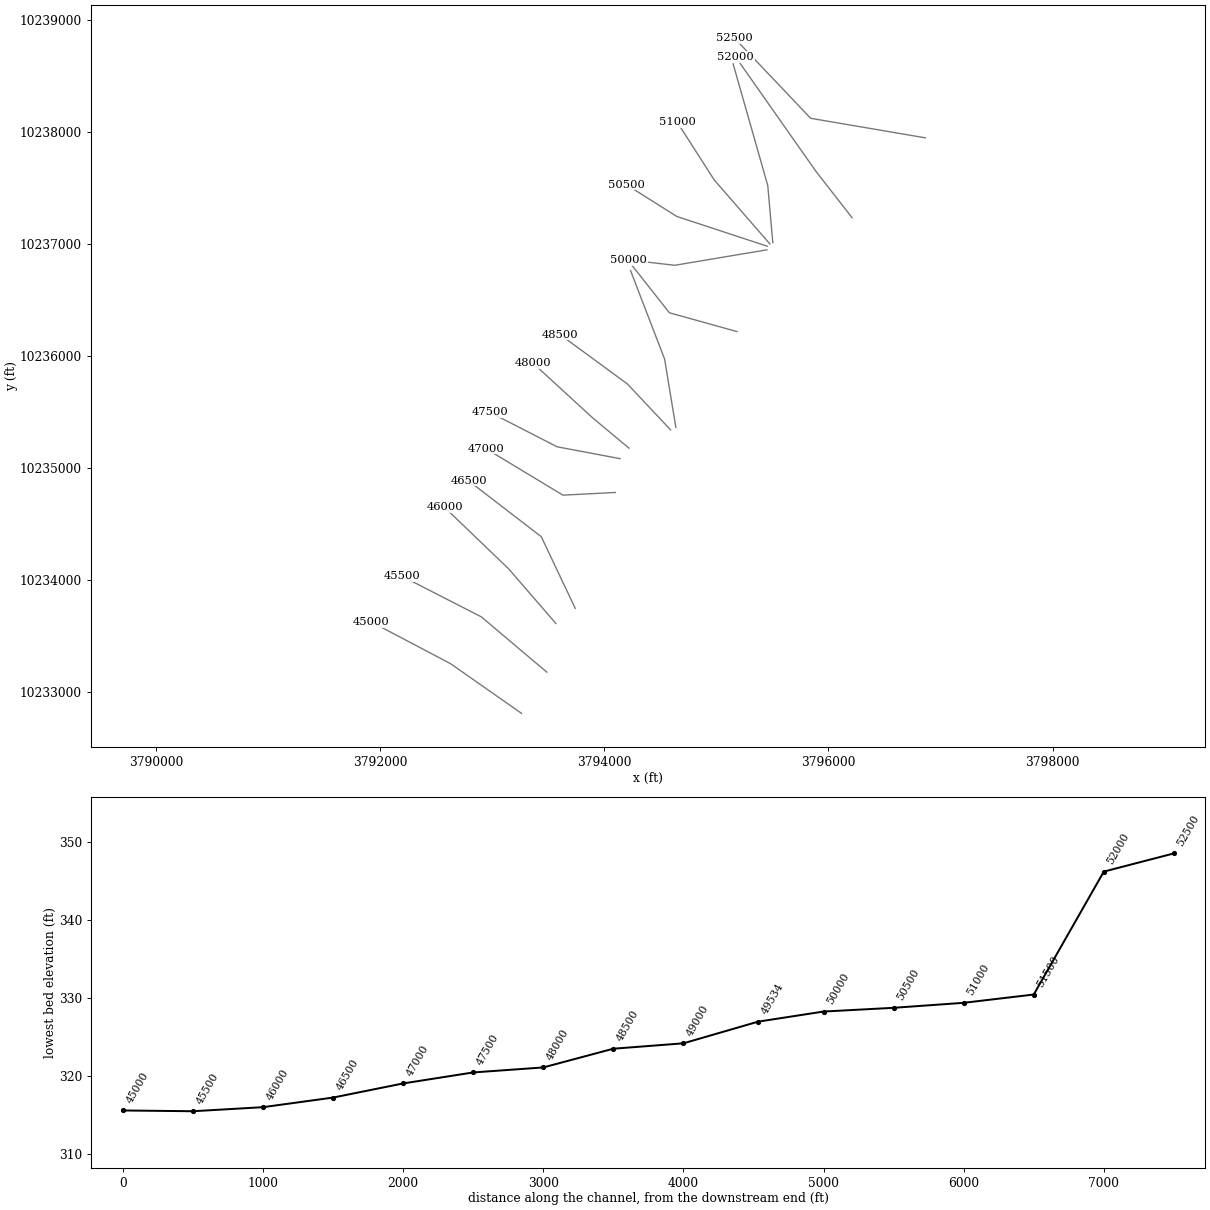
HEC-RAS study MCDONALD CREEK.prj: MCDONALD CREEK Base Level Engineering

--- MCDONALD CREEK.g01 (geometry) --- (continued)

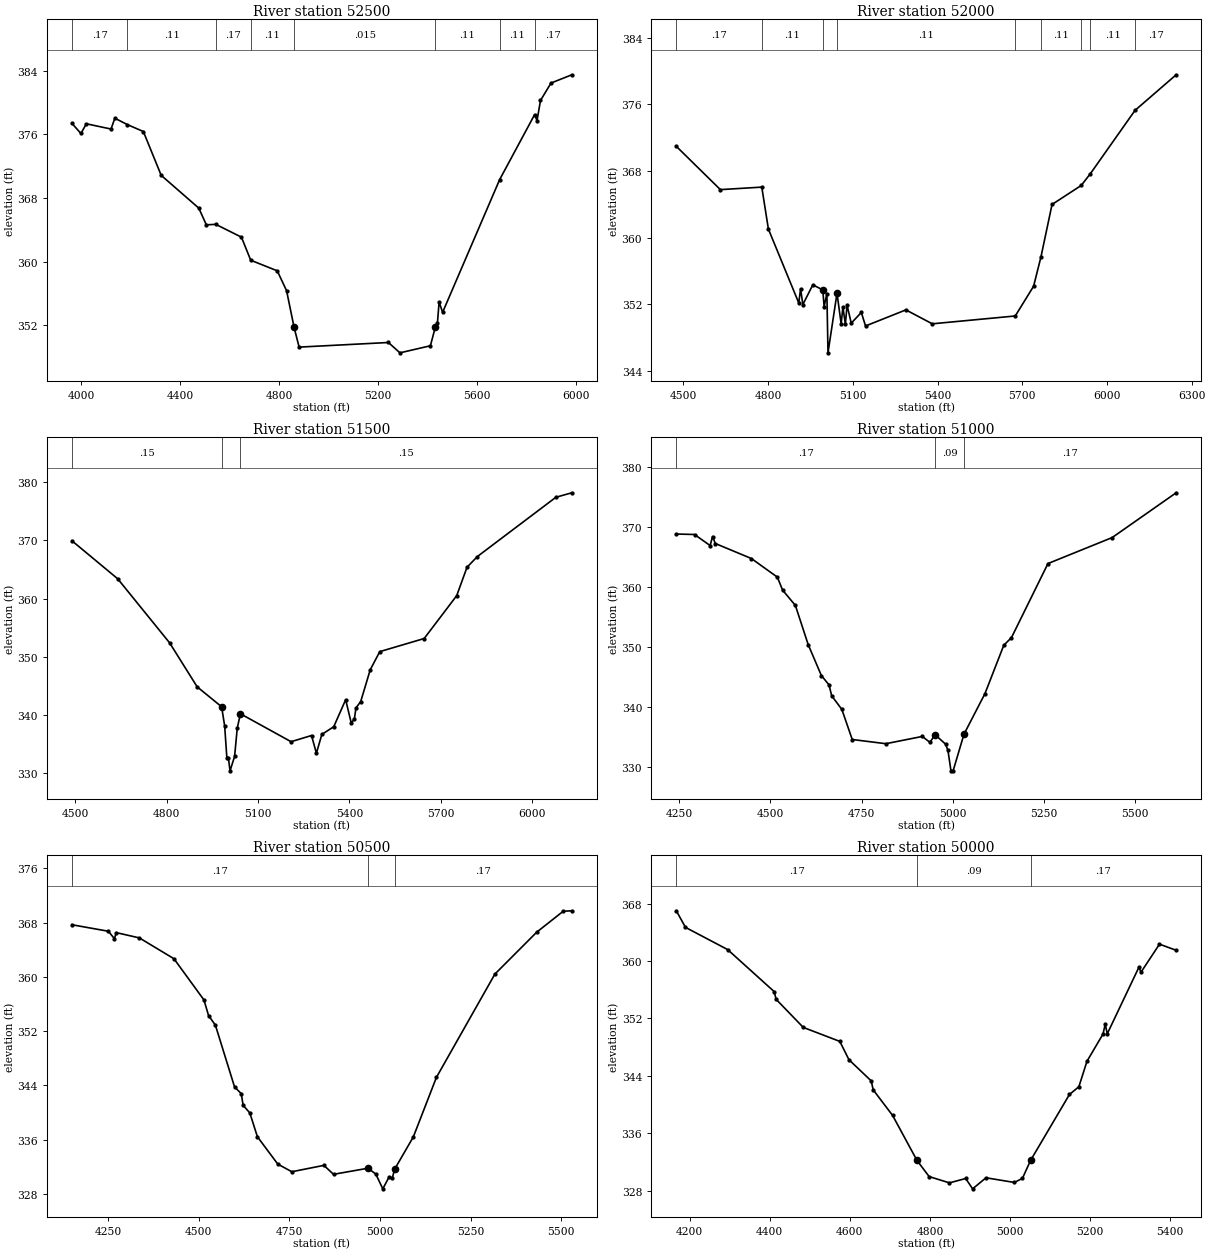
Type RM Length L Ch R = 1 ,52500   ,500,500,500
BEGIN DESCRIPTION:
MCDONALD CREEK 103.0
END DESCRIPTION:
XS GIS Cut Line= 3
      3796863.58     10237946.87      3795840.84      10238121.3
       3795163.1     10238835.24
#Sta/Elev= 30
  3962.5  377.37  3998.7   376.1  4020.7  377.32  4120.5  376.66  4135.9  378.02
  4186.4  377.22  4251.2  376.35  4323.4  370.84  4475.5  366.72    4506  364.62
  4544.2  364.68    4648  363.07  4685.6  360.17  4792.8  358.84  4830.6  356.34
    4861  351.73  4881.3  349.25  5242.5  349.83  5289.2  348.53  5412.4  349.42
 5432.23  351.76  5440.7  352.25  5447.6  354.92  5461.7  353.62  5692.6  370.31
  5833.7  378.46  5843.6  377.73  5857.7  380.25  5900.2  382.44  5984.4  383.48
#Mann= 8 ,-1 , 0
  3962.5     .17       0  4186.4     .11       0  4544.2     .17       0
  4685.6     .11       0    4861    .015       0 5432.23     .11       0
  5692.6     .11       0  5833.7     .17       0
#XS Ineff= 2 , 0
       0                  5447.6       0  354.92
Permanent Ineff=
       F       F
Bank Sta=4861,5432.23
XS Rating Curve= 0 ,0
Exp/Cntr=0.3,0.1

Type RM Length L Ch R = 1 ,52000   ,500,500,500
BEGIN DESCRIPTION:
MCDONALD CREEK 102.0
END DESCRIPTION:
XS GIS Cut Line= 3
      3796209.83     10237234.37       3795887.1     10237648.96
      3795171.88     10238668.15
#Sta/Elev= 30
  4474.6  370.96  4630.7  365.77  4777.4  366.07  4800.8  361.04  4908.4  352.18
  4914.8  353.87  4922.9  351.99  4958.2  354.36  4993.5  353.74  4998.2  351.75
    5008  353.29  5011.9   346.2  5043.8  353.35  5058.6  349.67  5064.7  351.71
  5073.4  349.62  5079.5  351.91  5094.3  349.76    5130  351.04  5144.9  349.42
  5287.8  351.35  5381.3  349.68  5675.2  350.62  5740.1  354.18  5766.1  357.68
  5805.5  363.99  5908.9  366.27  5941.5  367.69  6099.4  375.27  6245.1  379.54
#Mann= 9 ,-1 , 0
  4474.6     .17       0  4777.4     .11       0  4993.5     .07       0
  5043.8     .11       0  5675.2     .17       0  5766.1     .11       0
  5908.9     .17       0  5941.5     .11       0  6099.4     .17       0
#XS Ineff= 2 , 0
       0                  5043.8       0  353.35
Permanent Ineff=
       F       T
Bank Sta=4993.5,5043.8
XS Rating Curve= 0 ,0
Exp/Cntr=0.3,0.1

Type RM Length L Ch R = 1 ,51500   ,500,500,500
BEGIN DESCRIPTION:
MCDONALD CREEK 101.0
END DESCRIPTION:
XS GIS Cut Line= 3
       3795503.2     10237011.59       3795458.2     10237520.51
      3795148.93     10238607.77
#Sta/Elev= 30
  4489.1  369.91  4639.2   363.4  4809.8   352.4  4900.2  344.86  4980.5  341.44
  4990.5  338.14  4997.8  332.59  5002.9  332.59  5008.1  330.45  5023.1  332.92
  5031.8  337.77  5042.2  340.24  5208.5  335.45  5275.7  336.51  5291.7  333.47
  5309.6   336.7  5348.7  338.02  5387.8  342.65  5406.1  338.66  5416.4  339.35
  5421.6  341.24  5437.2  342.34  5468.4  347.78  5499.8   350.9  5645.6  353.15
  5752.4   360.5  5786.3  365.38  5820.2  367.21  6078.1  377.38  6130.4  378.15
#Mann= 3 , 0 , 0
  4489.1     .15       0  4980.5     .09       0  5042.2     .15       0
#XS Ineff= 2 , 0
       0                  5387.8       0  342.65
Permanent Ineff=
       F       F
Bank Sta=4980.5,5042.2
XS Rating Curve= 0 ,0
Exp/Cntr=0.3,0.1

Type RM Length L Ch R = 1 ,51000   ,500,500,500
BEGIN DESCRIPTION:
MCDONALD CREEK 100.0
END DESCRIPTION:
XS GIS Cut Line= 3
      3795476.83     10236999.84      3794979.97     10237571.49
      3794650.48     10238086.87
#Sta/Elev= 30
  4242.6  368.84  4292.5  368.76  4335.2  366.92  4341.9  368.42  4349.5  367.26
  4448.2  364.76  4519.4  361.66  4533.7   359.5  4568.8  356.94  4603.9  350.41
    4640  345.26  4660.9  343.71  4668.2  341.89    4696  339.63  4724.5  334.61
  4816.6  333.91  4916.4  335.12  4937.2  334.14  4951.5  335.41    4980  333.84
  4986.6  332.82  4994.9  329.39  5000.8  329.39  5030.5  335.48    5088  342.25
  5139.6  350.31  5160.7  351.59  5260.6  363.92  5436.5  368.25  5611.7  375.71
#Mann= 3 , 0 , 0
  4242.6     .17       0  4951.5     .09       0  5030.5     .17       0
Bank Sta=4951.5,5030.5
XS Rating Curve= 0 ,0
Exp/Cntr=0.3,0.1

Type RM Length L Ch R = 1 ,50500   ,500,500,500
BEGIN DESCRIPTION:
MCDONALD CREEK 99.0
END DESCRIPTION:
XS GIS Cut Line= 3
      3795453.36     10236979.33        3794647.      10237244.7
      3794199.74     10237526.82
#Sta/Elev= 30
  4151.1  367.68  4251.6  366.72    4268  365.63  4273.3  366.52  4336.9  365.74
  4432.2  362.67  4514.8   356.6  4527.6  354.29  4546.4  352.88  4599.1  343.79
  4617.7  342.78  4622.9  341.06  4641.2  339.95  4662.2  336.43  4718.3   332.4
    4757  331.27  4845.4  332.21    4872  330.89  4967.3  331.79  4988.6  330.92
  5007.8  328.75  5024.9  330.47  5034.3  330.38  5040.2  331.62    5092  336.41
  5155.6  345.18  5316.8  360.41  5432.1  366.59  5505.1  369.67  5528.8  369.74
#Mann= 3 , 0 , 0
  4151.1     .17       0  4967.3     .09       0  5040.2     .17       0
Bank Sta=4967.3,5040.2
XS Rating Curve= 0 ,0
Exp/Cntr=0.3,0.1

Type RM Length L Ch R = 1 ,50000   ,466,466,466
BEGIN DESCRIPTION:
MCDONALD CREEK 98.0
END DESCRIPTION:
XS GIS Cut Line= 3
      3795450.47     10236947.09      3794628.69     10236809.04
      3794216.57     10236856.13
#Sta/Elev= 30
  4166.7  366.99  4189.6  364.68  4294.8  361.59    4411  355.74    4416  354.66
  4483.7  350.75    4575   348.8  4597.8  346.25  4653.4   343.3  4658.4  342.05
  4706.8  338.49  4767.6  332.23    4798  329.98  4848.7   329.1  4889.3  329.71
  4906.6  328.27    4940  329.81  5010.9  329.16    5031  329.73  5051.2  332.22
  5148.4  341.41  5171.9  342.49  5192.1  346.03  5232.3  349.84  5237.7   351.2
  5242.8  349.86    5322  359.15  5327.1  358.44  5373.2  362.34  5414.8  361.49
#Mann= 3 ,-1 , 0
  4166.7     .17       0  4767.6     .09       0  5051.2     .17       0
Bank Sta=4767.6,5051.2
XS Rating Curve= 0 ,0
Exp/Cntr=0.3,0.1

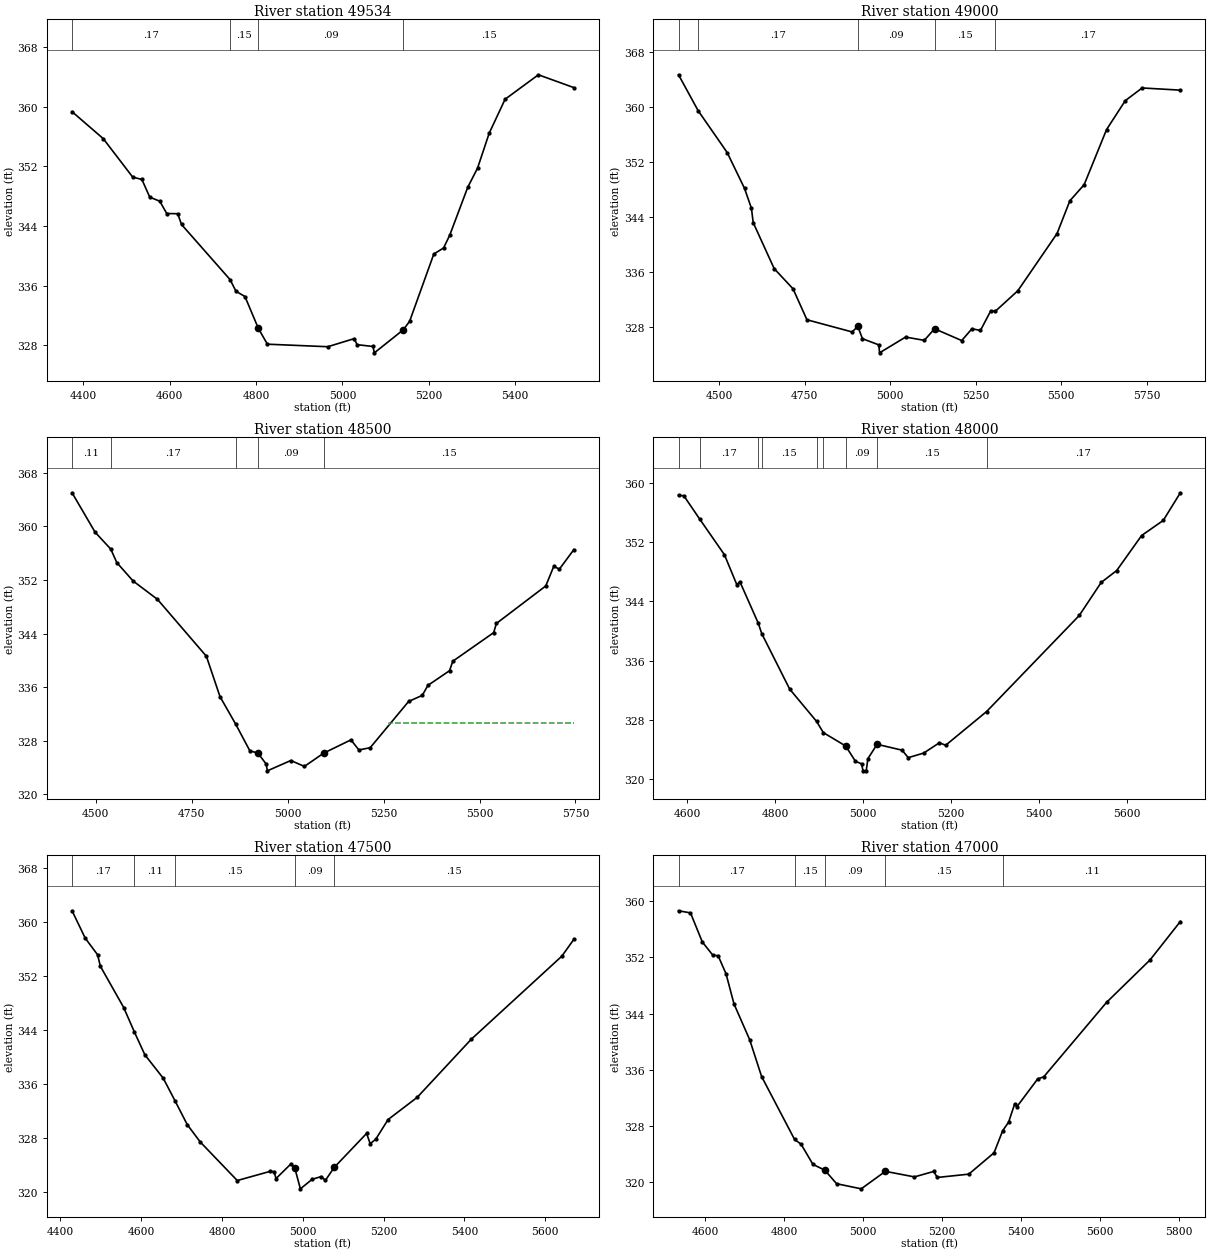
Type RM Length L Ch R = 1 ,49534   ,534,534,534
BEGIN DESCRIPTION:
MCDONALD CREEK 97.0
END DESCRIPTION:
XS GIS Cut Line= 3
      3795183.62     10236217.03      3794580.22     10236385.23
      3794248.45     10236806.21
#Sta/Elev= 30
  4373.6  359.31  4445.8   355.7  4514.2  350.53  4535.3  350.23  4553.6  347.85
  4576.8  347.31  4592.9  345.66  4618.4  345.63  4627.1  344.19  4739.6   336.8
  4753.3  335.23  4774.1  334.53  4805.2  330.25    4826  328.14    4966   327.8
  5027.3  328.89  5033.7  328.08  5070.6  327.83  5073.9  326.98  5141.1  330.08
  5155.6  331.22  5211.6  340.23  5234.2  341.04  5248.6  342.77  5290.2  349.18
  5312.8  351.73  5339.9  356.43  5376.7  360.98  5453.8  364.26    5536  362.54
#Mann= 4 ,-1 , 0
  4373.6     .17       0  4739.6     .15       0  4805.2     .09       0
  5141.1     .15       0
Bank Sta=4805.2,5141.1
XS Rating Curve= 0 ,0
Exp/Cntr=0.3,0.1

Type RM Length L Ch R = 1 ,49000   ,500,500,500
BEGIN DESCRIPTION:
MCDONALD CREEK 96.0
END DESCRIPTION:
XS GIS Cut Line= 3
      3794638.29     10235360.87      3794537.85     10235971.16
      3794233.67      10236762.4
#Sta/Elev= 30
  4381.5  364.73  4438.6  359.51  4523.6   353.4  4574.3  348.17  4594.5  345.27
  4599.7  343.18  4660.9  336.48  4716.1  333.53  4756.7  329.02  4888.4  327.25
  4905.6  328.04  4918.8  326.26  4966.8  325.36  4968.8   324.2    5045   326.5
  5099.6  326.02  5129.6  327.71  5208.9  325.99  5238.9  327.71  5263.6  327.46
  5293.6   330.3  5307.4  330.27  5372.9  333.25  5487.5  341.59  5524.9  346.36
  5566.8  348.72  5632.2  356.75  5686.9  360.96  5736.1  362.81  5847.7  362.49
#Mann= 5 ,-1 , 0
  4381.5     .11       0  4438.6     .17       0  4905.6     .09       0
  5129.6     .15       0  5307.4     .17       0
Bank Sta=4905.6,5129.6
XS Rating Curve= 0 ,0
Exp/Cntr=0.3,0.1

Type RM Length L Ch R = 1 ,48500   ,500,500,500
BEGIN DESCRIPTION:
MCDONALD CREEK 95.0
END DESCRIPTION:
XS GIS Cut Line= 3
      3794591.17     10235339.61       3794206.4     10235748.96
      3793605.08      10236190.3
#Sta/Elev= 30
  4438.2     365  4498.1  359.13  4539.1  356.59  4554.7  354.59  4597.2  351.84
  4660.7   349.1  4788.2  340.61  4823.8  334.57  4864.2  330.52  4901.5   326.5
  4922.5  326.16    4944  324.53  4947.2  323.51  5008.2  325.05  5043.7  324.17
  5093.9  326.15  5164.9  328.13  5185.7  326.63  5215.1  326.96  5315.4  333.87
  5350.9  334.77  5365.5  336.26  5421.9  338.45  5430.3  339.86  5536.9  344.13
    5544   345.5  5672.7   351.1  5693.5  354.02  5708.2  353.61  5745.9  356.52
#Mann= 5 ,-1 , 0
  4438.2     .11       0  4539.1     .17       0  4864.2     .15       0
  4922.5     .09       0  5093.9     .15       0
#XS Ineff= 2 , 0
       0                  5265.2       0   330.6
Permanent Ineff=
       F       F
Bank Sta=4922.5,5093.9
XS Rating Curve= 0 ,0
Exp/Cntr=0.3,0.1

Type RM Length L Ch R = 1 ,48000   ,500,500,500
BEGIN DESCRIPTION:
MCDONALD CREEK 94.0
END DESCRIPTION:
XS GIS Cut Line= 3
      3794219.65     10235176.41      3793896.88     10235445.63
      3793365.48     10235933.36
#Sta/Elev= 30
  4579.7  358.29  4591.7  358.24  4628.2  355.06  4684.1  350.28  4712.3  346.24
  4719.2  346.65    4761  341.05  4769.1  339.62  4832.5  332.15  4893.8  327.78
  4909.1  326.27    4960  324.46  4982.1   322.4  4996.1  322.06  4999.4  321.11
  5006.7  321.11  5010.5  322.75  5031.4  324.69  5088.2   323.9  5102.3  322.89
  5137.5  323.51  5173.2   324.9  5187.4  324.56  5280.5  329.11  5491.4  342.08
  5541.3  346.54  5576.5  348.14  5633.2  352.87  5682.5  354.91  5721.3  358.64
#Mann= 9 ,-1 , 0
  4579.7     .11       0  4628.2     .17       0    4761     .11       0
  4769.1     .15       0  4893.8     .11       0  4909.1     .15       0
    4960     .09       0  5031.4     .15       0  5280.5     .17       0
Bank Sta=4960,5031.4
XS Rating Curve= 0 ,0
Exp/Cntr=0.3,0.1

Type RM Length L Ch R = 1 ,47500   ,500,500,500
BEGIN DESCRIPTION:
MCDONALD CREEK 93.0
END DESCRIPTION:
XS GIS Cut Line= 3
      3794139.79     10235082.67      3793578.37     10235188.48
      3792981.44     10235495.15
#Sta/Elev= 30
  4428.7  361.66  4461.2  357.61  4491.7  355.16  4498.9  353.43  4556.5  347.33
  4582.5  343.77  4608.9  340.33  4654.5  336.85  4683.7   333.5  4713.8  329.99
  4746.1  327.41  4837.7   321.7  4919.1  323.06  4928.6  323.02  4933.7  321.99
    4970  324.13  4980.2  323.54    4994  320.47  5023.1  321.88  5045.6  322.29
  5055.8  321.72    5078  323.66    5158  328.68  5166.7  327.16  5180.5  327.81
  5211.1  330.73  5283.2  334.02  5416.6   342.6  5641.4  354.94  5671.1  357.43
#Mann= 5 ,-1 , 0
  4428.7     .17       0  4582.5     .11       0  4683.7     .15       0
  4980.2     .09       0    5078     .15       0
#XS Ineff= 2 , 0
       0                    5158       0  328.68
Permanent Ineff=
       F       F
Bank Sta=4980.2,5078
XS Rating Curve= 0 ,0
Exp/Cntr=0.3,0.1

Type RM Length L Ch R = 1 ,47000   ,500,500,500
BEGIN DESCRIPTION:
MCDONALD CREEK 92.0
END DESCRIPTION:
XS GIS Cut Line= 3
      3794098.16     10234780.59      3793630.87     10234756.64
      3792942.39     10235172.63
#Sta/Elev= 30
  4532.1  358.64  4562.4  358.34  4592.5  354.19  4618.9  352.33  4632.5  352.24
  4652.6  349.66  4672.6   345.4  4712.6  340.27  4742.7  335.05  4826.2   326.1
  4842.8  325.41  4872.9  322.54  4902.9  321.72  4932.9  319.79  4995.3  319.06
  5056.5  321.55  5130.2  320.76  5178.8  321.53  5188.4  320.68    5268  321.15
  5332.1  324.19  5354.1  327.35  5368.9  328.54  5384.4  331.15  5390.3  330.77
  5442.7   334.7  5458.2  335.01  5617.3   345.6  5727.9  351.66  5804.4  357.11
#Mann= 5 ,-1 , 0
  4532.1     .17       0  4826.2     .15       0  4902.9     .09       0
  5056.5     .15       0  5354.1     .11       0
Bank Sta=4902.9,5056.5
XS Rating Curve= 0 ,0
Exp/Cntr=0.3,0.1

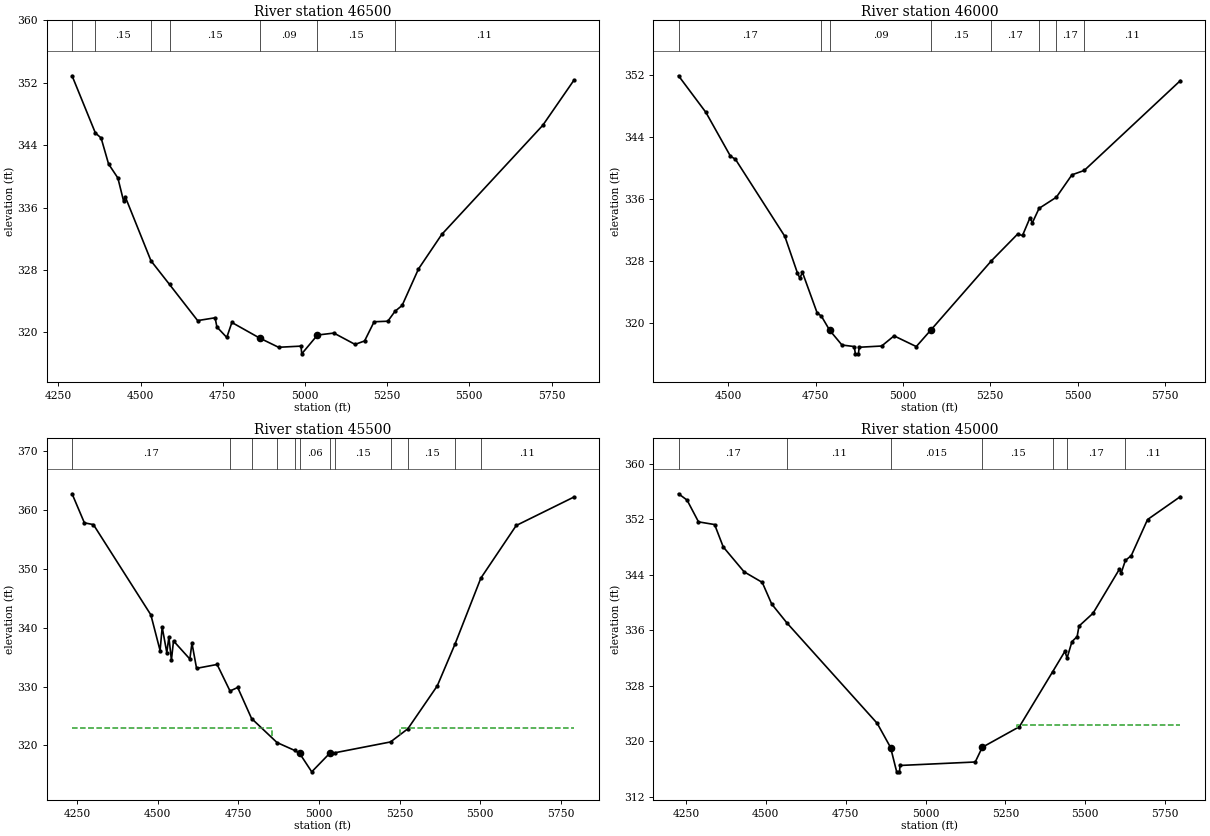
Type RM Length L Ch R = 1 ,46500   ,500,500,500
BEGIN DESCRIPTION:
MCDONALD CREEK 91.0
END DESCRIPTION:
XS GIS Cut Line= 3
      3793740.46      10233745.9      3793437.25     10234385.91
      3792789.09     10234884.75
#Sta/Elev= 30
  4291.8  352.88  4362.7  345.55  4380.1  344.91  4402.8  341.58  4431.1  339.78
  4448.3  336.86  4453.8  337.35  4531.8  329.17  4588.2  326.14  4673.7  321.51
  4726.8  321.87  4732.3  320.69  4762.3  319.35  4777.8  321.27  4861.9  319.28
  4919.8  318.09    4988  318.24  4990.3  317.25  5038.2  319.66  5088.1  319.91
  5152.4  318.46  5181.4   318.9  5210.4  321.36  5252.1  321.43  5273.9   322.7
  5295.6  323.45  5345.4  328.13  5416.1  332.55  5723.3  346.53  5817.9   352.3
#Mann= 7 ,-1 , 0
  4291.8     .17       0  4362.7     .15       0  4531.8     .17       0
  4588.2     .15       0  4861.9     .09       0  5038.2     .15       0
  5273.9     .11       0
Bank Sta=4861.9,5038.2
XS Rating Curve= 0 ,0
Exp/Cntr=0.3,0.1

Type RM Length L Ch R = 1 ,46000   ,500,500,500
BEGIN DESCRIPTION:
MCDONALD CREEK 90.0
END DESCRIPTION:
XS GIS Cut Line= 3
      3793567.84     10233611.09      3793147.94     10234096.99
      3792575.18     10234647.32
#Sta/Elev= 30
  4357.8  351.92  4436.2  347.19  4506.4  341.54  4520.7  341.14  4662.2  331.18
  4698.3  326.44    4705  325.81  4712.6  326.53  4754.3  321.34    4767  320.87
  4790.5  319.06  4825.6  317.16  4860.7  316.96  4864.1  316.02  4872.7  316.02
    4875  316.87  4939.3  317.03  4974.8  318.34  5038.4  316.96  5080.8  319.13
  5253.6  328.04  5328.3  331.47  5342.5   331.3  5363.6  333.55  5370.8  332.95
  5389.9   334.8  5439.4  336.24    5484  339.13  5519.3   339.7  5794.3  351.29
#Mann= 8 ,-1 , 0
  4357.8     .17       0    4767     .15       0  4790.5     .09       0
  5080.8     .15       0  5253.6     .17       0  5389.9     .11       0
  5439.4     .17       0  5519.3     .11       0
Bank Sta=4790.5,5080.8
XS Rating Curve= 0 ,0
Exp/Cntr=0.3,0.1

Type RM Length L Ch R = 1 ,45500   ,500,500,500
BEGIN DESCRIPTION:
MCDONALD CREEK 89.0
END DESCRIPTION:
XS GIS Cut Line= 3
      3793487.03      10233176.4      3792901.81     10233670.49
      3792198.77      10234030.6
#Sta/Elev= 30
  4234.1  362.76  4272.3  357.82  4300.3  357.52  4478.4  342.18    4507  336.11
  4513.5  340.08  4527.8  335.78  4534.3   338.4  4542.1  334.49  4548.6  337.75
  4599.3  334.67  4605.8  337.37  4620.1  333.09  4683.8  333.75  4723.8  329.24
  4747.6  329.84  4790.7  324.56  4869.5  320.48  4924.2  319.14  4939.7  318.63
  4977.2   315.5  5033.4  318.68  5048.9  318.74  5221.4  320.58  5275.2  322.82
  5366.4  330.11  5421.9  337.28  5501.5  348.42  5611.2  357.37  5789.9   362.2
#Mann= 12 ,-1 , 0
  4234.1     .17       0  4723.8     .11       0  4790.7     .15       0
  4869.5     .11       0  4924.2     .15       0  4939.7     .06       0
  5033.4     .11       0  5048.9     .15       0  5221.4     .11       0
  5275.2     .15       0  5421.9     .17       0  5501.5     .11       0
#XS Ineff= 2 , 0
       0  4854.2  322.91  5249.8       0  322.92
Permanent Ineff=
       F       F
Bank Sta=4939.7,5033.4
XS Rating Curve= 0 ,0
Exp/Cntr=0.3,0.1

Type RM Length L Ch R = 1 ,45000   ,500,500,500
BEGIN DESCRIPTION:
MCDONALD CREEK 88.0
END DESCRIPTION:
XS GIS Cut Line= 3
      3793261.33     10232808.35      3792627.94     10233252.16
      3791921.91     10233623.87
#Sta/Elev= 30
  4226.6  355.71  4253.3   354.8  4289.1  351.66  4339.6  351.27  4366.6  348.04
    4432  344.45  4488.7  342.93  4518.3  339.81    4566  337.08  4848.7   322.6
  4890.6  319.11  4909.7   315.6  4918.5   315.6  4920.2  316.52  5155.7  317.02
  5177.7  319.14  5293.9  322.11  5398.1  330.04  5436.4  332.98  5443.3  332.02
  5458.5  334.38  5474.8  335.11  5480.5  336.62  5524.6  338.48  5607.1  344.83
  5612.7  344.29  5625.8  346.09  5644.3  346.79  5695.2  351.99  5797.9   355.3
#Mann= 7 ,-1 , 0
  4226.6     .17       0    4566     .11       0  4890.6    .015       0
  5177.7     .15       0  5398.1     .11       0  5443.3     .17       0
  5625.8     .11       0
#XS Ineff= 2 , 0
       0                  5287.9       0  322.31
Permanent Ineff=
       F       F
Bank Sta=4890.6,5177.7
XS Rating Curve= 0 ,0
Exp/Cntr=0.3,0.1