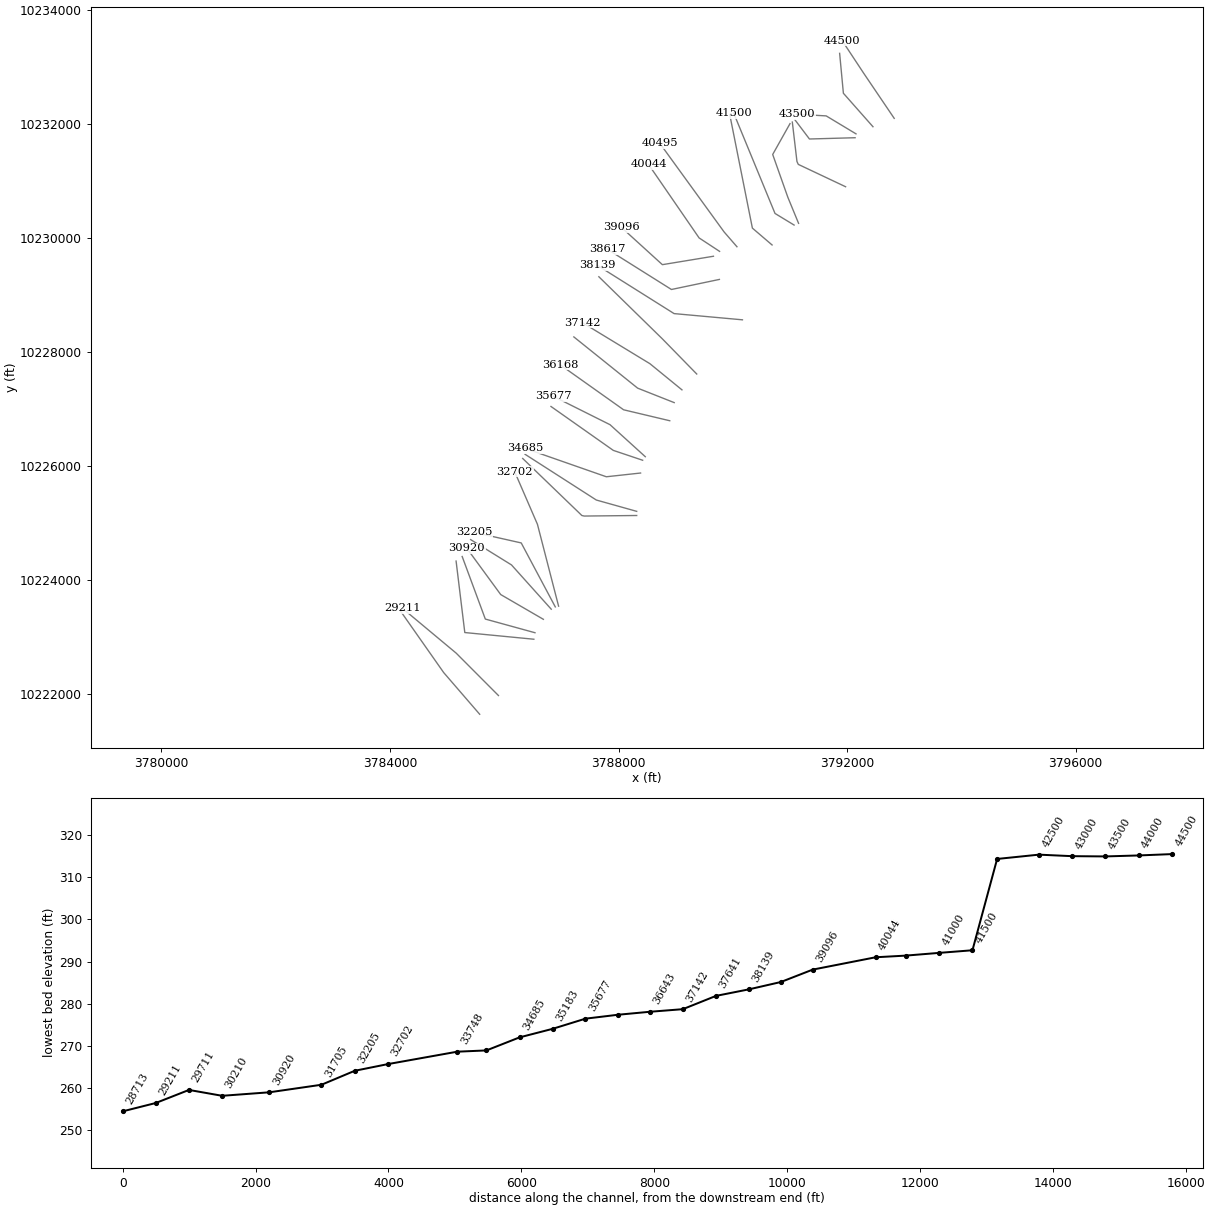
HEC-RAS study MCDONALD CREEK.prj: MCDONALD CREEK Base Level Engineering

--- MCDONALD CREEK.g01 (geometry) --- (continued)

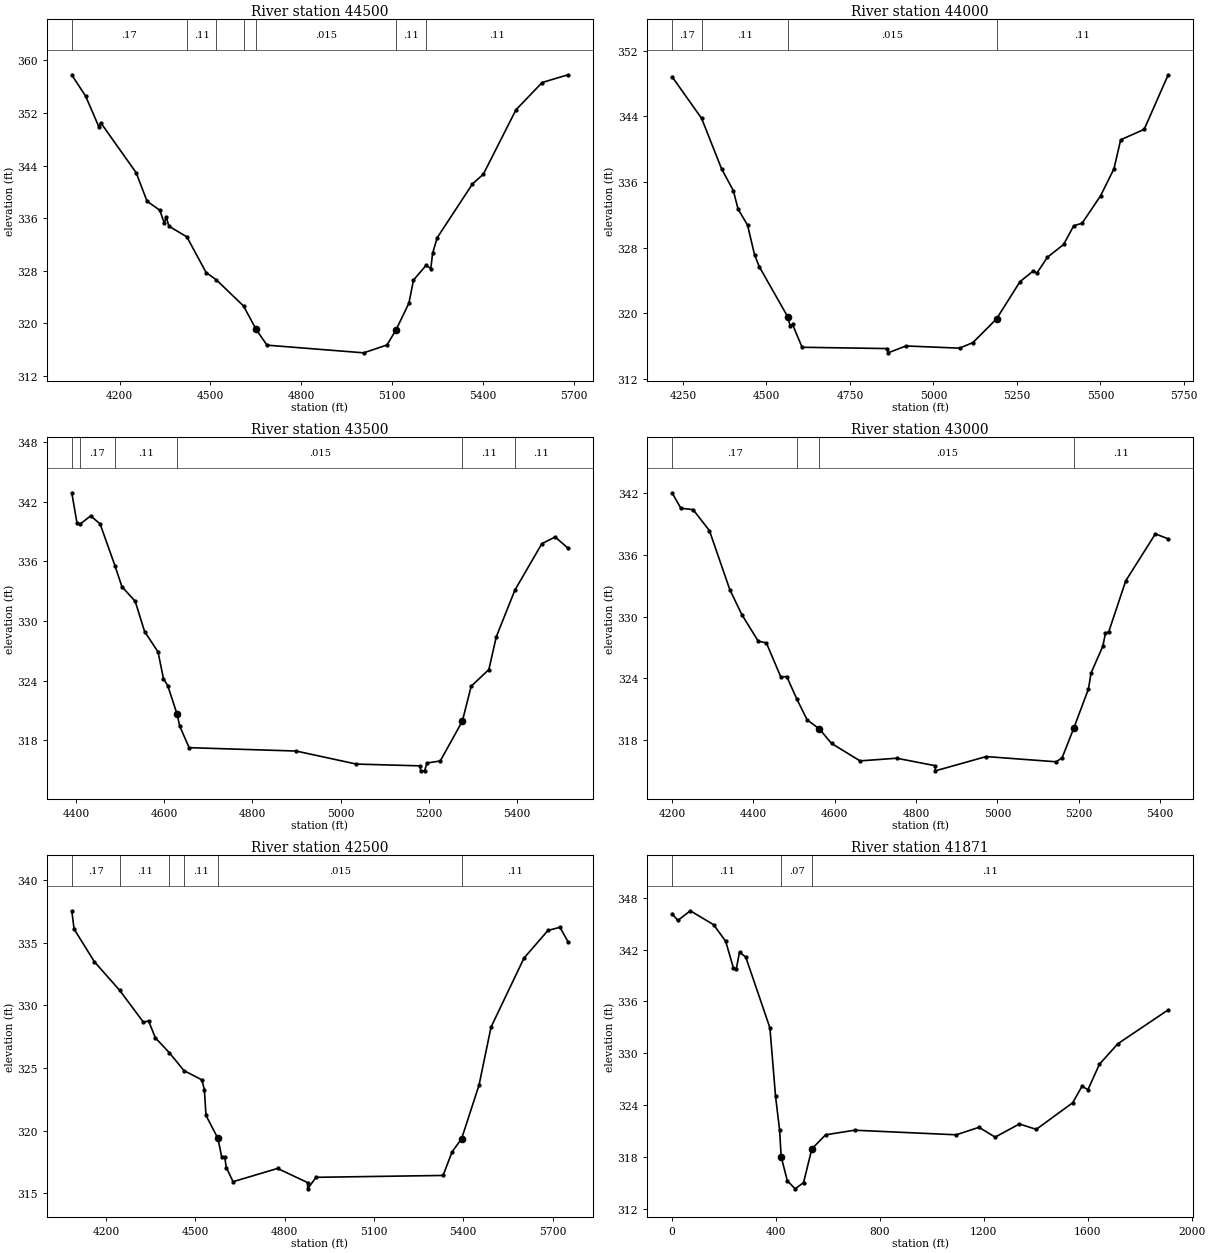
Type RM Length L Ch R = 1 ,44500   ,500,500,500
BEGIN DESCRIPTION:
MCDONALD CREEK 87.0
END DESCRIPTION:
XS GIS Cut Line= 3
      3792823.82     10232093.07        3792288.      10232886.6
      3791914.08     10233454.21
#Sta/Elev= 30
  4042.5  357.79  4088.4  354.55  4132.1  349.87  4138.1  350.51    4255   342.9
  4290.9  338.56  4332.9   337.2  4347.9  335.19  4353.9  336.22  4362.9  334.77
  4422.2  333.14  4485.7  327.71  4519.6  326.59  4609.3  322.61  4650.6  319.06
  4686.6  316.65  5005.8  315.48  5082.6  316.68  5112.8  319.01  5154.9  323.04
    5170  326.56  5211.5  328.79  5227.2  328.32  5233.2  330.65  5248.3  333.01
  5364.6   341.2  5400.5  342.68  5508.3  352.49  5594.6  356.64  5679.7  357.82
#Mann= 7 ,-1 , 0
  4042.5     .17       0  4422.2     .11       0  4519.6     .17       0
  4609.3     .11       0  4650.6    .015       0  5112.8     .11       0
  5211.5     .11       0
Bank Sta=4650.6,5112.8
XS Rating Curve= 0 ,0
Exp/Cntr=0.3,0.1

Type RM Length L Ch R = 1 ,44000   ,500,500,500
BEGIN DESCRIPTION:
MCDONALD CREEK 86.0
END DESCRIPTION:
XS GIS Cut Line= 3
      3792452.11     10231946.27      3791934.44     10232533.05
      3791868.75     10233232.78
#Sta/Elev= 30
  4217.5  348.85    4306  343.76  4365.7  337.61  4400.9  334.95  4415.1   332.7
  4443.5  330.74  4464.4  327.13  4478.6  325.67    4564  319.54  4570.7  318.48
  4578.2  318.63  4606.7  315.84  4861.8  315.68    4864  315.16  4917.9     316
  5078.4  315.73  5118.5  316.42  5188.8   319.3  5259.2  323.85  5299.3  325.16
  5309.4  324.87  5341.2  326.82  5389.7  328.38  5419.9  330.66    5445  330.97
  5500.2  334.31  5540.4  337.61  5560.5  341.15  5630.8  342.42  5702.8  349.08
#Mann= 4 ,-1 , 0
  4217.5     .17       0    4306     .11       0    4564    .015       0
  5188.8     .11       0
Bank Sta=4564,5188.8
XS Rating Curve= 0 ,0
Exp/Cntr=0.3,0.1

Type RM Length L Ch R = 1 ,43500   ,500,500,500
BEGIN DESCRIPTION:
MCDONALD CREEK 85.0
END DESCRIPTION:
XS GIS Cut Line= 3
      3792155.19     10231821.31      3791633.38     10232136.27
      3791118.78     10232165.05
#Sta/Elev= 30
  4390.5  342.88  4402.3  339.84  4408.5   339.7  4433.3  340.56  4454.7  339.75
  4488.5  335.53  4504.2  333.44  4534.3  331.97  4555.6  328.93    4586  326.89
  4598.4  324.18    4608   323.5  4629.4   320.6  4635.2  319.42  4656.6  317.26
  4899.2  316.92  5035.6  315.61  5180.8  315.43  5181.3  314.93  5190.4  314.93
  5195.8  315.72  5225.9  315.92    5276  319.93    5296  323.43  5336.1  325.11
  5352.9   328.4  5395.2   333.1  5456.2  337.76  5486.3  338.44  5515.4  337.32
#Mann= 6 ,-1 , 0
  4390.5     .11       0  4408.5     .17       0  4488.5     .11       0
  4629.4    .015       0    5276     .11       0  5395.2     .11       0
Bank Sta=4629.4,5276
XS Rating Curve= 0 ,0
Exp/Cntr=0.3,0.1

Type RM Length L Ch R = 1 ,43000   ,500,500,500
BEGIN DESCRIPTION:
MCDONALD CREEK 84.0
END DESCRIPTION:
XS GIS Cut Line= 3
      3792139.58     10231753.59       3791340.4     10231731.11
      3791087.52     10232066.07
#Sta/Elev= 30
  4200.5  342.07  4222.2  340.56  4252.2  340.43  4292.3  338.39  4342.3  332.65
  4372.3  330.18  4412.3  327.62  4432.3  327.45  4467.6  324.14  4482.3  324.17
  4507.5  321.95  4532.4  319.96  4562.4  319.07  4592.4  317.66  4662.4  315.96
  4752.4  316.22    4847  315.49  4847.5  314.99  4972.5  316.38  5144.7  315.87
  5159.2  316.28  5187.9  319.17  5223.8  322.98    5230  324.51  5259.1  327.13
  5265.4  328.38  5273.7  328.55  5315.4   333.5  5388.2  338.07  5419.7  337.58
#Mann= 4 ,-1 , 0
  4200.5     .17       0  4507.5     .11       0  4562.4    .015       0
  5187.9     .11       0
Bank Sta=4562.4,5187.9
XS Rating Curve= 0 ,0
Exp/Cntr=0.3,0.1

Type RM Length L Ch R = 1 ,42500   ,629,629,629
BEGIN DESCRIPTION:
MCDONALD CREEK 83.0
END DESCRIPTION:
XS GIS Cut Line= 4
      3791972.93     10230894.21      3791145.41     10231286.02
      3791121.86      10231337.1      3791040.84     10232027.82
#Sta/Elev= 30
  4084.4  337.55  4092.2  336.09  4160.4  333.48  4245.3   331.2  4325.2  328.65
  4342.4  328.76  4365.1  327.41  4412.2  326.22  4461.3  324.79  4521.5  324.05
  4529.9  323.28  4535.4  321.21  4575.4  319.38  4587.9  317.93  4598.2  317.91
  4603.7  317.05  4626.4  315.92    4776  316.98  4876.7  315.85  4877.2  315.35
  4904.9  316.27  5332.1  316.42  5362.3   318.3  5394.3  319.35  5452.9  323.63
  5493.2  328.26  5603.9  333.77  5684.5  335.98  5724.8  336.23  5751.7  335.09
#Mann= 6 ,-1 , 0
  4084.4     .17       0  4245.3     .11       0  4412.2     .17       0
  4461.3     .11       0  4575.4    .015       0  5394.3     .11       0
Bank Sta=4575.4,5394.3
XS Rating Curve= 0 ,0
Exp/Cntr=0.3,0.1

Type RM Length L Ch R = 1 ,41871   ,371,371,371
XS GIS Cut Line= 4
      3791150.19      10230252.7      3790961.92      10230710.8
      3790697.29     10231459.94      3791000.21     10232000.52
#Sta/Elev= 30
       0  346.16    22.3  345.37    70.2  346.49   160.4  344.87   206.3  342.96
   236.1  339.88   246.9  339.73   259.6   341.7   283.6  341.14   376.6  332.95
   398.3  325.02   413.9  321.13   419.9  318.04   443.6  315.26   473.9  314.33
   506.2  315.06     538  318.95     591  320.58   702.5  321.11  1093.9  320.58
  1181.3  321.45  1243.2  320.31  1336.6  321.83  1401.7  321.21  1542.1  324.29
  1577.7   326.2  1600.6   325.8  1644.8  328.74  1715.6  331.11  1909.5  335.03
#Mann= 3 , 0 , 0
       0     .11       0   419.9     .07       0     538     .11       0
Bank Sta=419.9,538
XS Rating Curve= 0 ,0
Exp/Cntr=0.3,0.1

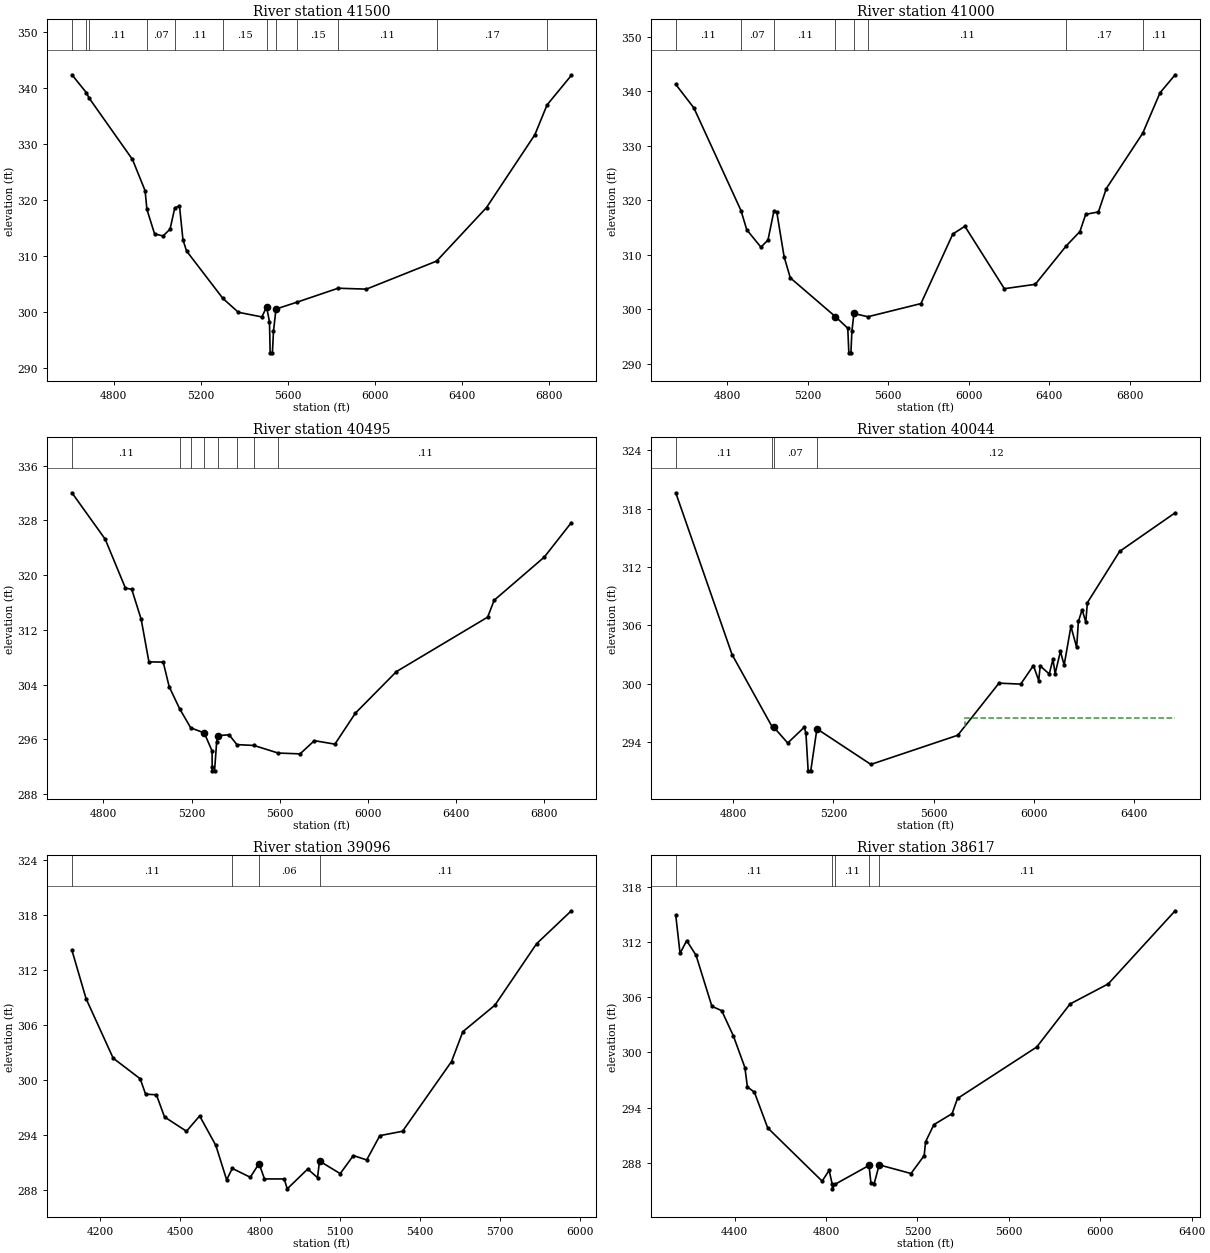
Type RM Length L Ch R = 1 ,41500   ,500,500,500
BEGIN DESCRIPTION:
MCDONALD CREEK 81.0
END DESCRIPTION:
XS GIS Cut Line= 3
      3791071.86     10230222.35      3790737.98     10230425.83
      3790014.59     10232185.87
#Sta/Elev= 30
    4609  342.39  4675.1   339.2  4687.7  338.24    4887  327.25  4945.1  321.66
  4953.3  318.33  4988.4  313.96  5027.3  313.57  5059.7  314.79  5081.4  318.61
    5103  318.94  5118.9  312.89  5135.4  310.89  5302.1  302.42  5373.3  299.93
  5481.4   299.1    5503  300.87  5516.3  298.27  5519.5  292.68  5529.8  292.68
  5534.8  296.54  5546.3  300.51    5643  301.74  5831.6  304.23  5961.5  304.07
    6284  309.08  6513.4  318.66  6735.5  331.68  6791.4     337  6902.9  342.28
#Mann= 12 ,-1 , 0
    4609     .11       0  4675.1     .17       0  4687.7     .11       0
  4953.3     .07       0  5081.4     .11       0  5302.1     .15       0
    5503     .15       0  5546.3     .11       0    5643     .15       0
  5831.6     .11       0    6284     .17       0  6791.4     .11       0
Bank Sta=5503,5546.3
XS Rating Curve= 0 ,0
Exp/Cntr=0.3,0.1

Type RM Length L Ch R = 1 ,41000   ,505,505,505
BEGIN DESCRIPTION:
MCDONALD CREEK 80.0
END DESCRIPTION:
XS GIS Cut Line= 3
       3790686.5     10229873.35      3790341.93     10230168.82
      3789946.88      10232154.6
#Sta/Elev= 30
  4546.1  341.23  4636.2  336.91    4870  318.11  4898.5   314.6  4968.8  311.42
  5003.7  312.71  5032.9  317.95  5047.4  317.87  5083.9  309.65  5114.5   305.8
  5338.8  298.68  5399.9  296.57  5405.1  292.06  5415.4  292.06  5420.3     296
  5430.5  299.27  5499.6  298.67    5763  301.08  5921.4  313.83  5981.1  315.24
    6177  303.81  6330.4  304.61  6483.8  311.63  6552.1  314.28  6580.8  317.43
  6643.9  317.87  6683.1  322.15  6863.6  332.27  6949.7  339.69  7024.7  342.99
#Mann= 8 ,-1 , 0
  4546.1     .11       0    4870     .07       0  5032.9     .11       0
  5338.8     .15       0  5430.5     .15       0  5499.6     .11       0
  6483.8     .17       0  6863.6     .11       0
Bank Sta=5338.8,5430.5
XS Rating Curve= 0 ,0
Exp/Cntr=0.3,0.1

Type RM Length L Ch R = 1 ,40495   ,451,451,451
BEGIN DESCRIPTION:
MCDONALD CREEK 77.0
END DESCRIPTION:
XS GIS Cut Line= 3
      3790071.87     10229842.13      3789847.12     10230101.51
      3788717.84     10231661.08
#Sta/Elev= 30
  4656.8  332.04  4807.8  325.26  4899.9   318.1  4928.4  317.94  4971.2  313.57
  5006.5  307.33  5071.4   307.3  5098.5  303.71  5145.9  300.49  5196.5  297.69
  5257.8  296.95  5293.4  294.32  5293.9  291.91  5294.4  291.41  5304.7  291.41
  5314.2  295.63  5320.5  296.55  5370.7  296.68  5406.2  295.24  5483.5  295.12
  5593.4  294.01  5693.2  293.89  5758.1  295.82  5851.4  295.31  5944.5  299.84
  6130.9  305.91  6545.4  313.87  6574.8  316.33  6802.9  322.65  6925.5  327.68
#Mann= 8 ,-1 , 0
  4656.8     .11       0  5145.9     .17       0  5196.5     .11       0
  5257.8     .06       0  5320.5     .11       0  5406.2     .11       0
  5483.5     .15       0  5593.4     .11       0
Bank Sta=5257.8,5320.5
XS Rating Curve= 0 ,0
Exp/Cntr=0.3,0.1

Type RM Length L Ch R = 1 ,40044   ,948,948,948
BEGIN DESCRIPTION:
MCDONALD CREEK 76.0
END DESCRIPTION:
XS GIS Cut Line= 3
      3789767.87     10229761.06      3789409.69     10229996.61
      3788524.98     10231284.88
#Sta/Elev= 30
  4571.3  319.62  4795.8  302.98  4955.6  295.55  4961.5  295.53  5017.8  293.88
  5083.5   295.5  5090.3  294.92  5099.3  291.02  5109.6  291.02  5134.3  295.34
  5349.4  291.68  5695.9  294.68  5860.3  300.04  5946.9  299.94  5997.7  301.85
  6018.7  300.31  6024.7  301.81  6060.8  300.98  6075.5  302.49  6084.3  301.02
  6105.3  303.31  6120.2   301.9  6147.2  305.88    6170  303.72    6177  306.39
  6191.9  307.59  6206.4  306.33  6212.9  308.32  6341.4  313.59  6562.8  317.56
#Mann= 4 ,-1 , 0
  4571.3     .11       0  4955.6     .17       0  4961.5     .07       0
  5134.3     .12       0
#XS Ineff= 2 , 0
       0                  5722.9       0  296.45
Permanent Ineff=
       F       F
Bank Sta=4961.5,5134.3
XS Rating Curve= 0 ,0
Exp/Cntr=0.3,0.1

Type RM Length L Ch R = 1 ,39096   ,479,479,479
BEGIN DESCRIPTION:
MCDONALD CREEK 75.0
END DESCRIPTION:
XS GIS Cut Line= 3
      3789660.42     10229675.46      3788766.92     10229527.93
      3788051.92     10230179.87
#Sta/Elev= 30
  4094.4   314.1  4147.3  308.83    4249  302.34  4350.4  300.09  4370.7  298.41
  4411.2  298.35  4441.6  295.93    4524  294.37  4573.4  296.04  4634.2  292.82
  4674.7  289.07  4695.8  290.32  4763.4  289.35  4796.3  290.85  4816.6  289.17
  4890.6  289.17    4902  288.09  4978.8  290.25  5015.6  289.31    5023  291.12
  5100.7  289.75    5150  291.72    5200  291.24  5249.3  293.89  5334.5  294.37
  5518.2  301.97  5560.8  305.23  5681.1  308.12  5837.1  314.81  5967.6  318.41
#Mann= 4 ,-1 , 0
  4094.4     .11       0  4695.8     .17       0  4796.3     .06       0
    5023     .11       0
Bank Sta=4796.3,5023
XS Rating Curve= 0 ,0
Exp/Cntr=0.3,0.1

Type RM Length L Ch R = 1 ,38617   ,478,478,478
BEGIN DESCRIPTION:
MCDONALD CREEK 74.0
END DESCRIPTION:
XS GIS Cut Line= 3
      3789764.62     10229269.22      3788925.38     10229092.72
      3787801.93     10229799.91
#Sta/Elev= 30
  4142.4  314.93  4161.2  310.79  4190.2  312.18  4231.1  310.59  4300.5  305.03
  4343.5  304.55  4394.6   301.8  4444.9  298.36  4455.9  296.24  4486.5  295.68
  4544.6  291.79  4782.9  285.99  4813.5  287.16  4827.1  285.65  4827.6  285.15
  4839.8  285.65    4988   287.7  4996.2  285.84  5010.5  285.71  5032.5  287.76
  5171.8  286.82  5229.5  288.77  5235.4  290.27  5271.9  292.14  5351.6  293.34
  5375.2  294.99  5721.7  300.59  5867.7  305.28  6034.9  307.47  6327.5  315.43
#Mann= 5 ,-1 , 0
  4142.4     .11       0  4827.1     .09       0  4839.8     .11       0
    4988     .06       0  5032.5     .11       0
Bank Sta=4988,5032.5
XS Rating Curve= 0 ,0
Exp/Cntr=0.3,0.1

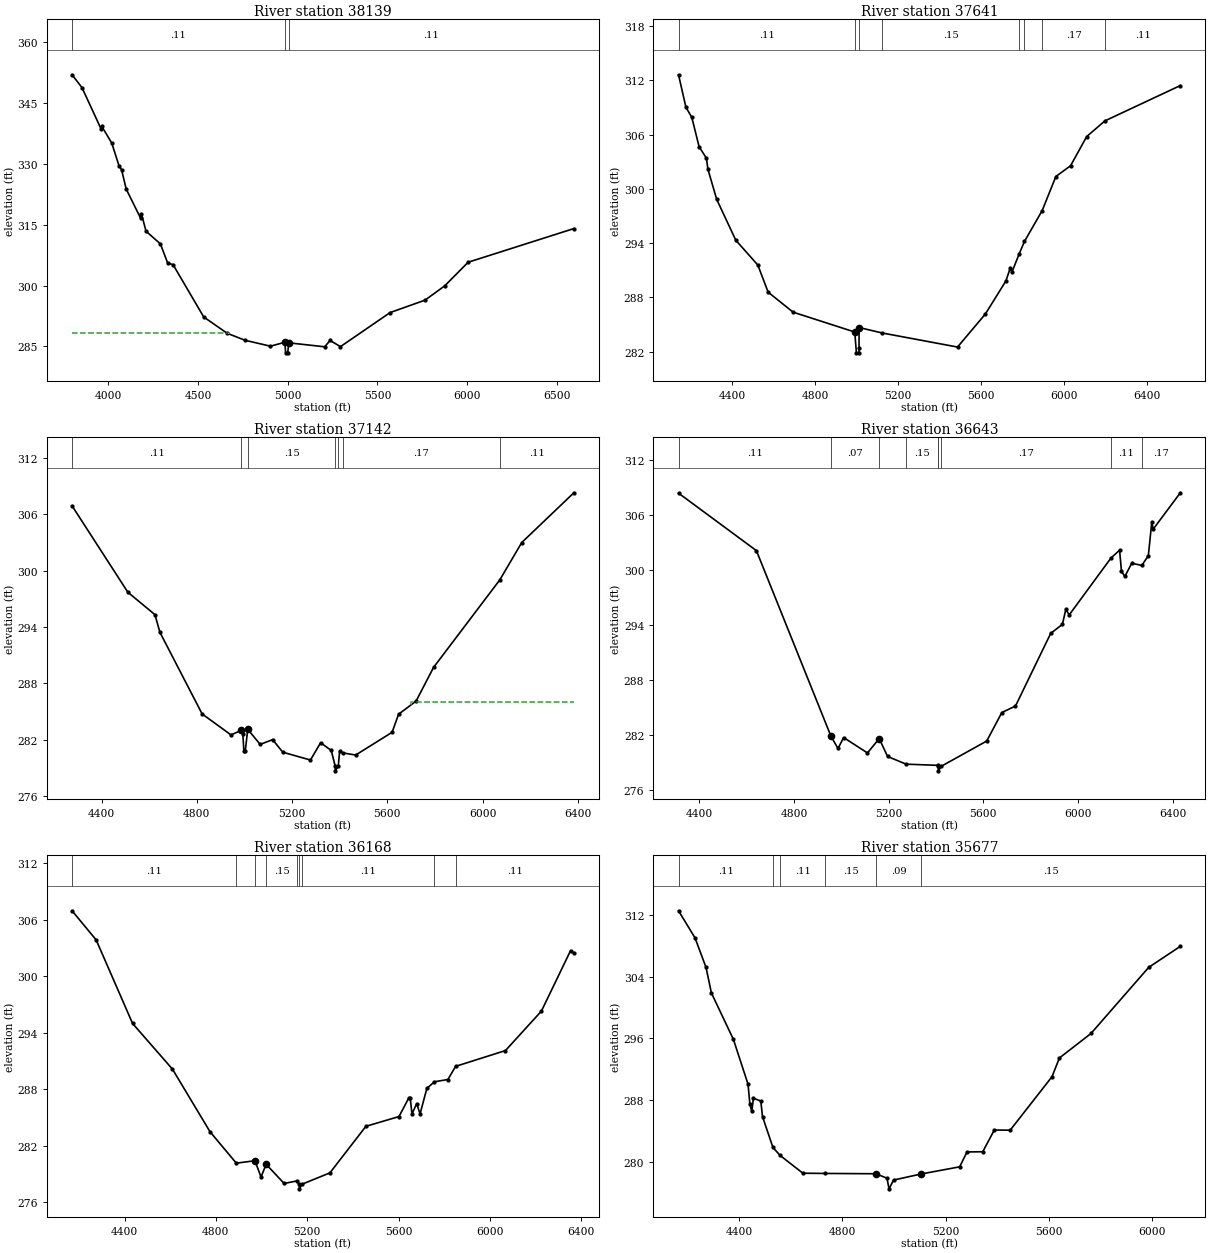
Type RM Length L Ch R = 1 ,38139   ,498,498,498
BEGIN DESCRIPTION:
MCDONALD CREEK 73.0
END DESCRIPTION:
XS GIS Cut Line= 3
       3790167.9     10228561.07      3788972.14      10228669.9
      3787623.96     10229519.21
#Sta/Elev= 30
  3799.3  351.98  3854.5  348.82  3959.9  338.71  3964.9  339.26  4020.3  335.14
  4060.4  329.58  4075.3  328.53  4100.6  323.81  4180.7  316.64  4185.7  317.67
    4211  313.42  4291.1  310.28  4331.5  305.58  4361.7  305.16  4532.4  292.26
  4662.9  288.24  4763.3  286.51  4903.9  285.06  4984.2  286.03  4988.4  283.42
  5000.2  283.42  5005.5  285.89    5206  284.91  5236.1  286.47  5293.8  284.95
  5570.4  293.35  5764.7  296.41  5874.2  299.93  6004.8  305.76  6593.4  314.06
#Mann= 3 , 0 , 0
  3799.3     .11       0  4984.2     .07       0  5005.5     .11       0
#XS Ineff= 2 , 0
       0  4672.9  288.42               0
Permanent Ineff=
       F       F
Bank Sta=4984.2,5005.5
XS Rating Curve= 0 ,0
Exp/Cntr=0.3,0.1

Type RM Length L Ch R = 1 ,37641   ,499,499,499
BEGIN DESCRIPTION:
MCDONALD CREEK 72.0
END DESCRIPTION:
XS GIS Cut Line= 3
      3789367.88     10227611.04      3788769.34     10228224.39
      3787655.24     10229316.06
#Sta/Elev= 30
    4143  312.61  4178.4  309.03  4206.7  307.91    4242  304.66  4277.4  303.38
  4284.4  302.17  4326.8  298.83  4418.9  294.31  4524.9  291.57  4574.5  288.57
  4694.6  286.36  4991.7  284.16  4999.7  281.86  5011.7  281.86  5012.2  282.36
  5012.9  284.66    5123  284.06  5486.7   282.5    5621  286.16    5720  289.82
  5741.2  291.29  5748.2  290.75    5784  292.82    5809  294.18  5894.4  297.59
  5960.4  301.36  6031.1  302.55  6108.9  305.78  6196.5  307.51  6559.8  311.42
#Mann= 8 ,-1 , 0
    4143     .11       0  4991.7     .06       0  5012.9     .11       0
    5123     .15       0    5784     .17       0    5809     .15       0
  5894.4     .17       0  6196.5     .11       0
Bank Sta=4991.7,5012.9
XS Rating Curve= 0 ,0
Exp/Cntr=0.3,0.1

Type RM Length L Ch R = 1 ,37142   ,499,499,499
BEGIN DESCRIPTION:
MCDONALD CREEK 71.0
END DESCRIPTION:
XS GIS Cut Line= 3
      3789109.23     10227333.32      3788549.01     10227791.62
      3787367.87     10228511.06
#Sta/Elev= 30
  4276.2  306.89  4510.5   297.7  4624.2  295.32    4645  293.44  4822.3  284.76
  4943.6  282.53  4986.7  283.02  4993.1  282.63  4997.5  280.86  5003.6  280.86
  5013.7  283.13    5066  281.52  5118.2  282.03  5160.9  280.69  5277.1  279.86
  5319.7   281.7  5364.3  280.88    5381  279.21  5381.5  278.71    5394  279.21
  5399.5  280.78  5412.4  280.62  5466.9  280.39  5619.9  282.81  5647.1  284.73
  5720.6  286.13  5794.2  289.72  6072.2  299.02  6164.2  302.99    6383  308.28
#Mann= 7 ,-1 , 0
  4276.2     .11       0  4986.7     .06       0  5013.7     .15       0
    5381     .09       0    5394     .15       0  5412.4     .17       0
  6072.2     .11       0
#XS Ineff= 2 , 0
       0                  5699.3       0  286.06
Permanent Ineff=
       F       F
Bank Sta=4986.7,5013.7
XS Rating Curve= 0 ,0
Exp/Cntr=0.3,0.1

Type RM Length L Ch R = 1 ,36643   ,475,475,475
BEGIN DESCRIPTION:
MCDONALD CREEK 70.0
END DESCRIPTION:
XS GIS Cut Line= 3
      3788973.79     10227109.38      3788333.94     10227363.05
      3787217.86     10228261.06
#Sta/Elev= 30
  4311.7  308.38  4640.8  302.11    4956  281.86  4985.7  280.53  5009.5  281.72
  5110.3  280.04  5159.9  281.61  5195.1  279.66  5273.3  278.82  5407.1  278.69
  5409.3  278.59  5409.8  278.09  5422.3  278.59  5614.2  281.34  5678.2  284.45
  5735.8  285.16  5884.6  293.08  5934.2  294.07  5948.6  295.71    5963   295.1
  6139.3   301.3  6175.8  302.16  6183.7  299.87  6198.1  299.29  6226.9  300.73
  6270.1   300.5  6297.3  301.56  6311.7  305.18  6318.1  304.46  6432.5  308.42
#Mann= 9 ,-1 , 0
  4311.7     .11       0    4956     .07       0  5159.9     .15       0
  5273.3     .15       0  5407.1     .17       0  5409.3     .09       0
  5422.3     .17       0  6139.3     .11       0  6270.1     .17       0
Bank Sta=4956,5159.9
XS Rating Curve= 0 ,0
Exp/Cntr=0.3,0.1

Type RM Length L Ch R = 1 ,36168   ,491,491,491
BEGIN DESCRIPTION:
MCDONALD CREEK 69.0
END DESCRIPTION:
XS GIS Cut Line= 3
      3788895.63     10226791.68      3788088.44     10226983.64
       3786973.8     10227776.04
#Sta/Elev= 30
  4170.3  306.97  4275.8  303.87  4435.3  294.98    4610  290.12  4774.5  283.46
  4889.6  280.12  4971.1  280.38  4997.7  278.65  5020.3     280  5098.9  277.96
  5154.4  278.23    5165  277.89  5165.5  277.39  5178.1  277.89  5299.5  279.09
  5456.9  284.04  5601.9  285.08  5643.8  287.01    5651  287.07  5658.6  285.36
  5679.5  286.45  5694.2  285.36  5723.8  288.07  5757.1  288.78    5816  289.02
  5849.9  290.42  6068.1   292.1  6225.6   296.3  6353.4  302.74  6367.6  302.48
#Mann= 9 ,-1 , 0
  4170.3     .11       0  4889.6     .15       0  4971.1     .09       0
  5020.3     .15       0  5154.4     .11       0    5165     .12       0
  5178.1     .11       0  5757.1     .15       0  5849.9     .11       0
Bank Sta=4971.1,5020.3
XS Rating Curve= 0 ,0
Exp/Cntr=0.3,0.1

Type RM Length L Ch R = 1 ,35677   ,494,494,494
BEGIN DESCRIPTION:
MCDONALD CREEK 68.0
END DESCRIPTION:
XS GIS Cut Line= 3
      3788467.82      10226161.1      3787851.05     10226722.19
      3786859.21     10227218.76
#Sta/Elev= 30
  4166.2  312.58    4230  309.06  4272.6  305.23  4293.5   301.9  4378.7  295.87
  4435.4  290.04  4442.2  287.53  4449.6  286.51  4456.4  288.22  4484.7  287.87
  4491.5  285.83  4531.7  281.84  4558.7  280.82  4647.6  278.49  4733.9  278.46
  4930.7  278.42  4973.3  277.84  4981.3  276.46  4998.8   277.6  5104.2  278.38
  5254.8  279.32  5283.2  281.25  5344.2  281.28  5388.9   284.1  5450.4  284.08
  5612.4  291.03    5641  293.46  5763.3  296.64  5986.8  305.23  6109.2  307.96
#Mann= 6 ,-1 , 0
  4166.2     .11       0  4531.7     .15       0  4558.7     .11       0
  4733.9     .15       0  4930.7     .09       0  5104.2     .15       0
Bank Sta=4930.7,5104.2
XS Rating Curve= 0 ,0
Exp/Cntr=0.3,0.1

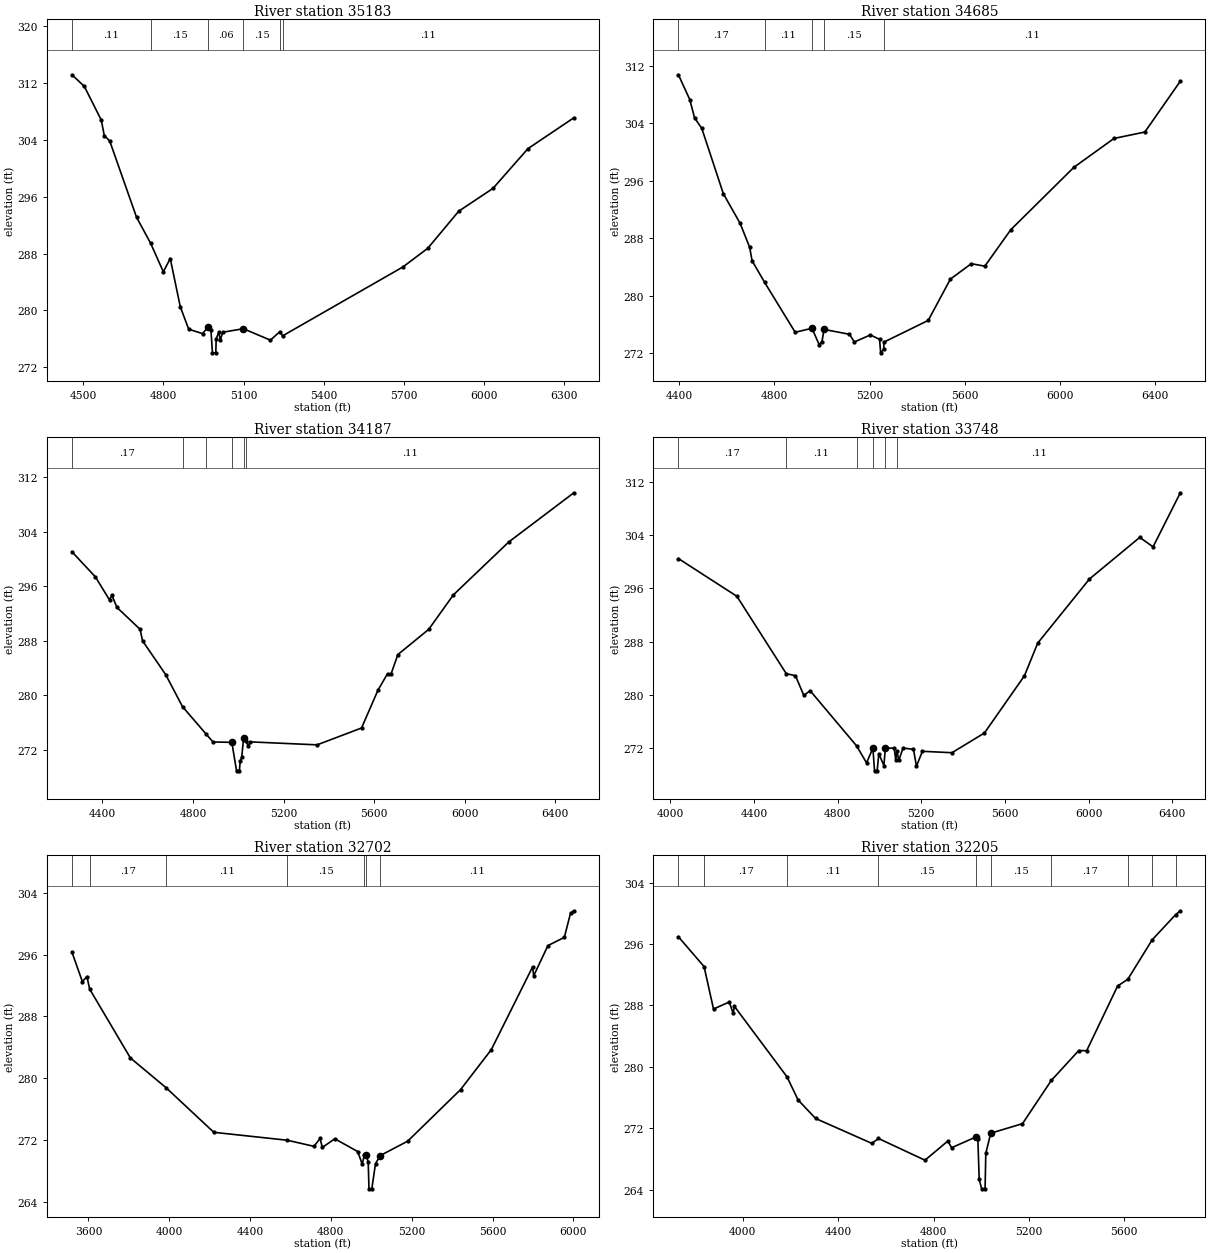
Type RM Length L Ch R = 1 ,35183   ,498,498,498
BEGIN DESCRIPTION:
MCDONALD CREEK 67.0
END DESCRIPTION:
XS GIS Cut Line= 3
      3788421.69     10226098.97      3787908.19     10226271.78
      3786817.55     10227041.67
#Sta/Elev= 30
  4458.2  313.11  4504.5  311.48  4567.8  306.75  4579.1  304.58  4599.4  303.81
  4699.8  293.09  4752.6  289.43  4799.9  285.43  4825.8   287.3  4863.2  280.54
  4894.8  277.37  4946.5  276.75  4968.7  277.74    4978  277.22  4983.6  274.05
  4996.1  274.05  4997.5  276.02    5007  276.94  5013.1  275.83  5021.8  276.94
  5099.3  277.44  5200.3  275.83  5235.4  277.02  5245.7  276.43  5696.5  286.13
  5788.8  288.74  5904.6  293.95  6032.6  297.15  6163.2  302.73    6335  307.07
#Mann= 6 ,-1 , 0
  4458.2     .11       0  4752.6     .15       0  4968.7     .06       0
  5099.3     .15       0  5235.4     .15       0  5245.7     .11       0
Bank Sta=4968.7,5099.3
XS Rating Curve= 0 ,0
Exp/Cntr=0.3,0.1

Type RM Length L Ch R = 1 ,34685   ,498,498,498
BEGIN DESCRIPTION:
MCDONALD CREEK 66.0
END DESCRIPTION:
XS GIS Cut Line= 3
      3788385.29     10225875.01      3787786.17     10225809.42
      3786366.12      10226306.7
#Sta/Elev= 30
  4397.3  310.72    4445  307.27  4465.1  304.72  4495.3  303.27  4585.9  294.17
  4656.3  290.05  4696.5   286.7  4706.6  284.84    4759  281.84  4887.6  274.88
  4958.1  275.44  4988.2  273.16    5000  273.58  5008.8  275.28  5115.5   274.6
  5135.9  273.53  5203.3  274.51  5241.9   273.9  5246.3  272.02  5259.3  272.52
    5260  273.51  5446.1  276.53  5539.2  282.28    5627  284.43  5683.7  284.08
  5792.9  289.16  6057.8  297.84  6226.2  301.86  6355.6  302.75  6504.6  309.83
#Mann= 5 ,-1 , 0
  4397.3     .17       0    4759     .11       0  4958.1     .06       0
  5008.8     .15       0  5259.3     .11       0
Bank Sta=4958.1,5008.8
XS Rating Curve= 0 ,0
Exp/Cntr=0.3,0.1

Type RM Length L Ch R = 1 ,34187   ,439,439,439
BEGIN DESCRIPTION:
MCDONALD CREEK 65.0
END DESCRIPTION:
XS GIS Cut Line= 3
       3788317.5     10225203.14      3787610.74     10225401.62
      3786364.42     10226203.13
#Sta/Elev= 30
  4265.9  301.05  4369.4  297.37  4431.7  293.99  4442.1  294.68  4464.9  292.88
  4566.8  289.68  4577.5     288  4679.7  283.04  4754.1  278.34  4857.7  274.34
  4888.7  273.16  4971.8  273.11  4992.6  268.93  5005.2  268.93  5008.8  270.37
  5015.3   270.9    5024  273.78  5033.7  273.32  5045.1  272.52  5051.1  273.18
  5348.2  272.74  5544.4  275.21    5617  280.76  5659.3  283.18  5674.5  283.11
  5704.9  285.98  5840.9  289.67  5949.9  294.73  6194.9   302.5  6481.8   309.7
#Mann= 6 ,-1 , 0
  4265.9     .17       0  4754.1     .11       0  4857.7     .15       0
  4971.8     .09       0    5024     .15       0  5033.7     .11       0
Bank Sta=4971.8,5024
XS Rating Curve= 0 ,0
Exp/Cntr=0.3,0.1

Type RM Length L Ch R = 1 ,33748   ,1046,1046,1046
BEGIN DESCRIPTION:
MCDONALD CREEK 64.0
END DESCRIPTION:
XS GIS Cut Line= 4
      3788317.49     10225130.22       3787397.9     10225120.73
      3787357.66      10225130.3      3786322.78     10226130.18
#Sta/Elev= 30
    4039  300.47  4318.7  294.81  4554.6  283.21  4598.7   282.9  4638.7  279.94
  4668.7  280.66  4890.9  272.38  4938.7  269.82    4969  272.05  4976.7  268.63
  4989.3  268.63  4997.3   271.2  5021.6  269.42  5028.6  272.07    5071  272.02
  5078.2  270.25    5084  271.63  5092.4  270.21  5113.5  272.05  5163.1  271.85
  5177.3  269.32  5205.6  271.56  5347.1  271.35  5502.4  274.31  5693.6  282.89
  5757.1  287.79  6004.6  297.41  6245.1  303.65  6308.7  302.23    6439  310.34
#Mann= 6 ,-1 , 0
    4039     .17       0  4554.6     .11       0  4890.9     .15       0
    4969     .09       0  5028.6     .15       0    5084     .11       0
Bank Sta=4969,5028.6
XS Rating Curve= 0 ,0
Exp/Cntr=0.3,0.1

Type RM Length L Ch R = 1 ,32702   ,497,497,497
BEGIN DESCRIPTION:
MCDONALD CREEK 63.0
END DESCRIPTION:
XS GIS Cut Line= 3
      3786950.56     10223541.17      3786580.67     10224975.75
      3786182.79     10225896.02
#Sta/Elev= 30
  3518.5  296.33    3570  292.51  3592.6  293.16  3606.2  291.54  3807.6  282.63
    3984  278.78  4220.6     273  4585.1  271.97  4716.3  271.18  4746.6   272.2
  4757.6  271.04  4819.6  272.16  4933.2   270.5  4955.1  268.86  4966.1  270.11
  4974.5  270.07  4984.8  269.13  4988.6  265.68  5002.6  265.68  5020.9  268.94
  5044.4  269.99  5180.1  271.85  5441.6  278.52    5594   283.7  5798.3  294.41
  5803.7  293.26  5874.2  297.17  5955.6  298.24  5986.3  301.39  6002.6  301.68
#Mann= 7 ,-1 , 0
  3518.5     .11       0  3606.2     .17       0    3984     .11       0
  4585.1     .15       0  4966.1     .11       0  4974.5     .06       0
  5044.4     .11       0
Bank Sta=4974.5,5044.4
XS Rating Curve= 0 ,0
Exp/Cntr=0.3,0.1

Type RM Length L Ch R = 1 ,32205   ,500,500,500
BEGIN DESCRIPTION:
MCDONALD CREEK 62.0
END DESCRIPTION:
XS GIS Cut Line= 3
      3786892.85     10223527.84      3786296.63     10224649.41
      3785481.94     10224832.89
#Sta/Elev= 30
  3729.8  296.94  3837.4  293.06    3877  287.53  3942.9  288.44  3959.2  286.99
  3964.9  287.87  4185.1   278.7  4231.8  275.68  4305.2  273.27  4541.3  270.02
    4569  270.66  4764.1  267.83  4859.6  270.32  4875.9  269.46  4979.2  270.88
  4985.8  270.63  4991.5  265.33  5001.9   264.1  5016.1   264.1  5019.2  268.72
  5039.8  271.35    5173  272.59  5294.4  278.24  5408.8  282.11  5442.3   282.1
  5572.1  290.53  5614.8   291.4  5716.9  296.54  5814.9  299.81  5835.1  300.33
#Mann= 10 ,-1 , 0
  3729.8     .11       0  3837.4     .17       0  4185.1     .11       0
    4569     .15       0  4979.2     .09       0  5039.8     .15       0
  5294.4     .17       0  5614.8     .11       0  5716.9     .17       0
  5814.9     .11       0
Bank Sta=4979.2,5039.8
XS Rating Curve= 0 ,0
Exp/Cntr=0.3,0.1

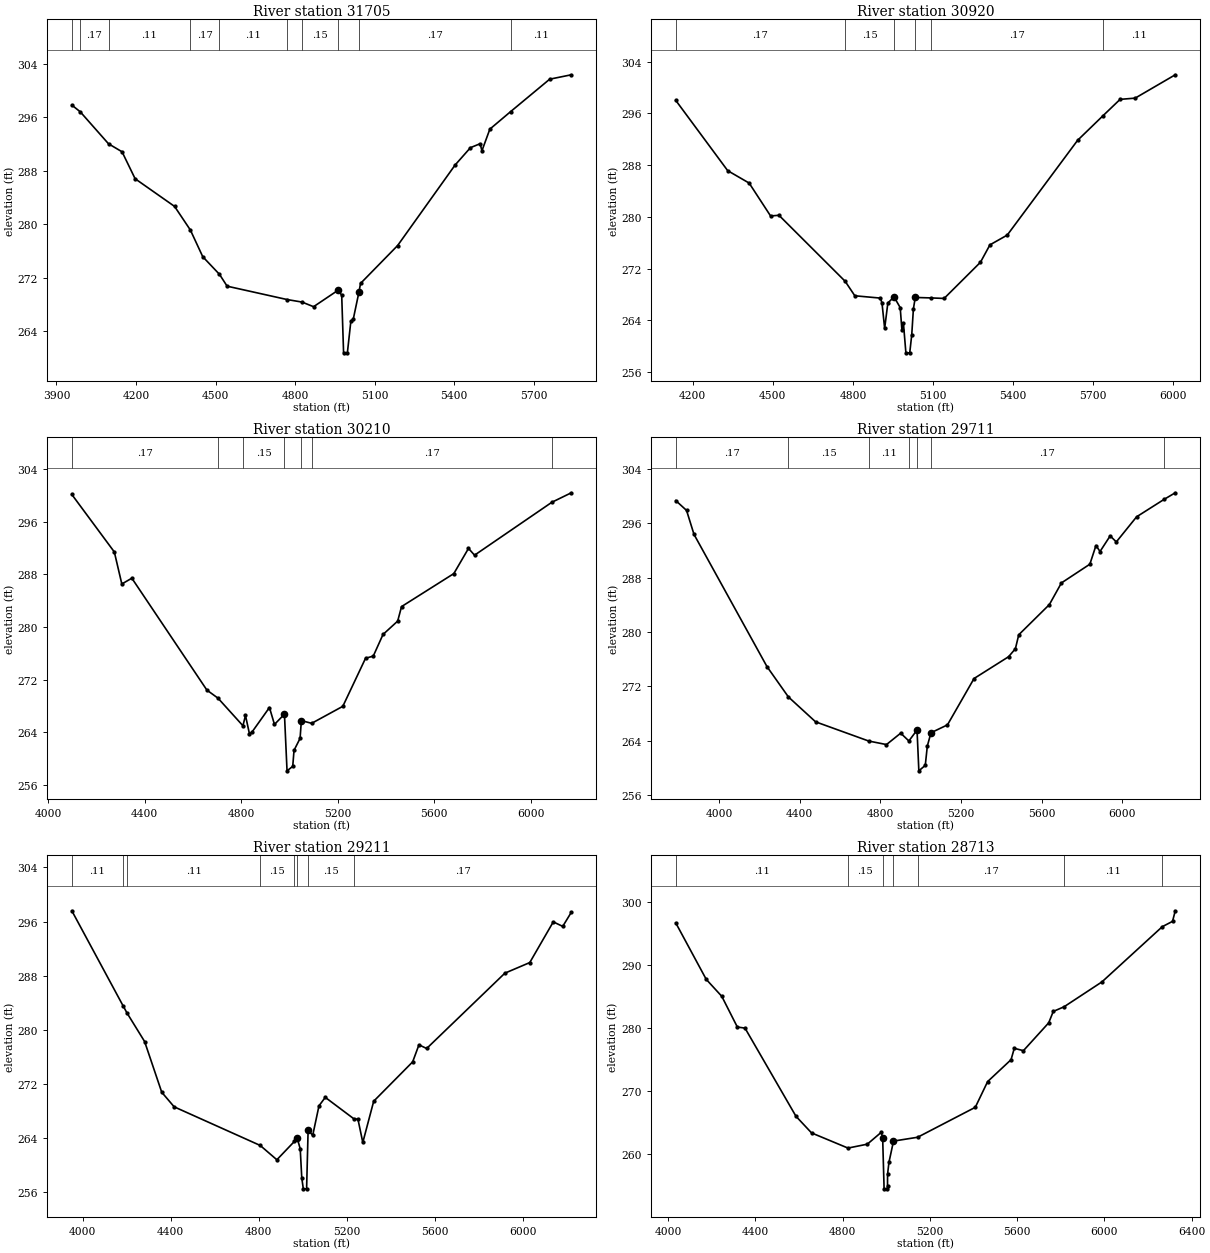
Type RM Length L Ch R = 1 ,31705   ,785,785,785
BEGIN DESCRIPTION:
MCDONALD CREEK 61.0
END DESCRIPTION:
XS GIS Cut Line= 3
      3786821.82     10223487.89      3786126.49     10224263.82
      3785411.46     10224707.89
#Sta/Elev= 30
  3958.1  297.85  3989.9  296.84  4096.4  292.06  4147.5  290.86  4196.8  286.83
  4345.6  282.69  4405.1  279.16  4451.8  275.17  4514.9  272.53  4543.7  270.76
    4770  268.76  4826.5  268.38  4869.7  267.69  4961.6  270.14  4975.8  269.42
  4982.9  260.79  4997.2  260.79  5010.2  265.48  5019.6  265.86  5040.9  269.89
  5046.8  271.17  5186.7  276.84  5403.4  288.88  5461.3  291.48  5497.9  292.07
  5504.6  291.01  5534.5  294.25  5613.1  296.88  5760.1  301.72  5841.7  302.38
#Mann= 10 ,-1 , 0
  3958.1     .11       0  3989.9     .17       0  4096.4     .11       0
  4405.1     .17       0  4514.9     .11       0    4770     .17       0
  4826.5     .15       0  4961.6     .09       0  5040.9     .17       0
  5613.1     .11       0
Bank Sta=4961.6,5040.9
XS Rating Curve= 0 ,0
Exp/Cntr=0.3,0.1

Type RM Length L Ch R = 1 ,30920   ,710,710,710
BEGIN DESCRIPTION:
MCDONALD CREEK 60.0
END DESCRIPTION:
XS GIS Cut Line= 3
       3786684.2      10223310.3      3785937.86     10223744.19
      3785344.05     10224556.98
#Sta/Elev= 30
  4136.7  298.02  4331.1  287.16  4411.4  285.24  4491.6  280.16  4523.1  280.26
  4770.8  270.06    4807  267.82    4903  267.46  4908.8  266.67  4918.7  262.77
  4930.6  266.69  4953.7  267.66  4976.9  265.99  4983.3  262.51    4989  263.56
  4998.2     259  5012.6     259  5020.1  261.79  5026.3   265.8  5033.3  267.56
  5091.3  267.49  5141.3  267.41  5277.3     273  5312.8  275.69  5377.6   277.2
    5641  291.85  5736.8  295.68  5800.1  298.18  5856.5  298.37  6006.6  301.98
#Mann= 6 ,-1 , 0
  4136.7     .17       0  4770.8     .15       0  4953.7     .09       0
  5033.3     .15       0  5091.3     .17       0  5736.8     .11       0
Bank Sta=4953.7,5033.3
XS Rating Curve= 0 ,0
Exp/Cntr=0.3,0.1

Type RM Length L Ch R = 1 ,30210   ,499,499,499
BEGIN DESCRIPTION:
MCDONALD CREEK 58.0
END DESCRIPTION:
XS GIS Cut Line= 3
       3786537.7       10223075.      3785668.42     10223314.63
       3785263.5     10224411.37
#Sta/Elev= 30
  4098.3   300.1  4274.5  291.38  4305.6  286.52  4347.1   287.4  4658.3  270.42
  4704.2   269.2  4807.7  265.01  4818.2  266.57  4834.6   263.8    4845  264.04
  4917.6  267.78  4938.4  265.21  4979.8  266.77  4990.5  258.17  5014.1  258.85
  5019.5  261.28  5044.6   263.1  5049.9  265.79  5092.6  265.38  5221.8  267.96
    5316  275.25    5348  275.58  5388.4  278.86  5449.2  280.89  5465.2  283.09
    5682   288.1  5742.8  291.92  5767.9  290.89  6088.4  298.92  6169.1  300.36
#Mann= 7 ,-1 , 0
  4098.3     .17       0  4704.2     .11       0  4807.7     .15       0
  4979.8     .09       0  5049.9     .15       0  5092.6     .17       0
  6088.4     .11       0
Bank Sta=4979.8,5049.9
XS Rating Curve= 0 ,0
Exp/Cntr=0.3,0.1

Type RM Length L Ch R = 1 ,29711   ,500,500,500
BEGIN DESCRIPTION:
MCDONALD CREEK 57.0
END DESCRIPTION:
XS GIS Cut Line= 3
      3786517.82     10222961.07      3785309.39     10223078.22
      3785156.97     10224331.38
#Sta/Elev= 30
  3785.9  299.37  3839.4  297.92  3876.3  294.39    4238  274.92  4344.2  270.45
  4479.1  266.78  4742.5  263.95  4830.7  263.43  4901.1  265.11  4941.6  263.96
  4982.1  265.57  4991.1  259.56    5023  260.37  5033.1  263.21  5051.2  265.17
  5132.9  266.33  5264.8  273.16    5436  276.37  5469.8  277.55  5486.4   279.6
  5638.2  284.05    5698  287.24    5839     290  5869.2  292.75  5889.4  291.87
  5939.7  294.17  5970.1  293.28  6070.7  296.98  6206.6  299.54  6262.4  300.52
#Mann= 7 ,-1 , 0
  3785.9     .17       0  4344.2     .15       0  4742.5     .11       0
  4941.6     .17       0  4982.1     .09       0  5051.2     .17       0
  6206.6     .11       0
Bank Sta=4982.1,5051.2
XS Rating Curve= 0 ,0
Exp/Cntr=0.3,0.1

Type RM Length L Ch R = 1 ,29211   ,498,498,498
BEGIN DESCRIPTION:
MCDONALD CREEK 56.0
END DESCRIPTION:
XS GIS Cut Line= 3
       3785898.4     10221973.96      3785158.08     10222717.57
      3784221.57     10223500.07
#Sta/Elev= 30
  3950.7  297.59  4183.6  283.53  4201.8  282.45  4281.4  278.25  4359.2  270.75
  4415.7  268.59  4806.6  262.88  4882.4  260.76  4962.2  263.48  4974.4     264
  4988.5  262.39  4995.6  258.06  5002.6  256.46  5017.5  256.46  5024.4  265.18
  5045.2  264.36  5073.8  268.74  5102.4  269.99  5232.6  266.81  5250.8  266.76
  5272.9  263.32  5322.4  269.42  5499.4  275.24    5528  277.76  5563.1  277.22
  5918.4  288.36  6031.6  289.93  6138.4  295.95  6181.3  295.28  6220.4  297.37
#Mann= 8 ,-1 , 0
  3950.7     .11       0  4183.6     .17       0  4201.8     .11       0
  4806.6     .15       0  4962.2     .11       0  4974.4     .07       0
  5024.4     .15       0  5232.6     .17       0
#XS Ineff= 2 , 0
       0                  5102.4       0  269.99
Permanent Ineff=
       F       F
Bank Sta=4974.4,5024.4
XS Rating Curve= 0 ,0
Exp/Cntr=0.3,0.1

Type RM Length L Ch R = 1 ,28713   ,498,498,498
BEGIN DESCRIPTION:
MCDONALD CREEK 55.0
END DESCRIPTION:
XS GIS Cut Line= 3
      3785569.82     10221645.49      3784940.06     10222376.27
      3784180.23     10223461.28
#Sta/Elev= 30
  4035.3  296.75  4174.9  287.78  4246.2  285.08  4317.5   280.2  4352.6  280.03
  4586.3  266.01  4657.6  263.37  4824.6  260.96  4913.2  261.58  4976.9  263.46
  4983.5  262.63  4990.1  254.48  5005.3  254.48  5005.8  254.98    5006  256.79
  5012.3  258.68  5033.2  262.07  5143.8  262.68  5408.1  267.44  5464.7  271.53
    5572  275.01  5586.8  276.82  5628.6  276.44  5744.6  280.87  5765.5  282.68
    5815  283.42  5988.7  287.38  6265.1  296.15  6312.1     297  6324.6  298.68
#Mann= 7 ,-1 , 0
  4035.3     .11       0  4824.6     .15       0  4983.5     .09       0
  5033.2     .15       0  5143.8     .17       0    5815     .11       0
  6265.1     .17       0
Bank Sta=4983.5,5033.2
XS Rating Curve= 0 ,0
Exp/Cntr=0.3,0.1