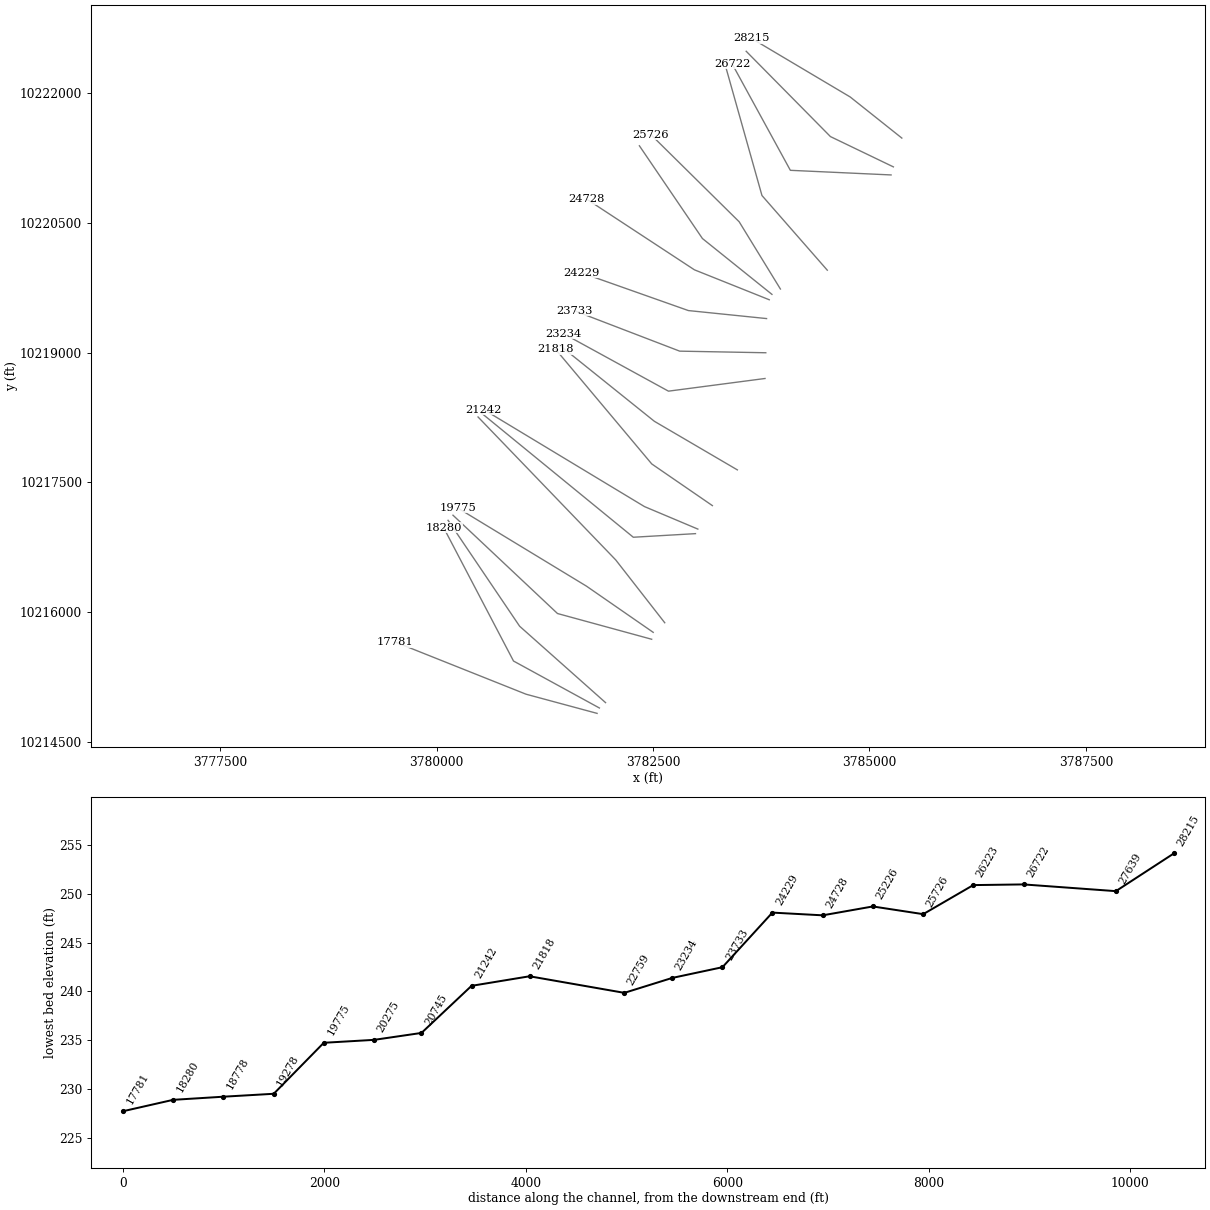
HEC-RAS study MCDONALD CREEK.prj: MCDONALD CREEK Base Level Engineering

--- MCDONALD CREEK.g01 (geometry) --- (continued)

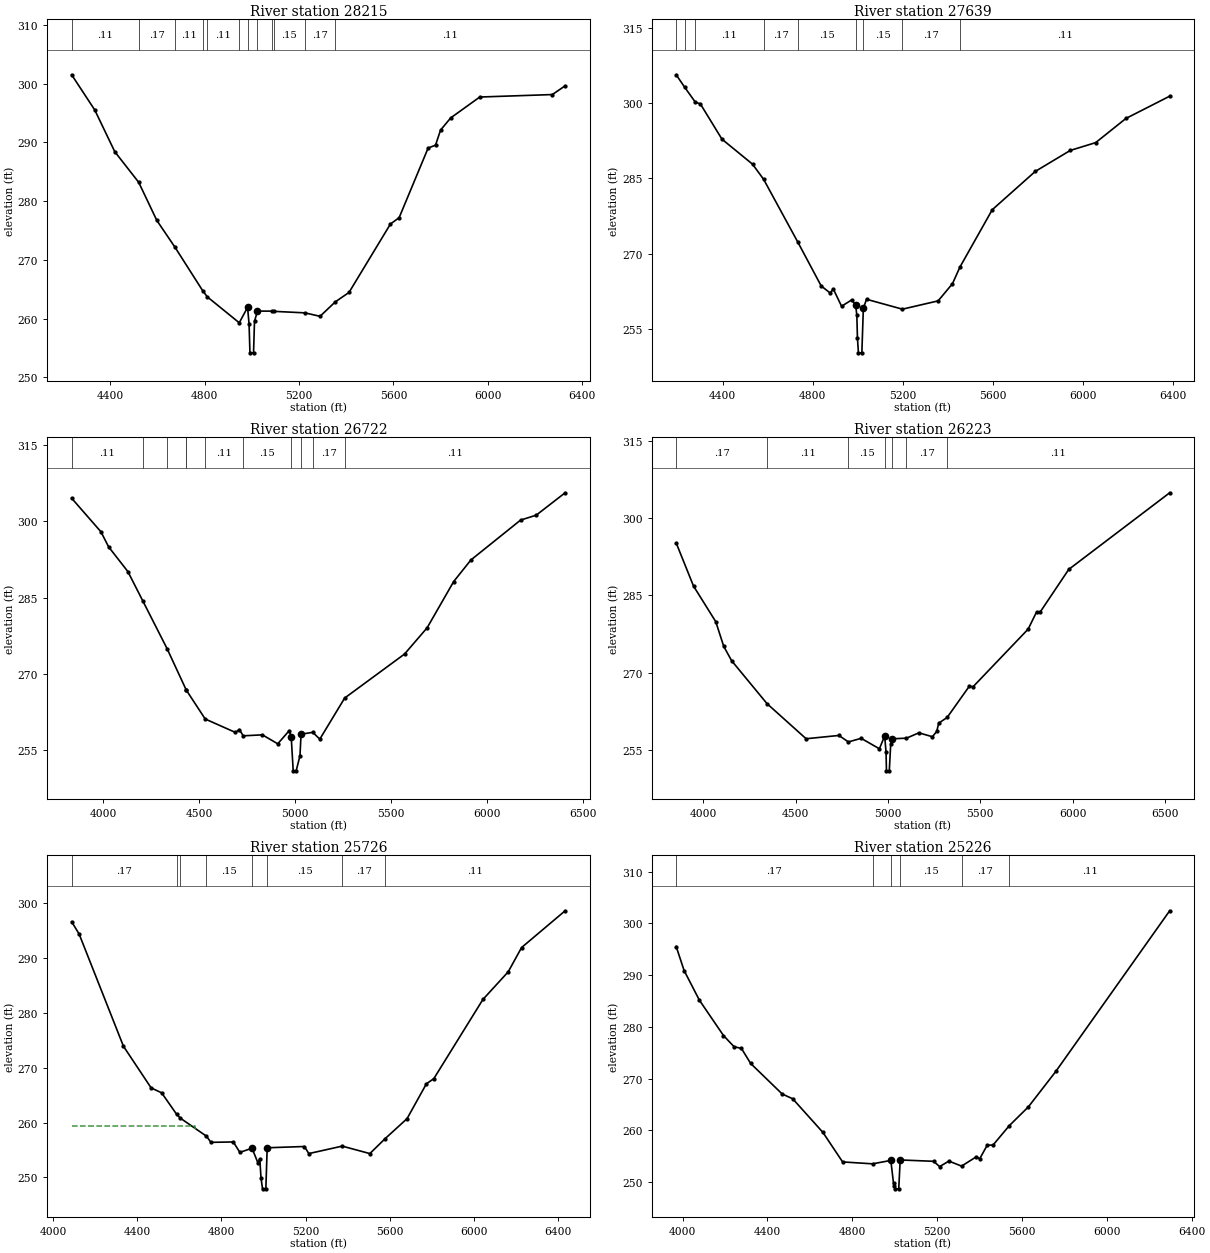
Type RM Length L Ch R = 1 ,28215   ,576,576,576
BEGIN DESCRIPTION:
MCDONALD CREEK 54.0
END DESCRIPTION:
XS GIS Cut Line= 3
      3785374.49      10221481.2      3784777.76     10221956.36
      3783637.04     10222634.17
#Sta/Elev= 30
  4237.2  301.53  4335.1  295.53  4419.9  288.42    4521  283.22  4597.7  276.73
  4674.6  272.16    4792  264.75  4811.6   263.7  4946.9  259.28  4982.1  261.91
  4988.5  259.06  4992.2  254.16  5007.4  254.16  5011.5  259.53    5024  261.27
  5085.3  261.27  5093.1  261.23  5225.4  260.97    5289  260.38  5353.8  262.85
  5411.7  264.45    5587   276.1    5624  277.19  5746.7  289.05    5778  289.54
  5799.4  292.11  5842.2  294.18  5965.4  297.74  6272.7  298.16  6326.9  299.65
#Mann= 12 ,-1 , 0
  4237.2     .11       0    4521     .17       0  4674.6     .11       0
    4792     .15       0  4811.6     .11       0  4946.9     .15       0
  4982.1     .09       0    5024     .15       0  5085.3     .11       0
  5093.1     .15       0  5225.4     .17       0  5353.8     .11       0
Bank Sta=4982.1,5024
XS Rating Curve= 0 ,0
Exp/Cntr=0.3,0.1

Type RM Length L Ch R = 1 ,27639   ,917,917,917
BEGIN DESCRIPTION:
MCDONALD CREEK 53.0
END DESCRIPTION:
XS GIS Cut Line= 3
      3785276.84     10221148.22      3784549.76     10221498.36
      3783576.46     10222484.55
#Sta/Elev= 30
    4193  305.63  4230.2  303.18  4278.1  300.17  4300.3  299.84  4396.4  292.81
  4532.1  287.84  4581.2  284.84  4732.6  272.39  4837.3   263.6    4877   262.2
  4891.1  262.99  4927.8  259.56    4973  260.83  4990.1  259.79  4995.6  257.77
  4998.3  253.24  5002.7  250.29  5017.9  250.29  5024.5  259.14  5038.6  260.95
    5198  258.98  5356.8  260.63  5420.5  264.05  5453.9  267.38  5597.2  278.77
  5788.2  286.39  5943.8  290.57  6056.9  292.13  6191.2  296.94  6385.6  301.37
#Mann= 9 ,-1 , 0
    4193     .11       0  4230.2     .17       0  4278.1     .11       0
  4581.2     .17       0  4732.6     .15       0  4990.1     .09       0
  5024.5     .15       0    5198     .17       0  5453.9     .11       0
Bank Sta=4990.1,5024.5
XS Rating Curve= 0 ,0
Exp/Cntr=0.3,0.1

Type RM Length L Ch R = 1 ,26722   ,499,499,499
BEGIN DESCRIPTION:
MCDONALD CREEK 51.0
END DESCRIPTION:
XS GIS Cut Line= 3
      3785250.21     10221054.99      3784086.64     10221108.44
      3783412.54     10222341.85
#Sta/Elev= 30
  3835.2  304.53  3987.7  297.94  4027.8  294.97  4127.9  290.13  4206.2  284.33
  4332.9  274.93  4431.9  266.87  4432.1  266.85  4530.9  261.16  4688.5  258.52
  4708.5   259.1  4728.9  257.86  4828.6  258.05  4908.7  256.29  4968.8  258.89
  4978.8  257.67  4989.2  250.98  5004.6  250.98  5024.4  253.95  5030.1  258.18
  5090.9  258.54  5127.8  257.21  5257.3  265.28    5569  273.92  5686.8  279.08
  5825.2  288.17  5914.7   292.4  6173.3  300.23  6254.9   301.2  6405.6   305.6
#Mann= 11 ,-1 , 0
  3835.2     .11       0  4206.2     .17       0  4332.9     .15       0
  4431.9     .11       0  4432.1     .15       0  4530.9     .11       0
  4728.9     .15       0  4978.8     .09       0  5030.1     .15       0
  5090.9     .17       0  5257.3     .11       0
Bank Sta=4978.8,5030.1
XS Rating Curve= 0 ,0
Exp/Cntr=0.3,0.1

Type RM Length L Ch R = 1 ,26223   ,497,497,497
BEGIN DESCRIPTION:
MCDONALD CREEK 50.0
END DESCRIPTION:
XS GIS Cut Line= 3
      3784513.26     10219953.93      3783758.63     10220816.93
      3783345.62     10222284.73
#Sta/Elev= 30
  3853.6  295.21  3947.4  286.83  4067.9   279.9  4110.7  275.13  4153.4  272.33
  4345.3  263.97  4556.8  257.15  4734.3  257.79  4785.7  256.53  4854.8  257.23
  4953.5   255.2    4982   257.7  4989.6   254.5  4991.7  250.91  5007.1  250.91
  5014.7  256.06  5020.6  257.14  5100.1  257.26  5167.2   258.3  5240.4  257.54
    5264  258.59  5274.4  260.17  5320.5   261.3  5440.6  267.38  5460.3  267.25
  5758.6  278.46  5804.2  281.79    5825  281.85  5978.4  290.07  6524.8  304.97
#Mann= 7 ,-1 , 0
  3853.6     .17       0  4345.3     .11       0  4785.7     .15       0
    4982     .09       0  5020.6     .15       0  5100.1     .17       0
  5320.5     .11       0
Bank Sta=4982,5020.6
XS Rating Curve= 0 ,0
Exp/Cntr=0.3,0.1

Type RM Length L Ch R = 1 ,25726   ,500,500,500
BEGIN DESCRIPTION:
MCDONALD CREEK 49.0
END DESCRIPTION:
XS GIS Cut Line= 3
      3783971.61      10219736.4      3783495.31     10220513.55
      3782475.42     10221521.18
#Sta/Elev= 30
  4088.5  296.64  4123.9  294.41  4334.7  273.93  4466.2  266.34  4516.2  265.44
  4587.5  261.52  4605.1  260.82  4729.2  257.53  4750.4  256.41  4856.9  256.48
  4887.8  254.58  4945.8  255.34  4973.6  252.67  4982.5  253.43  4988.4   249.9
  4995.7  247.93  5011.4  247.93  5017.7  255.42  5194.4  255.65  5215.7  254.36
  5374.3  255.72  5505.6  254.36  5577.3  257.05  5682.4  260.73  5774.3  267.08
  5809.7  268.03    6043  282.47  6163.2  287.51  6226.8  291.94  6433.7  298.64
#Mann= 8 ,-1 , 0
  4088.5     .17       0  4587.5     .11       0  4605.1     .17       0
  4729.2     .15       0  4945.8     .09       0  5017.7     .15       0
  5374.3     .17       0  5577.3     .11       0
#XS Ineff= 2 , 0
       0    4677   259.3               0
Permanent Ineff=
       F       F
Bank Sta=4945.8,5017.7
XS Rating Curve= 0 ,0
Exp/Cntr=0.3,0.1

Type RM Length L Ch R = 1 ,25226   ,498,498,498
BEGIN DESCRIPTION:
MCDONALD CREEK 48.0
END DESCRIPTION:
XS GIS Cut Line= 3
      3783873.91     10219674.28      3783070.91     10220319.82
      3782342.58     10221391.92
#Sta/Elev= 30
  3969.7  295.53    4007  290.89    4079  285.17  4192.6  278.34  4242.2  276.19
  4277.4  275.84  4320.6  272.95  4469.4  267.04    4519  266.12  4661.4  259.62
  4754.2  253.92  4895.7  253.55  4981.4  254.21  4995.8  249.25  4998.8  249.77
  5003.1  248.72  5018.8  248.72  5025.7   254.3  5182.9  254.04  5211.6  253.02
  5255.4  254.08    5315  253.11  5385.2  254.93  5400.1  254.49  5436.1  257.17
  5463.1  257.17  5540.1  260.93  5630.2  264.57  5759.4  271.41  6296.1  302.44
#Mann= 6 ,-1 , 0
  3969.7     .17       0  4895.7     .15       0  4981.4     .09       0
  5025.7     .15       0    5315     .17       0  5540.1     .11       0
Bank Sta=4981.4,5025.7
XS Rating Curve= 0 ,0
Exp/Cntr=0.3,0.1

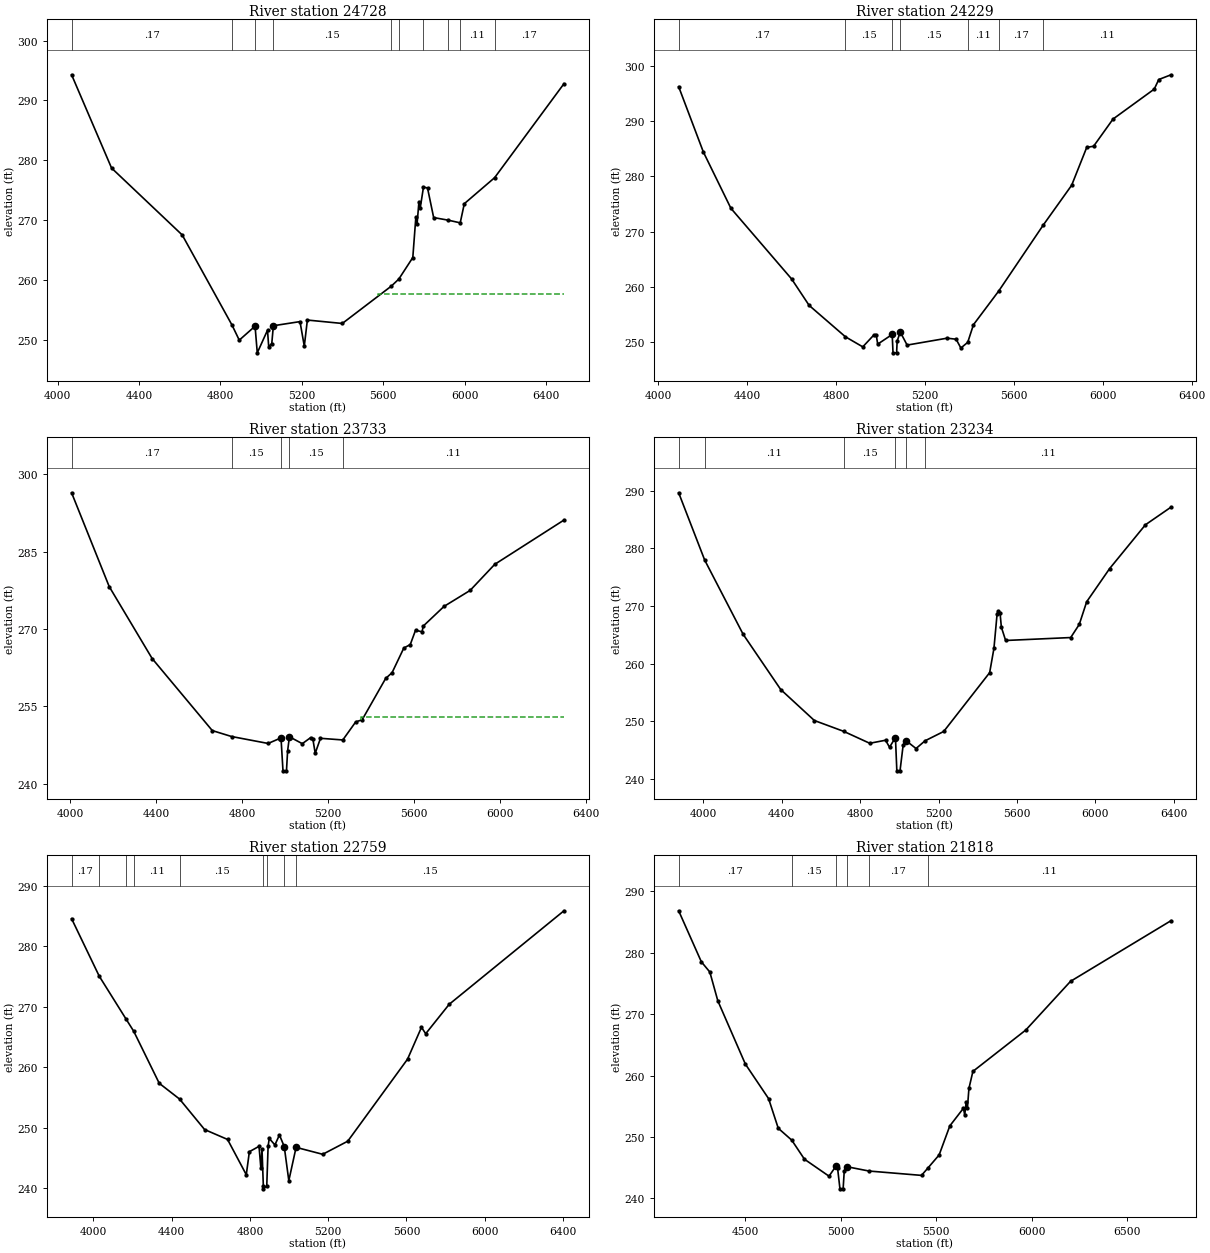
Type RM Length L Ch R = 1 ,24728   ,499,499,499
BEGIN DESCRIPTION:
MCDONALD CREEK 47.0
END DESCRIPTION:
XS GIS Cut Line= 3
      3783842.86     10219612.11        3782978.     10219958.37
      3781734.05     10220775.28
#Sta/Elev= 30
  4068.4  294.29  4264.8   278.7  4612.1  267.51  4857.1  252.43  4892.4  249.93
  4970.1  252.27  4980.9  247.81  5031.2  251.59  5037.1  248.84  5052.2  249.37
    5060  252.34  5190.9  253.03    5212  248.93  5227.1  253.29  5398.8  252.72
    5640  258.97  5676.5  260.14  5745.3  263.74  5760.4  270.56  5766.4  269.41
  5775.5  273.09  5781.5  271.95  5797.7  275.51  5817.6  275.37  5847.8  270.42
  5918.8  269.99  5978.3  269.54  5998.4  272.74  6147.4  277.09  6488.2   292.8
#Mann= 10 ,-1 , 0
  4068.4     .17       0  4857.1     .15       0  4970.1     .09       0
    5060     .15       0    5640     .11       0  5676.5     .17       0
  5797.7     .11       0  5918.8     .17       0  5978.3     .11       0
  6147.4     .17       0
#XS Ineff= 2 , 0
       0                  5573.6       0  257.72
Permanent Ineff=
       F       F
Bank Sta=4970.1,5060
XS Rating Curve= 0 ,0
Exp/Cntr=0.3,0.1

Type RM Length L Ch R = 1 ,24229   ,496,496,496
BEGIN DESCRIPTION:
MCDONALD CREEK 46.0
END DESCRIPTION:
XS GIS Cut Line= 3
      3783811.76     10219394.58      3782908.49     10219487.17
      3781676.36     10219922.88
#Sta/Elev= 30
    4092  296.18  4203.1  284.38  4327.1   274.2  4600.3  261.43    4679  256.66
  4842.2  250.99  4920.2  249.17  4970.5  251.33  4980.5  251.38  4987.4  249.66
  5052.6  251.41  5056.3  248.09  5072.4  248.09  5074.9  250.21  5088.8  251.86
  5119.7  249.49  5299.8  250.74  5340.1  250.55  5361.6  248.96  5392.4  249.99
  5418.1  253.17  5531.8  259.26    5732  271.17  5859.8  278.36  5927.7  285.21
  5958.6  285.42    6046  290.33  6231.4  295.74  6251.7  297.47  6306.9  298.33
#Mann= 7 ,-1 , 0
    4092     .17       0  4842.2     .15       0  5052.6     .09       0
  5088.8     .15       0  5392.4     .11       0  5531.8     .17       0
    5732     .11       0
Bank Sta=5052.6,5088.8
XS Rating Curve= 0 ,0
Exp/Cntr=0.3,0.1

Type RM Length L Ch R = 1 ,23733   ,499,499,499
BEGIN DESCRIPTION:
MCDONALD CREEK 45.0
END DESCRIPTION:
XS GIS Cut Line= 3
      3783802.87     10218999.46      3782808.25     10219018.03
      3781596.42     10219483.37
#Sta/Elev= 30
  4005.2  296.42  4180.3  278.23  4380.3  264.27  4660.3   250.3  4749.9  249.15
  4920.4   247.8  4980.4  248.88  4989.6  242.49  5005.8  242.49  5011.1  246.32
  5019.5   249.1  5079.5  247.76  5118.3  248.93  5128.8  248.64  5139.7   245.9
  5164.2   248.8  5268.2  248.48  5328.2  251.98  5358.2  252.39  5467.6   260.4
  5497.6  261.53  5552.3  266.31  5582.3  266.98  5606.9  269.76    5637  269.46
  5643.1  270.58  5739.5  274.38    5861  277.48  5975.7  282.54  6298.1  291.13
#Mann= 5 ,-1 , 0
  4005.2     .17       0  4749.9     .15       0  4980.4     .09       0
  5019.5     .15       0  5268.2     .11       0
#XS Ineff= 2 , 0
       0                  5352.9       0  252.85
Permanent Ineff=
       F       F
Bank Sta=4980.4,5019.5
XS Rating Curve= 0 ,0
Exp/Cntr=0.3,0.1

Type RM Length L Ch R = 1 ,23234   ,475,475,475
BEGIN DESCRIPTION:
MCDONALD CREEK 44.0
END DESCRIPTION:
XS GIS Cut Line= 3
      3783793.97       10218702.      3782678.35     10218555.49
      3781463.26     10219221.41
#Sta/Elev= 30
  3874.8  289.62  4007.5  277.95  4203.7  265.07  4395.4  255.49  4566.8  250.12
  4716.3  248.24  4849.2  246.17  4929.9   246.7  4950.1  245.48  4980.3  247.16
  4987.4  241.39  5003.6  241.39  5019.8   245.9  5034.8  246.61  5085.3  245.26
  5131.2   246.6  5226.5  248.22  5460.7  258.42  5482.5  262.62  5498.6  268.58
  5504.3  269.09  5513.7  268.81  5520.4  266.31  5542.2     264    5874  264.51
  5917.6  266.78  5955.5  270.72  6072.5  276.47  6255.1  284.07  6385.6  287.13
#Mann= 6 ,-1 , 0
  3874.8     .17       0  4007.5     .11       0  4716.3     .15       0
  4980.3     .09       0  5034.8     .15       0  5131.2     .11       0
Bank Sta=4980.3,5034.8
XS Rating Curve= 0 ,0
Exp/Cntr=0.3,0.1

Type RM Length L Ch R = 1 ,22759   ,941,941,941
BEGIN DESCRIPTION:
MCDONALD CREEK 42.0
END DESCRIPTION:
XS GIS Cut Line= 3
      3783474.34     10217645.39      3782515.66     10218207.07
      3781420.19     10219087.15
#Sta/Elev= 30
  3888.9   284.6  4030.3  275.07  4165.8  268.05  4206.5  265.95  4336.8  257.34
  4440.6  254.73  4568.6  249.68  4685.9  248.04  4781.7   242.2  4797.4  246.01
  4846.8   246.9  4856.1  243.32  4861.9   246.5  4868.8  240.36  4869.3  239.86
  4886.3  240.36  4893.2  246.92    4899  248.21  4927.9  247.13  4951.1  248.78
 4975.59  246.87    4999  241.22  5036.2  246.73  5172.2  245.58  5300.2  247.75
  5605.8  261.34    5677  266.61  5698.6  265.55  5818.6  270.42  6405.2  285.91
#Mann= 9 ,-1 , 0
  3888.9     .17       0  4030.3     .11       0  4165.8     .17       0
  4206.5     .11       0  4440.6     .15       0  4868.8     .09       0
  4886.3     .15       0 4975.59     .09       0  5036.2     .15       0
Bank Sta=4975.59,5036.2
XS Rating Curve= 0 ,0
Exp/Cntr=0.3,0.1

Type RM Length L Ch R = 1 ,21818   ,576,576,576
BEGIN DESCRIPTION:
MCDONALD CREEK 41.0
END DESCRIPTION:
XS GIS Cut Line= 3
      3783185.82     10217232.47      3782485.46     10217714.12
      3781374.42     10219039.42
#Sta/Elev= 30
    4150  286.83  4268.9  278.52  4313.3  276.86  4355.2  272.17  4499.5  261.87
  4621.1  256.25  4671.8  251.42  4742.4  249.49  4809.1  246.38  4937.7  243.62
  4973.5  245.23  4982.3  245.01    4995  241.56  5011.6  241.56  5017.6  244.52
  5031.9  245.16  5146.6  244.46  5422.2  243.75  5455.8  244.95  5514.6  247.08
  5570.6  251.81  5642.1  254.69  5648.6  253.56  5656.4  255.75  5662.9  254.77
  5670.7  257.91  5691.5  260.68  5968.7  267.42  6202.8  275.34  6729.4  285.22
#Mann= 6 ,-1 , 0
    4150     .17       0  4742.4     .15       0  4973.5     .09       0
  5031.9     .15       0  5146.6     .17       0  5455.8     .11       0
Bank Sta=4973.5,5031.9
XS Rating Curve= 0 ,0
Exp/Cntr=0.3,0.1

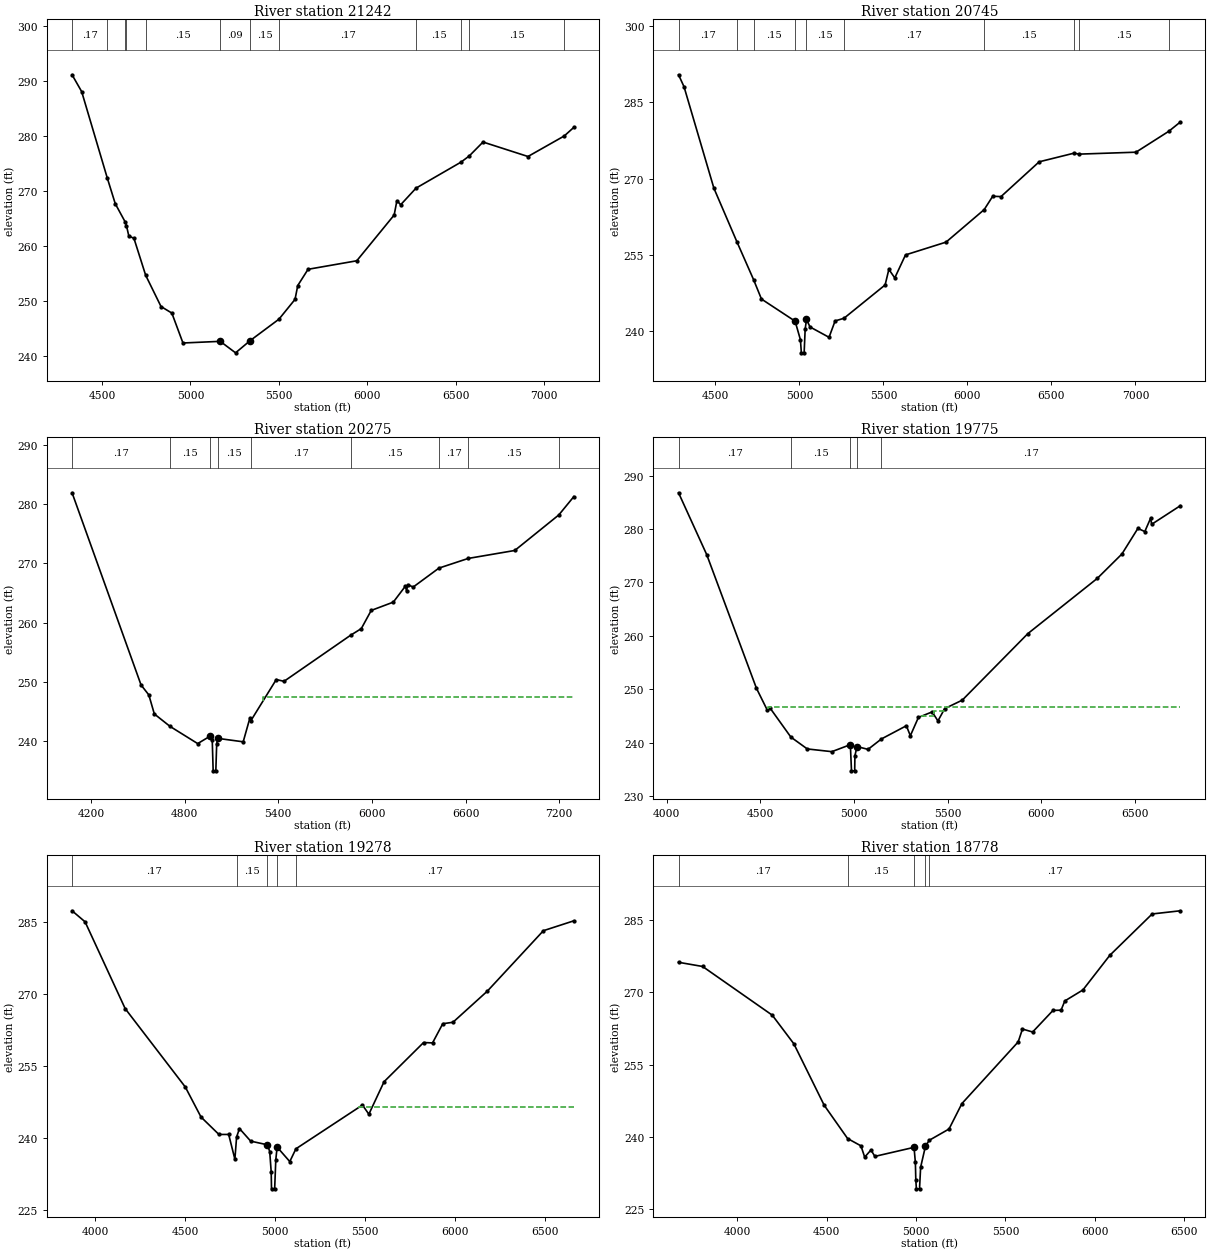
Type RM Length L Ch R = 1 ,21242   ,497,497,497
BEGIN DESCRIPTION:
MCDONALD CREEK 40.0
END DESCRIPTION:
XS GIS Cut Line= 3
      3783017.86     10216961.07      3782401.06     10217221.19
      3780544.22      10218342.4
#Sta/Elev= 30
  4330.6  291.14  4384.9  288.08  4529.2  272.43  4574.9   267.7  4632.7  264.28
  4638.1  263.73  4651.5  261.84  4680.7  261.39    4747  254.68  4833.8     249
    4895  247.81  4957.9  242.37  5168.7  242.67  5255.5  240.58  5337.5  242.79
  5500.9   246.7  5591.8   250.3  5607.3  252.82  5665.5  255.77  5941.1  257.32
  6152.6  265.64  6168.1  268.24  6189.5  267.51  6276.4  270.53  6530.4  275.25
  6577.4  276.38  6655.3  278.91  6909.5  276.28  7114.5  280.01  7169.1  281.58
#Mann= 12 ,-1 , 0
  4330.6     .17       0  4529.2     .11       0  4632.7     .17       0
  4638.1     .11       0    4747     .15       0  5168.7     .09       0
  5337.5     .15       0  5500.9     .17       0  6276.4     .15       0
  6530.4     .17       0  6577.4     .15       0  7114.5     .11       0
Bank Sta=5168.7,5337.5
XS Rating Curve= 0 ,0
Exp/Cntr=0.3,0.1

Type RM Length L Ch R = 1 ,20745   ,470,470,470
BEGIN DESCRIPTION:
MCDONALD CREEK 39.0
END DESCRIPTION:
XS GIS Cut Line= 3
      3782990.49     10216908.41       3782272.3     10216866.76
      3780517.58     10218302.44
#Sta/Elev= 30
  4280.6  290.38  4313.3  288.03  4491.1  268.09  4628.5  257.53  4727.1  250.14
  4774.1  246.32  4974.4  241.97  5006.1  238.32  5011.6  235.75  5028.2  235.75
  5034.3   240.4  5042.2  242.32    5063  240.84  5176.4   238.8  5212.5  242.02
  5265.2  242.54  5510.2  249.09  5532.4  252.15  5567.6  250.47  5631.5  254.99
  5872.7   257.5  6099.8  263.89  6150.5  266.51    6200  266.45    6427  273.28
  6634.4  274.98  6664.4  274.79  7003.2  275.17  7198.2  279.27  7267.2   281.1
#Mann= 10 ,-1 , 0
  4280.6     .17       0  4628.5     .11       0  4727.1     .15       0
  4974.4     .09       0  5042.2     .15       0  5265.2     .17       0
  6099.8     .15       0  6634.4     .17       0  6664.4     .15       0
  7198.2     .11       0
#XS Ineff= 2 , 0
       0                  5439.8       0  247.11
Permanent Ineff=
       F       F
Bank Sta=4974.4,5042.2
XS Rating Curve= 0 ,0
Exp/Cntr=0.3,0.1

Type RM Length L Ch R = 1 ,20275   ,500,500,500
BEGIN DESCRIPTION:
MCDONALD CREEK 38.0
END DESCRIPTION:
XS GIS Cut Line= 3
      3782635.29      10215878.4      3782069.14     10216604.58
      3780478.57     10218257.07
#Sta/Elev= 30
  4079.2  281.88  4521.2   249.5  4570.9  247.83  4606.2  244.62  4706.6  242.53
  4883.9  239.63  4962.6  240.87  4977.1  240.23    4983  235.04  5000.1  235.04
  5005.6  239.58  5012.5  240.51  5175.4  239.93  5217.5  243.86  5223.8  243.46
  5387.3  250.42    5437  250.12  5862.9  257.87    5932     259  5995.5  262.06
    6137  263.46    6215  266.17  6221.9   265.3  6229.1  266.41  6264.4     266
  6429.3  269.19  6616.8  270.82    6915  272.16  7197.3  278.15  7293.6  281.24
#Mann= 9 ,-1 , 0
  4079.2     .17       0  4706.6     .15       0  4962.6     .09       0
  5012.5     .15       0  5223.8     .17       0  5862.9     .15       0
  6429.3     .17       0  6616.8     .15       0  7197.3     .11       0
#XS Ineff= 2 , 0
       0                  5302.4       0  247.48
Permanent Ineff=
       F       F
Bank Sta=4962.6,5012.5
XS Rating Curve= 0 ,0
Exp/Cntr=0.3,0.1

Type RM Length L Ch R = 1 ,19775   ,497,497,497
BEGIN DESCRIPTION:
MCDONALD CREEK 37.0
END DESCRIPTION:
XS GIS Cut Line= 3
      3782502.12      10215767.4      3781732.02     10216300.82
      3780242.55     10217205.72
#Sta/Elev= 30
  4063.2  286.79  4213.6  275.22  4479.1  250.21  4535.9  246.19  4550.8  246.55
    4663  241.06  4750.7  238.84  4881.8  238.33  4980.7  239.64  4986.8  234.74
  5003.9  234.74  5005.1  237.59  5016.6  239.28  5075.1  238.76  5146.7  240.71
  5279.8  243.18  5301.1  241.31  5344.2  244.74  5417.4  245.77  5448.4  244.09
  5484.6  246.39  5578.2  247.97    5929  260.44  6299.2  270.76  6430.9  275.33
  6516.2  280.12  6553.1  279.53    6584  282.02  6589.9  280.89  6742.8  284.37
#Mann= 5 ,-1 , 0
  4063.2     .17       0    4663     .15       0  4980.7     .09       0
  5016.6     .15       0  5146.7     .17       0
#XS Ineff= 4 ,-1
  4542.8  4529.8  246.61  5359.3  5426.1  245.09  5496.9  5533.7  246.59
  5426.1  5496.9  245.86
Permanent Ineff=
       F       F       F       F
Bank Sta=4980.7,5016.6
XS Rating Curve= 0 ,0
Exp/Cntr=0.3,0.1

Type RM Length L Ch R = 1 ,19278   ,500,500,500
BEGIN DESCRIPTION:
MCDONALD CREEK 36.0
END DESCRIPTION:
XS GIS Cut Line= 3
      3782484.35     10215687.51      3781396.39     10215984.99
      3780189.06      10217121.5
#Sta/Elev= 30
  3872.1  287.44  3944.3  285.14  4166.9  267.06  4500.9  250.72    4588  244.47
  4687.5  240.84  4741.6  240.84  4776.1  235.68  4785.6  240.31  4801.5  242.07
  4863.7  239.45    4957  238.68  4969.4  237.28  4977.7  233.03  4979.4  229.51
  4996.9  229.51  5003.2  235.54  5010.5  238.21  5080.9  235.19  5114.9  237.85
  5484.3  246.97  5519.9  245.06  5604.4  251.83  5823.7  259.99  5873.5  259.91
  5930.2  263.91  5986.8  264.21  6177.8   270.7  6488.9  283.29  6658.1  285.35
#Mann= 5 ,-1 , 0
  3872.1     .17       0  4785.6     .15       0    4957     .09       0
  5010.5     .15       0  5114.9     .17       0
#XS Ineff= 2 , 0
       0                  5463.3       0  246.56
Permanent Ineff=
       F       F
Bank Sta=4957,5010.5
XS Rating Curve= 0 ,0
Exp/Cntr=0.3,0.1

Type RM Length L Ch R = 1 ,18778   ,498,498,498
BEGIN DESCRIPTION:
MCDONALD CREEK 35.0
END DESCRIPTION:
XS GIS Cut Line= 3
       3781951.6     10214954.96      3780959.06     10215838.01
      3780132.11     10217062.65
#Sta/Elev= 30
  3671.5  276.27  3806.1   275.4  4195.8  265.28  4316.2  259.35  4485.9  246.58
    4617  239.66  4691.6  238.14  4712.5   235.8  4747.7  237.28  4769.4  235.95
  4988.5  237.83    4996  234.69  4998.5  230.96  5001.7  229.21  5019.2  229.21
  5025.4   233.7  5052.4  238.07  5073.8   239.3  5184.2  241.64  5256.2  246.92
  5570.9  259.73  5594.8   262.4  5651.8  261.79  5765.8  266.28  5810.7  266.32
  5831.7  268.24  5932.8  270.52  6083.4  277.72  6320.3  286.31  6477.7  286.97
#Mann= 5 ,-1 , 0
  3671.5     .17       0    4617     .15       0  4988.5     .09       0
  5052.4     .15       0  5073.8     .17       0
Bank Sta=4988.5,5052.4
XS Rating Curve= 0 ,0
Exp/Cntr=0.3,0.1

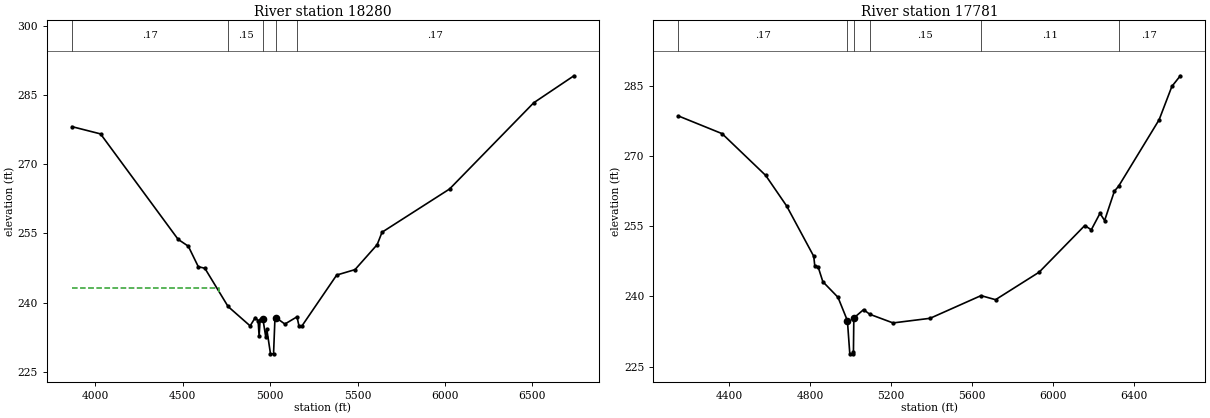
Type RM Length L Ch R = 1 ,18280   ,499,499,499
BEGIN DESCRIPTION:
MCDONALD CREEK 34.0
END DESCRIPTION:
XS GIS Cut Line= 3
      3781880.57     10214892.81      3780888.18     10215435.95
      3780082.68     10216974.67
#Sta/Elev= 30
  3868.7  278.17  4031.4   276.6  4474.9  253.72    4533  252.24    4590   247.8
  4627.6  247.45  4760.2  239.16  4886.4  234.95  4915.9  236.77    4932  236.06
  4937.7  232.72  4943.4   236.3  4959.5  236.42  4975.6  232.55  4981.3  234.29
  5002.7  228.89  5020.2  228.89  5027.9  236.35  5033.5  236.77  5084.8  235.35
  5154.2  236.92  5165.9  234.87  5182.4  234.94    5381  245.98  5485.7  247.16
  5612.4  252.58  5640.1  255.27  6026.1  264.65    6507  283.35  6736.8  289.21
#Mann= 5 ,-1 , 0
  3868.7     .17       0  4760.2     .15       0  4959.5     .09       0
  5033.5     .15       0  5154.2     .17       0
#XS Ineff= 2 , 0
       0  4709.2  243.16               0
Permanent Ineff=
       F       F
Bank Sta=4959.5,5033.5
XS Rating Curve= 0 ,0
Exp/Cntr=0.3,0.1

Type RM Length L Ch R = 1 ,17781   ,498,498,498
BEGIN DESCRIPTION:
MCDONALD CREEK 33.0
END DESCRIPTION:
XS GIS Cut Line= 3
      3781853.92     10214830.67       3781033.3     10215052.22
      3779519.13     10215656.26
#Sta/Elev= 30
    4150  278.59  4365.6  274.81    4581  265.88  4684.5  259.35  4818.5  248.58
  4823.7  246.53  4839.9  246.35  4863.6  243.14  4938.2  239.82  4984.9  234.82
  4996.7  227.72  5014.2  227.72  5014.7  228.22  5016.6  235.39  5064.7  237.17
  5095.6  236.18  5210.4  234.33  5393.5  235.32  5645.2  240.17    5717   239.3
  5932.6  245.19  6157.9  255.16  6190.2  254.25  6233.2  257.77    6256  256.23
  6304.5  262.53    6325  263.56  6525.5  277.79  6588.5  284.92  6630.2  287.19
#Mann= 6 ,-1 , 0
    4150     .17       0  4984.9     .09       0  5016.6     .17       0
  5095.6     .15       0  5645.2     .11       0    6325     .17       0
Bank Sta=4984.9,5016.6
XS Rating Curve= 0 ,0
Exp/Cntr=0.3,0.1