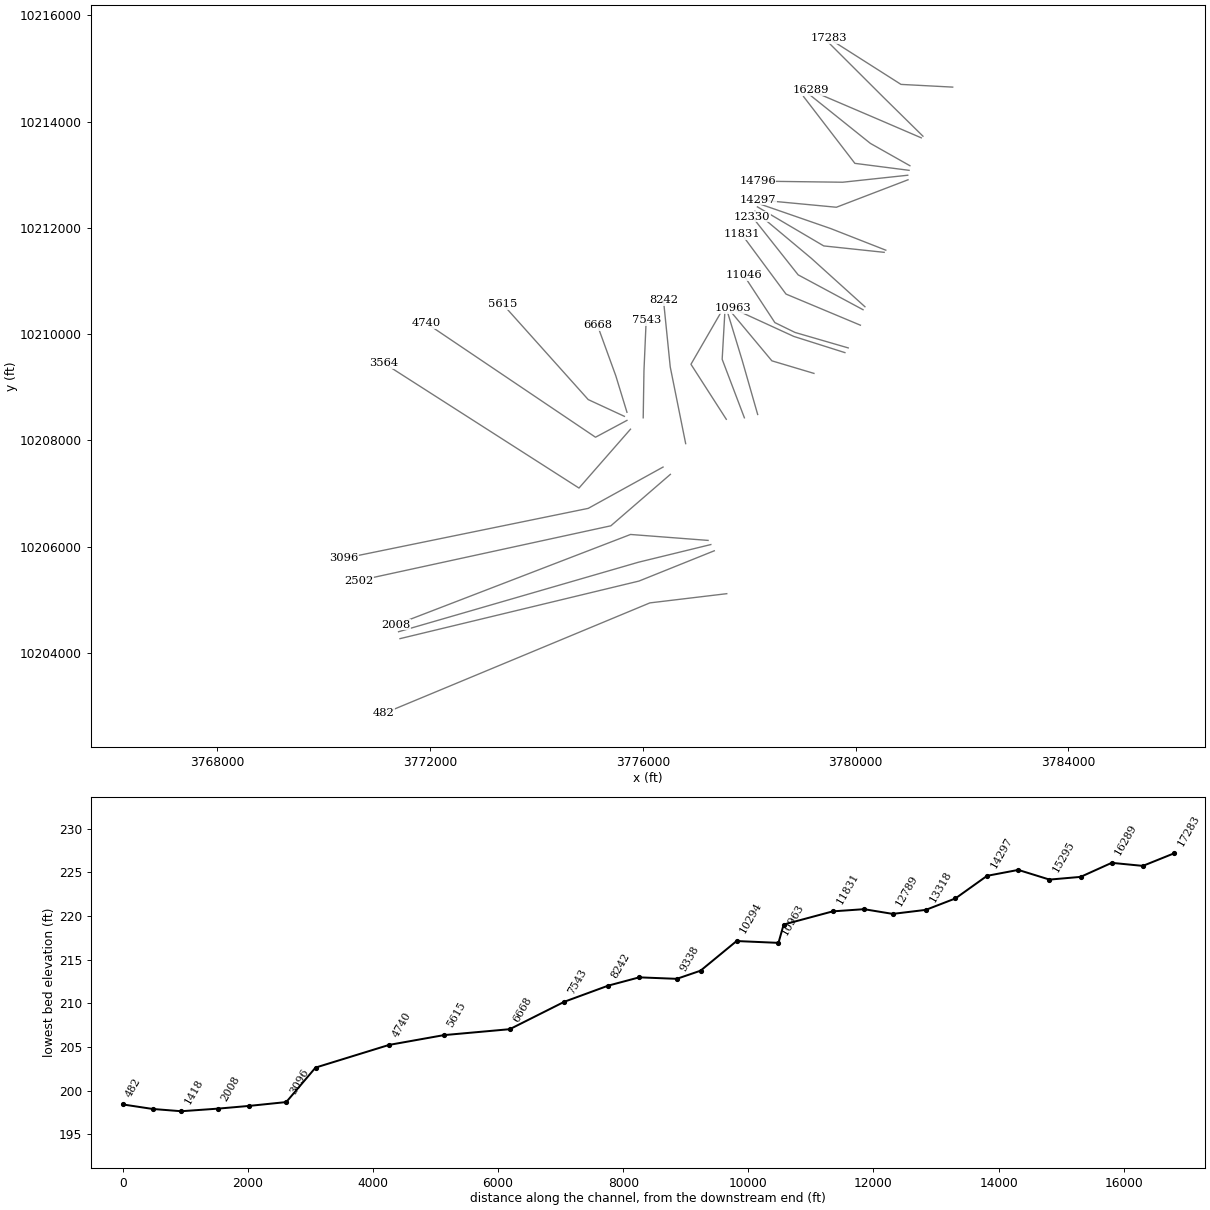
HEC-RAS study MCDONALD CREEK.prj: MCDONALD CREEK Base Level Engineering

--- MCDONALD CREEK.g01 (geometry) --- (continued)

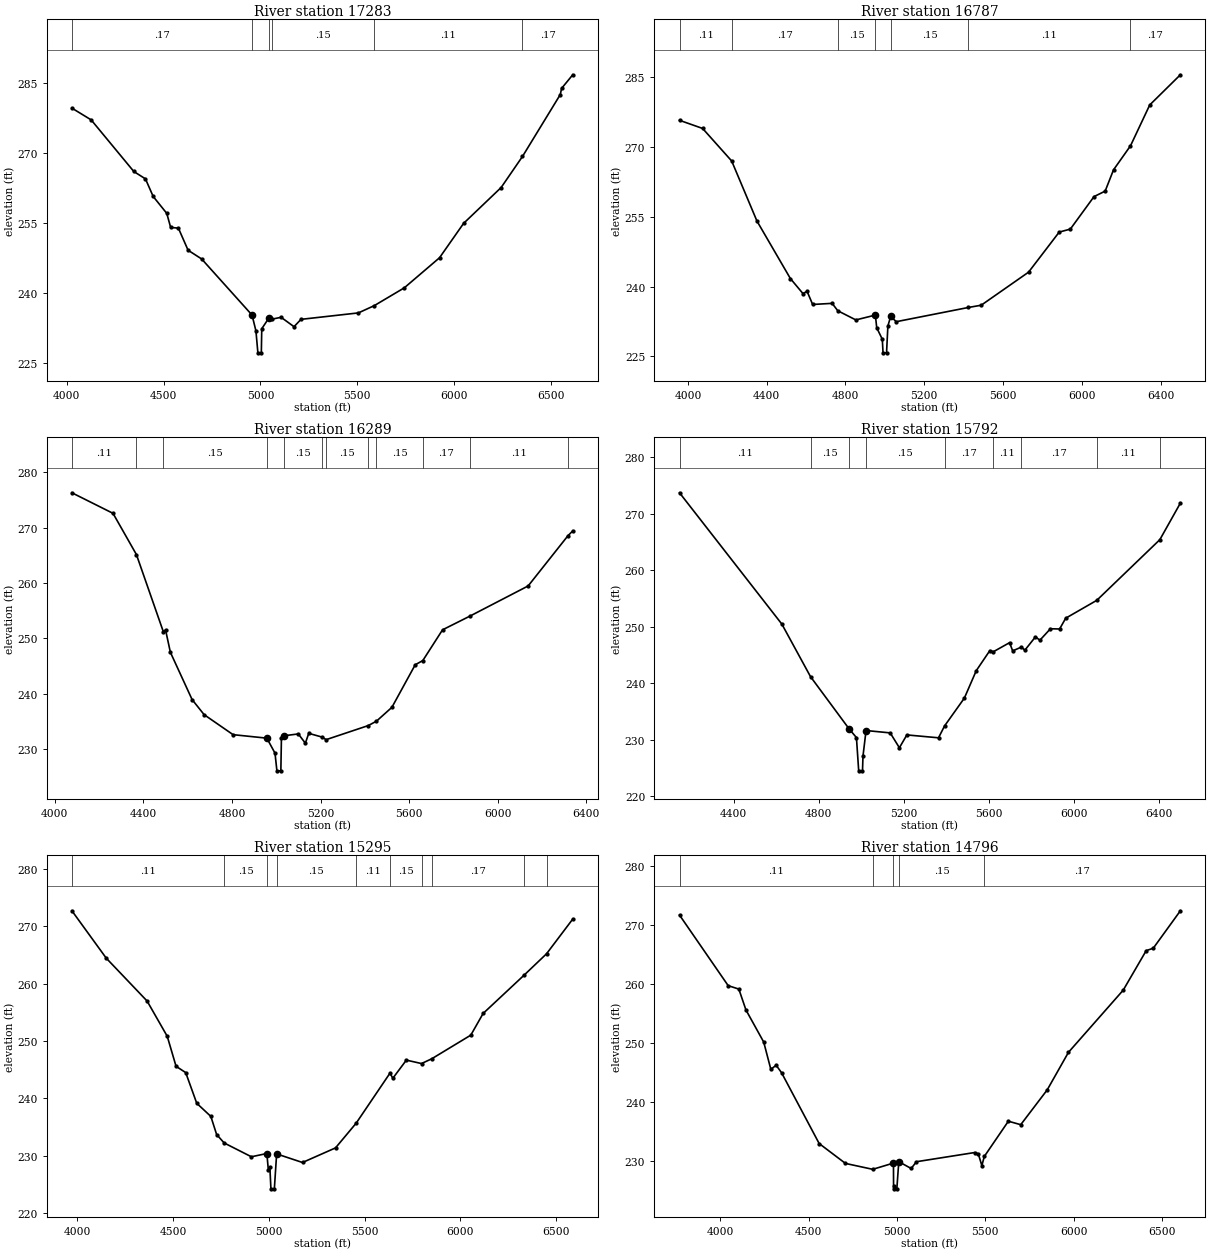
Type RM Length L Ch R = 1 ,17283   ,496,496,496
BEGIN DESCRIPTION:
MCDONALD CREEK 32.0
END DESCRIPTION:
XS GIS Cut Line= 3
      3781827.31     10214648.65      3780854.76     10214699.79
      3779493.65     10215566.62
#Sta/Elev= 30
  4026.1  279.58  4125.7  277.06    4346  266.01  4406.1  264.43  4446.1  260.66
  4516.2  257.05  4536.3  254.04  4576.3  253.88  4626.4  249.15  4696.5  247.28
  4956.8  235.27  4976.9  231.88    4987  227.18  5004.8  227.18    5007  232.34
  5043.4  234.61  5059.6  234.39  5106.9  234.79  5173.7  232.78  5209.7  234.35
  5506.1  235.73  5588.5  237.29  5743.4   241.1  5925.4  247.54  6049.9  254.91
  6243.7  262.58    6354  269.23  6549.4  282.49  6556.1  283.81  6613.7  286.72
#Mann= 6 ,-1 , 0
  4026.1     .17       0  4956.8     .09       0  5043.4     .15       0
  5059.6     .15       0  5588.5     .11       0    6354     .17       0
Bank Sta=4956.8,5043.4
XS Rating Curve= 0 ,0
Exp/Cntr=0.3,0.1

Type RM Length L Ch R = 1 ,16787   ,498,498,498
BEGIN DESCRIPTION:
MCDONALD CREEK 31.0
END DESCRIPTION:
XS GIS Cut Line= 3
       3781267.9     10213725.19      3780525.11     10214456.68
       3779463.3     10215516.47
#Sta/Elev= 30
  3957.5   275.7  4074.8  273.95  4222.3  266.96  4350.6  254.06  4520.3  241.71
    4584  238.49  4605.1  238.96  4633.4  236.14  4732.4  236.38  4760.9  234.79
  4852.7  232.82  4951.7  233.86  4958.7  231.13    4987  228.67  4990.7  225.75
  5008.5  225.75  5015.3   231.5  5029.4  233.58  5057.7  232.44  5423.3  235.49
  5489.1  235.98  5729.5  243.08  5885.1  251.69  5941.6  252.33  6061.8  259.31
  6118.4  260.49  6160.8  265.06    6247  270.22  6344.7     279  6500.2  285.48
#Mann= 7 ,-1 , 0
  3957.5     .11       0  4222.3     .17       0  4760.9     .15       0
  4951.7     .09       0  5029.4     .15       0  5423.3     .11       0
    6247     .17       0
Bank Sta=4951.7,5029.4
XS Rating Curve= 0 ,0
Exp/Cntr=0.3,0.1

Type RM Length L Ch R = 1 ,16289   ,497,497,497
BEGIN DESCRIPTION:
MCDONALD CREEK 30.0
END DESCRIPTION:
XS GIS Cut Line= 3
      3781236.31     10213693.97      3780388.43     10214058.95
      3779157.93     10214585.44
#Sta/Elev= 30
  4076.9   276.3  4262.5  272.59  4368.2  265.15  4489.9   251.2  4499.8  251.54
  4521.6   247.5  4619.6  238.97    4674  236.24  4804.7  232.63  4957.1     232
    4994  229.29  5002.6   226.1  5020.4   226.1    5023  232.02  5033.3  232.43
  5099.2  232.76  5131.1  231.09  5146.3  232.87  5206.7  232.19  5224.8  231.73
    5415  234.27  5451.9  235.06  5521.9  237.57  5627.1  245.25  5661.4  246.01
  5750.5  251.56  5874.9  254.05    6137  259.48  6316.4  268.53  6338.4  269.42
#Mann= 12 ,-1 , 0
  4076.9     .11       0  4368.2     .17       0  4489.9     .15       0
  4957.1     .09       0  5033.3     .15       0  5206.7     .11       0
  5224.8     .15       0    5415     .11       0  5451.9     .15       0
  5661.4     .17       0  5874.9     .11       0  6316.4     .17       0
Bank Sta=4957.1,5033.3
XS Rating Curve= 0 ,0
Exp/Cntr=0.3,0.1

Type RM Length L Ch R = 1 ,15792   ,497,497,497
BEGIN DESCRIPTION:
MCDONALD CREEK 29.0
END DESCRIPTION:
XS GIS Cut Line= 3
      3781022.36     10213169.31      3780278.77      10213589.7
      3779107.03     10214529.39
#Sta/Elev= 30
  4145.8  273.73  4627.3  250.47  4762.2  241.16  4943.6  231.92  4978.1  230.38
  4988.7  224.49  5006.6  224.49  5008.9   227.1  5023.3  231.63  5136.9  231.21
  5180.1  228.58  5215.3  230.85  5364.2  230.34  5392.8  232.45  5485.8  237.37
  5541.8  242.23  5605.8  245.79  5622.2  245.58  5698.6  247.19    5713  245.73
  5754.2  246.41  5770.3  245.85  5820.3  248.22  5841.1  247.62  5890.7  249.65
  5933.9  249.61  5962.6  251.52  6108.6  254.68  6405.5  265.43    6502   271.9
#Mann= 9 ,-1 , 0
  4145.8     .11       0  4762.2     .15       0  4943.6     .09       0
  5023.3     .15       0  5392.8     .17       0  5622.2     .11       0
  5754.2     .17       0  6108.6     .11       0  6405.5     .17       0
Bank Sta=4943.6,5023.3
XS Rating Curve= 0 ,0
Exp/Cntr=0.3,0.1

Type RM Length L Ch R = 1 ,15295   ,499,499,499
BEGIN DESCRIPTION:
MCDONALD CREEK 28.0
END DESCRIPTION:
XS GIS Cut Line= 3
      3781007.05     10213082.73      3779987.63     10213213.77
      3779021.65     10214471.78
#Sta/Elev= 30
  3972.2  272.74  4151.6  264.46  4364.6  256.98  4469.8  250.82  4515.8  245.58
  4566.2  244.48  4623.8  239.12  4697.3  236.83  4727.6  233.66    4767  232.19
    4909  229.78  4989.7  230.35  4997.4  227.48  5005.4  227.91  5010.9  224.18
  5028.8  224.18  5040.7  230.28  5175.7  228.78    5348  231.33  5455.6  235.64
  5632.4  244.39  5647.1  243.49  5717.7  246.66  5796.8  246.06    5850  246.89
    6054  251.02  6118.4  254.81  6330.4  261.44  6449.3  265.23  6586.1  271.29
#Mann= 10 ,-1 , 0
  3972.2     .11       0    4767     .15       0  4989.7     .09       0
  5040.7     .15       0  5455.6     .11       0  5632.4     .15       0
  5796.8     .11       0    5850     .17       0  6330.4     .11       0
  6449.3     .17       0
Bank Sta=4989.7,5040.7
XS Rating Curve= 0 ,0
Exp/Cntr=0.3,0.1

Type RM Length L Ch R = 1 ,14796   ,499,499,499
BEGIN DESCRIPTION:
MCDONALD CREEK 27.0
END DESCRIPTION:
XS GIS Cut Line= 3
      3780981.63     10212990.12      3779758.27     10212858.76
      3778154.49     10212878.97
#Sta/Elev= 30
  3769.6  271.72    4045  259.75  4105.3  259.17  4145.5  255.63  4246.1  250.18
  4286.3  245.56  4316.5  246.25  4346.7     245  4559.9  232.97  4708.7   229.6
    4863   228.6  4980.3  229.66  4980.9  225.79  4981.4  225.29  4999.4  225.29
  5010.4   229.9  5080.4  228.74  5110.4  229.89  5440.4  231.45  5460.5  231.22
  5480.5  229.22  5494.3  230.78  5630.5  236.76  5700.5  236.17  5850.5  242.08
  5970.5  248.44  6280.5  258.99  6410.5  265.69  6450.5   266.1  6603.9  272.45
#Mann= 5 ,-1 , 0
  3769.6     .11       0    4863     .15       0  4980.3     .09       0
  5010.4     .15       0  5494.3     .17       0
Bank Sta=4980.3,5010.4
XS Rating Curve= 0 ,0
Exp/Cntr=0.3,0.1

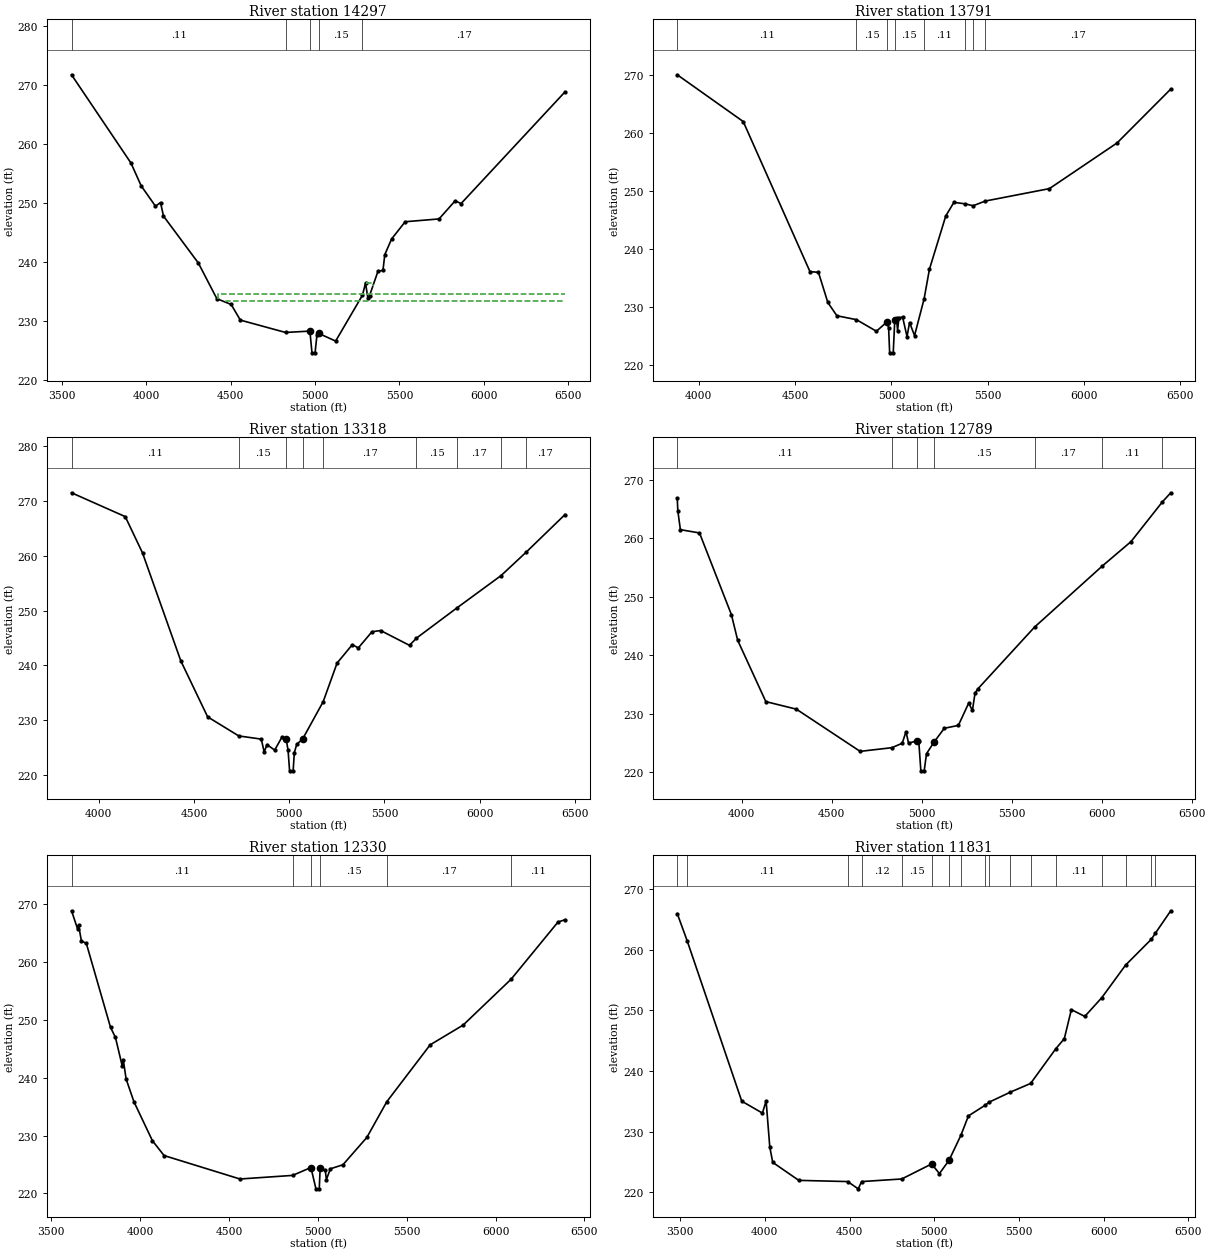
Type RM Length L Ch R = 1 ,14297   ,506,506,506
BEGIN DESCRIPTION:
MCDONALD CREEK 26.0
END DESCRIPTION:
XS GIS Cut Line= 3
      3780986.65     10212904.43      3779639.55     10212387.73
      3778164.66      10212527.5
#Sta/Elev= 30
  3557.2  271.68  3909.4  256.74  3969.9  252.88  4054.6  249.44  4084.6  250.05
  4102.1  247.76  4308.8  239.81  4418.2  233.78  4502.9   232.8  4557.6  230.15
  4825.4  228.06  4969.7  228.29    4982  224.61  5000.3  224.61  5011.8  227.71
  5021.8   227.9  5122.2   226.6    5281  234.36  5299.2   236.4  5313.1  233.95
  5323.1  234.28  5373.4  238.45  5402.5  238.55  5413.5  241.23  5453.7  243.88
  5534.1   246.8    5735  247.28  5830.4  250.34  5865.6  249.88  6481.5  268.79
#Mann= 5 ,-1 , 0
  3557.2     .11       0  4825.4     .15       0  4969.7     .09       0
  5021.8     .15       0    5281     .17       0
#XS Ineff= 3 ,-1
  4472.9  4448.2  233.45  4423.5  4393.5  234.65  5299.2  5343.2   236.4
Permanent Ineff=
       F       F       F
Bank Sta=4969.7,5021.8
XS Rating Curve= 0 ,0
Exp/Cntr=0.3,0.1

Type RM Length L Ch R = 1 ,13791   ,473,473,473
BEGIN DESCRIPTION:
MCDONALD CREEK 25.0
END DESCRIPTION:
XS GIS Cut Line= 3
      3780568.98     10211580.03       3779534.1     10211986.13
      3778164.69     10212461.27
#Sta/Elev= 30
  3888.3  270.07  4230.6  261.99    4577  236.06    4621  235.93  4669.8  230.72
  4716.7  228.43  4818.3  227.75  4921.9  225.75  4976.2  227.35  4985.2  226.35
  4990.6  222.02  5009.2  222.02  5017.2  227.67  5026.4  227.98  5031.7  225.87
  5038.4  227.98  5057.5  228.24  5080.7  224.84    5094  227.25  5119.8     225
  5169.3  231.33  5197.1  236.47  5281.8  245.67  5324.2  248.03  5381.1  247.77
    5424  247.44    5487  248.25  5819.9   250.4  6170.9  258.29  6449.5   267.6
#Mann= 8 ,-1 , 0
  3888.3     .11       0  4818.3     .15       0  4976.2     .09       0
  5017.2     .15       0  5169.3     .11       0  5381.1     .17       0
    5424     .11       0    5487     .17       0
Bank Sta=4976.2,5017.2
XS Rating Curve= 0 ,0
Exp/Cntr=0.3,0.1

Type RM Length L Ch R = 1 ,13318   ,529,529,529
BEGIN DESCRIPTION:
MCDONALD CREEK 24.0
END DESCRIPTION:
XS GIS Cut Line= 3
      3780538.38     10211539.29      3779402.16      10211659.9
      3778154.45     10212395.08
#Sta/Elev= 30
  3857.4  271.54  4139.5  267.18    4230  260.55  4431.1  240.81  4571.9  230.58
  4735.3  227.09  4853.5  226.51  4868.8  224.16  4883.7   225.5  4923.9   224.5
  4961.4  226.83  4984.2  226.55  4994.3  224.43  5002.2  220.71  5020.8  220.71
  5027.1  224.04  5039.8  225.57    5070  226.49  5178.5  233.35  5251.5  240.41
  5331.6  243.78  5362.9  243.18  5434.5  246.13    5480  246.36  5631.8  243.65
  5668.3  244.97  5879.4  250.46  6112.7  256.41  6242.9  260.64  6448.2  267.56
#Mann= 9 ,-1 , 0
  3857.4     .11       0  4735.3     .15       0  4984.2     .09       0
    5070     .15       0  5178.5     .17       0  5668.3     .15       0
  5879.4     .17       0  6112.7     .11       0  6242.9     .17       0
Bank Sta=4984.2,5070
XS Rating Curve= 0 ,0
Exp/Cntr=0.3,0.1

Type RM Length L Ch R = 1 ,12789   ,459,459,459
BEGIN DESCRIPTION:
MCDONALD CREEK 23.0
END DESCRIPTION:
XS GIS Cut Line= 3
      3780176.78     10210515.38      3779169.91     10211425.44
       3778108.6     10212313.58
#Sta/Elev= 30
  3642.8  266.89    3646   264.7  3660.2   261.5  3766.3  260.94  3943.4  246.98
  3978.5  242.57  4134.7  232.09  4304.3   230.8  4658.5  223.58  4834.9  224.21
  4892.4  224.97  4913.3  226.95  4927.5  224.99  4976.8   225.4  4984.3  225.32
  4995.8  220.25  5014.4  220.25  5027.2  223.18  5068.9  225.16  5126.1  227.53
  5204.2  228.02  5261.4  231.83  5282.2  230.58  5296.6  233.51  5310.9  234.22
  5627.2  244.83  6003.5  255.28  6163.2  259.46  6337.3  266.25  6383.9  267.81
#Mann= 7 ,-1 , 0
  3642.8     .11       0  4834.9     .15       0  4976.8     .09       0
  5068.9     .15       0  5627.2     .17       0  6003.5     .11       0
  6337.3     .17       0
Bank Sta=4976.8,5068.9
XS Rating Curve= 0 ,0
Exp/Cntr=0.3,0.1

Type RM Length L Ch R = 1 ,12330   ,499,499,499
BEGIN DESCRIPTION:
MCDONALD CREEK 22.0
END DESCRIPTION:
XS GIS Cut Line= 3
      3780141.11     10210459.38      3778920.62     10211115.56
       3778057.9     10212206.32
#Sta/Elev= 30
  3614.3  268.82    3648  265.72  3653.6  266.38  3669.9  263.61  3697.5  263.19
  3833.7  248.68  3861.4  246.94  3899.6  242.01  3905.2  243.12  3921.5  239.75
  3965.3  235.84  4069.2  229.11  4134.9  226.54  4561.8  222.49    4858  223.11
  4961.1  224.47  4989.4  220.79  5008.1  220.79    5013  224.37  5041.8  223.96
  5048.2   222.4  5070.7  224.25  5141.2  224.95  5275.8  229.67    5388  235.84
  5631.8  245.66  5817.6  249.08  6087.4     257  6351.3  266.88  6390.7  267.27
#Mann= 6 ,-1 , 0
  3614.3     .11       0    4858     .15       0  4961.1     .09       0
    5013     .15       0    5388     .17       0  6087.4     .11       0
Bank Sta=4961.1,5013
XS Rating Curve= 0 ,0
Exp/Cntr=0.3,0.1

Type RM Length L Ch R = 1 ,11831   ,785,785,785
BEGIN DESCRIPTION:
MCDONALD CREEK 21.0
END DESCRIPTION:
XS GIS Cut Line= 3
      3780091.47     10210168.03      3778692.44     10210753.78
      3777862.47     10211875.51
#Sta/Elev= 30
  3483.3     266  3541.9   261.5  3863.9  235.02  3985.9  233.05  4007.6  235.07
  4029.3  227.45  4046.7  224.91  4200.3  221.94    4489  221.74  4551.1  220.54
  4571.3  221.74  4808.1  222.17  4984.4  224.65  5030.3  223.06  5086.7  225.24
    5157  229.38  5201.5  232.59    5299  234.33  5325.3  234.88  5449.7  236.52
  5568.5  237.95    5717  243.68  5767.2  245.34  5808.9  250.14  5888.2  249.02
  5988.5  252.12  6128.6  257.49  6281.7  261.79  6303.9  262.74  6395.4  266.47
#Mann= 17 ,-1 , 0
  3483.3     .17       0  3541.9     .11       0    4489     .11       0
  4571.3     .12       0  4808.1     .15       0  4984.4     .07       0
  5086.7     .15       0    5157     .11       0    5299     .15       0
  5325.3     .11       0  5449.7     .15       0  5568.5     .17       0
    5717     .11       0  5988.5     .17       0  6128.6     .11       0
  6281.7     .17       0  6303.9     .11       0
Bank Sta=4984.4,5086.7
XS Rating Curve= 0 ,0
Exp/Cntr=0.3,0.1

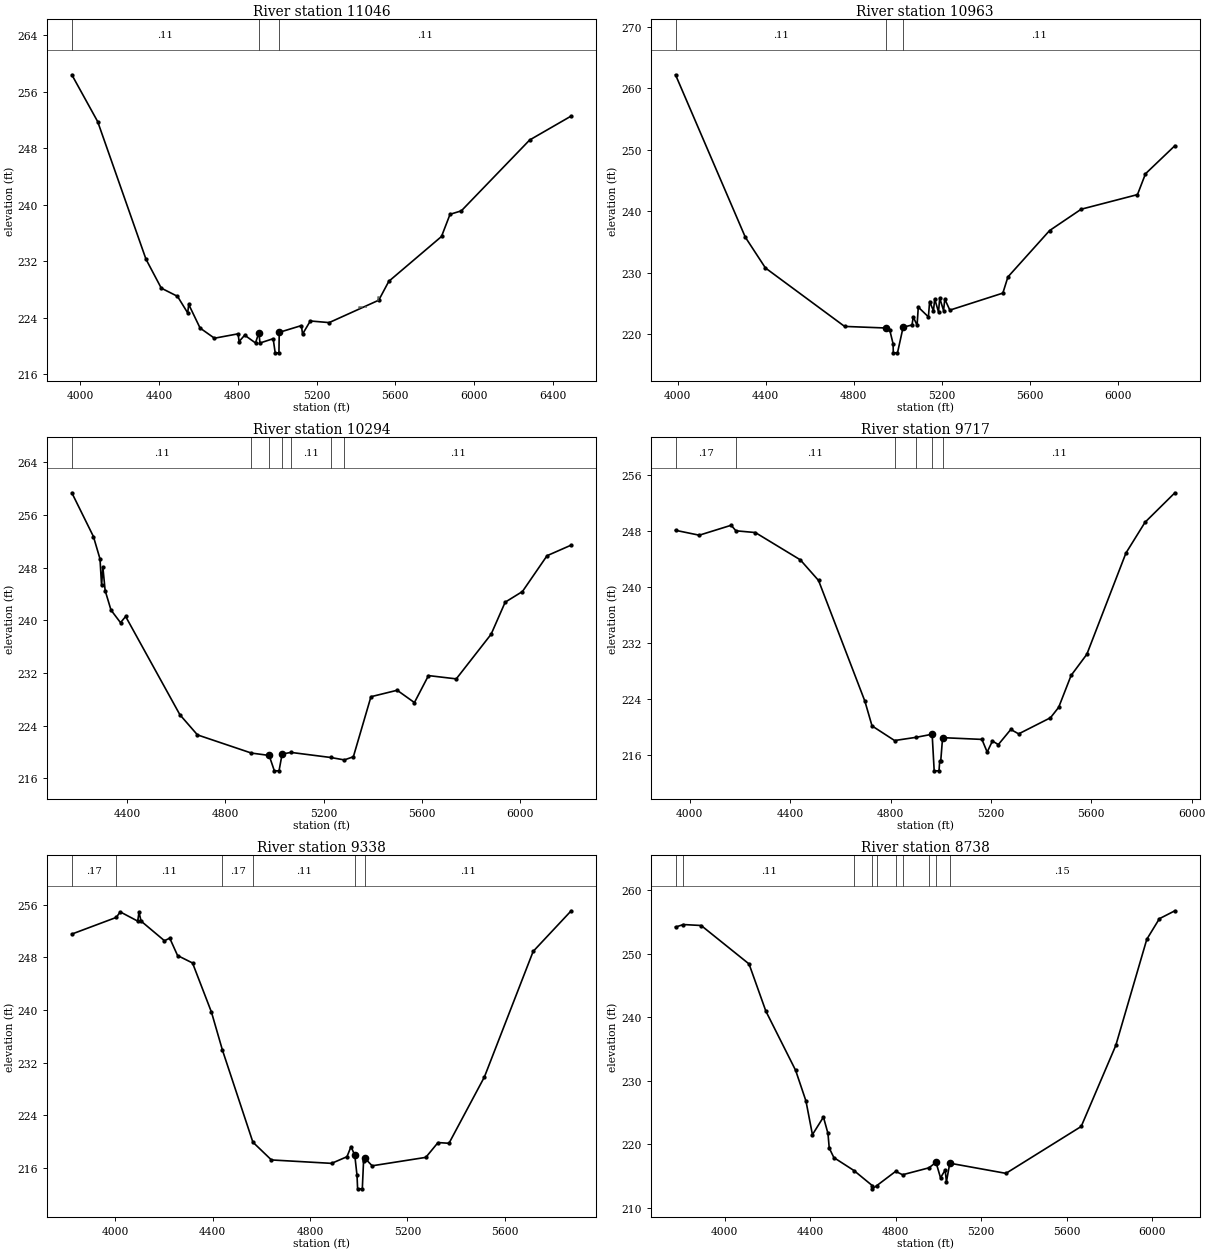
Type RM Length L Ch R = 1 ,11046   ,83,83,83
BEGIN DESCRIPTION:
MCDONALD CREEK 20.0
END DESCRIPTION:
XS GIS Cut Line= 4
      3779862.66     10209740.55      3778862.67      10210031.3
      3778483.06     10210216.69      3777896.75     10211111.44
#Sta/Elev= 30
  3958.6  258.39  4089.8  251.76  4334.9  232.28  4412.4  228.19  4494.7  227.03
  4546.5  224.68  4551.7  225.88  4609.3  222.54  4682.2   221.1  4802.1  221.72
  4807.3  220.63  4835.6  221.53  4890.5  220.43  4907.9   221.9  4913.1  220.42
  4980.1  221.03  4990.4  219.03  5009.4  219.03  5010.9  221.93  5123.5  222.89
  5129.1  221.68  5168.6  223.54  5264.2  223.31  5515.7  226.48    5567  229.16
  5834.2   235.5  5877.5  238.64  5934.8  239.13  6281.5  249.16  6492.2  252.55
#Mann= 3 ,-1 , 0
  3958.6     .11       0  4907.9     .06       0  5010.9     .11       0
#XS Ineff= 3 ,-1
  4551.7  4494.7  225.88  5416.3  5458.5  225.57  5509.7  5530.8   226.9
Permanent Ineff=
       F       F       F
Bank Sta=4907.9,5010.9
XS Rating Curve= 0 ,0
Exp/Cntr=0.3,0.1

Type RM Length L Ch R = 1 ,10963   ,669,669,669
BEGIN DESCRIPTION:
MCDONALD CREEK 19.0
END DESCRIPTION:
XS GIS Cut Line= 3
      3779800.25     10209651.98      3778838.31     10209956.85
      3777693.41     10210482.73
#Sta/Elev= 30
  3990.9  262.18  4308.1  235.75  4399.5  230.74  4759.2  221.23    4948  220.97
  4964.1  220.67  4979.5   218.4  4980.5  216.93  4999.5  216.93  5025.1  221.11
  5065.5  221.46    5071  222.77  5088.5  221.42    5094  224.37    5140  222.78
  5145.5  225.28    5163  223.76  5168.5   225.7  5185.9  223.59  5191.4  225.82
  5208.9  223.81  5214.4  225.68  5237.4  223.88  5478.2  226.65  5501.2  229.28
  5690.6  236.83    5834   240.3  6089.9  242.68  6126.3  246.07  6259.9  250.64
#Mann= 3 ,-1 , 0
  3990.9     .11       0    4948     .06       0  5025.1     .11       0
Bank Sta=4948,5025.1
XS Rating Curve= 0 ,0
Exp/Cntr=0.3,0.1

Type RM Length L Ch R = 1 ,10294   ,577,577,577
BEGIN DESCRIPTION:
MCDONALD CREEK 18.0
END DESCRIPTION:
XS GIS Cut Line= 3
      3779217.85     10209261.07      3778426.85     10209497.26
      3777652.73     10210425.14
#Sta/Elev= 30
  4174.5  259.38  4262.5  252.73  4289.3  249.33  4295.7   245.3  4300.9  248.09
  4310.2  244.53    4334  241.57  4372.8  239.65  4393.7  240.59  4614.7  225.66
  4686.2   222.6  4905.8  219.84  4978.1  219.48  4999.4  217.14  5018.4  217.14
    5031  219.69  5066.9  219.94  5228.5  219.17  5284.4   218.8  5321.2  219.28
  5392.8   228.4  5499.6  229.38  5569.8  227.51  5627.1  231.61  5740.3  231.11
  5882.2  237.89  5939.5  242.76  6009.8  244.38    6110  249.82  6208.4  251.43
#Mann= 7 ,-1 , 0
  4174.5     .11       0  4905.8     .15       0  4978.1     .09       0
    5031     .15       0  5066.9     .11       0  5228.5     .15       0
  5284.4     .11       0
Bank Sta=4978.1,5031
XS Rating Curve= 0 ,0
Exp/Cntr=0.3,0.1

Type RM Length L Ch R = 1 ,9717    ,379,379,379
BEGIN DESCRIPTION:
MCDONALD CREEK 17.0
END DESCRIPTION:
XS GIS Cut Line= 3
      3778159.59     10208487.71       3777868.9     10209503.95
       3777597.3     10210396.76
#Sta/Elev= 30
    3943   248.1  4037.6   247.4  4164.9  248.82  4183.6  248.03  4261.1  247.78
  4440.4  243.88  4513.1  240.93  4697.7  223.69  4726.2  220.16    4816  218.07
  4902.4  218.53  4965.8  218.97  4973.9  213.74  4993.2  213.74  4995.9  215.13
    5000  215.13  5007.4  218.48  5164.2  218.23  5185.1  216.42    5206     218
  5229.5  217.49  5279.2  219.65  5310.6  219.02  5437.2  221.32    5470  222.81
  5519.6  227.37  5582.3  230.39  5738.1  244.85  5814.3  249.25  5933.2  253.46
#Mann= 6 ,-1 , 0
    3943     .17       0  4183.6     .11       0    4816     .15       0
  4902.4     .11       0  4965.8     .06       0  5007.4     .11       0
Bank Sta=4965.8,5007.4
XS Rating Curve= 0 ,0
Exp/Cntr=0.3,0.1

Type RM Length L Ch R = 1 ,9338    ,600,600,600
BEGIN DESCRIPTION:
MCDONALD CREEK 16.0
END DESCRIPTION:
XS GIS Cut Line= 3
      3777909.57      10208425.3      3777491.72     10209526.27
      3777541.49     10210396.75
#Sta/Elev= 30
  3822.4  251.51  4004.7  254.04  4021.1  254.88  4092.8  253.48  4098.1  254.83
  4106.7  253.48  4202.6   250.5  4224.3  250.89  4256.4  248.25  4317.8  247.12
  4395.5  239.65  4440.5  233.89  4565.5   219.9  4641.5   217.2  4888.5  216.68
  4951.7  217.69  4968.2  219.23  4983.7   217.9  4992.9  214.84  4995.3  212.81
  5014.6  212.81  5019.8   217.1  5024.9  217.47  5054.9  216.31  5275.2  217.59
  5325.3  219.84  5370.3  219.73  5515.6   229.8  5715.8  248.88  5871.9  255.05
#Mann= 6 ,-1 , 0
  3822.4     .17       0  4004.7     .11       0  4440.5     .17       0
  4565.5     .11       0  4983.7     .06       0  5024.9     .11       0
Bank Sta=4983.7,5024.9
XS Rating Curve= 0 ,0
Exp/Cntr=0.3,0.1

Type RM Length L Ch R = 1 ,8738    ,496,496,496
BEGIN DESCRIPTION:
MCDONALD CREEK 15.0
END DESCRIPTION:
XS GIS Cut Line= 3
      3777569.29     10208397.51      3776904.75     10209432.54
      3777458.21     10210390.56
#Sta/Elev= 30
    3770  254.23  3806.8  254.63    3890  254.48    4114  248.42  4192.6  240.99
    4332  231.65  4380.3  226.82  4410.6  221.52  4462.1  224.29  4483.3  221.71
  4489.2   219.4    4511   217.9  4604.6  215.87    4691  213.48  4691.5  212.98
  4711.4  213.48  4799.8  215.73  4832.5   215.2  4955.6  216.29  4988.7  217.16
  5009.9  214.72  5031.7  215.94  5037.5  214.09  5053.2  217.02    5316  215.42
  5668.1  222.81  5829.8  235.57    5975  252.31  6033.8  255.55  6106.4   256.8
#Mann= 10 ,-1 , 0
    3770     .17       0  3806.8     .11       0  4604.6     .15       0
    4691     .09       0  4711.4     .15       0  4799.8     .17       0
  4832.5     .15       0  4955.6     .11       0  4988.7     .07       0
  5053.2     .15       0
Bank Sta=4988.7,5053.2
XS Rating Curve= 0 ,0
Exp/Cntr=0.3,0.1

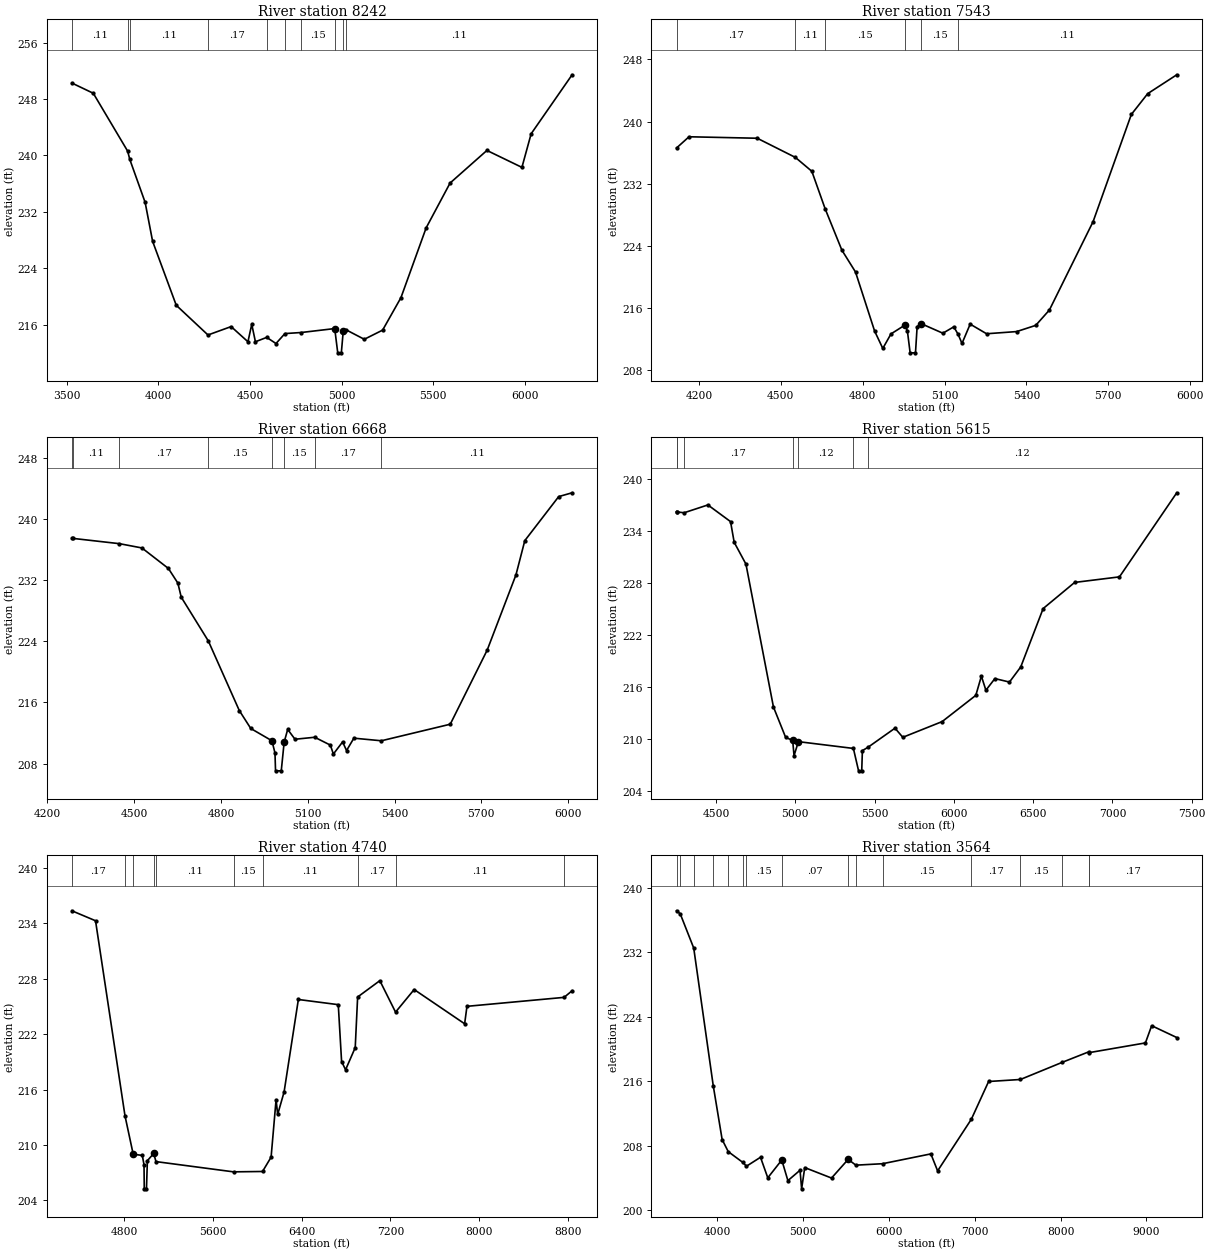
Type RM Length L Ch R = 1 ,8242    ,699,699,699
BEGIN DESCRIPTION:
MCDONALD CREEK 14.0
END DESCRIPTION:
XS GIS Cut Line= 3
      3776805.42     10207939.13      3776515.16     10209382.84
      3776388.75     10210633.57
#Sta/Elev= 30
  3527.4  250.26  3644.3  248.81  3831.8  240.61  3843.6  239.43  3927.2  233.35
    3968  227.83    4097  218.77  4270.1  214.56  4396.4  215.75  4488.2   213.6
    4509  216.07    4529   213.6  4590.6  214.22  4641.2  213.35    4690  214.76
  4778.7  214.91  4961.7  215.47  4978.2  212.03  4997.8  212.03  5008.3  215.13
  5025.3  215.27  5123.1  213.95  5223.1  215.25  5323.1  219.85  5460.6  229.74
  5591.2  236.09  5792.2  240.71  5983.2  238.31  6033.5  243.07  6257.1  251.43
#Mann= 10 ,-1 , 0
  3527.4     .11       0  3831.8     .17       0  3843.6     .11       0
  4270.1     .17       0  4590.6     .11       0    4690     .17       0
  4778.7     .15       0  4961.7     .09       0  5008.3     .15       0
  5025.3     .11       0
Bank Sta=4961.7,5008.3
XS Rating Curve= 0 ,0
Exp/Cntr=0.3,0.1

Type RM Length L Ch R = 1 ,7543    ,875,875,875
BEGIN DESCRIPTION:
MCDONALD CREEK 12.0
END DESCRIPTION:
XS GIS Cut Line= 3
      3776006.81     10208425.27      3776020.94     10209307.55
      3776062.31     10210257.35
#Sta/Elev= 30
  4117.6  236.59  4163.4  238.04  4413.4  237.85  4553.2  235.38  4613.5  233.59
  4662.2  228.76  4723.5  223.43  4773.5  220.61  4843.5     213  4873.5  210.76
  4903.5  212.63  4953.5  213.74  4963.5  213.05  4973.7  210.19  4993.3  210.19
  4999.3  213.56  5013.5  213.96  5093.6  212.72  5133.6  213.54  5149.2   212.6
  5163.7   211.4  5193.7  213.89  5253.8  212.65  5363.9  212.93  5433.9  213.73
    5484  215.71  5644.1   227.1  5784.3  240.92  5844.3   243.6  5950.7  246.03
#Mann= 6 ,-1 , 0
  4117.6     .17       0  4553.2     .11       0  4662.2     .15       0
  4953.5     .09       0  5013.5     .15       0  5149.2     .11       0
Bank Sta=4953.5,5013.5
XS Rating Curve= 0 ,0
Exp/Cntr=0.3,0.1

Type RM Length L Ch R = 1 ,6668    ,1053,1053,1053
BEGIN DESCRIPTION:
MCDONALD CREEK 11.0
END DESCRIPTION:
XS GIS Cut Line= 3
      3775701.26     10208529.39        3775492.     10209213.82
      3775146.09     10210167.21
#Sta/Elev= 30
  4284.3  237.49  4288.4   237.5  4448.9  236.81  4526.6  236.25  4618.2  233.56
  4650.9  231.64  4662.5   229.8  4756.2  224.06  4863.3  214.94    4903  212.59
  4976.2  210.98  4986.7  209.37  4988.6  207.04  5008.4  207.04  5018.4  210.79
  5030.6  212.47  5055.9  211.18  5124.1  211.44  5178.3  210.41  5188.6  209.24
  5220.5  210.83  5234.2   209.7  5259.5  211.32  5354.6  210.98  5592.8  213.15
  5720.5  222.86    5820  232.72  5850.6  237.21  5967.8  242.98  6014.2  243.48
#Mann= 8 ,-1 , 0
  4284.3     .17       0  4288.4     .11       0  4448.9     .17       0
  4756.2     .15       0  4976.2     .09       0  5018.4     .15       0
  5124.1     .17       0  5354.6     .11       0
Bank Sta=4976.2,5018.4
XS Rating Curve= 0 ,0
Exp/Cntr=0.3,0.1

Type RM Length L Ch R = 1 ,5615    ,875,875,875
BEGIN DESCRIPTION:
MCDONALD CREEK 10.0
END DESCRIPTION:
XS GIS Cut Line= 3
      3775652.68     10208453.01      3774972.55     10208768.17
      3773367.88     10210561.04
#Sta/Elev= 30
  4250.4  236.21  4255.3  236.16  4298.4  236.07  4448.3  236.97  4591.3  235.05
  4614.2  232.67  4688.4  230.16  4861.9  213.71  4939.1   210.2  4983.1  209.87
  4991.8  208.11  5019.3  209.72  5366.2  208.94  5398.9  206.36  5418.8  206.36
    5423  208.69  5458.9  209.08  5628.6  211.27    5678  210.22  5926.2  212.03
  6138.5  215.05  6173.6  217.26  6202.1  215.64  6258.9  216.98  6350.8  216.58
  6421.9  218.32  6563.2  225.04    6762  228.05  7044.6  228.69  7406.1  238.37
#Mann= 7 ,-1 , 0
  4250.4     .17       0  4255.3     .11       0  4298.4     .17       0
  4983.1     .09       0  5019.3     .12       0  5366.2     .12       0
  5458.9     .12       0
Bank Sta=4983.1,5019.3
XS Rating Curve= 0 ,0
Exp/Cntr=0.3,0.1

Type RM Length L Ch R = 1 ,4740    ,1176,1176,1176
BEGIN DESCRIPTION:
MCDONALD CREEK 8.0
END DESCRIPTION:
XS GIS Cut Line= 3
      3775701.22     10208376.63      3775109.71     10208059.84
       3771927.3     10210206.27
#Sta/Elev= 30
    4329  235.36  4542.3  234.28  4808.1  213.14  4881.9  208.99    4964  208.86
  4979.4  207.85  4981.7  205.24  5001.6  205.24  5009.7  208.29  5066.7  209.07
  5087.2  208.19  5786.3  207.08  6047.9  207.12    6125  208.67  6169.9   214.9
  6184.3   213.3  6241.9  215.72  6370.8  225.75  6730.6  225.19  6760.5  219.03
  6796.5  218.14  6883.4  220.54  6905.1  226.02  7105.3  227.79  7246.9  224.38
  7414.6  226.83  7869.7  223.12  7890.7  225.01  8766.3  225.98  8838.6   226.7
#Mann= 10 ,-1 , 0
    4329     .17       0  4808.1     .15       0  4881.9     .09       0
  5066.7     .15       0  5087.2     .11       0  5786.3     .15       0
  6047.9     .11       0  6905.1     .17       0  7246.9     .11       0
  8766.3     .17       0
Bank Sta=4881.9,5066.7
XS Rating Curve= 0 ,0
Exp/Cntr=0.3,0.1

Type RM Length L Ch R = 1 ,3564    ,468,468,468
BEGIN DESCRIPTION:
MCDONALD CREEK 7.0
END DESCRIPTION:
XS GIS Cut Line= 3
      3775767.88      10208211.1      3774798.94     10207103.24
      3771132.77     10209451.23
#Sta/Elev= 30
  3528.2  237.17  3571.7  236.79  3728.7  232.54  3955.9  215.45  4059.6  208.76
  4130.6  207.26  4299.1  205.93  4343.1  205.45  4506.3  206.56    4591  204.01
  4754.1  206.22  4825.3  203.66  4966.7  204.95  4985.2  202.64  5021.4  205.28
  5333.4  203.98  5527.1   206.3  5616.6  205.58  5927.9  205.76  6490.1  206.98
  6568.8  204.87  6961.4  211.28  7162.6  215.97  7532.9  216.22  8022.1  218.36
  8332.6  219.67  8336.5  219.56  8988.6  220.76  9061.3   222.9  9353.6  221.43
#Mann= 16 ,-1 , 0
  3528.2     .17       0  3571.7     .11       0  3728.7     .17       0
  3955.9     .11       0  4130.6     .15       0  4299.1     .11       0
  4343.1     .15       0  4754.1     .07       0  5527.1     .11       0
  5616.6     .11       0  5927.9     .15       0  6961.4     .17       0
  7532.9     .15       0  8022.1     .17       0  8332.6     .11       0
  8336.5     .17       0
Bank Sta=4754.1,5527.1
XS Rating Curve= 0 ,0
Exp/Cntr=0.3,0.1

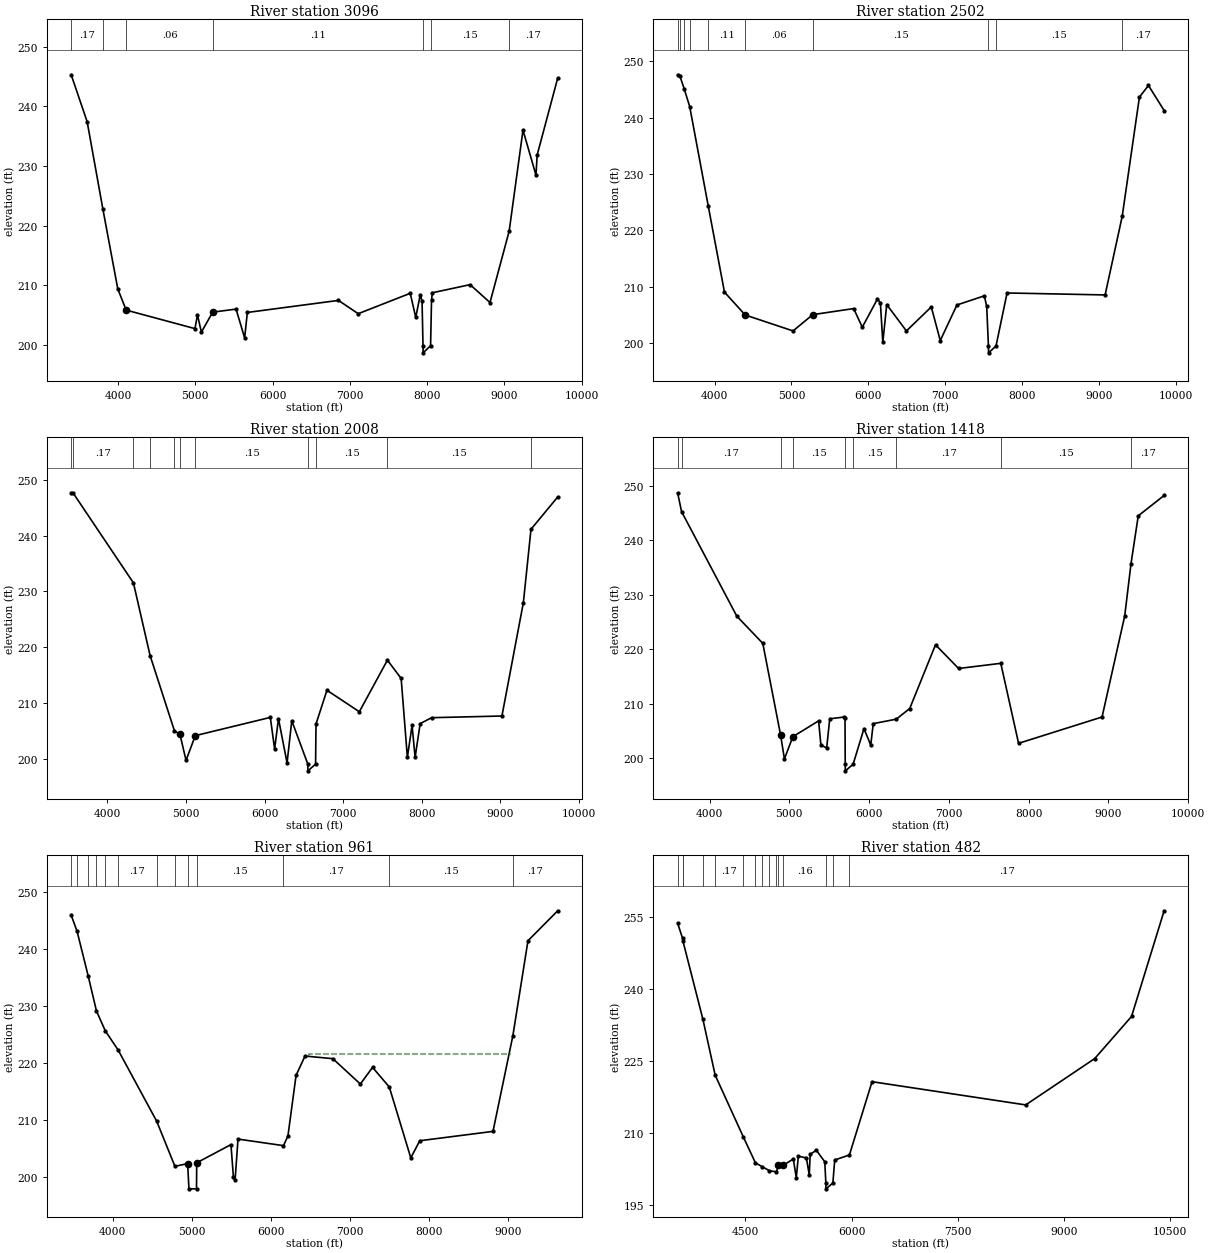
Type RM Length L Ch R = 1 ,3096    ,594,594,594
BEGIN DESCRIPTION:
MCDONALD CREEK 6.0
END DESCRIPTION:
XS GIS Cut Line= 3
      3776380.06     10207498.17      3774972.94     10206720.96
       3770377.5     10205779.43
#Sta/Elev= 30
  3392.5   245.3  3599.3  237.43  3801.9  222.85  3995.7  209.41    4104 205.856
  4994.7  202.75  5027.5  205.05    5078  202.15  5224.1  205.51  5526.7  206.02
  5638.1  201.19  5672.9  205.46  6852.8  207.48    7108  205.25  7781.7  208.67
  7853.1  204.62  7911.7  208.44  7934.8  207.33    7947  199.89  7948.5  198.69
  8045.2  199.89  8057.3  207.48  8068.1  208.76    8557  210.12  8814.3  207.12
  9062.4  219.09  9241.4  236.02  9409.3  228.49  9425.1  231.87  9690.9  244.75
#Mann= 7 ,-1 , 0
  3392.5     .17       0  3801.9     .11       0    4104     .06       0
  5224.1     .11       0    7947     .12       0  8045.2     .15       0
  9062.4     .17       0
Bank Sta=4104,5224.1
XS Rating Curve= 0 ,0
Exp/Cntr=0.3,0.1

Type RM Length L Ch R = 1 ,2502    ,494,494,494
BEGIN DESCRIPTION:
MCDONALD CREEK 5.0
END DESCRIPTION:
XS GIS Cut Line= 3
      3776517.83     10207361.06      3775398.26     10206392.78
      3770663.92     10205362.75
#Sta/Elev= 30
  3519.8  247.62  3550.7  247.35  3604.8  245.16    3677  241.98  3919.2  224.25
  4129.1  209.03  4398.9  204.97  5020.9  202.14  5276.7  205.03  5808.9  206.11
  5920.8   202.8  6117.2  207.79  6156.1  207.14  6187.6  200.11  6238.7  206.81
  6494.7  202.14    6818   206.4  6934.6  200.43  7151.5  206.75  7507.7  208.37
  7538.4  206.48  7560.9  199.45  7562.4  198.25  7659.3  199.45  7803.1  208.88
  9077.8  208.53    9300  222.49  9523.8  243.66  9641.4  245.72  9845.1  241.27
#Mann= 10 ,-1 , 0
  3519.8     .11       0  3550.7     .17       0  3604.8     .11       0
    3677     .17       0  3919.2     .11       0  4398.9     .06       0
  5276.7     .15       0  7560.9     .12       0  7659.3     .15       0
    9300     .17       0
Bank Sta=4398.9,5276.7
XS Rating Curve= 0 ,0
Exp/Cntr=0.3,0.1

Type RM Length L Ch R = 1 ,2008    ,590,590,590
BEGIN DESCRIPTION:
MCDONALD CREEK 4.0
END DESCRIPTION:
XS GIS Cut Line= 3
      3777226.46     10206117.96      3775768.75     10206229.86
      3771354.01     10204529.42
#Sta/Elev= 30
    3538  247.64  3564.5  247.56  4330.2  231.54  4542.3  218.55  4852.8  205.07
  4922.1  204.49    5000  199.81  5117.7  204.23  6072.8  207.49  6127.5  201.84
  6176.7  207.25  6285.9  199.35  6345.9   206.9  6550.3  199.14  6551.8  197.94
    6649  199.14  6654.3  206.31  6793.5  212.34  7205.8   208.5  7563.1  217.72
    7738  214.46  7817.2  200.36  7877.2  206.05  7915.8  200.33    7980  206.38
  8125.6  207.44  9020.9  207.74  9293.9  228.02  9390.7  241.12  9730.9  246.89
#Mann= 11 ,-1 , 0
    3538     .11       0  3564.5     .17       0  4330.2     .11       0
  4542.3     .17       0  4852.8     .15       0  4922.1     .06       0
  5117.7     .15       0  6550.3     .12       0    6649     .15       0
  7563.1     .15       0  9390.7     .17       0
#XS Ineff= 2 , 0
       0                  6793.5       0  212.34
Permanent Ineff=
       F       F
Bank Sta=4922.1,5117.7
XS Rating Curve= 0 ,0
Exp/Cntr=0.3,0.1

Type RM Length L Ch R = 1 ,1418    ,457,457,457
BEGIN DESCRIPTION:
MCDONALD CREEK 3.0
END DESCRIPTION:
XS GIS Cut Line= 3
      3777278.49     10206039.84      3775918.28     10205707.61
      3771406.15     10204399.22
#Sta/Elev= 30
  3599.8  248.77  3649.4  245.31  4341.6  226.09  4667.6  221.08    4890 204.284
  4938.7  199.83  5044.4  203.92  5367.3  206.83  5395.7  202.42    5468  201.83
  5506.8  207.21  5685.1  207.53    5698  207.43  5700.8  198.84  5702.3  197.64
  5799.5  198.84  5935.7   205.4  6020.8  202.38    6052  206.32  6340.3  207.14
  6509.3   209.1  6832.3  220.82  7121.7  216.46  7650.5  217.41  7873.5   202.7
    8920  207.54  9204.1  226.13  9282.9  235.74  9373.5  244.53    9698  248.28
#Mann= 9 ,-1 , 0
  3599.8     .11       0  3649.4     .17       0    4890     .06       0
  5044.4     .15       0  5700.8     .12       0  5799.5     .15       0
  6340.3     .17       0  7650.5     .15       0  9282.9     .17       0
#XS Ineff= 2 , 0
       0                  6832.3       0  220.82
Permanent Ineff=
       F       F
Bank Sta=4890,5044.4
XS Rating Curve= 0 ,0
Exp/Cntr=0.3,0.1

Type RM Length L Ch R = 1 ,961     ,479,479,479
BEGIN DESCRIPTION:
MCDONALD CREEK 2.0
END DESCRIPTION:
XS GIS Cut Line= 3
      3777343.65     10205922.67      3775927.21     10205352.75
       3771432.5     10204269.09
#Sta/Elev= 30
  3473.2  245.92  3548.1  243.07  3688.1  235.26  3792.9   229.1    3905  225.61
  4066.6  222.26  4554.4  209.76  4784.5  201.85  4945.4  202.33  4961.8   197.9
  5057.5   197.9 5060.03  202.47  5492.9  205.66  5523.9  199.99  5545.1   199.4
  5581.8  206.63  6156.9  205.48  6213.1  207.17    6316  217.81  6429.2   221.2
  6780.9  220.74  7128.6  216.29  7282.9  219.21  7494.5  215.77  7766.4  203.33
  7879.6  206.34  8805.4  207.98  9056.8  224.78  9247.5  241.43  9623.5  246.69
#Mann= 13 ,-1 , 0
  3473.2     .11       0  3548.1     .17       0  3688.1     .11       0
  3792.9     .17       0    3905     .11       0  4066.6     .17       0
  4554.4     .11       0  4784.5     .15       0  4945.4     .06       0
 5060.03     .15       0  6156.9     .17       0  7494.5     .15       0
  9056.8     .17       0
#XS Ineff= 2 ,-1
  5581.8  6213.1  206.63  6477.3  9037.9  221.57
Permanent Ineff=
       F       F
Bank Sta=4945.4,5060.03
XS Rating Curve= 0 ,0
Exp/Cntr=0.3,0.1

Type RM Length L Ch R = 1 ,482     ,0,0,0
BEGIN DESCRIPTION:
MCDONALD CREEK 1.0
END DESCRIPTION:
XS GIS Cut Line= 3
      3777577.99     10205115.36      3776132.53      10204942.1
      3771132.77      10202862.8
#Sta/Elev= 30
  3544.2   253.8  3613.7  250.66  3620.3  250.02  3901.6  233.75  4074.6  222.12
  4470.4   209.3  4643.8  203.82  4742.7  203.01  4841.7  202.19  4940.7  201.96
    4968  203.41  5036.9  203.33  5178.4  204.65  5220.1  200.72  5249.4  205.22
  5362.5  204.87  5403.3  201.34  5416.6  205.61  5503.3  206.47  5622.4  204.06
    5638  199.62  5639.5  198.42  5736.7  199.62  5763.2  204.44  5970.4  205.47
  6290.1  220.75  8459.9  215.91  9434.7  225.57  9954.5  234.34 10414.9  256.37
#Mann= 15 ,-1 , 0
  3544.2     .17       0  3613.7     .11       0  3620.3     .17       0
  3901.6     .11       0  4074.6     .17       0  4470.4     .11       0
  4643.8     .17       0  4742.7     .11       0  4841.7     .17       0
  4940.7     .15       0    4968     .06       0  5036.9     .16       0
    5638     .12       0  5736.7     .15       0  5970.4     .17       0
Bank Sta=4968,5036.9
XS Rating Curve= 0 ,0
Exp/Cntr=0.3,0.1

Chan Stop Cuts=-1
Use User Specified Reach Order=0
Composite Channel Slope=5