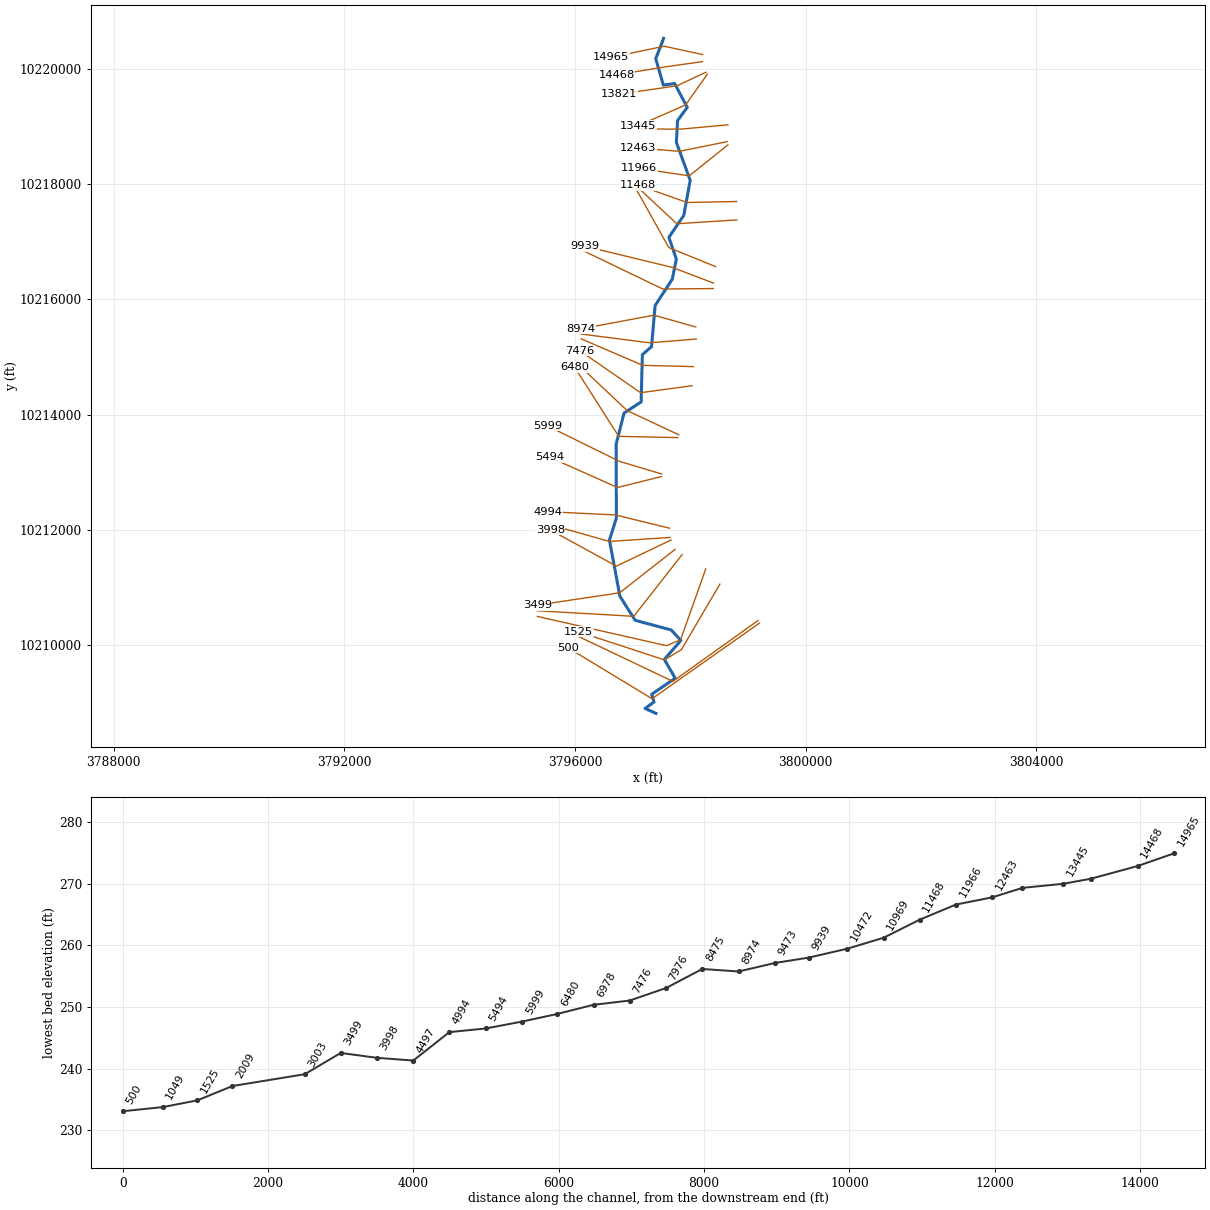
--- PERSIMMON CREEK.prj (project) ---

Proj Title=PERSIMMON CREEK Base Level Engineering
Current Plan=p01
Default Exp/Contr=0.3,0.1
English Units
Geom File=g01
Flow File=f01
Plan File=p01
Y Axis Title=Elevation
X Axis Title(PF)=Main Channel Distance
X Axis Title(XS)=Station
BEGIN DESCRIPTION:
PERSIMMON CREEK
END DESCRIPTION:
DSS Export Rating Curves= 0
DSS Export Rating Curve Sorted= 0
DSS Export Volume Flow Curves= 0
DXF OffsetX= 0
DXF OffsetY= 0
DXF ScaleX= 1
DXF ScaleY= 10

--- PERSIMMON CREEK.p01 (plan) ---

Plan Title=Multiple Run
Short Identifier=Multiple
Geom File=g01
Flow File=f01
Subcritical Flow
K Sum by GR= 0
Std Step Tol= 0.01
Critical Tol= 0.01
Num of Std Step Trials= 20
Max Error Tol= 0.3
Flow Tol Ratio= 0.001
Split Flow NTrial= 30
Split Flow Tol= 0.02
Split Flow Ratio= 0.02
Log Output Level= 0
Friction Slope Method= 1
Unsteady Friction Slope Method= 2
Unsteady Bridges Friction Slope Method= 1
Parabolic Critical Depth
Global Vel Dist=  1 , 1 , 1
Global Log Level= 0
CheckData=True
Encroach Param= -1, 0, 0, 0
BEGIN DESCRIPTION:
Multiple Run
END DESCRIPTION:

--- PERSIMMON CREEK.f01 (steady flow) ---

Flow Title=Multiple
Program Version=4.10
Number of Profiles= 7
Profile Names=10-year,25-year,50-year,1pct_min,100-year,1pct_plu,500-year
River Rch & RM=PERSIMMON CREEK,Reach-1         ,14965
    1984    2821    3940    1802    5443   16438   10753
River Rch & RM=PERSIMMON CREEK,Reach-1         ,10472
    2189    3117    4356    1993    6019   18177   11896
River Rch & RM=PERSIMMON CREEK,Reach-1         ,3998
    2380    3414    4792    2203    6652   20089   13265
Boundary for River Rch & Prof#=PERSIMMON CREEK,Reach-1         , 1
Up Type= 0
Dn Type= 3
Dn Slope=0.005
Boundary for River Rch & Prof#=PERSIMMON CREEK,Reach-1         , 2
Up Type= 0
Dn Type= 3
Dn Slope=0.005
Boundary for River Rch & Prof#=PERSIMMON CREEK,Reach-1         , 3
Up Type= 0
Dn Type= 3
Dn Slope=0.005
Boundary for River Rch & Prof#=PERSIMMON CREEK,Reach-1         , 4
Up Type= 0
Dn Type= 3
Dn Slope=0.005
Boundary for River Rch & Prof#=PERSIMMON CREEK,Reach-1         , 5
Up Type= 0
Dn Type= 3
Dn Slope=0.005
Boundary for River Rch & Prof#=PERSIMMON CREEK,Reach-1         , 6
Up Type= 0
Dn Type= 3
Dn Slope=0.005
Boundary for River Rch & Prof#=PERSIMMON CREEK,Reach-1         , 7
Up Type= 0
Dn Type= 3
Dn Slope=0.005
DSS Import GetInterval= 0
DSS Import GetPeak= 0
DSS Import FillOption= 0

--- PERSIMMON CREEK.g01 (geometry) ---

Geom Title=Existing Conditions
Program Version=4.10

River Reach=PERSIMMON CREEK ,Reach-1
Reach XY= 30
      3797537.23     10220530.96      3797401.04     10220177.75
      3797532.59     10219718.12      3797727.37     10219747.65
      3797947.13     10219333.52      3797779.39     10219104.54
       3797758.5     10218725.36      3797998.23     10218066.84
       3797886.7     10217458.19      3797628.61     10217077.63
      3797758.08     10216699.81      3797687.63     10216351.15
      3797389.96     10215895.19      3797327.49     10215180.15
      3797168.66     10215041.78      3797147.26     10214221.14
      3796851.31     10214028.46      3796713.76     10213489.76
      3796718.32     10212207.21      3796597.81     10211824.49
      3796779.56     10210849.31      3797043.45     10210432.12
       3797668.2     10210264.51      3797837.33     10210082.56
      3797549.49     10209753.32      3797738.25     10209427.65
      3797330.27     10209147.71       3797371.5     10209015.33
      3797215.25     10208902.48      3797403.49      10208816.8

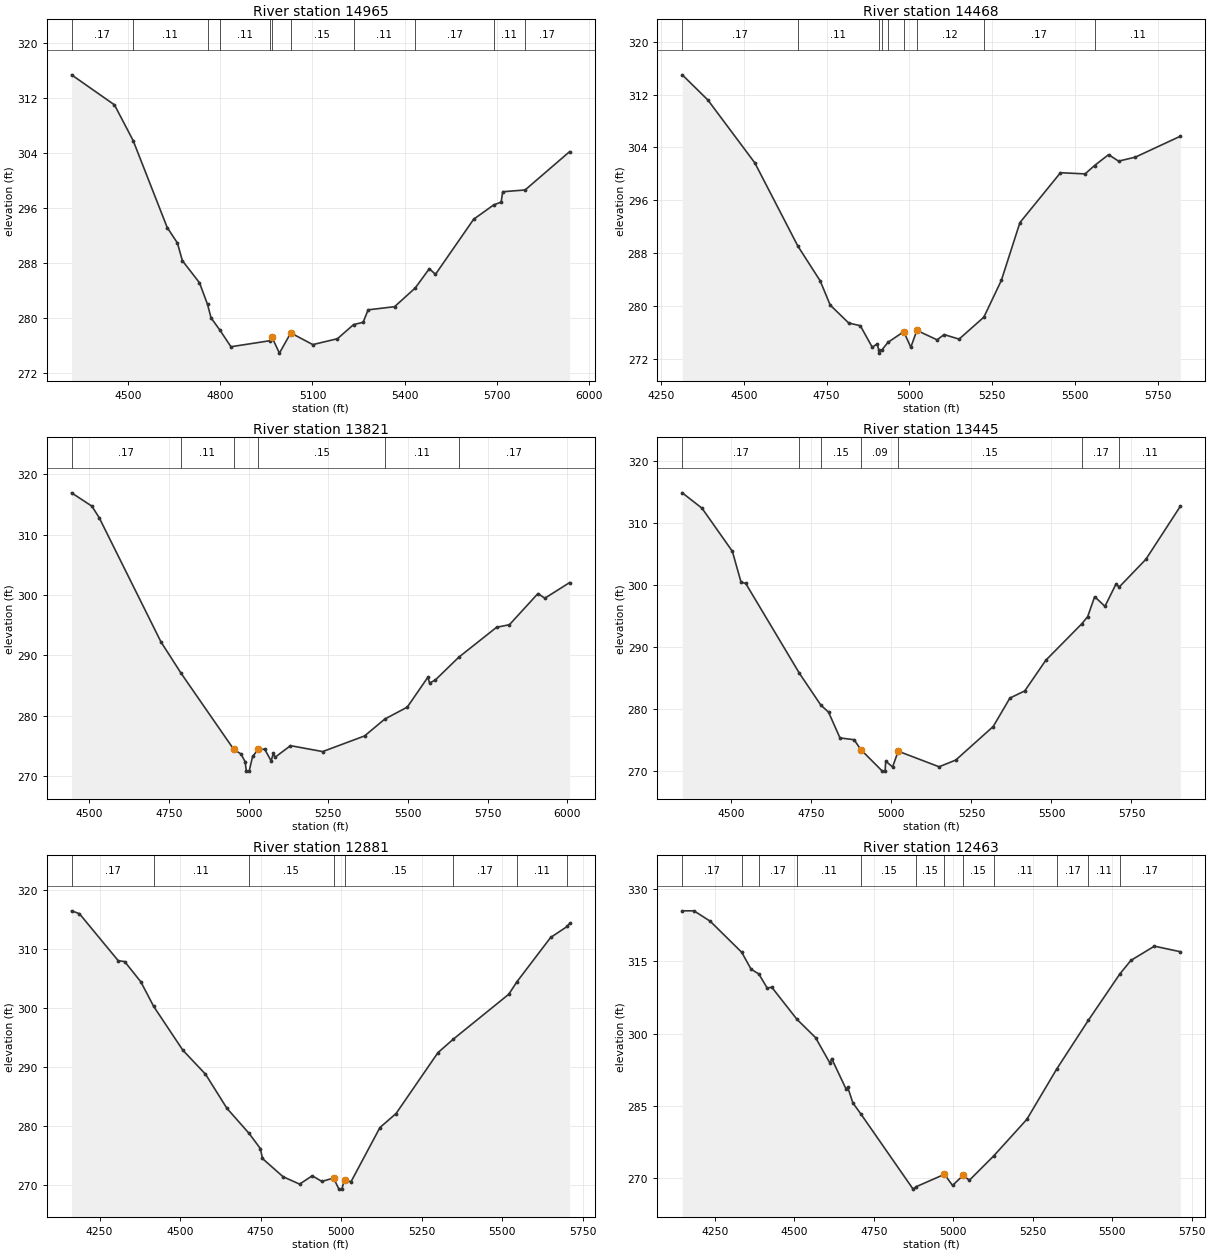
Type RM Length L Ch R = 1 ,14965   ,497,497,497
BEGIN DESCRIPTION:
PERSIMMON CREEK 28.0
END DESCRIPTION:
XS GIS Cut Line= 3
      3798214.04     10220249.69      3797546.73      10220394.3
      3796631.35     10220200.87
#Sta/Elev= 30
  4317.2  315.42  4456.6  311.05  4517.3  305.85    4628  293.19  4661.2  290.94
  4677.2  288.37  4732.8  285.16  4759.1  281.99  4770.5  280.04  4798.7  278.29
  4835.1  275.84  4960.7  276.71  4968.2  277.24  4992.6  274.91  5029.5  277.85
  5101.1  276.15  5181.3  277.01  5233.7  279.07  5264.6  279.39  5280.8  281.21
  5366.8  281.67  5433.9  284.39  5479.7   287.2  5499.7  286.38  5623.8   294.4
  5689.1  296.49  5713.1  296.89  5718.2   298.4    5791  298.66  5935.6  304.24
#Mann= 11 ,-1 , 0
  4317.2     .17       0  4517.3     .11       0  4759.1     .15       0
  4798.7     .11       0  4960.7     .15       0  4968.2     .09       0
  5029.5     .15       0  5233.7     .11       0  5433.9     .17       0
  5689.1     .11       0    5791     .17       0
#XS Ineff= 2 , 0
       0                  5280.8       0  281.21
Permanent Ineff=
       F       F
Bank Sta=4968.2,5029.5
XS Rating Curve= 0 ,0
Exp/Cntr=0.3,0.1

Type RM Length L Ch R = 1 ,14468   ,647,647,647
BEGIN DESCRIPTION:
PERSIMMON CREEK 27.0
END DESCRIPTION:
XS GIS Cut Line= 3
      3798209.97     10220126.88        3797531.     10220030.35
      3796724.04     10219897.65
#Sta/Elev= 30
  4314.2  314.98  4391.5  311.17  4533.3  301.65  4663.2  289.06  4730.5  283.81
  4760.8  280.14  4816.8  277.42  4851.7  277.02  4887.7  273.76  4902.2  274.26
  4907.5  273.37    4908  272.87  4917.1  273.37  4935.3  274.51    4983  276.12
  5004.1  273.75  5022.4  276.31  5083.6  274.88  5104.5  275.68  5149.9  274.99
  5224.7  278.32  5277.4  283.87  5333.5  292.62    5456  300.17  5530.2  299.99
  5558.9  301.26  5601.1   302.9  5631.5  301.92  5682.2  302.53  5817.8  305.69
#Mann= 9 ,-1 , 0
  4314.2     .17       0  4663.2     .11       0  4907.5     .12       0
  4917.1     .11       0  4935.3     .15       0    4983     .07       0
  5022.4     .12       0  5224.7     .17       0  5558.9     .11       0
Bank Sta=4983,5022.4
XS Rating Curve= 0 ,0
Exp/Cntr=0.3,0.1

Type RM Length L Ch R = 1 ,13821   ,376,376,376
BEGIN DESCRIPTION:
PERSIMMON CREEK 26.0
END DESCRIPTION:
XS GIS Cut Line= 3
       3798271.4     10219942.69      3797767.82     10219707.49
      3796770.94     10219562.26
#Sta/Elev= 30
  4444.2  316.91    4508   314.7  4530.8   312.8  4724.7  292.22    4788  287.01
  4953.2  274.41    4976  273.64  4988.9  272.36  4992.8   270.8  5001.6   270.8
  5012.5  273.25  5030.3   274.4  5050.5  274.43  5070.7  272.48  5077.5  273.81
  5082.5  273.08  5131.3  275.02  5232.4  274.04  5363.8  276.63  5427.4  279.43
  5497.8   281.4  5562.8  286.38  5567.8  285.38  5586.1  285.91    5659  289.65
  5778.1  294.63  5818.5  295.06    5908  300.22  5929.7  299.45  6007.4  302.04
#Mann= 6 ,-1 , 0
  4444.2     .17       0    4788     .11       0  4953.2     .07       0
  5030.3     .15       0  5427.4     .11       0    5659     .17       0
Bank Sta=4953.2,5030.3
XS Rating Curve= 0 ,0
Exp/Cntr=0.3,0.1

Type RM Length L Ch R = 1 ,13445   ,564,564,564
BEGIN DESCRIPTION:
PERSIMMON CREEK 25.0
END DESCRIPTION:
XS GIS Cut Line= 3
       3798295.9     10219909.89      3797919.52     10219375.67
      3797092.64     10219013.54
#Sta/Elev= 30
  4346.5   314.9  4408.1  312.42    4503  305.46    4530   300.5  4544.8  300.27
  4712.6  285.77  4779.5  280.64  4803.5  279.51  4839.2  275.35  4883.3  275.06
  4904.5  273.46  4971.5  269.99  4980.3  269.99  4982.1  271.61  5003.6  270.66
  5021.1  273.21  5148.9  270.69  5201.1  271.78    5318  277.19  5370.2  281.78
  5416.7  282.94  5482.2  287.87  5594.3  293.74  5613.2  294.92    5635  298.14
  5667.2  296.59  5701.5  300.16  5711.9  299.71    5795  304.17  5902.7  312.73
#Mann= 7 ,-1 , 0
  4346.5     .17       0  4712.6     .11       0  4779.5     .15       0
  4904.5     .09       0  5021.1     .15       0  5594.3     .17       0
  5711.9     .11       0
Bank Sta=4904.5,5021.1
XS Rating Curve= 0 ,0
Exp/Cntr=0.3,0.1

Type RM Length L Ch R = 1 ,12881   ,418,418,418
BEGIN DESCRIPTION:
PERSIMMON CREEK 24.0
END DESCRIPTION:
XS GIS Cut Line= 3
      3798652.07     10219029.84      3797818.61     10218954.06
      3797108.83     10218960.25
#Sta/Elev= 30
  4163.1  316.52  4187.4  316.04  4307.9  308.07    4328  307.91  4378.2  304.48
    4418  300.32  4508.7  292.88    4579  288.82  4645.4  283.04  4714.4  278.77
  4749.7  276.18  4755.8  274.52    4820  271.42  4871.3  270.17  4910.4  271.58
  4940.5  270.63  4976.7   271.2  4993.4  269.32  5002.4  269.32  5010.8  270.94
  5030.8  270.56  5120.8  279.77  5170.8  282.14  5300.8  292.46  5348.7  294.76
  5520.8  302.37  5546.2  304.49  5650.8     312  5702.3  313.87  5709.8  314.39
#Mann= 8 ,-1 , 0
  4163.1     .17       0    4418     .11       0  4714.4     .15       0
  4976.7     .09       0  5010.8     .15       0  5348.7     .17       0
  5546.2     .11       0  5702.3     .17       0
Bank Sta=4976.7,5010.8
XS Rating Curve= 0 ,0
Exp/Cntr=0.3,0.1

Type RM Length L Ch R = 1 ,12463   ,497,497,497
BEGIN DESCRIPTION:
PERSIMMON CREEK 23.0
END DESCRIPTION:
XS GIS Cut Line= 3
       3798643.9     10218739.21      3797808.65     10218570.09
      3797096.55     10218628.68
#Sta/Elev= 30
  4147.8  325.43  4184.6  325.43  4235.6  323.28  4334.8  316.84  4364.2  313.34
  4388.6  312.35  4414.9  309.44  4429.4   309.6  4508.2  302.98    4567  299.17
  4612.6  293.85  4617.7  294.82  4663.3  288.48  4668.4  288.85  4684.5  285.63
  4709.9  283.32  4873.9  267.78  4883.4  268.28  4972.6  270.85  4997.9  268.55
  5030.9  270.61    5051  269.63  5127.3  274.65  5231.6  282.23    5326   292.7
  5425.4  302.78  5524.7   312.4  5559.2  315.17  5632.9  318.11  5714.5  316.96
#Mann= 12 ,-1 , 0
  4147.8     .17       0  4334.8     .11       0  4388.6     .17       0
  4508.2     .11       0  4709.9     .15       0  4883.4     .15       0
  4972.6     .09       0  5030.9     .15       0  5127.3     .11       0
    5326     .17       0  5425.4     .11       0  5524.7     .17       0
Bank Sta=4972.6,5030.9
XS Rating Curve= 0 ,0
Exp/Cntr=0.3,0.1

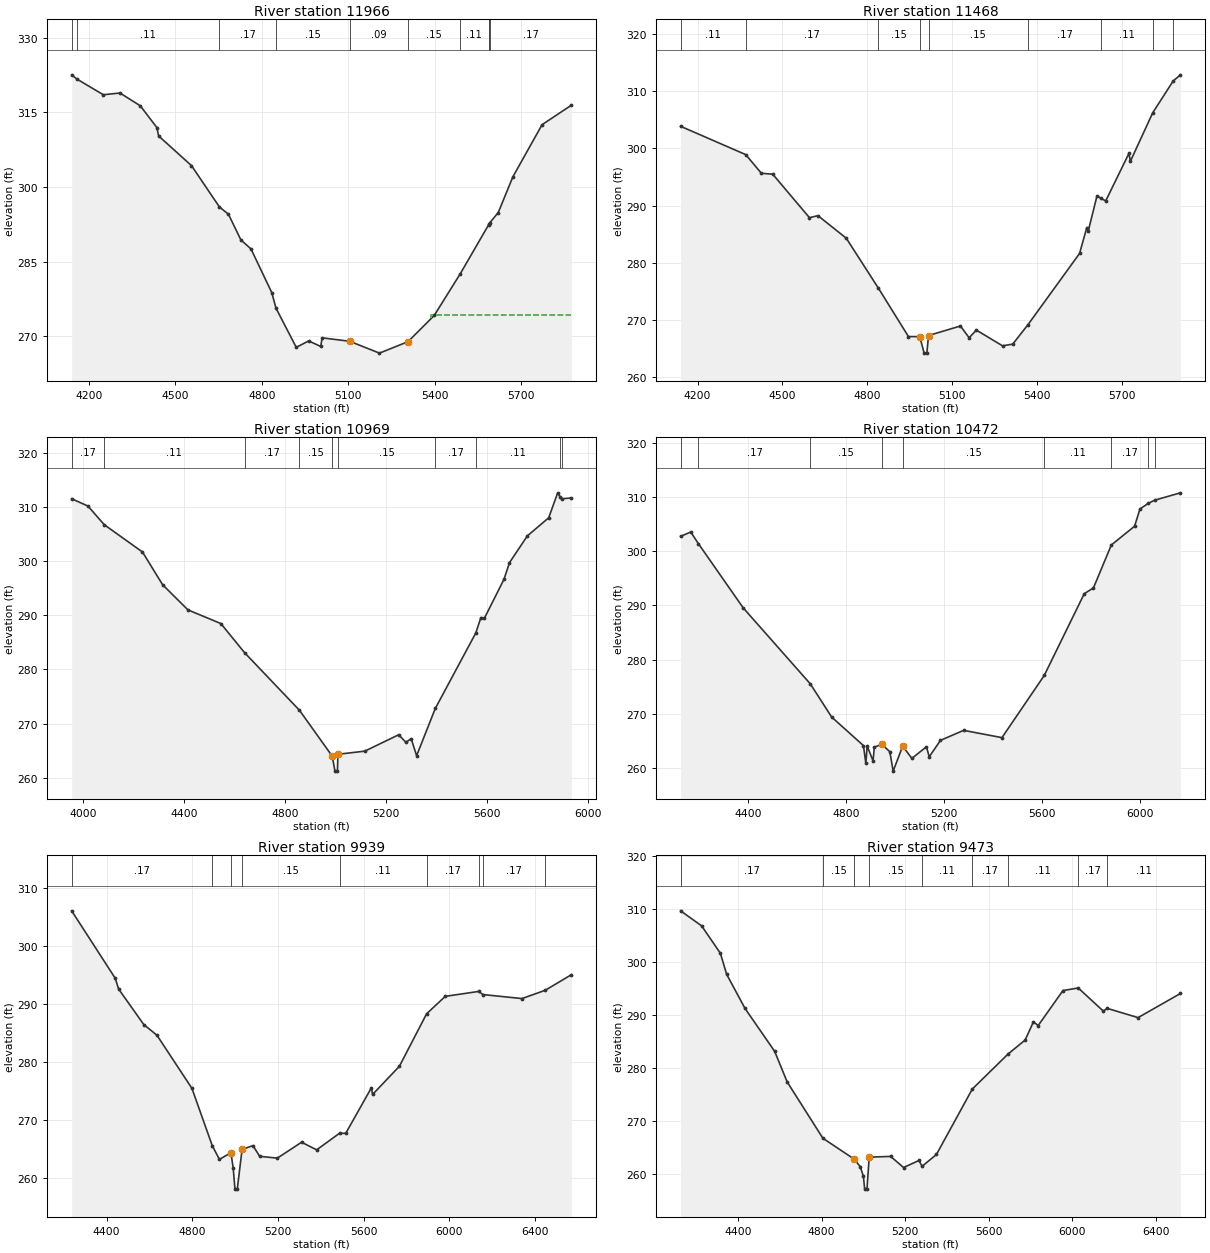
Type RM Length L Ch R = 1 ,11966   ,498,498,498
BEGIN DESCRIPTION:
PERSIMMON CREEK 22.0
END DESCRIPTION:
XS GIS Cut Line= 3
      3798652.05     10218681.89      3797981.71     10218144.59
      3797117.03     10218272.55
#Sta/Elev= 30
  4140.9  322.51  4158.6  321.68  4250.7  318.51  4308.3  318.86  4378.7   316.3
  4436.3  311.93  4442.7  310.22  4556.4  304.28  4653.5  295.96  4684.6  294.52
  4727.6  289.37  4762.8  287.54  4834.8  278.78  4849.5  275.65  4919.7  267.78
  4962.9  269.07  5004.5  267.96  5009.6  269.69    5105     269  5208.3  266.62
  5307.2  268.92  5398.2  274.18  5488.7  282.58  5586.4  292.35    5589  292.62
  5590.6  292.78  5620.2  294.85  5671.1  302.05  5772.2   312.5  5874.1  316.42
#Mann= 10 ,-1 , 0
  4140.9     .17       0  4158.6     .11       0  4653.5     .17       0
  4849.5     .15       0    5105     .09       0  5307.2     .15       0
  5488.7     .11       0  5586.4     .17       0    5589     .11       0
  5590.6     .17       0
#XS Ineff= 2 , 0
       0                    5388       0  274.33
Permanent Ineff=
       F       F
Bank Sta=5105,5307.2
XS Rating Curve= 0 ,0
Exp/Cntr=0.3,0.1

Type RM Length L Ch R = 1 ,11468   ,499,499,499
BEGIN DESCRIPTION:
PERSIMMON CREEK 21.0
END DESCRIPTION:
XS GIS Cut Line= 3
       3798803.5     10217699.47      3797943.87      10217682.2
      3797088.32     10217986.03
#Sta/Elev= 30
  4140.2  303.88  4370.6  298.92  4425.9  295.65  4465.9   295.5  4595.9  287.88
  4625.9  288.24    4726  284.29  4839.1  275.59    4946  267.07    4986  267.06
  5001.5  264.17  5011.1  264.17    5017  267.25  5129.8  268.92  5160.6  266.86
  5186.2   268.2  5278.7  265.45  5314.9  265.75  5368.7  269.15  5551.2  281.62
  5576.7  286.14    5582  285.57  5612.9  291.71  5626.8  291.26  5643.7  290.82
  5725.7  299.13    5731  297.76    5810  306.25  5882.1   311.8  5907.9  312.89
#Mann= 9 ,-1 , 0
  4140.2     .11       0  4370.6     .17       0  4839.1     .15       0
    4986     .09       0    5017     .15       0  5368.7     .17       0
  5626.8     .11       0    5810     .17       0  5882.1     .11       0
Bank Sta=4986,5017
XS Rating Curve= 0 ,0
Exp/Cntr=0.3,0.1

Type RM Length L Ch R = 1 ,10969   ,497,497,497
BEGIN DESCRIPTION:
PERSIMMON CREEK 20.0
END DESCRIPTION:
XS GIS Cut Line= 3
      3798807.64     10217380.19      3797765.77     10217313.57
      3797081.55     10217951.98
#Sta/Elev= 30
    3956  311.53  4020.7  310.17  4085.2  306.73  4236.4   301.7  4316.5  295.64
  4416.7     291    4547  288.48  4640.8  283.11  4858.5  272.46  4987.9  264.01
    4999  261.23  5008.7  261.23  5010.8  264.34  5117.2  264.92  5251.5  267.95
  5279.8  266.55  5300.9  267.22  5322.4  264.08  5396.4   272.8    5557  286.76
  5576.9  289.57    5591  289.47  5668.7  296.67  5690.2  299.72  5761.1  304.67
  5845.6  308.01  5881.2  312.62  5890.4  311.91  5898.7  311.53  5935.8  311.67
#Mann= 10 ,-1 , 0
    3956     .17       0  4085.2     .11       0  4640.8     .17       0
  4858.5     .15       0  4987.9     .09       0  5010.8     .15       0
  5396.4     .17       0    5557     .11       0  5890.4     .17       0
  5898.7     .11       0
Bank Sta=4987.9,5010.8
XS Rating Curve= 0 ,0
Exp/Cntr=0.3,0.1

Type RM Length L Ch R = 1 ,10472   ,533,533,533
BEGIN DESCRIPTION:
PERSIMMON CREEK 19.0
END DESCRIPTION:
XS GIS Cut Line= 3
      3798439.21     10216569.68      3797627.95     10216899.38
      3797059.81     10217916.23
#Sta/Elev= 30
  4124.3  302.71  4165.7  303.51  4197.3  301.34  4379.9  289.53  4653.9  275.53
    4741  269.42  4870.6  264.17  4880.5  260.91  4885.9  264.09  4909.9  261.35
  4915.3  263.88  4946.1  264.39  4978.5  263.03    4992  259.46  5030.8  264.05
  5068.4  261.81  5127.8  263.94  5139.4   262.1  5185.2  265.13  5279.8  266.97
  5436.2  265.63  5608.9  277.09  5772.1  292.14  5809.8  293.22  5882.7  301.12
  5977.7  304.58  5999.4  307.74  6033.8   308.8  6061.7   309.4  6164.8  310.73
#Mann= 9 ,-1 , 0
  4124.3     .11       0  4197.3     .17       0  4653.9     .15       0
  4946.1     .09       0  5030.8     .15       0  5608.9     .11       0
  5882.7     .17       0  6033.8     .11       0  6061.7     .17       0
Bank Sta=4946.1,5030.8
XS Rating Curve= 0 ,0
Exp/Cntr=0.3,0.1

Type RM Length L Ch R = 1 ,9939    ,466,466,466
BEGIN DESCRIPTION:
PERSIMMON CREEK 18.0
END DESCRIPTION:
XS GIS Cut Line= 3
       3798402.4     10216283.13      3797689.92     10216555.32
      3796163.23     10216925.81
#Sta/Elev= 30
  4237.3  306.03    4441  294.38  4456.3  292.55    4574  286.41  4635.4  284.57
  4798.8   275.4    4894  265.49  4927.3  263.14  4980.8  264.29  4991.5   261.7
  4999.8  258.01  5010.6  258.01    5033  264.85  5083.7  265.52  5115.3  263.67
  5197.6  263.36  5310.8   266.1  5381.3  264.79  5488.4  267.66  5516.9  267.63
  5637.1  275.51  5642.3  274.34  5767.6  279.21  5894.7  288.27  5981.7  291.27
    6137  292.12  6158.3  291.58  6339.9  290.89  6449.1  292.33    6571  295.02
#Mann= 9 ,-1 , 0
  4237.3     .17       0    4894     .15       0  4980.8     .09       0
    5033     .15       0  5488.4     .11       0  5894.7     .17       0
    6137     .11       0  6158.3     .17       0  6449.1     .11       0
Bank Sta=4980.8,5033
XS Rating Curve= 0 ,0
Exp/Cntr=0.3,0.1

Type RM Length L Ch R = 1 ,9473    ,499,499,499
BEGIN DESCRIPTION:
PERSIMMON CREEK 17.0
END DESCRIPTION:
XS GIS Cut Line= 3
      3798398.23     10216188.99      3797522.96     10216180.77
      3796155.06     10216839.85
#Sta/Elev= 30
  4124.7   309.7  4225.1  306.87  4315.1  301.69  4345.1  297.72  4432.8  291.29
  4575.1  283.16  4635.1  277.38    4806  266.75  4955.1  262.83  4985.1  261.39
    5000  259.57  5006.3  257.14  5017.1  257.14  5027.9  263.18  5130.4  263.32
  5192.7  261.22  5266.1  262.55  5281.2  261.45  5349.8  263.68  5521.8  276.05
  5693.6  282.68  5774.8   285.3  5814.5  288.74  5837.1  288.03  5955.8  294.64
  6028.9  295.13    6149  290.77  6167.7  291.28  6315.5  289.53  6518.4  294.09
#Mann= 9 ,-1 , 0
  4124.7     .17       0    4806     .15       0  4955.1     .09       0
  5027.9     .15       0  5281.2     .11       0  5521.8     .17       0
  5693.6     .11       0  6028.9     .17       0  6167.7     .11       0
Bank Sta=4955.1,5027.9
XS Rating Curve= 0 ,0
Exp/Cntr=0.3,0.1

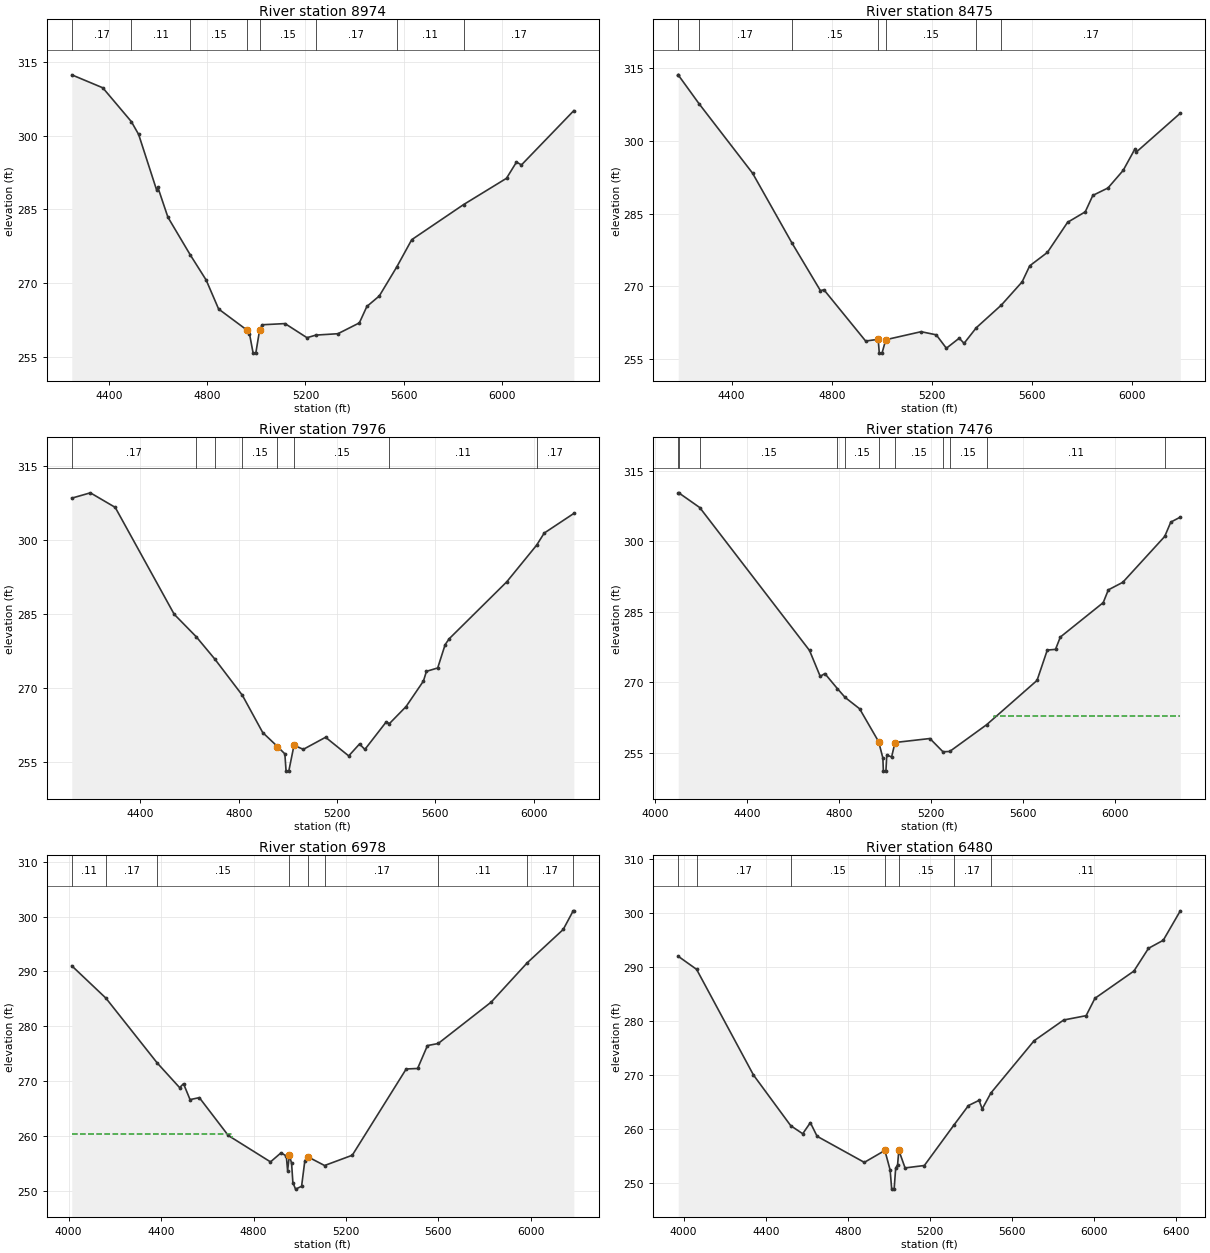
Type RM Length L Ch R = 1 ,8974    ,499,499,499
BEGIN DESCRIPTION:
PERSIMMON CREEK 16.0
END DESCRIPTION:
XS GIS Cut Line= 3
      3798095.35     10215521.76      3797370.55     10215726.98
       3796097.8     10215489.03
#Sta/Elev= 30
  4246.7  312.38  4373.3  309.74  4489.6  302.87  4519.5  300.25  4592.6  288.98
  4597.8   289.5    4639   283.4  4729.8  275.77  4794.9  270.63  4845.8  264.73
  4963.2  260.38  4971.6  259.72  4986.5  255.76  4997.4  255.76  5012.9  260.43
  5023.1  261.53  5116.7  261.77  5206.2   258.9  5242.8  259.43  5332.4  259.71
  5419.8  261.91  5450.4  265.25  5501.2  267.39  5572.4  273.29  5633.5  278.84
  5845.3  285.99  6020.1  291.33  6060.8  294.63  6081.1  294.05  6294.8   305.1
#Mann= 8 ,-1 , 0
  4246.7     .17       0  4489.6     .11       0  4729.8     .15       0
  4963.2     .09       0  5012.9     .15       0  5242.8     .17       0
  5572.4     .11       0  5845.3     .17       0
Bank Sta=4963.2,5012.9
XS Rating Curve= 0 ,0
Exp/Cntr=0.3,0.1

Type RM Length L Ch R = 1 ,8475    ,499,499,499
BEGIN DESCRIPTION:
PERSIMMON CREEK 15.0
END DESCRIPTION:
XS GIS Cut Line= 3
      3798103.58       10215313.      3797293.34      10215247.3
      3796111.41     10215398.78
#Sta/Elev= 30
  4187.1  313.68  4187.7  313.61  4269.9  307.73  4483.8  293.36  4640.1  279.02
  4754.7  269.09  4768.8  269.26  4935.3  258.67  4985.4  259.02  4989.8  256.17
  5000.7  256.17  5015.6  258.94  5156.8   260.6  5217.3  259.95  5257.6  257.18
    5309  259.26  5328.2  258.19  5377.3  261.43  5477.3  266.11    5560  270.89
  5590.3  274.21  5660.9  276.98  5741.5   283.2  5812.1  285.37  5842.3  288.76
  5902.8   290.3  5963.3  293.92  6010.8  298.39  6015.8  297.71  6191.6  305.75
#Mann= 8 ,-1 , 0
  4187.1     .17       0  4187.7     .11       0  4269.9     .17       0
  4640.1     .15       0  4985.4     .09       0  5015.6     .15       0
  5377.3     .11       0  5477.3     .17       0
Bank Sta=4985.4,5015.6
XS Rating Curve= 0 ,0
Exp/Cntr=0.3,0.1

Type RM Length L Ch R = 1 ,7976    ,500,500,500
BEGIN DESCRIPTION:
PERSIMMON CREEK 14.0
END DESCRIPTION:
XS GIS Cut Line= 3
      3798054.45     10214834.07      3797175.43     10214856.17
      3796107.12     10215316.58
#Sta/Elev= 30
  4120.7  308.47  4196.4  309.55  4297.4   306.6  4537.4  284.91  4627.2  280.34
  4703.1  275.79    4815  268.45  4897.5  260.91  4957.6  258.07  4987.6  256.58
  4992.6  253.08  5003.6  253.08  5024.8  258.32  5062.7   257.5  5153.3  259.95
  5247.4  256.17  5291.4  258.59  5313.1  257.48  5399.4  263.03  5413.3  262.74
  5480.9  266.19  5551.4  271.36  5563.6  273.33  5609.4  274.01  5639.8  278.76
  5656.4  279.95  5890.3  291.49  6011.9  298.93  6042.7  301.38  6163.3  305.37
#Mann= 8 ,-1 , 0
  4120.7     .17       0  4627.2     .15       0  4703.1     .17       0
    4815     .15       0  4957.6     .09       0  5024.8     .15       0
  5413.3     .11       0  6011.9     .17       0
#XS Ineff= 2 , 0
       0                  5399.4       0  263.03
Permanent Ineff=
       F       F
Bank Sta=4957.6,5024.8
XS Rating Curve= 0 ,0
Exp/Cntr=0.3,0.1

Type RM Length L Ch R = 1 ,7476    ,498,498,498
BEGIN DESCRIPTION:
PERSIMMON CREEK 13.0
END DESCRIPTION:
XS GIS Cut Line= 3
      3798029.81     10214502.49      3797137.44     10214381.76
       3796082.1     10215111.92
#Sta/Elev= 30
  4099.5  310.36  4101.8  310.36  4193.1  307.22  4670.6  276.76    4717  271.25
  4737.2  271.84  4791.6  268.64  4825.3  266.76  4888.4  264.34  4971.1  257.33
  4989.5  253.87  4991.8  251.05  5002.8  251.05  5006.6  254.51  5027.5  254.06
  5042.4  257.15  5194.1     258  5250.9  255.18  5280.3  255.24  5440.8  260.94
  5660.1  270.38  5704.7  276.85  5740.5     277  5761.4  279.62    5948  286.96
  5970.2  289.68  6033.1  291.29  6215.4  301.06  6241.9  304.12  6283.3  305.18
#Mann= 11 ,-1 , 0
  4099.5     .11       0  4101.8     .17       0  4193.1     .15       0
  4791.6     .11       0  4825.3     .15       0  4971.1     .09       0
  5042.4     .15       0  5250.9     .17       0  5280.3     .15       0
  5440.8     .11       0  6215.4     .17       0
#XS Ineff= 2 , 0
       0                  5473.7       0  262.82
Permanent Ineff=
       F       F
Bank Sta=4971.1,5042.4
XS Rating Curve= 0 ,0
Exp/Cntr=0.3,0.1

Type RM Length L Ch R = 1 ,6978    ,498,498,498
BEGIN DESCRIPTION:
PERSIMMON CREEK 12.0
END DESCRIPTION:
XS GIS Cut Line= 3
      3797800.63     10213651.06      3796907.26     10214069.24
      3796044.52      10214883.2
#Sta/Elev= 30
  4013.6  291.03  4161.3  285.14  4383.6  273.32  4480.4  268.84  4497.1  269.56
  4525.4  266.66  4565.6  267.02  4690.8  260.13  4873.5  255.32  4919.1  256.97
    4942  256.39  4947.5  253.73  4955.2  256.53  4964.8  255.06  4970.3  251.56
  4981.9  250.36    5008  250.87  5022.2  255.56  5036.3  256.22  5107.5  254.66
  5227.3  256.53  5460.7  272.24  5510.1  272.33  5552.6   276.5  5599.1  276.88
  5828.5  284.42  5984.5  291.58    6140  297.64  6183.3  301.04  6186.1  301.04
#Mann= 9 ,-1 , 0
  4013.6     .11       0  4161.3     .17       0  4383.6     .15       0
  4955.2     .09       0  5036.3     .15       0  5107.5     .17       0
  5599.1     .11       0  5984.5     .17       0  6183.3     .11       0
#XS Ineff= 2 , 0
       0  4708.1  260.35               0
Permanent Ineff=
       F       F
Bank Sta=4955.2,5036.3
XS Rating Curve= 0 ,0
Exp/Cntr=0.3,0.1

Type RM Length L Ch R = 1 ,6480    ,481,481,481
BEGIN DESCRIPTION:
PERSIMMON CREEK 11.0
END DESCRIPTION:
XS GIS Cut Line= 3
      3797784.22     10213601.94      3796758.37     10213624.39
      3795995.42     10214821.78
#Sta/Elev= 30
  3973.9  292.05  4063.3  289.63  4340.4  270.04  4522.2  260.63  4580.4  259.15
  4617.5  261.21  4650.4  258.68  4880.5  253.84  4980.5  256.05  5006.1  252.44
  5013.8  248.88  5025.7  248.88  5033.2  252.78  5042.5   253.4  5048.5  256.08
  5078.9  252.81  5172.9  253.26  5315.8   260.7  5387.9  264.38  5439.5  265.34
  5454.7  263.75    5497   266.7  5707.5  276.39  5851.7  280.24  5960.9  281.04
  6003.9  284.26  6193.7  289.31  6264.8  293.53  6336.7  295.02  6419.8  300.48
#Mann= 7 ,-1 , 0
  3973.9     .11       0  4063.3     .17       0  4522.2     .15       0
  4980.5     .09       0  5048.5     .15       0  5315.8     .17       0
    5497     .11       0
#XS Ineff= 2 , 0
       0  4617.5  261.21               0
Permanent Ineff=
       F       F
Bank Sta=4980.5,5048.5
XS Rating Curve= 0 ,0
Exp/Cntr=0.3,0.1

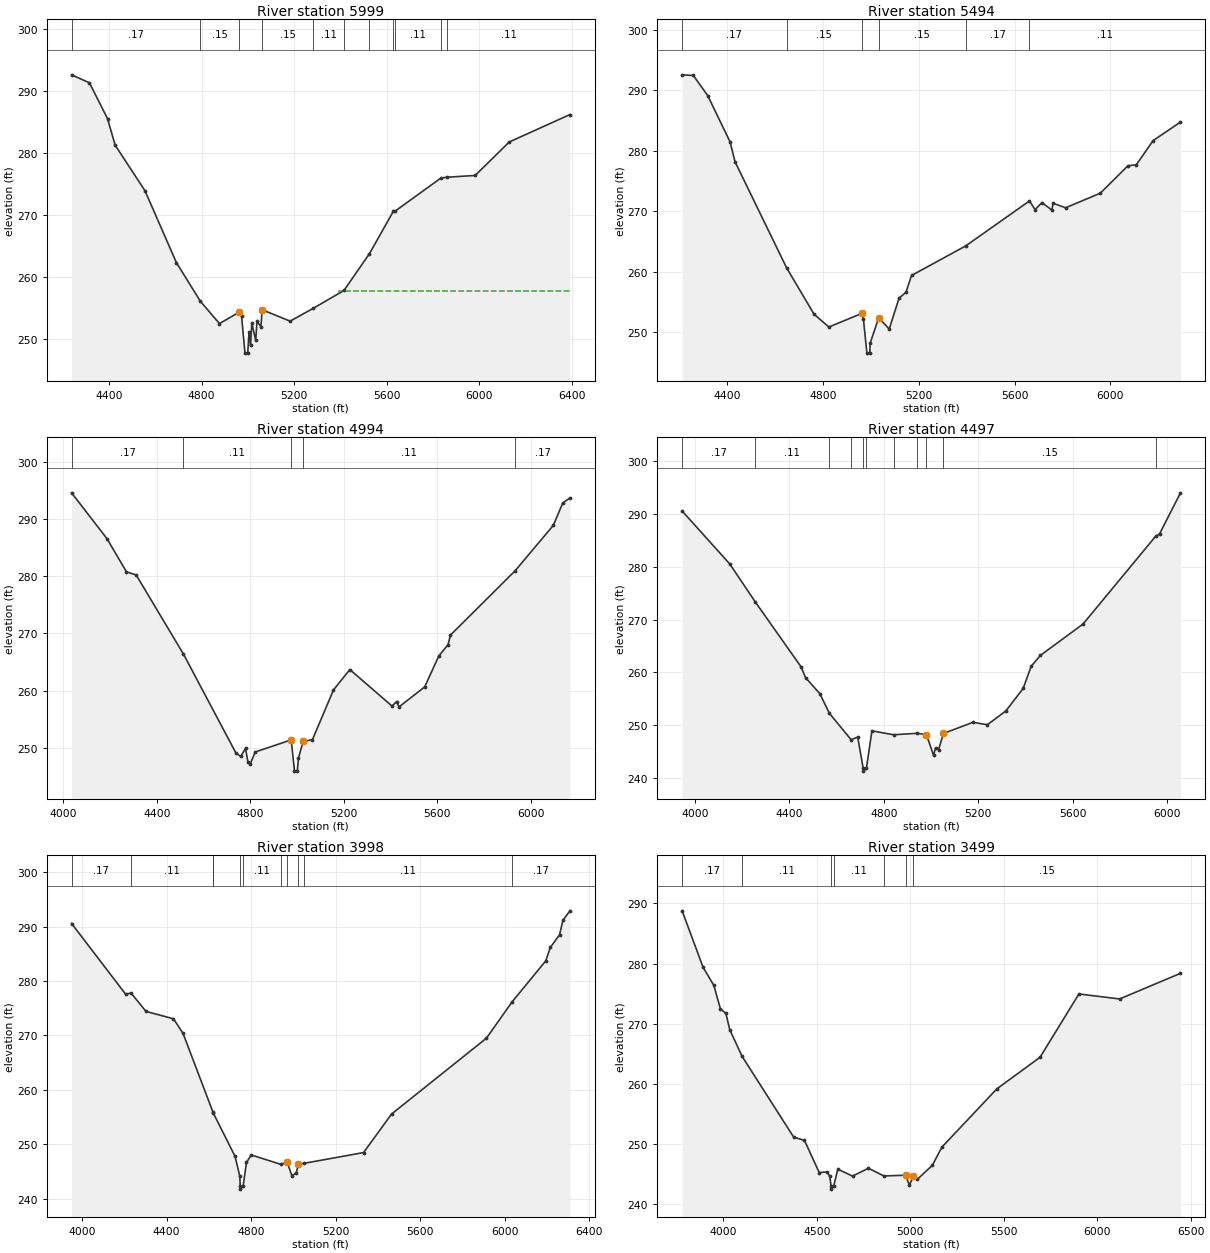
Type RM Length L Ch R = 1 ,5999    ,505,505,505
BEGIN DESCRIPTION:
PERSIMMON CREEK 10.0
END DESCRIPTION:
XS GIS Cut Line= 3
      3797501.84     10212971.54      3796771.61     10213190.31
      3795522.28     10213805.77
#Sta/Elev= 30
  4237.7  292.56  4314.9  291.27  4393.1  285.49  4426.1  281.21    4555  273.86
  4690.8  262.27  4794.7  256.01  4877.1  252.42  4962.2  254.25  4972.6  253.68
  4987.5  247.65  4999.4  247.65  5004.9  251.04  5011.4  248.89    5017  252.51
  5033.9  249.71  5039.4  252.79  5056.3  251.93  5061.9  254.65  5182.6  252.81
  5283.1  254.89  5415.6  257.76  5525.9  263.71  5628.6  270.51  5638.1   270.6
  5834.9  275.91  5862.4  276.04  5982.8  276.32  6130.1  281.72  6392.7  286.15
#Mann= 11 ,-1 , 0
  4237.7     .17       0  4794.7     .15       0  4962.2     .09       0
  5061.9     .15       0  5283.1     .11       0  5415.6     .15       0
  5525.9     .17       0  5628.6     .15       0  5638.1     .11       0
  5834.9     .15       0  5862.4     .11       0
#XS Ineff= 2 , 0
       0                  5393.3       0  257.68
Permanent Ineff=
       F       F
Bank Sta=4962.2,5061.9
XS Rating Curve= 0 ,0
Exp/Cntr=0.3,0.1

Type RM Length L Ch R = 1 ,5494    ,500,500,500
BEGIN DESCRIPTION:
PERSIMMON CREEK 9.0
END DESCRIPTION:
XS GIS Cut Line= 3
      3797501.82     10212926.53      3796738.23     10212736.84
      3795557.42     10213262.19
#Sta/Elev= 30
  4213.2  292.55  4260.1  292.44  4320.3  289.09  4413.1  281.47  4433.7  278.19
  4648.9  260.64  4763.4  252.97  4825.2  250.84    4963  253.09  4969.5  252.14
  4984.1  246.52  4996.1  246.52  4997.6  248.17  5033.2  252.35  5077.2  250.51
  5118.2  255.62  5146.9  256.57  5170.2  259.36  5396.9  264.27  5662.4  271.69
  5685.7  270.26  5714.4  271.42  5755.4  270.19  5760.9  271.31  5812.9  270.56
  5957.8  272.97    6073  277.51  6108.2  277.68    6178  281.67  6292.4  284.74
#Mann= 6 ,-1 , 0
  4213.2     .17       0  4648.9     .15       0    4963     .09       0
  5033.2     .15       0  5396.9     .17       0  5662.4     .11       0
Bank Sta=4963,5033.2
XS Rating Curve= 0 ,0
Exp/Cntr=0.3,0.1

Type RM Length L Ch R = 1 ,4994    ,497,497,497
BEGIN DESCRIPTION:
PERSIMMON CREEK 8.0
END DESCRIPTION:
XS GIS Cut Line= 3
      3797640.95     10212030.07      3796704.22     10212259.85
       3795536.9      10212316.6
#Sta/Elev= 30
  4035.5  294.53  4187.3  286.51  4270.5  280.73    4312  280.19  4514.2  266.38
  4738.9   249.1  4759.4  248.49    4780   249.9  4790.3  247.57  4800.6   247.2
  4821.3  249.27  4975.7  251.39  4989.6  245.93  5001.6  245.93  5006.4  248.15
  5026.4  251.11  5066.5  251.43  5156.6  260.11  5226.6  263.67  5406.9   257.3
  5426.9  258.08  5436.9  257.14    5547  260.64  5607.1  266.02  5647.1  268.03
  5657.1  269.68    5935  280.96  6097.7  288.86  6137.7  292.74  6168.7  293.64
#Mann= 5 ,-1 , 0
  4035.5     .17       0  4514.2     .11       0  4975.7     .06       0
  5026.4     .11       0    5935     .17       0
Bank Sta=4975.7,5026.4
XS Rating Curve= 0 ,0
Exp/Cntr=0.3,0.1

Type RM Length L Ch R = 1 ,4497    ,499,499,499
BEGIN DESCRIPTION:
PERSIMMON CREEK 7.0
END DESCRIPTION:
XS GIS Cut Line= 3
      3797649.12     10211870.41      3796597.96     10211800.18
      3795582.45     10212087.23
#Sta/Elev= 30
  3946.5  290.52  4148.2   280.5  4256.7  273.28  4448.9   261.1  4468.9  258.99
  4529.1  255.98  4569.6  252.26  4661.6  247.26  4689.4  247.76  4712.8  241.82
  4713.3  241.32  4726.1  241.82  4749.6  248.94  4841.2   248.2  4939.9  248.47
  4980.1  248.23  5010.5  244.29  5018.7  245.71  5031.3  245.36  5052.1  248.44
  5176.8  250.55  5238.1   250.1  5316.4  252.71  5389.5  256.96  5423.5  261.15
  5462.7  263.22  5642.9  269.14    5950  285.74  5966.6  286.19  6055.3  293.96
#Mann= 11 ,-1 , 0
  3946.5     .17       0  4256.7     .11       0  4569.6     .15       0
  4661.6     .11       0  4712.8     .08       0  4726.1     .11       0
  4841.2     .15       0  4939.9     .11       0  4980.1     .07       0
  5052.1     .15       0    5950     .17       0
Bank Sta=4980.1,5052.1
XS Rating Curve= 0 ,0
Exp/Cntr=0.3,0.1

Type RM Length L Ch R = 1 ,3998    ,499,499,499
BEGIN DESCRIPTION:
PERSIMMON CREEK 6.0
END DESCRIPTION:
XS GIS Cut Line= 3
      3797665.51     10211825.38      3796719.01     10211371.95
      3795571.27     10212000.55
#Sta/Elev= 30
  3950.5  290.58    4206   277.6  4232.1  277.79  4302.7  274.42  4432.6  273.07
  4477.9  270.38  4618.7  255.99  4619.8  255.84  4724.1  247.77  4746.3  244.15
  4748.7  242.26  4749.2  241.76    4762  242.26  4778.1  246.67  4800.7  248.04
    4941  246.31  4970.4  246.73  4993.1   244.2  5013.5  244.76  5023.9  246.29
  5051.9  246.51    5332  248.48  5464.8  255.57  5913.4   269.5  6035.1  276.19
    6194  283.71  6215.8  286.18  6259.4  288.51  6275.5  291.19  6308.6  292.91
#Mann= 11 ,-1 , 0
  3950.5     .17       0  4232.1     .11       0  4618.7     .15       0
  4619.8     .11       0  4748.7     .12       0    4762     .11       0
    4941     .15       0  4970.4     .07       0  5023.9     .15       0
  5051.9     .11       0  6035.1     .17       0
Bank Sta=4970.4,5023.9
XS Rating Curve= 0 ,0
Exp/Cntr=0.3,0.1

Type RM Length L Ch R = 1 ,3499    ,496,496,496
BEGIN DESCRIPTION:
PERSIMMON CREEK 5.0
END DESCRIPTION:
XS GIS Cut Line= 3
      3797735.16     10211661.68      3796774.69     10210909.09
      3795346.12     10210695.83
#Sta/Elev= 30
  3779.8  288.78  3891.6  279.42  3949.5  276.38  3984.7  272.47  4013.6  271.76
  4034.5  269.04  4099.9  264.63  4376.2  251.19    4434  250.64  4512.7  245.31
  4554.3   245.4  4568.8  244.71  4576.3  243.05  4576.8  242.55  4590.1  243.05
  4612.1  245.87  4690.8  244.71  4775.8  246.02  4858.3  244.74  4974.7  244.86
  4994.8  243.21  5016.2  244.67  5037.2  244.16  5118.1  246.53  5168.7  249.53
  5461.9  259.19  5693.6  264.46  5901.3  274.97  6119.1  274.14  6444.4   278.4
#Mann= 7 ,-1 , 0
  3779.8     .17       0  4099.9     .11       0  4576.3     .08       0
  4590.1     .11       0  4858.3     .15       0  4974.7     .07       0
  5016.2     .15       0
Bank Sta=4974.7,5016.2
XS Rating Curve= 0 ,0
Exp/Cntr=0.3,0.1

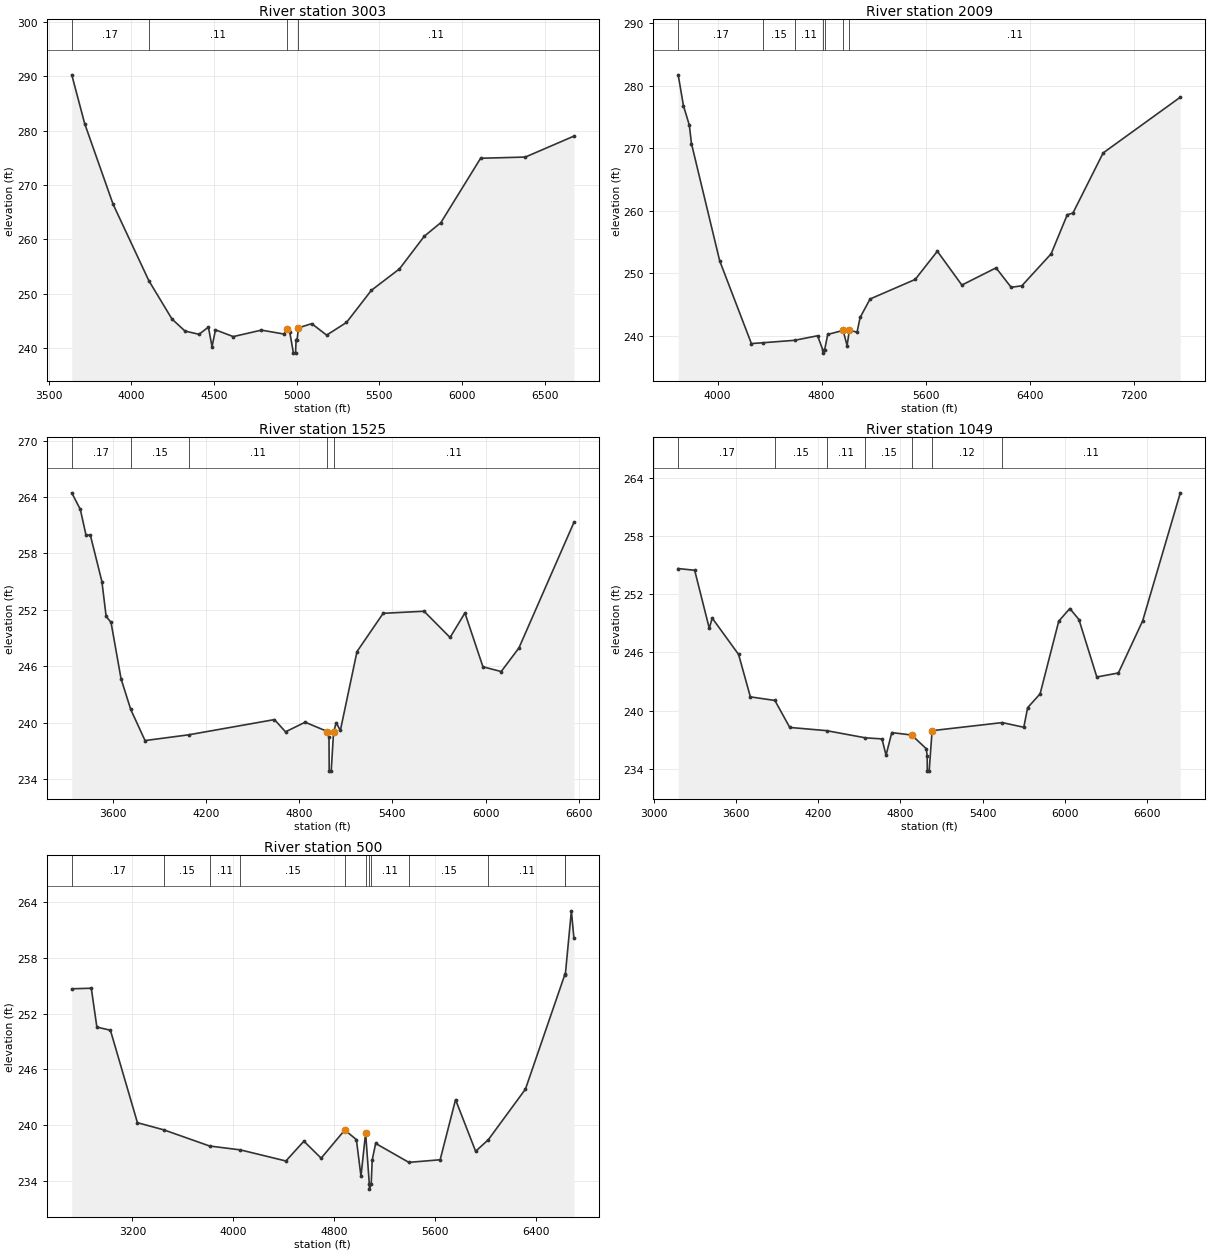
Type RM Length L Ch R = 1 ,3003    ,994,994,994
BEGIN DESCRIPTION:
PERSIMMON CREEK 4.0
END DESCRIPTION:
XS GIS Cut Line= 3
      3797857.95     10211571.63      3797019.45     10210501.25
      3795344.51     10210597.36
#Sta/Elev= 30
  3640.3  290.27  3718.5  281.29  3890.3  266.47  4106.7  252.41  4246.5  245.37
  4325.1  243.16  4410.1  242.56  4466.7  243.88  4488.8  240.28  4509.6  243.38
  4617.2  242.14  4787.2  243.33  4923.6  242.61  4944.5  243.55  4958.9  242.98
  4981.1   239.1  4993.9   239.1  4997.2  241.58  5003.3  241.58  5011.6  243.75
  5091.8  244.52  5181.9  242.41  5302.1  244.74  5452.3  250.64  5622.6  254.59
  5772.9   260.6    5873   263.1  6113.4  274.93  6383.9  275.15  6677.7     279
#Mann= 4 ,-1 , 0
  3640.3     .17       0  4106.7     .11       0  4944.5     .06       0
  5011.6     .11       0
Bank Sta=4944.5,5011.6
XS Rating Curve= 0 ,0
Exp/Cntr=0.3,0.1

Type RM Length L Ch R = 1 ,2009    ,484,484,484
BEGIN DESCRIPTION:
PERSIMMON CREEK 3.0
END DESCRIPTION:
XS GIS Cut Line= 4
      3798267.28     10211321.94      3797831.13     10210093.78
      3797588.16     10209991.41      3795348.65     10210499.12
#Sta/Elev= 30
  3696.7  281.71  3737.3  276.77  3782.5  273.66    3799  270.71    4016  251.96
    4260  238.72  4348.2  238.85  4592.1  239.24  4769.4  239.97  4809.5  237.69
    4810  237.19  4823.3  237.69  4847.2  240.18  4965.4  240.82  4996.2  238.41
  5014.4   240.9  5072.7  240.52  5096.5  242.89  5173.1  245.85  5520.3  248.98
  5690.7  253.49  5879.2  248.08  6142.4  250.83  6258.6  247.72  6340.6  247.96
  6566.2  253.08  6690.6  259.34  6733.7  259.59  6966.1  269.21    7560  278.13
#Mann= 7 ,-1 , 0
  3696.7     .17       0  4348.2     .15       0  4592.1     .11       0
  4809.5     .09       0  4823.3     .11       0  4965.4     .06       0
  5014.4     .11       0
#XS Ineff= 2 , 0
       0                  5096.5       0  242.89
Permanent Ineff=
       F       F
Bank Sta=4965.4,5014.4
XS Rating Curve= 0 ,0
Exp/Cntr=0.3,0.1

Type RM Length L Ch R = 1 ,1525    ,476,476,476
BEGIN DESCRIPTION:
PERSIMMON CREEK 2.0
END DESCRIPTION:
XS GIS Cut Line= 4
      3798512.87     10211059.91      3797845.65     10209921.94
      3797551.56     10209744.73      3796061.85     10210232.73
#Sta/Elev= 30
  3337.5  264.45  3392.6  262.68  3428.9  259.97    3457  259.95  3531.3  255.02
  3558.6  251.31    3590  250.68  3654.4  244.69  3716.7  241.42  3808.8  238.11
    4089  238.72  4641.3  240.34  4712.5  239.04  4838.7  240.06  4982.4  239.07
  4992.1  238.45  4993.5  234.86  5006.4  234.86 5021.45  238.99  5038.6  240.01
  5065.2  239.18  5172.3  247.57  5340.6  251.64  5603.7  251.86    5771  249.07
  5866.6  251.68  5982.5  245.95    6100  245.45    6214  247.96  6567.6   261.3
#Mann= 5 ,-1 , 0
  3337.5     .17       0  3716.7     .15       0    4089     .11       0
  4982.4     .06       0 5021.45     .11       0
Bank Sta=4982.4,5021.45
XS Rating Curve= 0 ,0
Exp/Cntr=0.3,0.1

Type RM Length L Ch R = 1 ,1049    ,549,549,549
BEGIN DESCRIPTION:
PERSIMMON CREEK 1.0
END DESCRIPTION:
XS GIS Cut Line= 3
      3799175.99     10210429.51      3797697.46     10209371.92
      3796029.74     10210166.79
#Sta/Elev= 30
  3178.4  254.64  3298.8  254.46  3405.7  248.47  3426.6  249.54  3619.4  245.79
  3705.4  241.42  3884.4  241.05  3992.9  238.27  4261.3  237.94  4545.4   237.2
  4666.2  237.09  4695.7  235.41  4737.6  237.74  4882.5  237.49  4989.4  236.08
  4996.2  235.29  4996.8  233.77  5010.4  233.77  5031.9  237.94    5544  238.77
  5701.2  238.29  5729.4  240.31  5820.2  241.73  5956.4  249.22  6037.1  250.52
  6103.7  249.39  6234.3  243.47  6391.6  243.88  6568.8  249.25  6843.7  262.44
#Mann= 7 ,-1 , 0
  3178.4     .17       0  3884.4     .15       0  4261.3     .11       0
  4545.4     .15       0  4882.5     .06       0  5031.9     .12       0
    5544     .11       0
Bank Sta=4882.5,5031.9
XS Rating Curve= 0 ,0
Exp/Cntr=0.3,0.1

Type RM Length L Ch R = 1 ,500     ,0,0,0
BEGIN DESCRIPTION:
PERSIMMON CREEK 1.5
END DESCRIPTION:
XS GIS Cut Line= 3
      3799200.56     10210384.49      3797335.95     10209070.82
      3795881.79     10209954.09
#Sta/Elev= 30
  2719.1  254.66    2874  254.72  2918.1  250.54  3025.5   250.2  3239.8  240.25
    3449  239.48  3812.1  237.74  4057.1  237.32  4417.3  236.13  4560.1  238.26
  4696.8  236.43  4884.1  239.46  4976.4  238.43  5012.7  234.49  5049.5  239.14
  5079.1   233.6  5079.6   233.1  5093.7   233.6  5101.8  236.23    5129  238.02
  5392.4  235.98  5640.6  236.26  5762.8  242.73  5922.1  237.17  6023.3  238.43
    6317  243.86  6629.2  256.18  6633.5  256.22  6681.4  263.05  6701.4  260.13
#Mann= 12 ,-1 , 0
  2719.1     .17       0    3449     .15       0  3812.1     .11       0
  4057.1     .15       0  4884.1     .06       0  5049.5     .11       0
  5079.1     .11       0  5093.7     .11       0  5392.4     .15       0
  6023.3     .11       0  6629.2     .15       0  6633.5     .11       0
#XS Ineff= 2 , 0
       0  4884.1  239.46  5762.8       0  242.73
Permanent Ineff=
       T       T
Bank Sta=4884.1,5049.5
XS Rating Curve= 0 ,0
Exp/Cntr=0.3,0.1

Chan Stop Cuts=-1
Use User Specified Reach Order=0
Composite Channel Slope=5