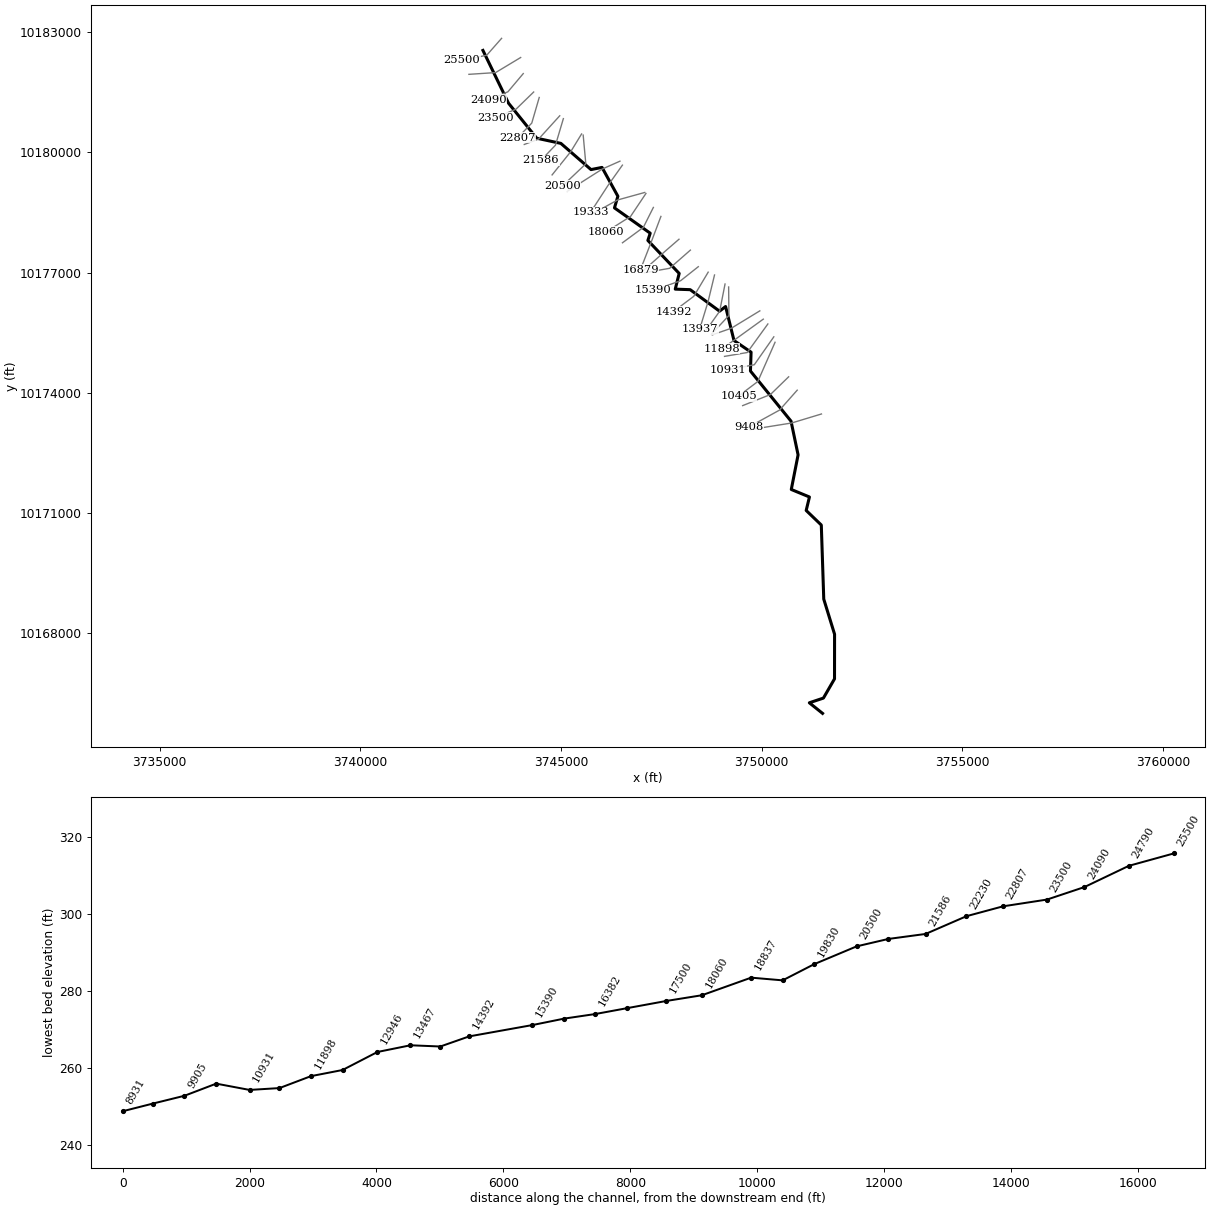
--- POLE CREEK.prj (project) ---

Proj Title=POLE CREEK Base Level Engineering
Current Plan=p01
Default Exp/Contr=0.3,0.1
English Units
Geom File=g01
Flow File=f01
Plan File=p01
Y Axis Title=Elevation
X Axis Title(PF)=Main Channel Distance
X Axis Title(XS)=Station
BEGIN DESCRIPTION:
POLE CREEK
END DESCRIPTION:
DSS Export Rating Curves= 0
DSS Export Rating Curve Sorted= 0
DSS Export Volume Flow Curves= 0
DXF OffsetX= 0
DXF OffsetY= 0
DXF ScaleX= 1
DXF ScaleY= 10

--- POLE CREEK.p01 (plan) ---

Plan Title=Multiple Run
Short Identifier=Multiple
Geom File=g01
Flow File=f01
Subcritical Flow
K Sum by GR= 0
Std Step Tol= 0.01
Critical Tol= 0.01
Num of Std Step Trials= 20
Max Error Tol= 0.3
Flow Tol Ratio= 0.001
Split Flow NTrial= 30
Split Flow Tol= 0.02
Split Flow Ratio= 0.02
Log Output Level= 0
Friction Slope Method= 1
Unsteady Friction Slope Method= 2
Unsteady Bridges Friction Slope Method= 1
Parabolic Critical Depth
Global Vel Dist=  1 , 1 , 1
Global Log Level= 0
CheckData=True
Encroach Param= -1, 0, 0, 0
BEGIN DESCRIPTION:
Multiple Run
END DESCRIPTION:

--- POLE CREEK.f01 (steady flow) ---

Flow Title=Multiple
Program Version=4.10
Number of Profiles= 7
Profile Names=10-year,25-year,50-year,1pct_min,100-year,1pct_plu,500-year
River Rch & RM=POLE CREEK,Reach-1         ,25500
     166     207     265     112     339    1024     569
River Rch & RM=POLE CREEK,Reach-1         ,24790
     695     939    1267     562    1697    5125    3146
River Rch & RM=POLE CREEK,Reach-1         ,16382
    1120    1559    2144     968    2922    8824    5623
River Rch & RM=POLE CREEK,Reach-1         ,8931
    1297    1803    2479    1118    3375   10192    6471
River Rch & RM=POLE CREEK,Reach-1         ,1996
    1419    1974    2713    1221    3688   11138    7061
Boundary for River Rch & Prof#=POLE CREEK,Reach-1         , 1
Up Type= 0
Dn Type= 3
Dn Slope=0.005
Boundary for River Rch & Prof#=POLE CREEK,Reach-1         , 2
Up Type= 0
Dn Type= 3
Dn Slope=0.005
Boundary for River Rch & Prof#=POLE CREEK,Reach-1         , 3
Up Type= 0
Dn Type= 3
Dn Slope=0.005
Boundary for River Rch & Prof#=POLE CREEK,Reach-1         , 4
Up Type= 0
Dn Type= 3
Dn Slope=0.005
Boundary for River Rch & Prof#=POLE CREEK,Reach-1         , 5
Up Type= 0
Dn Type= 3
Dn Slope=0.005
Boundary for River Rch & Prof#=POLE CREEK,Reach-1         , 6
Up Type= 0
Dn Type= 3
Dn Slope=0.005
Boundary for River Rch & Prof#=POLE CREEK,Reach-1         , 7
Up Type= 0
Dn Type= 3
Dn Slope=0.005
DSS Import GetInterval= 0
DSS Import GetPeak= 0
DSS Import FillOption= 0

--- POLE CREEK.g01 (geometry) ---

Geom Title=Existing Conditions
Program Version=4.10

River Reach=POLE CREEK      ,Reach-1
Reach XY= 30
        3743054.     10182541.23      3743690.86     10181226.12
      3744394.66     10180351.53      3744996.23     10180222.45
       3745747.6     10179569.07      3746021.47     10179623.51
      3746417.04     10178904.45      3746332.13     10178614.04
      3747222.88     10177982.33      3747164.62     10177802.11
      3747944.88     10176979.22      3747847.05     10176587.67
      3748219.03     10176574.16      3748950.75     10176037.94
      3749101.51     10176153.97      3749310.87     10175306.05
      3749736.66     10175015.53      3749721.24     10174545.28
      3750732.34     10173294.93      3750908.32     10172454.05
      3750738.85     10171590.84      3751191.32     10171403.81
      3751110.18     10171067.66      3751486.92     10170704.39
      3751548.33     10168855.88      3751817.71     10167980.64
      3751816.28     10166867.66       3751539.7     10166388.13
      3751188.46     10166271.01      3751518.23     10166006.84

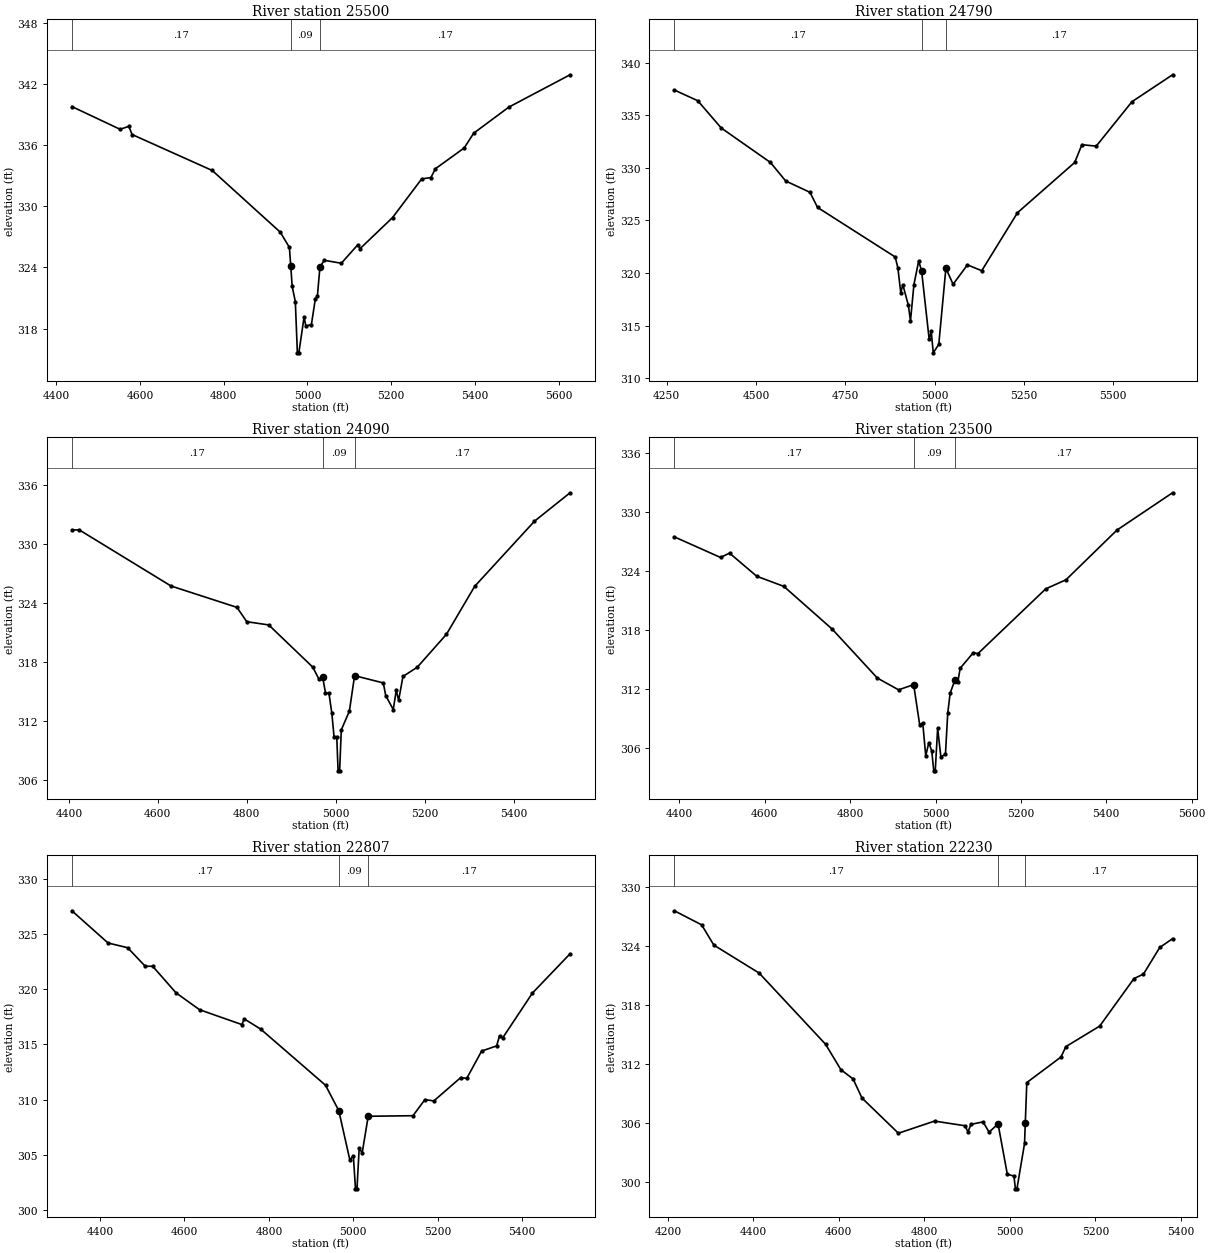
Type RM Length L Ch R = 1 ,25500   ,710,710,710
BEGIN DESCRIPTION:
POLE CREEK 50.0
END DESCRIPTION:
XS GIS Cut Line= 3
      3743518.93     10182842.65      3743147.23     10182420.59
      3742532.29      10182296.7
#Sta/Elev= 30
  4437.6  339.78  4552.8  337.55  4573.7  337.84  4581.3  337.04  4772.8  333.51
  4935.2  327.46    4957  325.97 4960.29  324.16  4963.6  322.16  4971.2  320.65
  4976.1  315.62  4979.6  315.62  4992.1  319.13  4996.3  318.26  5009.6   318.4
  5018.8  320.86  5023.9   321.2    5030  324.04  5040.2   324.7    5081  324.41
  5120.4  326.22  5125.5  325.83  5203.4  328.89  5272.9  332.68  5295.2  332.82
  5305.4  333.67  5374.5  335.72  5397.2  337.17  5481.2  339.73  5627.3   342.9
#Mann= 3 , 0 , 0
  4437.6     .17       0 4960.29     .09       0    5030     .17       0
Bank Sta=4960.29,5030
XS Rating Curve= 0 ,0
Exp/Cntr=0.3,0.1

Type RM Length L Ch R = 1 ,24790   ,700,700,700
BEGIN DESCRIPTION:
POLE CREEK 48.0
END DESCRIPTION:
XS GIS Cut Line= 3
      3743994.08     10182364.46      3743369.75     10181988.47
      3742704.48     10181944.86
#Sta/Elev= 30
  4271.2   337.4  4336.8  336.38  4402.4  333.79  4540.3  330.51    4583  328.75
    4651  327.67  4672.3  326.23  4889.8  321.52  4897.2  320.49  4905.4  318.13
  4911.2  318.88  4926.7  316.92  4932.6  315.44  4942.3   318.9  4955.5  321.13
  4963.6  320.23    4985  313.68  4990.8  314.43  4996.4   312.4  5011.9  313.21
  5031.8  320.44    5052  318.92  5092.1  320.77  5132.2  320.21  5232.4  325.73
  5392.7  330.51  5412.8   332.2  5452.9  332.06  5553.1  336.29  5666.7  338.85
#Mann= 3 , 0 , 0
  4271.2     .17       0  4963.6     .09       0  5031.8     .17       0
Bank Sta=4963.6,5031.8
XS Rating Curve= 0 ,0
Exp/Cntr=0.3,0.1

Type RM Length L Ch R = 1 ,24090   ,590,590,590
BEGIN DESCRIPTION:
POLE CREEK 47.0
END DESCRIPTION:
XS GIS Cut Line= 3
      3744058.85     10181963.36      3743676.54     10181509.79
      3743192.42     10181303.34
#Sta/Elev= 30
  4406.8  331.43  4422.9  331.47  4629.5  325.74  4777.8  323.56  4799.8   322.1
  4849.2  321.77  4948.1  317.47  4962.4  316.21  4970.2  316.47  4976.7  314.86
  4984.5   314.8    4991  312.76  4995.9  310.38    5002  310.38    5005   306.9
  5008.5   306.9  5012.2  311.07  5030.4  312.99  5042.1   316.6  5106.6  315.86
  5112.1  314.56    5129  313.15  5135.7   315.1  5141.1  314.09  5150.8  316.52
  5182.9  317.46  5248.6  320.82  5311.9   325.7  5446.3  332.34  5526.3  335.24
#Mann= 3 , 0 , 0
  4406.8     .17       0  4970.2     .09       0  5042.1     .17       0
Bank Sta=4970.2,5042.1
XS Rating Curve= 0 ,0
Exp/Cntr=0.3,0.1

Type RM Length L Ch R = 1 ,23500   ,693,693,693
BEGIN DESCRIPTION:
POLE CREEK 46.0
END DESCRIPTION:
XS GIS Cut Line= 3
      3744318.04     10181503.69      3743879.33     10181077.13
      3743367.89     10180861.09
#Sta/Elev= 30
  4388.1  327.43  4496.2  325.34  4517.3  325.78  4581.1  323.43  4644.6   322.4
  4757.8  318.06  4863.8  313.08  4913.4  311.89  4948.7  312.42  4962.8  308.35
    4970  308.52    4977  305.18  4984.2  306.52  4991.1  305.67  4995.8  303.66
  4999.3  303.66  5004.9  307.99  5012.5  305.06  5023.2  305.36  5028.6  309.54
  5034.2  311.55    5045  312.84  5052.3  312.73  5057.7  314.08  5088.5  315.67
  5099.3  315.57  5258.2  322.15  5305.6  323.07    5425  328.12  5555.2  331.91
#Mann= 3 , 0 , 0
  4388.1     .17       0  4948.7     .09       0    5045     .17       0
Bank Sta=4948.7,5045
XS Rating Curve= 0 ,0
Exp/Cntr=0.3,0.1

Type RM Length L Ch R = 1 ,22807   ,577,577,577
BEGIN DESCRIPTION:
POLE CREEK 44.0
END DESCRIPTION:
XS GIS Cut Line= 3
      3744456.85     10181367.89      3744270.63     10180727.94
      3743913.85     10180359.04
#Sta/Elev= 30
  4333.5  327.12  4419.1   324.2  4465.6  323.77  4507.2  322.09  4524.8  322.09
  4580.1  319.68  4635.8  318.15  4736.3   316.8  4741.5  317.32  4780.3   316.4
  4934.2   311.3  4965.5     309  4991.8  304.52    5000  304.91  5005.1  301.91
  5008.6  301.91  5013.8  305.57    5021  305.18  5035.2  308.49  5141.2  308.54
  5169.5     310  5190.6  309.88  5254.4     312  5268.5  311.92  5303.8   314.4
  5339.3  314.87  5346.2  315.78  5353.4  315.58  5424.1  319.66  5513.2  323.22
#Mann= 3 , 0 , 0
  4333.5     .17       0  4965.5     .09       0  5035.2     .17       0
Bank Sta=4965.5,5035.2
XS Rating Curve= 0 ,0
Exp/Cntr=0.3,0.1

Type RM Length L Ch R = 1 ,22230   ,644,644,644
BEGIN DESCRIPTION:
POLE CREEK 43.0
END DESCRIPTION:
XS GIS Cut Line= 3
      3744967.86     10180911.08      3744440.43     10180329.94
      3744084.25     10180195.79
#Sta/Elev= 30
  4215.2  327.55  4279.1  326.12  4307.5  324.07  4413.6  321.23    4569  314.01
  4604.8  311.43  4633.2   310.5  4654.1  308.56  4739.3  304.99  4823.8  306.22
  4894.7  305.75  4902.2  305.13  4908.9  305.89  4937.3  306.14  4951.5   305.1
  4972.4  305.94  4994.1  300.83  5009.5  300.65  5013.1  299.35  5016.6  299.35
  5034.4  303.95 5036.14  306.04  5039.7  310.13  5119.7  312.72    5131  313.77
  5210.3  315.86  5290.3  320.67  5312.6  321.13  5350.7  323.83  5380.6  324.72
#Mann= 3 , 0 , 0
  4215.2     .17       0  4972.4     .09       0 5036.14     .17       0
Bank Sta=4972.4,5036.14
XS Rating Curve= 0 ,0
Exp/Cntr=0.3,0.1

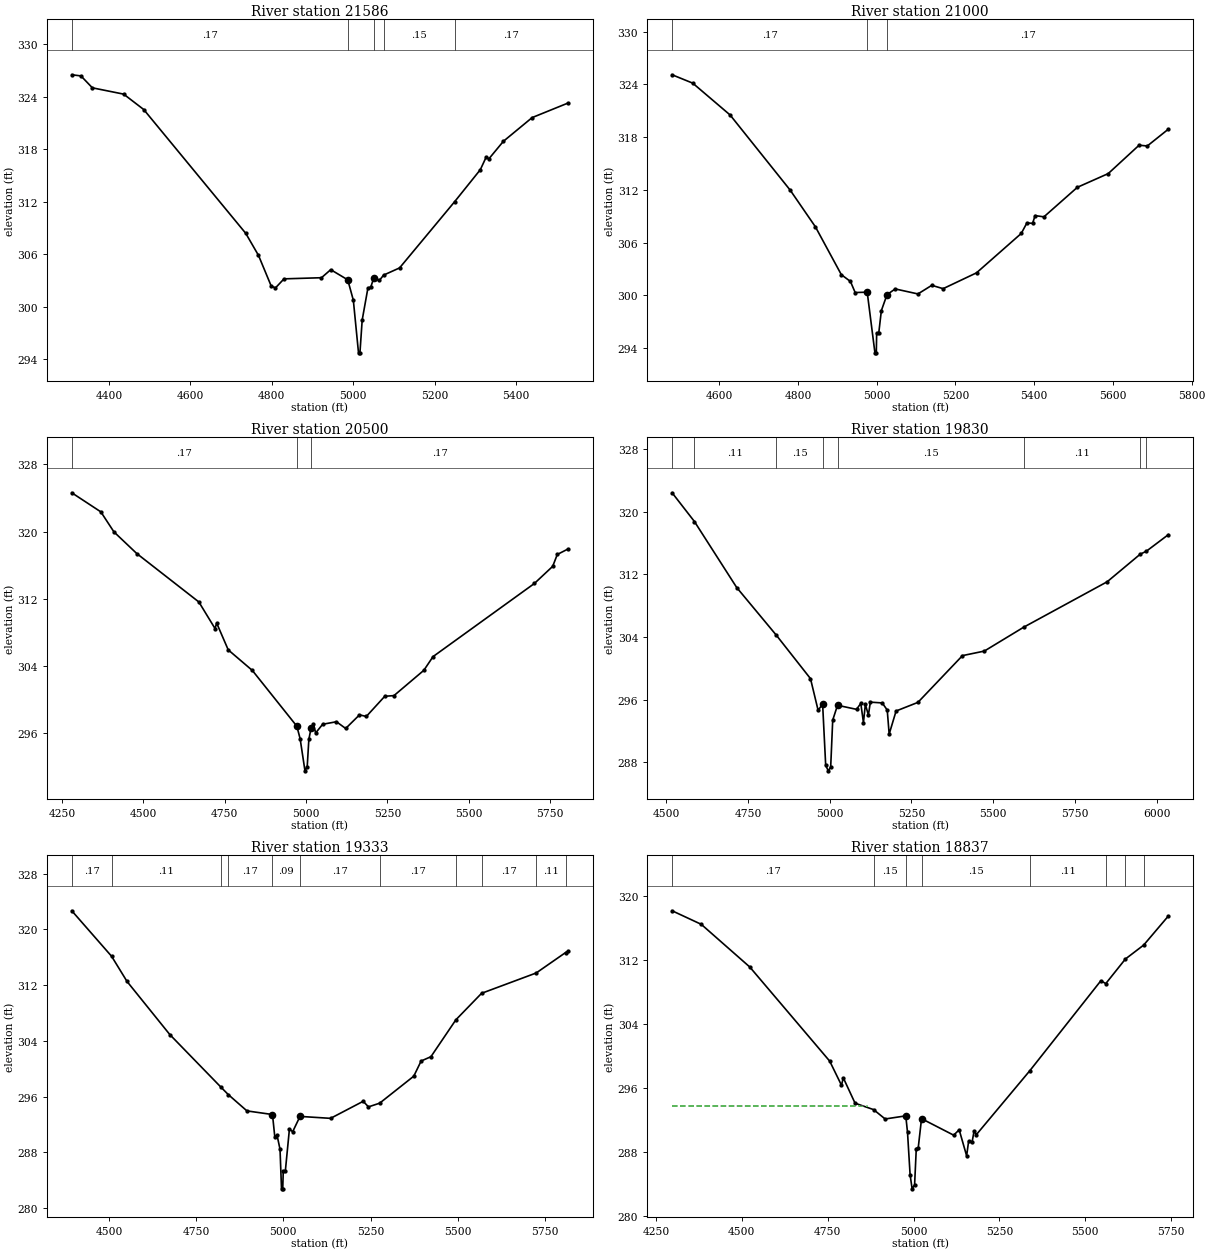
Type RM Length L Ch R = 1 ,21586   ,586,586,586
BEGIN DESCRIPTION:
POLE CREEK 42.0
END DESCRIPTION:
XS GIS Cut Line= 3
      3745058.48     10180840.35      3744861.53      10180177.9
      3744496.95     10179797.51
#Sta/Elev= 30
  4308.9  326.51  4331.4  326.38  4359.4  325.02  4436.2   324.3  4485.5  322.54
  4735.9   308.4  4767.2  305.88  4798.5  302.37  4808.9  302.17  4829.8   303.2
  4921.8  303.33  4944.5  304.25  4986.3  303.09    5000  300.76  5012.7  294.75
  5016.2  294.75  5021.7  298.49  5035.8  302.16  5042.8  302.26    5050  303.27
  5064.1  303.03  5074.3  303.63  5113.5  304.45  5248.4     312  5311.7  315.67
  5325.8  317.08  5332.7  316.91  5368.3  318.91  5438.9  321.62  5526.9  323.28
#Mann= 5 ,-1 , 0
  4308.9     .17       0  4986.3     .09       0    5050     .17       0
  5074.3     .15       0  5248.4     .17       0
Bank Sta=4986.3,5050
XS Rating Curve= 0 ,0
Exp/Cntr=0.3,0.1

Type RM Length L Ch R = 1 ,21000   ,500,500,500
BEGIN DESCRIPTION:
POLE CREEK 41.0
END DESCRIPTION:
XS GIS Cut Line= 3
      3745511.99     10180457.73      3745241.02      10180014.5
      3744777.74     10179436.57
#Sta/Elev= 30
  4480.5  325.09  4532.8  324.14  4627.7  320.52  4780.5  311.96  4844.5  307.79
  4910.3  302.35  4933.4  301.58  4945.4  300.32    4976  300.36  4995.6  293.46
  4999.1  293.46    5000  295.74  5005.4  295.74  5011.9  298.26  5026.3  300.08
  5047.1  300.73  5104.8  300.16    5140  301.14  5168.8  300.76  5253.6  302.56
  5367.2  307.04  5381.6  308.24    5396  308.19  5402.4  309.07  5424.8  308.93
  5509.7  312.29  5588.1  313.85  5666.5  317.08  5687.3  316.99  5740.7   318.9
#Mann= 3 , 0 , 0
  4480.5     .17       0    4976     .09       0  5026.3     .17       0
Bank Sta=4976,5026.3
XS Rating Curve= 0 ,0
Exp/Cntr=0.3,0.1

Type RM Length L Ch R = 1 ,20500   ,670,670,670
BEGIN DESCRIPTION:
POLE CREEK 40.0
END DESCRIPTION:
XS GIS Cut Line= 3
      3745552.12     10180429.99      3745618.06     10179712.91
      3745033.78     10179158.86
#Sta/Elev= 30
  4279.9  324.62  4369.2  322.35  4409.4  319.97  4479.7  317.39  4670.5  311.63
  4720.2  308.47  4725.2  309.12  4760.8  305.93    4835  303.48  4971.7  296.85
  4981.8  295.36  4996.7  291.54  5003.6  292.04  5008.6  295.28  5015.5  296.63
  5022.7  297.09  5029.6  296.05    5051  297.08  5093.5  297.38  5121.8  296.58
  5164.3   298.2  5185.3  298.01    5242  300.41  5270.3  300.49  5362.1   303.5
  5390.4  305.13  5701.9  313.83  5758.2  315.87  5772.3  317.28  5805.2  317.93
#Mann= 3 , 0 , 0
  4279.9     .17       0  4971.7     .09       0  5015.5     .17       0
Bank Sta=4971.7,5015.5
XS Rating Curve= 0 ,0
Exp/Cntr=0.3,0.1

Type RM Length L Ch R = 1 ,19830   ,497,497,497
BEGIN DESCRIPTION:
POLE CREEK 38.0
END DESCRIPTION:
XS GIS Cut Line= 3
      3746468.44     10179779.01      3746028.11     10179582.71
      3745154.14     10179026.22
#Sta/Elev= 30
  4517.9  322.42  4586.2  318.75  4715.6  310.32  4836.9  304.23  4941.3  298.69
  4964.6  294.65  4978.4  295.44  4987.8  287.62  4995.7  286.92  5003.1  287.42
  5009.3   293.4    5024  295.29  5082.1  294.77  5095.2  295.53  5103.3  293.09
  5109.2   295.4  5118.5  294.04  5124.4  295.69  5160.8  295.59  5176.1  294.68
    5182  291.61  5203.2  294.56    5270  295.66  5406.3  301.63  5473.2  302.21
  5593.7  305.26  5849.1  311.06  5950.4  314.59  5968.3  314.94  6036.1  317.07
#Mann= 8 ,-1 , 0
  4517.9     .17       0  4586.2     .11       0  4836.9     .15       0
  4978.4     .09       0    5024     .15       0  5593.7     .11       0
  5950.4     .17       0  5968.3     .11       0
Bank Sta=4978.4,5024
XS Rating Curve= 0 ,0
Exp/Cntr=0.3,0.1

Type RM Length L Ch R = 1 ,19333   ,496,496,496
BEGIN DESCRIPTION:
POLE CREEK 37.0
END DESCRIPTION:
XS GIS Cut Line= 3
      3746530.12     10179680.25      3746179.14     10179185.75
      3745734.17     10178501.75
#Sta/Elev= 30
  4393.6  322.69  4507.7  316.15    4552  312.53  4674.6   304.9  4821.2  297.34
  4842.1  296.28  4895.7  293.93  4968.9  293.41  4975.7  290.12  4981.8  290.48
  4990.5  288.42  4994.8  282.73  4998.3  282.73  4999.8  285.31  5005.8  285.31
  5017.5  291.34  5026.7  290.93  5047.8  293.14  5135.4  292.86  5228.9  295.31
  5244.1  294.51  5276.1  295.04  5373.9  298.92    5395   301.1  5423.1  301.72
  5494.6  307.02  5568.3  310.83  5724.8  313.75  5808.9  316.68    5816  316.89
#Mann= 11 ,-1 , 0
  4393.6     .17       0  4507.7     .11       0  4821.2     .15       0
  4842.1     .17       0  4968.9     .09       0  5047.8     .17       0
  5276.1     .17       0  5494.6     .11       0  5568.3     .17       0
  5724.8     .11       0  5808.9     .17       0
#XS Ineff= 2 , 0
       0                  5228.9       0  295.31
Permanent Ineff=
       F       F
Bank Sta=4968.9,5047.8
XS Rating Curve= 0 ,0
Exp/Cntr=0.3,0.1

Type RM Length L Ch R = 1 ,18837   ,777,777,777
BEGIN DESCRIPTION:
POLE CREEK 36.0
END DESCRIPTION:
XS GIS Cut Line= 3
      3747085.51     10178998.45      3746408.12     10178810.78
      3745758.87     10178452.38
#Sta/Elev= 30
  4297.1  318.14  4381.9  316.45    4523  311.13  4755.9  299.37  4790.2  296.36
  4795.4  297.29  4829.7  294.12  4883.6  293.32  4917.3  292.15  4977.3  292.54
  4982.4  290.47  4989.9  285.19  4995.8  283.43    5003  283.93  5007.9  288.46
  5013.6  288.56  5023.2  292.19  5116.7  290.13  5132.8   290.8  5154.5  287.55
  5160.3  289.39  5170.6  289.32  5176.3  290.68  5183.1  290.21  5338.7  298.19
  5545.3  309.41  5559.5  309.05  5616.7  312.12  5669.9  313.86  5741.6  317.48
#Mann= 8 ,-1 , 0
  4297.1     .17       0  4883.6     .15       0  4977.3     .09       0
  5023.2     .15       0  5338.7     .11       0  5559.5     .17       0
  5616.7     .11       0  5669.9     .17       0
#XS Ineff= 2 , 0
       0    4864  293.73               0
Permanent Ineff=
       F       F
Bank Sta=4977.3,5023.2
XS Rating Curve= 0 ,0
Exp/Cntr=0.3,0.1

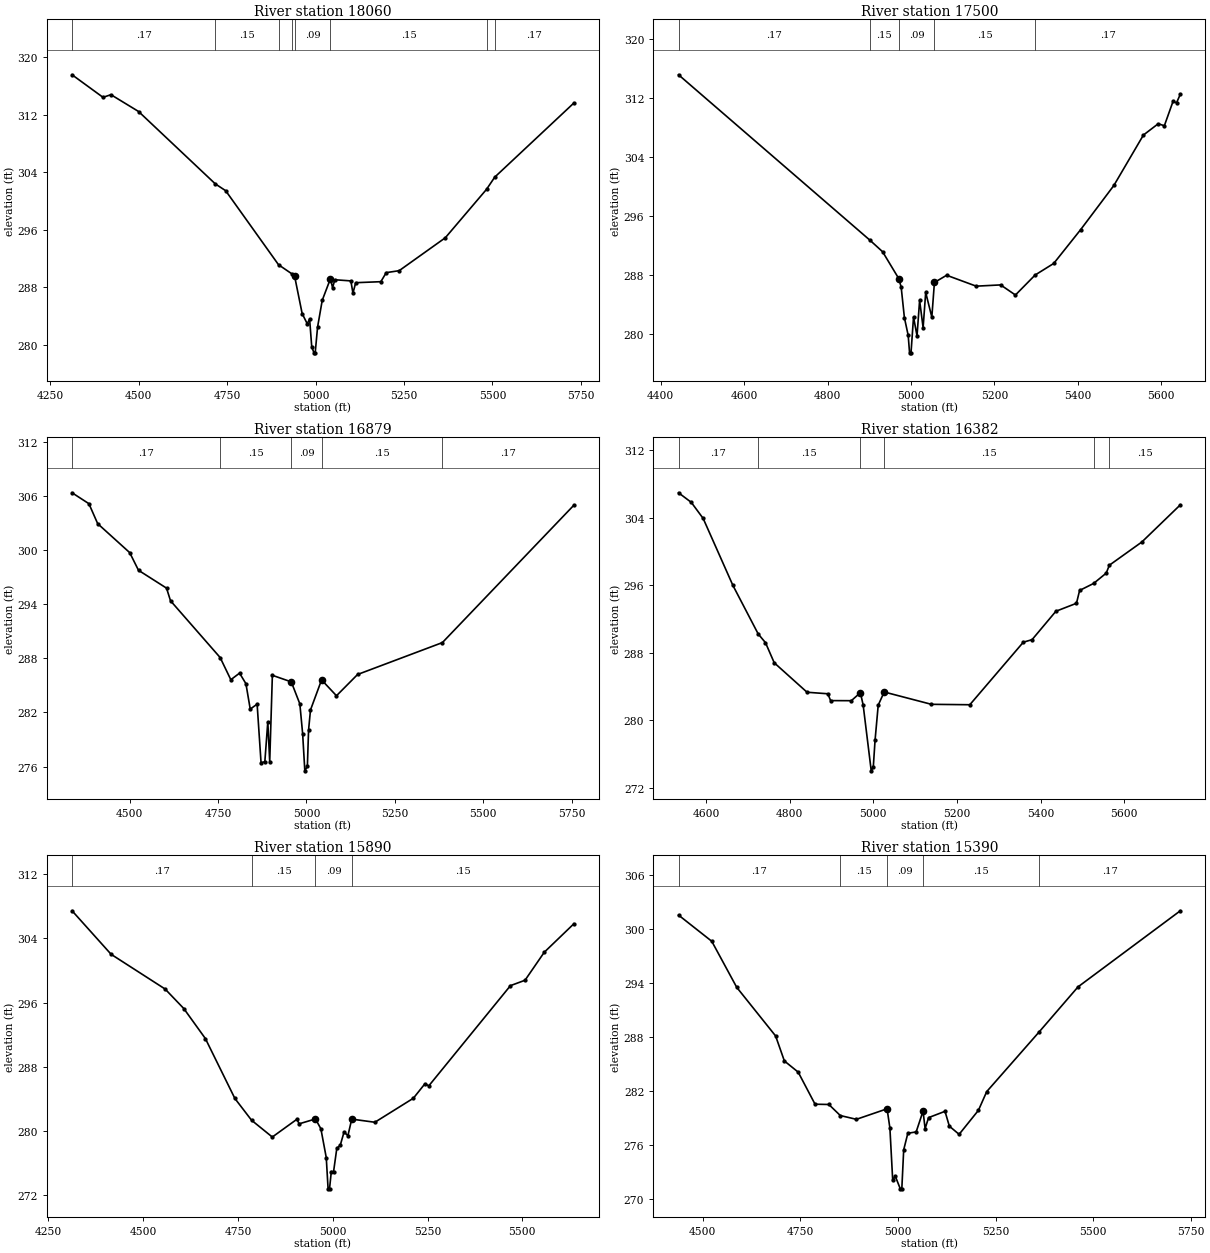
Type RM Length L Ch R = 1 ,18060   ,560,560,560
BEGIN DESCRIPTION:
POLE CREEK 36.5
END DESCRIPTION:
XS GIS Cut Line= 3
      3747116.35     10178973.78      3746733.87     10178401.65
      3746116.73     10178011.17
#Sta/Elev= 30
  4311.8  317.56  4399.3  314.42  4421.7  314.79  4499.8  312.45  4716.7  302.38
    4746  301.43  4895.4  291.13  4934.4  289.82  4940.6  289.61  4962.2  284.34
  4976.6  282.91  4983.3  283.58  4989.3  279.72  4995.6  278.87  4999.1  278.87
  5005.8  282.45    5019  286.18  5042.3   289.2  5048.2  287.92  5054.5  289.04
  5099.9  288.88  5105.8  287.18  5113.6  288.63  5184.7  288.77  5199.9  290.03
  5236.4   290.3  5366.9  294.88  5483.4  301.62  5506.7  303.32  5730.3  313.63
#Mann= 8 ,-1 , 0
  4311.8     .17       0  4716.7     .15       0  4895.4     .17       0
  4934.4     .15       0  4940.6     .09       0  5042.3     .15       0
  5483.4     .11       0  5506.7     .17       0
Bank Sta=4940.6,5042.3
XS Rating Curve= 0 ,0
Exp/Cntr=0.3,0.1

Type RM Length L Ch R = 1 ,17500   ,621,621,621
BEGIN DESCRIPTION:
POLE CREEK 35.0
END DESCRIPTION:
XS GIS Cut Line= 3
      3747301.46     10178625.13      3747051.43     10178127.06
      3746531.46     10177743.72
#Sta/Elev= 30
  4442.7  315.09  4901.7  292.66    4932   291.1    4971  287.44  4976.6  286.29
  4984.3  282.17  4993.4  279.76  4996.7  277.39  5000.2  277.39  5006.2  282.25
  5014.6  279.69  5020.8   284.5  5029.2  280.81  5035.4  285.58  5050.1  282.23
  5056.3  286.93  5085.6  287.91  5156.5  286.43  5215.1   286.6  5250.6  285.23
  5297.8  287.94  5342.4  289.51  5407.2  294.11  5486.6  300.08  5557.5  306.92
    5593  308.45  5607.7  308.18  5628.5  311.48  5636.9  311.29    5646  312.45
#Mann= 5 ,-1 , 0
  4442.7     .17       0  4901.7     .15       0    4971     .09       0
  5056.3     .15       0  5297.8     .17       0
Bank Sta=4971,5056.3
XS Rating Curve= 0 ,0
Exp/Cntr=0.3,0.1

Type RM Length L Ch R = 1 ,16879   ,497,497,497
BEGIN DESCRIPTION:
POLE CREEK 32.0
END DESCRIPTION:
XS GIS Cut Line= 3
      3747489.49     10178401.09      3747255.38     10177781.02
      3746980.58      10177076.3
#Sta/Elev= 30
  4337.2  306.37  4384.8  305.16  4409.7  302.94  4500.2  299.73  4525.1  297.77
  4604.4  295.79  4615.6  294.39    4756  288.09  4786.2  285.63  4810.9  286.36
  4828.9  285.19  4841.1  282.37  4860.6  282.92  4871.7  276.42  4882.4  276.53
  4890.8  280.96  4896.2  276.53  4903.7  286.12  4957.2  285.39  4981.4  282.95
  4989.3  279.65  4995.5  275.52  5002.7  276.02  5006.1  280.05  5011.5  282.27
  5042.9  285.61    5085  283.85  5144.7  286.21  5384.6  289.75  5756.4  304.99
#Mann= 5 ,-1 , 0
  4337.2     .17       0    4756     .15       0  4957.2     .09       0
  5042.9     .15       0  5384.6     .17       0
#XS Ineff= 2 , 0
       0  4810.9  286.36               0
Permanent Ineff=
       F       F
Bank Sta=4957.2,5042.9
XS Rating Curve= 0 ,0
Exp/Cntr=0.3,0.1

Type RM Length L Ch R = 1 ,16382   ,492,492,492
BEGIN DESCRIPTION:
POLE CREEK 31.0
END DESCRIPTION:
XS GIS Cut Line= 3
      3747940.11     10177832.23      3747588.11       10177527.
      3747039.18     10177039.28
#Sta/Elev= 30
  4534.1  306.95  4564.5  305.82    4593  303.91  4664.2  295.97  4724.6  290.23
  4742.1  289.19    4763  286.81  4841.5  283.32  4891.2  283.14  4897.8  282.33
  4947.4  282.32  4969.1  283.27  4975.7   281.8    4995  274.01    5000  274.51
  5004.2  277.66  5011.7  281.79    5026  283.35  5138.9  281.89  5230.8  281.84
  5358.8  289.25  5379.7  289.55  5436.6  292.91  5485.9  293.86  5493.4  295.38
  5526.9  296.21    5557  297.43  5564.6  298.37  5642.3  301.12  5734.3  305.52
#Mann= 6 ,-1 , 0
  4534.1     .17       0  4724.6     .15       0  4969.1     .09       0
    5026     .15       0  5526.9     .17       0  5564.6     .15       0
Bank Sta=4969.1,5026
XS Rating Curve= 0 ,0
Exp/Cntr=0.3,0.1

Type RM Length L Ch R = 1 ,15890   ,500,500,500
BEGIN DESCRIPTION:
POLE CREEK 30.0
END DESCRIPTION:
XS GIS Cut Line= 3
      3748223.95     10177560.73      3747707.33     10177107.27
      3747081.06     10176996.43
#Sta/Elev= 30
  4312.6  307.44  4415.6  302.02  4557.9   297.7  4607.2  295.27  4664.2  291.53
    4742  284.07    4786  281.36  4840.7  279.27  4905.2  281.47  4911.8  280.92
  4954.5  281.52  4968.8   280.3    4983  276.71  4987.8  272.82  4991.6  272.82
  4996.3  274.97  5002.3  274.97  5010.8  277.86  5019.8  278.23  5029.9  279.89
  5040.1  279.44  5050.2   281.5  5111.2  281.11  5212.7   284.1  5243.2   285.9
  5253.4  285.64  5468.8  298.12  5507.2  298.79    5558  302.28    5636  305.82
#Mann= 4 ,-1 , 0
  4312.6     .17       0    4786     .15       0  4954.5     .09       0
  5050.2     .15       0
Bank Sta=4954.5,5050.2
XS Rating Curve= 0 ,0
Exp/Cntr=0.3,0.1

Type RM Length L Ch R = 1 ,15390   ,998,998,998
BEGIN DESCRIPTION:
POLE CREEK 29.0
END DESCRIPTION:
XS GIS Cut Line= 3
       3748421.4      10177147.3      3747981.71     10176798.24
      3747301.42     10176554.92
#Sta/Elev= 30
  4438.6  301.59  4523.6  298.68  4587.6  293.55    4687  288.15  4709.4  285.37
  4744.7  284.13  4787.9  280.56  4823.2  280.53  4852.5   279.3  4893.7  278.88
  4972.2  280.05  4979.4  277.91  4986.6  272.08    4993  272.58    5006  271.15
  5009.9  271.15  5014.7  275.49  5025.3  277.33  5046.6  277.48  5064.2  279.79
  5069.5  277.85  5078.4  279.07  5120.4  279.77  5131.5  278.12  5156.5  277.21
  5205.9  279.88  5227.1  281.96  5361.7  288.62  5460.8  293.61  5722.5  302.07
#Mann= 5 ,-1 , 0
  4438.6     .17       0  4852.5     .15       0  4972.2     .09       0
  5064.2     .15       0  5361.7     .17       0
Bank Sta=4972.2,5064.2
XS Rating Curve= 0 ,0
Exp/Cntr=0.3,0.1

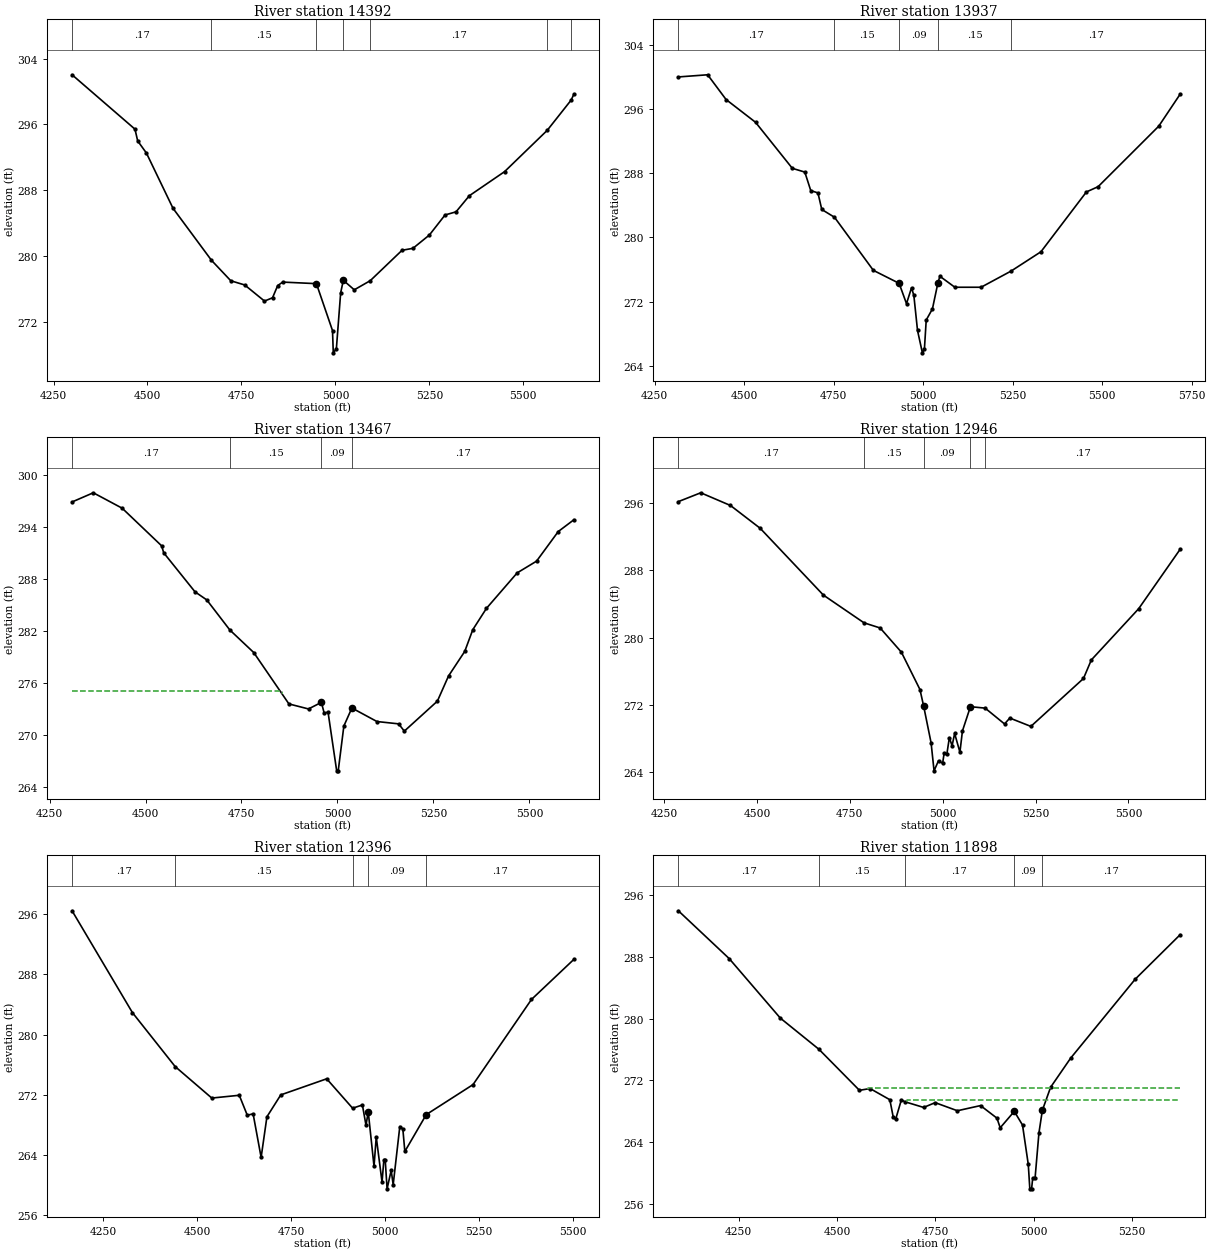
Type RM Length L Ch R = 1 ,14392   ,455,455,455
BEGIN DESCRIPTION:
POLE CREEK 28.0
END DESCRIPTION:
XS GIS Cut Line= 3
      3748667.85     10177011.07      3748309.08     10176409.19
      3747802.03     10176027.92
#Sta/Elev= 30
  4299.3  302.05  4466.7  295.43  4473.9     294  4497.2  292.52  4567.9   285.8
  4670.3  279.47  4721.7  276.98  4758.7  276.47  4811.3  274.51  4832.7  274.91
  4846.5   276.4  4859.9  276.82  4949.5  276.63  4992.3  270.92  4994.4  268.21
  5002.6  268.71    5014  275.51  5021.1  277.04  5050.2  275.88  5092.7  276.99
  5177.3  280.69  5206.4  280.93  5250.1  282.55  5291.8  284.99    5321  285.37
  5356.4  287.33  5450.1  290.26  5563.7  295.29  5627.3  298.97  5634.4  299.67
#Mann= 7 ,-1 , 0
  4299.3     .17       0  4670.3     .15       0  4949.5     .09       0
  5021.1     .15       0  5092.7     .17       0  5563.7     .11       0
  5627.3     .17       0
Bank Sta=4949.5,5021.1
XS Rating Curve= 0 ,0
Exp/Cntr=0.3,0.1

Type RM Length L Ch R = 1 ,13937   ,470,470,470
BEGIN DESCRIPTION:
POLE CREEK 27.0
END DESCRIPTION:
XS GIS Cut Line= 3
      3748825.57      10176940.6      3748664.88     10176275.74
      3748455.33     10175589.21
#Sta/Elev= 30
    4316  300.04  4397.8  300.31  4449.3  297.22  4531.6  294.38  4634.4  288.63
  4669.3  288.16  4685.9  285.85    4706  285.56  4716.7  283.49  4752.2  282.52
  4860.8  275.89  4932.8  274.27  4953.4  271.73  4967.4  273.71  4973.9  272.77
  4984.2  268.38  4997.8  265.59  5003.5  266.09  5008.5  269.69  5025.8  271.07
  5041.3  274.35  5046.7  275.15  5088.5  273.78  5161.7  273.78  5245.6   275.8
    5329  278.21    5456  285.68  5488.8  286.34  5658.1  293.89  5717.8  297.88
#Mann= 5 ,-1 , 0
    4316     .17       0  4752.2     .15       0  4932.8     .09       0
  5041.3     .15       0  5245.6     .17       0
Bank Sta=4932.8,5041.3
XS Rating Curve= 0 ,0
Exp/Cntr=0.3,0.1

Type RM Length L Ch R = 1 ,13467   ,521,521,521
BEGIN DESCRIPTION:
POLE CREEK 26.0
END DESCRIPTION:
XS GIS Cut Line= 3
      3749087.81     10176715.35      3748954.39     10176037.04
       3748598.1      10175534.9
#Sta/Elev= 30
  4308.7  296.93    4364  297.99  4439.2  296.21    4542  291.87  4547.5  291.06
    4629  286.56  4659.6  285.63  4719.7  282.16  4781.9  279.56  4873.6  273.63
  4924.6  273.05  4958.2  273.81  4965.3  272.59  4975.5  272.68    4998  265.91
    5002  265.91  5016.7  271.08  5037.6  273.16  5102.8   271.6  5159.4  271.33
  5174.2  270.49  5260.3  273.95  5289.3  276.85  5331.6  279.69  5352.5  282.19
  5388.2  284.66  5468.2  288.75  5518.6   290.1  5575.2  293.52  5615.7  294.87
#Mann= 4 ,-1 , 0
  4308.7     .17       0  4719.7     .15       0  4958.2     .09       0
  5037.6     .17       0
#XS Ineff= 2 , 0
       0  4855.4  275.12               0
Permanent Ineff=
       F       F
Bank Sta=4958.2,5037.6
XS Rating Curve= 0 ,0
Exp/Cntr=0.3,0.1

Type RM Length L Ch R = 1 ,12946   ,550,550,550
BEGIN DESCRIPTION:
POLE CREEK 25.0
END DESCRIPTION:
XS GIS Cut Line= 3
      3749177.29     10176641.34       3749184.6     10175929.98
      3748748.42     10175462.73
#Sta/Elev= 30
  4288.6  296.15  4348.9   297.2  4428.9  295.69  4508.9  292.98  4678.9  285.05
  4788.4  281.75  4831.8  281.14  4888.9  278.27  4938.9  273.83 4948.59  271.92
  4968.9   267.5  4976.9  264.17  4988.9  265.38    5000  265.07    5004  266.27
  5011.3  266.14  5018.1  268.12  5025.4  267.14  5032.3  268.61  5046.5  266.38
  5053.3  268.91  5074.8  271.79  5114.4  271.62  5166.6  269.74  5180.8  270.44
  5237.5  269.45  5379.1  275.14  5400.2  277.34  5527.7  283.43  5639.2  290.48
#Mann= 5 ,-1 , 0
  4288.6     .17       0  4788.4     .15       0 4948.59     .09       0
  5074.8     .17       0  5114.4     .17       0
Bank Sta=4948.59,5074.8
XS Rating Curve= 0 ,0
Exp/Cntr=0.3,0.1

Type RM Length L Ch R = 1 ,12396   ,498,498,498
BEGIN DESCRIPTION:
POLE CREEK 24.0
END DESCRIPTION:
XS GIS Cut Line= 3
      3749954.78     10176045.87      3749244.47     10175612.46
      3748771.21     10175447.45
#Sta/Elev= 30
  4167.9  296.47  4328.3  282.93  4441.8  275.76  4539.2  271.57  4612.2  271.94
  4633.5  269.29    4649  269.47  4670.3  263.68  4685.7  269.08  4722.5  271.99
  4844.5  274.13  4913.4  270.22  4939.4  270.65    4949  267.95  4954.9  269.75
  4970.3   262.5  4976.2   266.4  4991.6  260.39  4996.5  263.38    5000  263.38
    5005   259.5  5015.9  261.95  5021.2  260.05  5038.8  267.78  5046.9  267.45
  5052.2  264.47  5109.1  269.37  5233.4  273.36  5388.7  284.68  5501.2     290
#Mann= 5 ,-1 , 0
  4167.9     .17       0  4441.8     .15       0  4913.4     .17       0
  4954.9     .09       0  5109.1     .17       0
#XS Ineff= 2 , 0
       0  4844.5  274.13               0
Permanent Ineff=
       F       F
Bank Sta=4954.9,5109.1
XS Rating Curve= 0 ,0
Exp/Cntr=0.3,0.1

Type RM Length L Ch R = 1 ,11898   ,496,496,496
BEGIN DESCRIPTION:
POLE CREEK 23.0
END DESCRIPTION:
XS GIS Cut Line= 3
      3750041.18     10175839.17      3749308.82     10175310.06
      3749002.13     10175099.17
#Sta/Elev= 30
  4096.5  293.98  4225.7  287.78  4355.7  280.06    4454  276.01  4556.9  270.69
  4583.9  270.92  4634.2  269.47  4642.7  267.25  4648.9  266.92  4663.6  269.47
  4671.7  269.22  4720.1  268.47  4749.5  269.09  4805.9  268.04  4864.8  268.71
  4906.5  267.08  4914.8  265.83  4950.6  267.96  4971.5  266.19  4986.2  261.07
  4990.1  257.91  4994.6  257.91  4997.5  259.33  5003.5  259.33  5013.3  265.17
    5022   268.1    5043  271.09  5093.7  274.85  5258.1  285.11  5372.2  290.87
#Mann= 5 ,-1 , 0
  4096.5     .17       0    4454     .15       0  4671.7     .17       0
  4950.6     .09       0    5022     .17       0
#XS Ineff= 2 ,-1
  4678.3  4619.5  269.48  4577.7  4548.3  270.96
Permanent Ineff=
       F       F
Bank Sta=4950.6,5022
XS Rating Curve= 0 ,0
Exp/Cntr=0.3,0.1

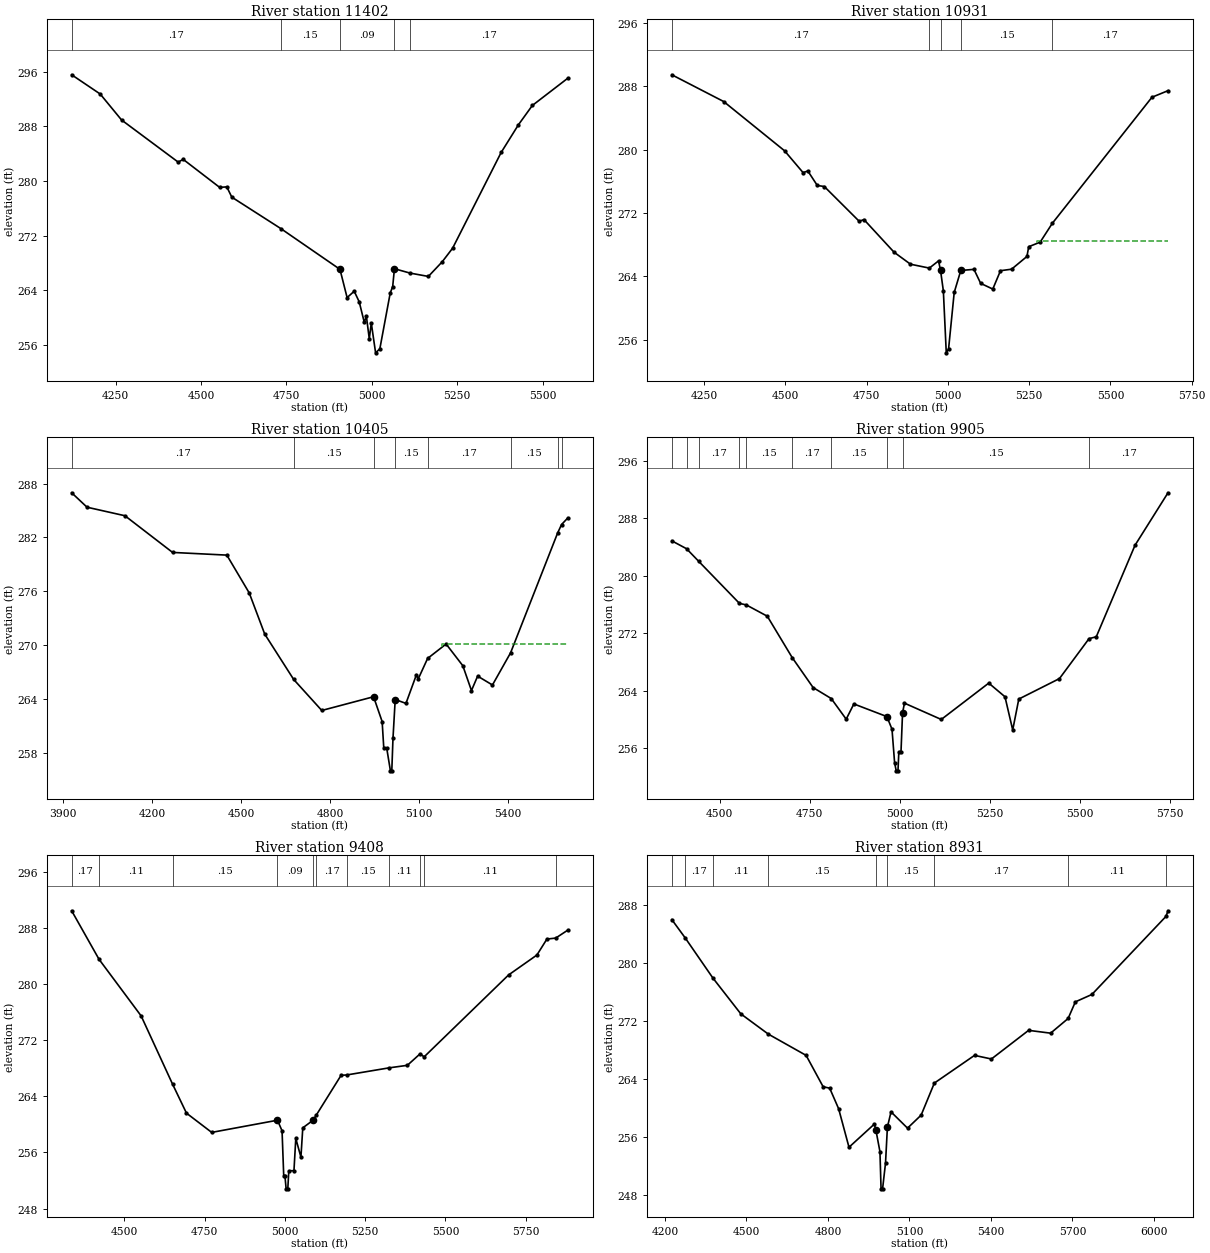
Type RM Length L Ch R = 1 ,11402   ,471,471,471
BEGIN DESCRIPTION:
POLE CREEK 22.0
END DESCRIPTION:
XS GIS Cut Line= 3
      3750155.32     10175718.84      3749640.83     10175006.64
      3749075.44     10174910.49
#Sta/Elev= 30
  4121.4  295.58  4204.9  292.76  4267.5  288.95  4433.1  282.78  4447.8  283.18
  4554.6  279.07  4575.4  279.15  4590.1  277.64  4733.7  273.03  4906.6  267.06
  4927.5  262.92  4948.3  263.85    4963  262.29  4977.7   259.3  4983.9  260.18
  4992.4  256.89  4998.3  259.18  5010.9  254.82  5023.3  255.41  5053.7  263.59
  5060.9  264.53    5066  267.15  5111.7  266.51  5165.3  266.02  5205.9  268.17
  5236.3  270.16  5378.3  284.19    5429  288.26  5469.6  291.08  5573.5  295.08
#Mann= 5 ,-1 , 0
  4121.4     .17       0  4733.7     .15       0  4906.6     .09       0
    5066     .15       0  5111.7     .17       0
Bank Sta=4906.6,5066
XS Rating Curve= 0 ,0
Exp/Cntr=0.3,0.1

Type RM Length L Ch R = 1 ,10931   ,526,526,526
BEGIN DESCRIPTION:
POLE CREEK 21.0
END DESCRIPTION:
XS GIS Cut Line= 3
       3750303.4     10175397.96      3749816.91     10174701.68
      3749151.17     10174577.59
#Sta/Elev= 30
  4150.6  289.48  4310.1   286.1  4497.6  279.87  4554.3  277.12  4569.1  277.32
  4598.2  275.49  4619.7  275.36    4727  270.97  4741.8  271.18  4834.3  267.06
  4884.9  265.54  4942.9  265.05  4971.2  265.96  4977.3  264.77    4986  262.18
    4995  254.34  5002.1  254.84  5019.4  261.97  5039.7  264.75  5080.2  264.89
  5100.8  263.12  5138.1   262.4  5161.8  264.72  5195.9  264.91  5243.2  266.52
  5248.6  267.75  5283.9  268.33  5321.3  270.71  5627.8  286.64  5677.2  287.47
#Mann= 5 ,-1 , 0
  4150.6     .17       0  4942.9     .15       0  4977.3     .09       0
  5039.7     .15       0  5321.3     .17       0
#XS Ineff= 2 , 0
       0                  5273.7       0  268.42
Permanent Ineff=
       F       F
Bank Sta=4977.3,5039.7
XS Rating Curve= 0 ,0
Exp/Cntr=0.3,0.1

Type RM Length L Ch R = 1 ,10405   ,500,500,500
BEGIN DESCRIPTION:
POLE CREEK 20.0
END DESCRIPTION:
XS GIS Cut Line= 3
      3750334.25     10175262.19      3749903.53     10174282.71
       3749424.1     10173920.12
#Sta/Elev= 30
    3930  286.97  3981.8  285.36  4109.4  284.41  4269.9  280.32  4452.6  280.02
  4528.1   275.8  4580.3  271.21  4677.7  266.16  4772.4   262.7  4946.8  264.23
  4975.7  261.46  4981.1  258.56  4990.9  258.54  5003.6  255.97  5008.2  255.97
  5012.2  259.59  5019.7  263.92  5055.9  263.49  5091.3   266.7  5097.5  266.24
  5128.8   268.5  5191.1  270.11  5247.4  267.69  5276.5  264.92  5297.3  266.53
  5347.2  265.54  5408.3  269.13    5567  282.51    5580  283.43  5601.1  284.17
#Mann= 8 ,-1 , 0
    3930     .17       0  4677.7     .15       0  4946.8     .09       0
  5019.7     .15       0  5128.8     .17       0  5408.3     .15       0
    5567     .11       0    5580     .17       0
#XS Ineff= 2 , 0
       0                  5176.6       0  270.11
Permanent Ineff=
       F       F
Bank Sta=4946.8,5019.7
XS Rating Curve= 0 ,0
Exp/Cntr=0.3,0.1

Type RM Length L Ch R = 1 ,9905    ,497,497,497
BEGIN DESCRIPTION:
POLE CREEK 19.0
END DESCRIPTION:
XS GIS Cut Line= 3
       3750673.1     10174400.99      3750219.19     10173959.23
      3749527.26     10173682.25
#Sta/Elev= 30
  4366.6  284.84  4407.6  283.74  4440.9  282.01  4554.4  276.14  4573.6  275.92
  4631.9  274.35  4701.1  268.59  4759.2  264.42  4809.6  262.89  4851.1  260.02
  4872.4  262.14  4964.2  260.38  4978.4  258.62  4985.6  253.97  4990.1  252.83
    4995  252.83  4997.4  255.49  5003.4  255.49  5007.7   260.9    5013  262.25
  5115.3  259.98  5247.2  265.04  5292.3  263.14  5313.8  258.52  5330.7  262.82
  5443.7  265.67  5525.9  271.23    5546  271.49  5653.7  284.23  5745.3  291.53
#Mann= 10 ,-1 , 0
  4366.6     .17       0  4407.6     .11       0  4440.9     .17       0
  4554.4     .11       0  4573.6     .15       0  4701.1     .17       0
  4809.6     .15       0  4964.2     .09       0  5007.7     .15       0
  5525.9     .17       0
#XS Ineff= 2 , 0
       0                  5247.2       0  265.04
Permanent Ineff=
       F       F
Bank Sta=4964.2,5007.7
XS Rating Curve= 0 ,0
Exp/Cntr=0.3,0.1

Type RM Length L Ch R = 1 ,9408    ,477,477,477
BEGIN DESCRIPTION:
POLE CREEK 18.0
END DESCRIPTION:
XS GIS Cut Line= 3
      3750886.66     10174067.67      3750445.89     10173570.54
      3749673.38     10173145.95
#Sta/Elev= 30
  4335.6  290.52  4420.9  283.59    4552  275.51  4650.1  265.75  4693.3  261.62
  4771.9  258.87  4976.8  260.61  4991.1   259.1  4996.3  252.68    5000  252.68
  5003.8  250.81    5009  250.81  5012.1  253.38  5028.2  253.41  5033.9  258.01
  5049.9  255.33  5055.7  259.52  5087.8  260.61  5098.4  261.39    5175  267.02
  5192.3  267.07  5323.5  268.08  5381.5  268.45  5421.2  270.09  5433.8  269.66
    5697  281.36  5785.1   284.2  5816.3  286.48  5843.7  286.62  5881.5  287.76
#Mann= 11 ,-1 , 0
  4335.6     .17       0  4420.9     .11       0  4650.1     .15       0
  4976.8     .09       0  5087.8     .15       0  5098.4     .17       0
  5192.3     .15       0  5323.5     .11       0  5421.2     .17       0
  5433.8     .11       0  5843.7     .17       0
Bank Sta=4976.8,5087.8
XS Rating Curve= 0 ,0
Exp/Cntr=0.3,0.1

Type RM Length L Ch R = 1 ,8931    ,424,424,424
BEGIN DESCRIPTION:
POLE CREEK 17.0
END DESCRIPTION:
XS GIS Cut Line= 3
      3751490.83     10173473.93      3750749.71     10173249.36
      3749711.25     10173083.57
#Sta/Elev= 30
  4225.6  286.04  4274.8  283.51  4376.8  277.96  4479.5  273.01  4580.7  270.21
  4719.8  267.27  4782.5  262.93  4806.5  262.74  4839.4   259.9  4877.6  254.57
  4970.6  257.76  4976.3  257.01  4991.5  253.96  4995.6  248.82  5001.2  248.82
    5012  252.38    5019  257.37  5032.3  259.46    5093  257.21  5143.1  259.01
  5191.7  263.44  5339.6  267.27  5401.7  266.77  5538.6  270.73  5619.6  270.34
    5684  272.37  5710.7  274.67  5771.5  275.69  6044.3  286.49  6051.6  287.26
#Mann= 9 ,-1 , 0
  4225.6     .11       0  4274.8     .17       0  4376.8     .11       0
  4580.7     .15       0  4976.3     .09       0    5019     .15       0
  5191.7     .17       0    5684     .11       0  6044.3     .17       0
Bank Sta=4976.3,5019
XS Rating Curve= 0 ,0
Exp/Cntr=0.3,0.1