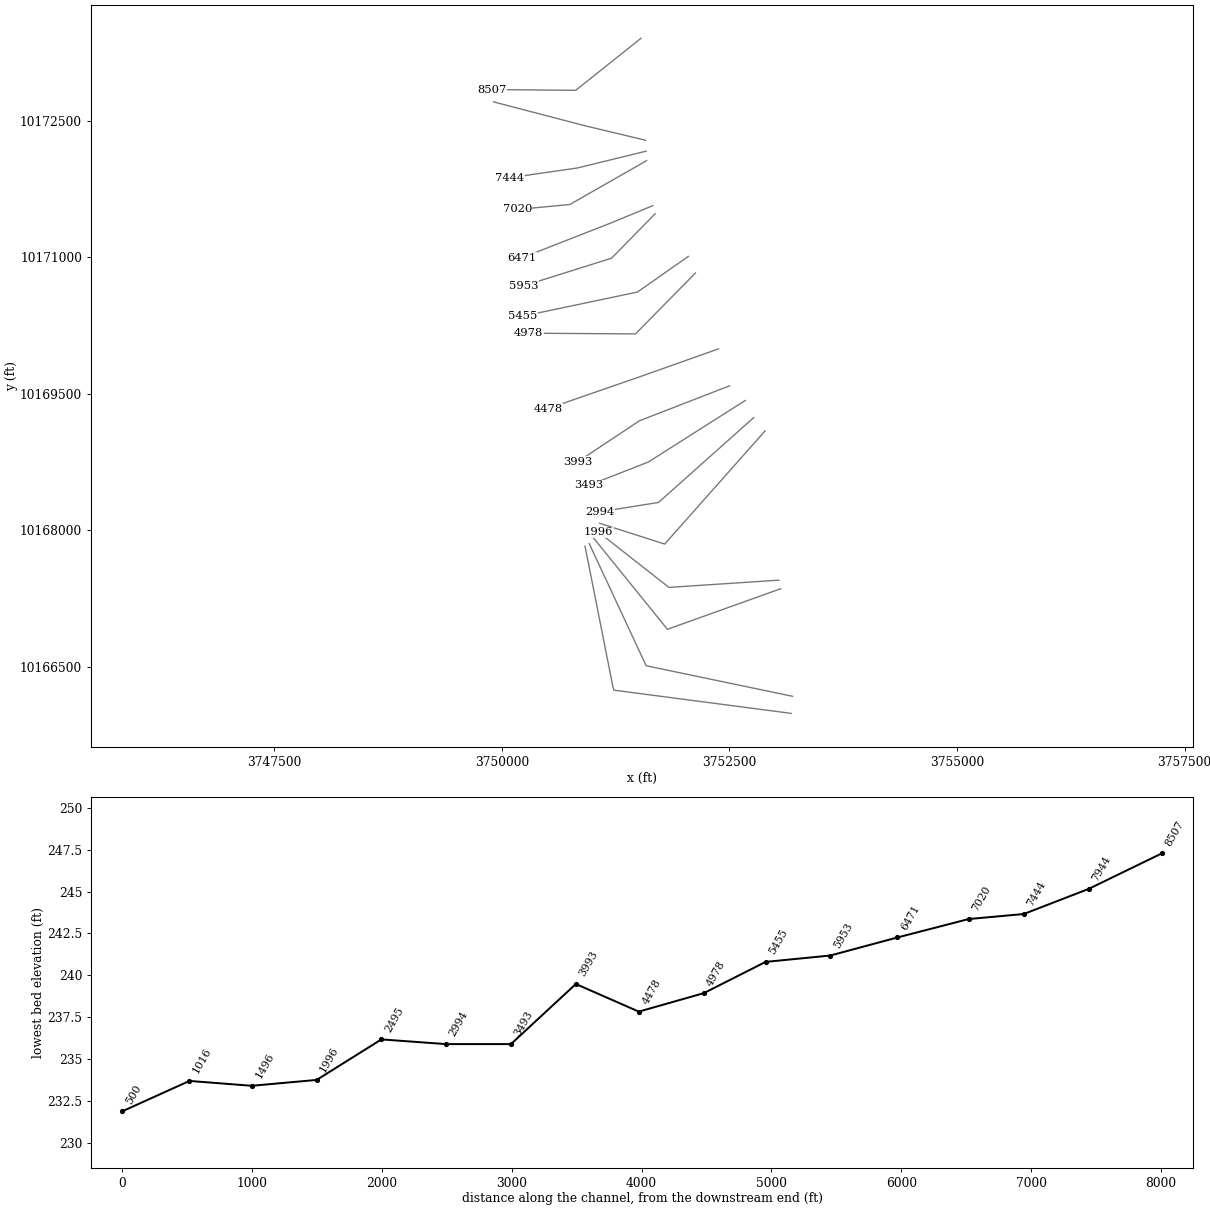
HEC-RAS study POLE CREEK.prj: POLE CREEK Base Level Engineering

--- POLE CREEK.g01 (geometry) --- (continued)

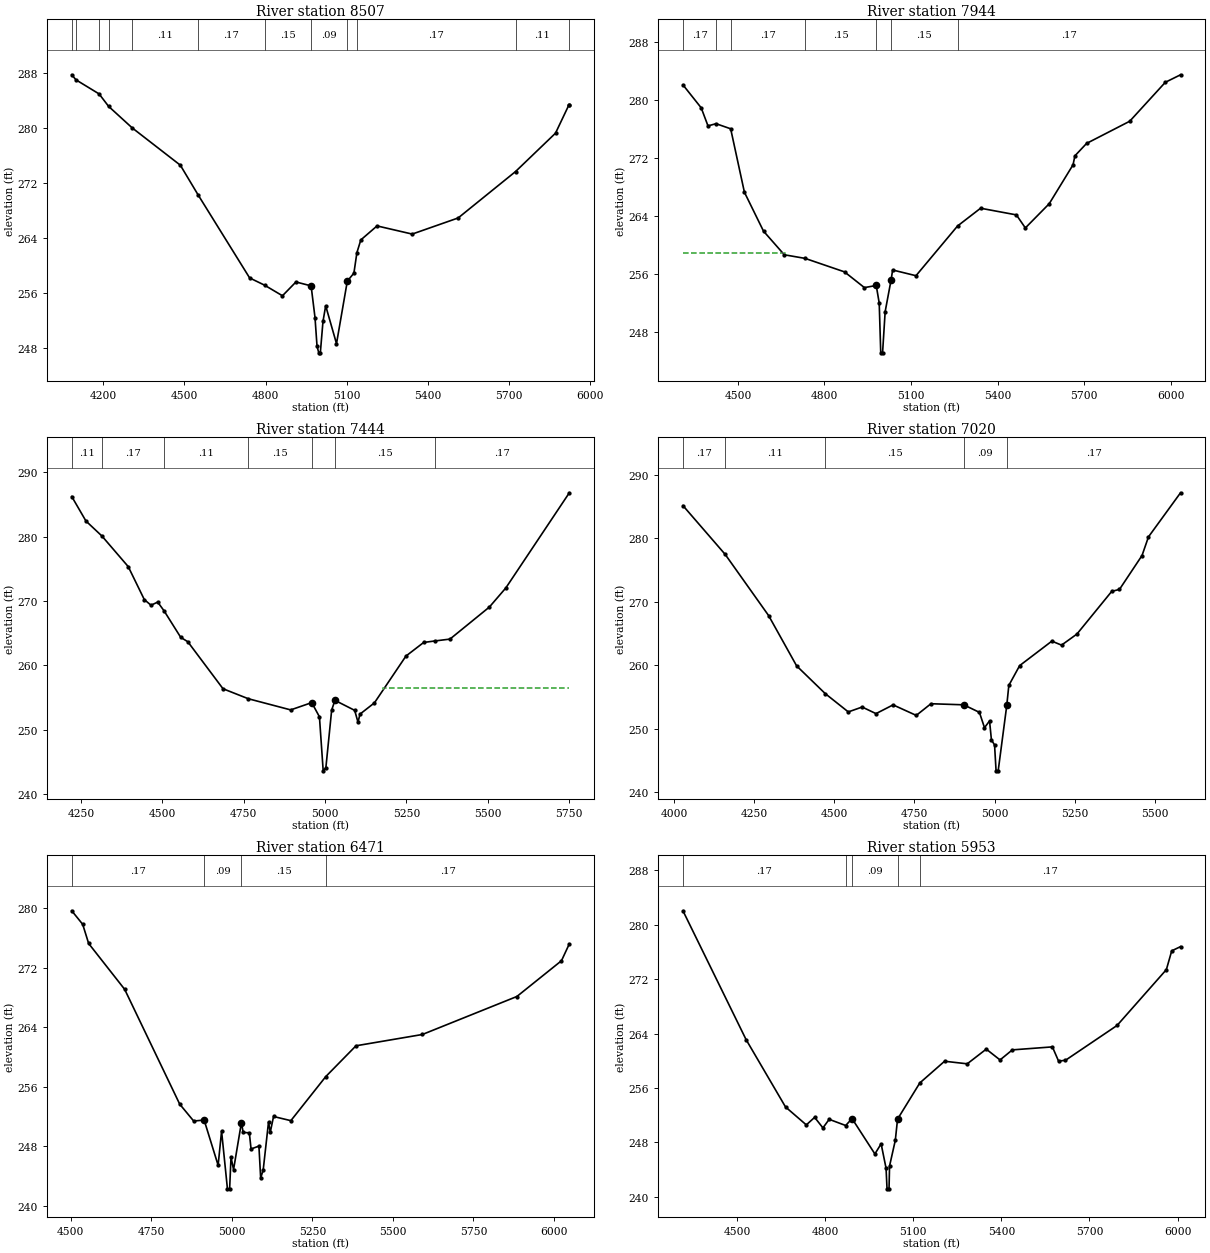
Type RM Length L Ch R = 1 ,8507    ,563,563,563
BEGIN DESCRIPTION:
POLE CREEK 16.0
END DESCRIPTION:
XS GIS Cut Line= 3
      3751527.31     10173406.24      3750810.47     10172834.86
      3749886.71     10172843.72
#Sta/Elev= 30
  4083.3  287.81  4099.1  287.07  4184.5  285.02  4219.8   283.2  4306.9  280.07
    4485  274.63  4551.2  270.27  4741.3   258.2  4796.7  257.14  4862.7   255.6
  4912.6  257.61  4968.7  257.04  4983.1  252.43  4990.6  248.24  4997.1  247.28
  5002.8  247.28  5012.6  251.85  5022.6  254.14  5062.6  248.62  5102.6  257.73
    5127   258.9  5138.1  261.89  5152.6  263.74  5212.6  265.78  5342.6  264.59
  5512.6  266.94  5724.7   273.7  5872.7   279.3  5922.2  283.41  5923.8  283.41
#Mann= 12 ,-1 , 0
  4083.3     .11       0  4099.1     .17       0  4184.5     .11       0
  4219.8     .17       0  4306.9     .11       0  4551.2     .17       0
  4796.7     .15       0  4968.7     .09       0  5102.6     .15       0
  5138.1     .17       0  5724.7     .11       0  5922.2     .17       0
Bank Sta=4968.7,5102.6
XS Rating Curve= 0 ,0
Exp/Cntr=0.3,0.1

Type RM Length L Ch R = 1 ,7944    ,500,500,500
BEGIN DESCRIPTION:
POLE CREEK 15.0
END DESCRIPTION:
XS GIS Cut Line= 3
       3751579.4     10172286.43       3750907.9     10172446.87
       3749907.5     10172708.31
#Sta/Elev= 30
  4309.6  282.13  4372.9  278.96  4396.4  276.47  4424.4  276.77    4475  276.07
  4522.6  267.32  4588.8  261.95  4660.8  258.69  4732.9  258.19  4869.5  256.33
  4938.4  254.16  4979.5  254.45  4989.8  252.02  4995.1  245.16  5001.4  245.16
  5010.4  250.85  5031.1  255.25  5036.3  256.59  5117.2   255.8  5261.3  262.66
  5341.1  265.11  5465.2  264.19  5496.2  262.39  5578.9  265.73  5661.5   271.1
    5668  272.34  5708.4  274.05  5857.9  277.11  5981.2  282.48    6034  283.52
#Mann= 7 ,-1 , 0
  4309.6     .17       0  4424.4     .11       0    4475     .17       0
  4732.9     .15       0  4979.5     .09       0  5031.1     .15       0
  5261.3     .17       0
#XS Ineff= 2 , 0
       0    4671     259               0
Permanent Ineff=
       F       F
Bank Sta=4979.5,5031.1
XS Rating Curve= 0 ,0
Exp/Cntr=0.3,0.1

Type RM Length L Ch R = 1 ,7444    ,424,424,424
BEGIN DESCRIPTION:
POLE CREEK 14.0
END DESCRIPTION:
XS GIS Cut Line= 3
      3751584.56     10172166.63      3750828.18     10171981.54
      3750084.58     10171874.97
#Sta/Elev= 30
  4221.3   286.2    4265   282.4  4314.2  280.07    4395  275.33  4444.4  270.22
    4465  269.34  4485.6  269.83  4505.2  268.47  4556.4  264.36  4578.2  263.68
  4686.4  256.39  4764.2  254.84  4894.5  253.11  4959.2  254.24  4982.9  252.04
  4994.4  243.66  5002.7  244.16  5020.5  253.09  5030.6  254.59  5091.2  253.04
  5101.4  251.21  5107.7  252.46  5151.9   254.2  5248.9  261.46  5303.4  263.57
  5337.7   263.8  5384.2  264.09  5505.4  269.06  5555.9  272.02  5751.2  286.78
#Mann= 7 ,-1 , 0
  4221.3     .11       0  4314.2     .17       0  4505.2     .11       0
  4764.2     .15       0  4959.2     .09       0  5030.6     .15       0
  5337.7     .17       0
#XS Ineff= 2 , 0
       0                  5178.3       0  256.55
Permanent Ineff=
       F       F
Bank Sta=4959.2,5030.6
XS Rating Curve= 0 ,0
Exp/Cntr=0.3,0.1

Type RM Length L Ch R = 1 ,7020    ,549,549,549
BEGIN DESCRIPTION:
POLE CREEK 13.0
END DESCRIPTION:
XS GIS Cut Line= 3
      3751589.81     10172062.49      3750745.81     10171580.36
      3750168.26     10171526.05
#Sta/Elev= 30
    4028  285.18  4159.7  277.49  4295.1  267.85  4382.6  259.91  4471.8  255.54
  4543.8  252.65    4587  253.42  4630.2  252.38  4683.5  253.76  4755.8   252.1
  4801.6  253.94  4903.8  253.77  4952.8  252.58  4968.6  250.16  4984.4  251.23
  4990.2  248.25    5000  247.44  5004.7  243.36  5011.3  243.36  5038.1  253.68
  5044.5  256.83  5078.3  259.95  5178.7  263.81  5208.9  263.18  5256.8  264.92
  5365.4  271.65  5389.7  271.97    5460  277.31  5480.1  280.25  5580.1   287.2
#Mann= 5 ,-1 , 0
    4028     .17       0  4159.7     .11       0  4471.8     .15       0
  4903.8     .09       0  5038.1     .17       0
Bank Sta=4903.8,5038.1
XS Rating Curve= 0 ,0
Exp/Cntr=0.3,0.1

Type RM Length L Ch R = 1 ,6471    ,518,518,518
BEGIN DESCRIPTION:
POLE CREEK 12.0
END DESCRIPTION:
XS GIS Cut Line= 3
      3751657.54      10171567.7      3751198.66     10171377.87
      3750223.14     10170995.99
#Sta/Elev= 30
  4503.4  279.66  4537.4  277.84  4555.9  275.26  4667.7  269.09  4838.5  253.65
  4881.8  251.38  4914.3  251.51  4957.7  245.43  4968.4  250.02  4986.6  242.26
  4993.4  242.26  4997.7  246.51  5005.6  244.85    5030  251.18  5035.4  249.84
  5054.5   249.8  5059.9  247.62  5084.3  248.01  5089.7  243.73  5097.5  244.77
  5114.1  251.25  5119.5  249.87  5129.7  251.99  5183.4  251.43  5291.8  257.36
  5385.5   261.5  5591.5  263.02  5884.8  268.13  6023.2  272.94  6047.6  275.21
#Mann= 4 ,-1 , 0
  4503.4     .17       0  4914.3     .09       0    5030     .15       0
  5291.8     .17       0
Bank Sta=4914.3,5030
XS Rating Curve= 0 ,0
Exp/Cntr=0.3,0.1

Type RM Length L Ch R = 1 ,5953    ,498,498,498
BEGIN DESCRIPTION:
POLE CREEK 11.0
END DESCRIPTION:
XS GIS Cut Line= 3
      3751683.57     10171479.17      3751205.21     10170990.82
      3750241.85     10170687.79
#Sta/Elev= 30
  4316.4  282.06  4531.2  263.13  4665.5  253.22  4736.3  250.58  4764.6  251.69
  4792.8  250.14  4814.1   251.4  4870.3  250.49  4891.9  251.51  4969.7  246.31
  4990.9   247.8  5007.7  244.21    5011  241.18  5017.8  241.18  5019.6  244.54
  5039.2  248.32  5046.8  251.43  5122.6  256.75  5206.9  259.94    5284  259.56
  5348.7  261.72  5395.6  260.13  5437.5  261.61  5573.8  262.05  5594.8  259.96
  5618.3  260.08  5793.9   265.2  5961.7  273.41  5979.9  276.17  6009.9  276.79
#Mann= 5 ,-1 , 0
  4316.4     .17       0  4870.3     .15       0  4891.9     .09       0
  5046.8     .15       0  5122.6     .17       0
Bank Sta=4891.9,5046.8
XS Rating Curve= 0 ,0
Exp/Cntr=0.3,0.1

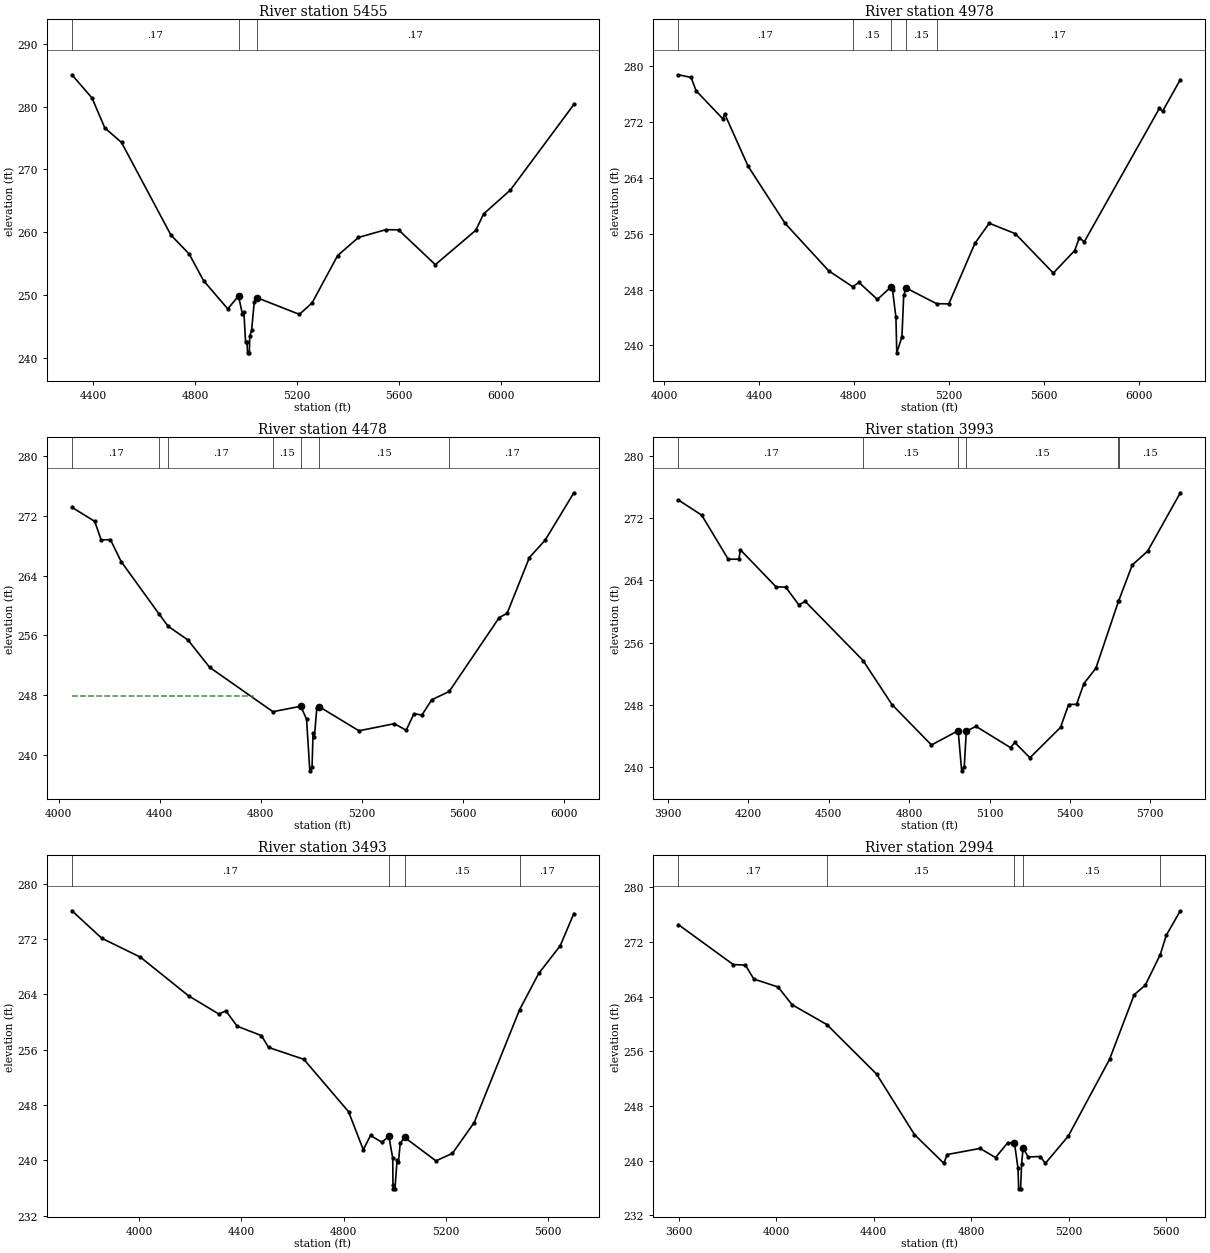
Type RM Length L Ch R = 1 ,5455    ,477,477,477
BEGIN DESCRIPTION:
POLE CREEK 10.0
END DESCRIPTION:
XS GIS Cut Line= 3
       3752048.1     10171010.38      3751488.37     10170618.47
      3750231.61     10170354.39
#Sta/Elev= 30
  4316.7  285.08  4395.2  281.39  4445.7  276.61  4511.1   274.3  4704.7  259.55
  4776.2  256.54  4832.8  252.29  4927.4   247.8  4969.7  249.85  4984.5  247.03
  4990.6  247.36  4997.3  242.54  5002.8  242.54  5005.2   240.8  5012.1   240.8
  5013.7  243.45    5021  244.38  5031.2  248.88  5041.4  249.59  5208.1  246.93
  5257.9  248.74  5358.2  256.29  5439.9  259.18  5546.9  260.41  5596.8  260.39
  5741.2  254.84  5899.7  260.31  5930.4  262.92  6035.3  266.72  6284.2  280.35
#Mann= 3 ,-1 , 0
  4316.7     .17       0  4969.7     .09       0  5041.4     .17       0
Bank Sta=4969.7,5041.4
XS Rating Curve= 0 ,0
Exp/Cntr=0.3,0.1

Type RM Length L Ch R = 1 ,4978    ,500,500,500
BEGIN DESCRIPTION:
POLE CREEK 9.0
END DESCRIPTION:
XS GIS Cut Line= 3
      3752126.22     10170828.07      3751467.84     10170158.84
      3750292.96     10170166.64
#Sta/Elev= 30
  4061.2  278.81  4114.5  278.43  4135.7  276.52  4248.9  272.47  4255.9   273.2
  4354.9  265.68  4510.5   257.5  4694.3  250.69  4794.5  248.42  4821.6  249.02
  4899.4  246.59  4955.9  248.37  4963.1   247.9  4977.2  244.02  4980.8  238.93
  5002.5  241.24    5010   247.2    5020  248.23  5148.2  245.98    5200  245.95
    5310  254.64    5370  257.52    5480  256.02    5640  250.37    5730   253.6
    5750  255.47    5770  254.83  6087.2  274.02    6100  273.56  6174.9  278.12
#Mann= 5 ,-1 , 0
  4061.2     .17       0  4794.5     .15       0  4955.9     .09       0
    5020     .15       0  5148.2     .17       0
Bank Sta=4955.9,5020
XS Rating Curve= 0 ,0
Exp/Cntr=0.3,0.1

Type RM Length L Ch R = 1 ,4478    ,485,485,485
BEGIN DESCRIPTION:
POLE CREEK 8.0
END DESCRIPTION:
XS GIS Cut Line= 3
      3752381.42     10169994.75      3751488.29     10169678.69
      3750506.45     10169338.51
#Sta/Elev= 30
  4052.6  273.16  4142.6  271.28  4168.2  268.79  4204.9  268.83  4247.3  265.89
  4398.2  258.82  4433.1  257.22  4512.5  255.35  4597.4  251.71    4848  245.76
    4958  246.49  4981.2  244.76    4994  237.83  5002.9  238.33  5006.9  242.92
  5012.2  242.34  5021.6   246.2  5032.2  246.41  5188.5   243.2  5328.5  244.15
  5375.4  243.27  5406.5   245.5  5437.7  245.31  5476.7  247.36  5545.8  248.47
  5743.8  258.38    5775  258.95  5863.1  266.43  5925.4  268.75  6039.1  275.11
#Mann= 7 ,-1 , 0
  4052.6     .17       0  4398.2     .15       0  4433.1     .17       0
    4848     .15       0    4958     .09       0  5032.2     .15       0
  5545.8     .17       0
#XS Ineff= 2 , 0
       0  4770.2  247.83               0
Permanent Ineff=
       F       F
Bank Sta=4958,5032.2
XS Rating Curve= 0 ,0
Exp/Cntr=0.3,0.1

Type RM Length L Ch R = 1 ,3993    ,500,500,500
BEGIN DESCRIPTION:
POLE CREEK 7.0
END DESCRIPTION:
XS GIS Cut Line= 3
      3752501.29     10169588.53      3751511.66     10169204.58
      3750835.29     10168755.65
#Sta/Elev= 30
  3938.5  274.36  4025.4  272.41  4124.5  266.73  4164.3  266.74  4169.6  267.95
  4303.1  263.17  4339.1  263.14  4387.5  260.87    4412  261.29  4627.6  253.69
  4735.9     248    4883  242.81  4982.6  244.65  4995.7  239.48  5005.3  239.98
    5013  244.58  5049.1  245.21  5178.4  242.46  5193.4  243.15  5250.5  241.16
  5364.8  245.08  5394.9  248.02  5424.6  248.05    5452  250.72  5496.7   252.7
  5580.7  261.29  5581.3  261.34  5632.4  265.99  5689.6  267.76  5811.8  275.29
#Mann= 6 ,-1 , 0
  3938.5     .17       0  4627.6     .15       0  4982.6     .09       0
    5013     .15       0  5580.7     .17       0  5581.3     .15       0
#XS Ineff= 2 , 0
       0                  5394.9       0  248.02
Permanent Ineff=
       F       F
Bank Sta=4982.6,5013
XS Rating Curve= 0 ,0
Exp/Cntr=0.3,0.1

Type RM Length L Ch R = 1 ,3493    ,499,499,499
BEGIN DESCRIPTION:
POLE CREEK 6.0
END DESCRIPTION:
XS GIS Cut Line= 3
      3752673.09     10169427.03      3751607.52     10168750.67
      3750956.04     10168495.42
#Sta/Elev= 30
  3737.9  276.06  3854.1   272.1  4005.8  269.35  4194.2  263.76  4312.4  261.14
  4339.5  261.61  4383.7  259.38  4478.5  258.03  4506.4  256.32  4644.3   254.6
    4819  247.04  4876.6  241.54  4904.9   243.6  4949.5  242.62  4976.5  243.48
  4991.8  240.33  4992.7  236.39  4993.2  235.89  5000.5  235.89  5008.8  240.11
  5014.2  239.81  5021.1   242.5  5038.6  243.31  5160.7  239.93  5225.2  241.02
  5309.9  245.46  5487.4  261.75  5562.2     267  5646.3     271  5699.7  275.66
#Mann= 4 ,-1 , 0
  3737.9     .17       0  4976.5     .09       0  5038.6     .15       0
  5487.4     .17       0
Bank Sta=4976.5,5038.6
XS Rating Curve= 0 ,0
Exp/Cntr=0.3,0.1

Type RM Length L Ch R = 1 ,2994    ,499,499,499
BEGIN DESCRIPTION:
POLE CREEK 5.0
END DESCRIPTION:
XS GIS Cut Line= 3
      3752766.87     10169239.55       3751720.6     10168306.93
      3751070.89     10168203.41
#Sta/Elev= 30
  3598.4  274.53  3823.6  268.69  3872.9  268.62  3908.1  266.57  4007.5  265.41
  4064.4  262.83  4207.4  259.92  4411.4  252.68  4566.9  243.83  4687.3  239.63
  4701.5  240.91  4836.1   241.8  4899.6  240.47  4949.8  242.63  4977.4  242.58
  4991.6  238.96  4994.6  235.89  5002.3  235.89  5006.6  239.49  5012.9  241.92
  5033.2  240.55  5083.8  240.62    5104  239.61  5198.2  243.61  5367.3  254.82
  5468.6  264.29    5514  265.67  5575.6  270.15  5600.2  272.97  5657.9  276.56
#Mann= 5 ,-1 , 0
  3598.4     .17       0  4207.4     .15       0  4977.4     .09       0
  5012.9     .15       0  5575.6     .17       0
Bank Sta=4977.4,5012.9
XS Rating Curve= 0 ,0
Exp/Cntr=0.3,0.1

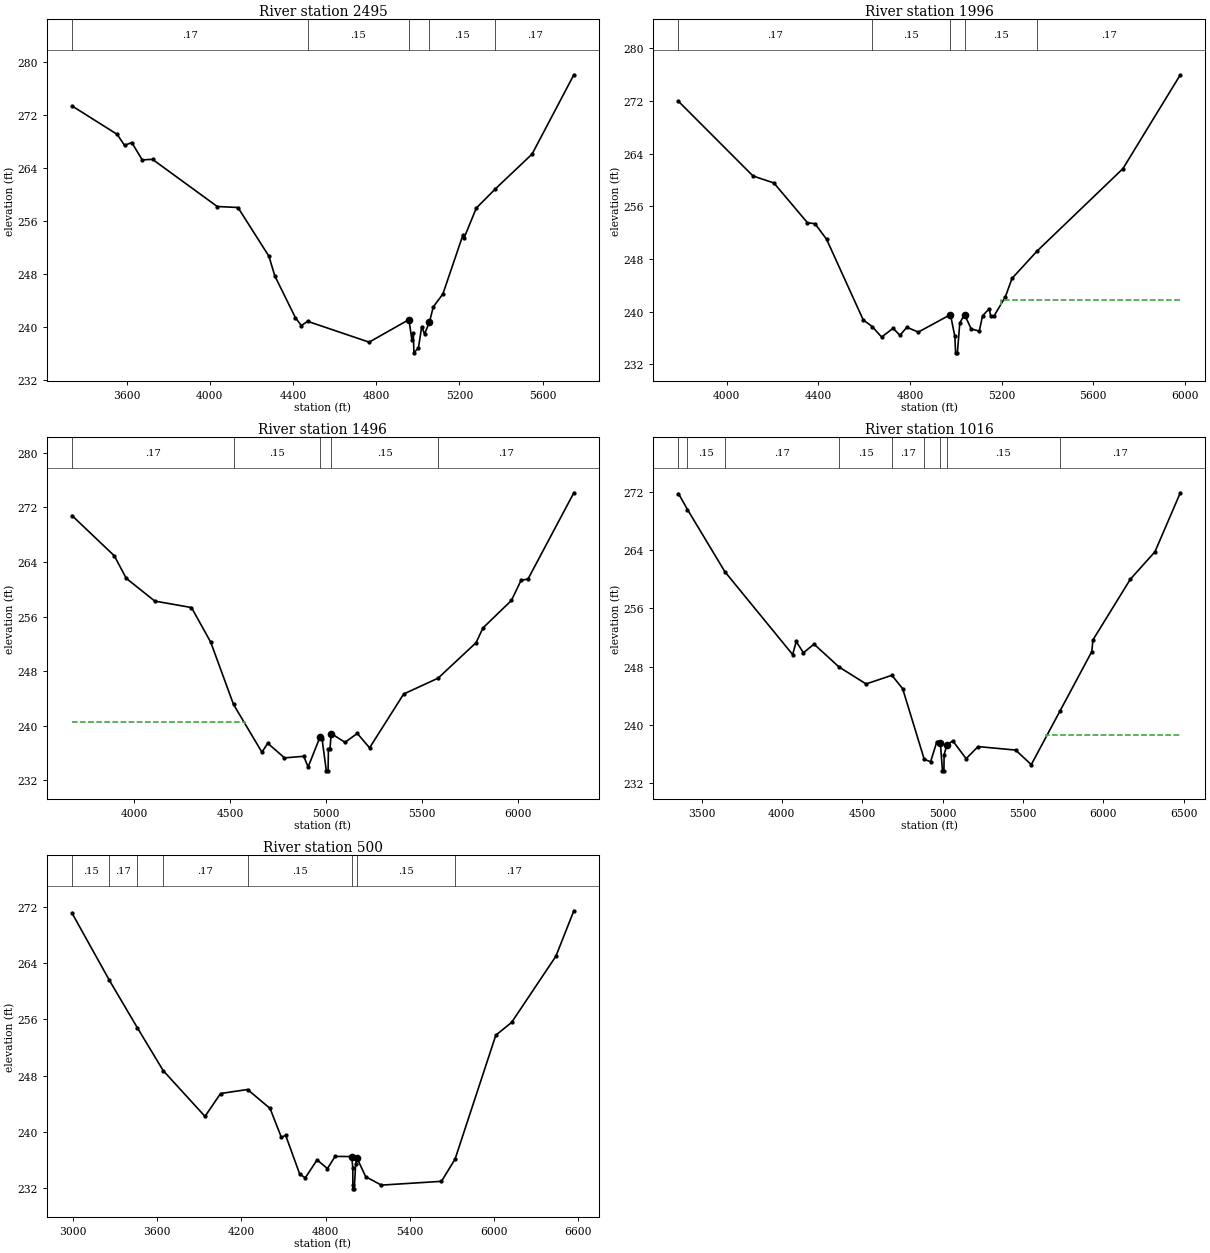
Type RM Length L Ch R = 1 ,2495    ,499,499,499
BEGIN DESCRIPTION:
POLE CREEK 4.0
END DESCRIPTION:
XS GIS Cut Line= 3
      3752891.88     10169093.73      3751788.71      10167849.7
      3751074.13     10168078.11
#Sta/Elev= 30
  3337.3   273.4  3554.7  269.11  3590.1  267.45  3625.2  267.87    3675  265.26
  3724.7  265.34  4035.9  258.23  4135.4  258.08  4284.2  250.74  4312.7  247.76
  4411.4  241.48  4439.8  240.28  4470.5  240.92    4766  237.78  4957.5  241.18
  4971.4  238.13  4978.4  239.19  4981.2  236.17  5003.1  236.92  5018.8  240.13
  5032.4  239.01  5056.2  240.83  5074.4   243.1  5120.5  245.04  5217.1  253.95
  5222.3  253.48  5281.4     258  5372.3  260.87  5549.3  266.13  5750.2  278.09
#Mann= 5 ,-1 , 0
  3337.3     .17       0  4470.5     .15       0  4957.5     .09       0
  5056.2     .15       0  5372.3     .17       0
Bank Sta=4957.5,5056.2
XS Rating Curve= 0 ,0
Exp/Cntr=0.3,0.1

Type RM Length L Ch R = 1 ,1996    ,500,500,500
BEGIN DESCRIPTION:
POLE CREEK 3.0
END DESCRIPTION:
XS GIS Cut Line= 3
      3753042.92      10167453.1      3751834.52     10167373.76
      3751063.74     10167979.15
#Sta/Elev= 30
    3789  271.93  4114.8  260.59  4205.8  259.53  4352.2   253.5  4385.3  253.34
  4435.5  251.01  4595.8  238.75  4634.9  237.74    4676  236.15  4726.1  237.47
  4756.1  236.41  4786.2  237.63  4836.3   236.9  4976.6  239.55  4995.8  236.24
    4999  233.75  5006.8  233.75  5017.4  238.29  5038.2  239.56  5067.1  237.38
  5102.4  237.05  5116.8  239.37  5145.7  240.44  5152.1  239.39  5166.5  239.33
  5216.2  242.24  5245.2  245.04  5355.7  249.23  5729.6  261.71  5980.1  275.95
#Mann= 5 ,-1 , 0
    3789     .17       0  4634.9     .15       0  4976.6     .09       0
  5038.2     .15       0  5355.7     .17       0
#XS Ineff= 2 , 0
       0                  5195.4       0  241.71
Permanent Ineff=
       F       F
Bank Sta=4976.6,5038.2
XS Rating Curve= 0 ,0
Exp/Cntr=0.3,0.1

Type RM Length L Ch R = 1 ,1496    ,480,480,480
BEGIN DESCRIPTION:
POLE CREEK 2.0
END DESCRIPTION:
XS GIS Cut Line= 3
      3753063.74     10167359.35      3751818.34     10166913.51
      3751006.71     10167916.32
#Sta/Elev= 30
  3677.2  270.82  3897.9  264.91  3959.6  261.62  4108.3  258.28  4299.5  257.33
  4399.7  252.25  4518.3  243.13    4666  236.14  4696.8  237.44  4783.7   235.3
  4883.7  235.53  4906.8  233.97  4968.7  238.37  4979.3  238.06  5001.5   233.4
  5010.6   233.4  5012.4  236.59  5020.4  236.53  5026.8  238.87  5098.7  237.58
  5162.7  238.88  5226.6  236.77  5404.1  244.66  5583.3  246.98  5781.4  252.19
  5816.6  254.33  5965.3  258.38  6014.9   261.3  6051.6  261.52  6290.1  274.15
#Mann= 5 ,-1 , 0
  3677.2     .17       0  4518.3     .15       0  4968.7     .09       0
  5026.8     .15       0  5583.3     .17       0
#XS Ineff= 2 , 0
       0    4579  240.62               0
Permanent Ineff=
       F       F
Bank Sta=4968.7,5026.8
XS Rating Curve= 0 ,0
Exp/Cntr=0.3,0.1

Type RM Length L Ch R = 1 ,1016    ,516,516,516
BEGIN DESCRIPTION:
POLE CREEK 1.0
END DESCRIPTION:
XS GIS Cut Line= 3
      3753193.99     10166177.05      3751584.85     10166512.85
      3750959.57     10167854.17
#Sta/Elev= 30
  3356.2  271.77  3412.6  269.57  3645.4  261.03  4067.3  249.65  4089.3  251.45
  4134.2   249.9  4200.1  251.09    4356  247.95  4524.1  245.62  4684.8  246.81
  4751.8  244.97  4885.9  235.29  4925.4  234.93    4964  237.64  4986.7  237.48
  4999.6  233.69  5008.7  233.69  5009.7   235.9    5027  237.26  5064.2   237.8
  5146.9  235.36    5221  237.02  5455.2  236.54  5552.2  234.54  5729.6  241.85
  5929.1  250.07  5935.9  251.66  6168.8     260    6322  263.77  6479.9  271.87
#Mann= 9 ,-1 , 0
  3356.2     .17       0  3412.6     .15       0  3645.4     .17       0
    4356     .15       0  4684.8     .17       0  4885.9     .15       0
  4986.7     .09       0    5027     .15       0  5729.6     .17       0
#XS Ineff= 2 , 0
       0                  5643.6       0  238.57
Permanent Ineff=
       F       F
Bank Sta=4986.7,5027
XS Rating Curve= 0 ,0
Exp/Cntr=0.3,0.1

Type RM Length L Ch R = 1 ,500     ,0,0,0
BEGIN DESCRIPTION:
POLE CREEK 1.5
END DESCRIPTION:
XS GIS Cut Line= 4
       3753178.3     10165989.56      3751230.85     10166244.55
       3751218.7     10166286.97      3750912.98     10167826.71
#Sta/Elev= 30
  2991.8  271.15  3257.9  261.59    3458  254.81  3642.2  248.71  3940.3  242.19
  4051.2  245.45  4243.8  246.02  4404.2  243.32  4484.9   239.2  4515.1  239.51
    4616  233.95  4655.4  233.45  4739.3     236  4813.1  234.77  4868.1   236.5
  4986.8  236.47  4993.9  234.84  4994.2  232.38  4994.7  231.88  5004.3  231.88
  5014.4  235.42  5024.6  236.23  5086.1   233.6  5197.9  232.41  5626.1  232.95
  5723.2  236.12  6013.5  253.75  6125.7  255.56  6441.7  264.99  6569.8  271.46
#Mann= 8 ,-1 , 0
  2991.8     .15       0  3257.9     .17       0    3458     .15       0
  3642.2     .17       0  4243.8     .15       0  4986.8     .09       0
  5024.6     .15       0  5723.2     .17       0
Bank Sta=4986.8,5024.6
XS Rating Curve= 0 ,0
Exp/Cntr=0.3,0.1

Chan Stop Cuts=-1
Use User Specified Reach Order=0
Composite Channel Slope=5