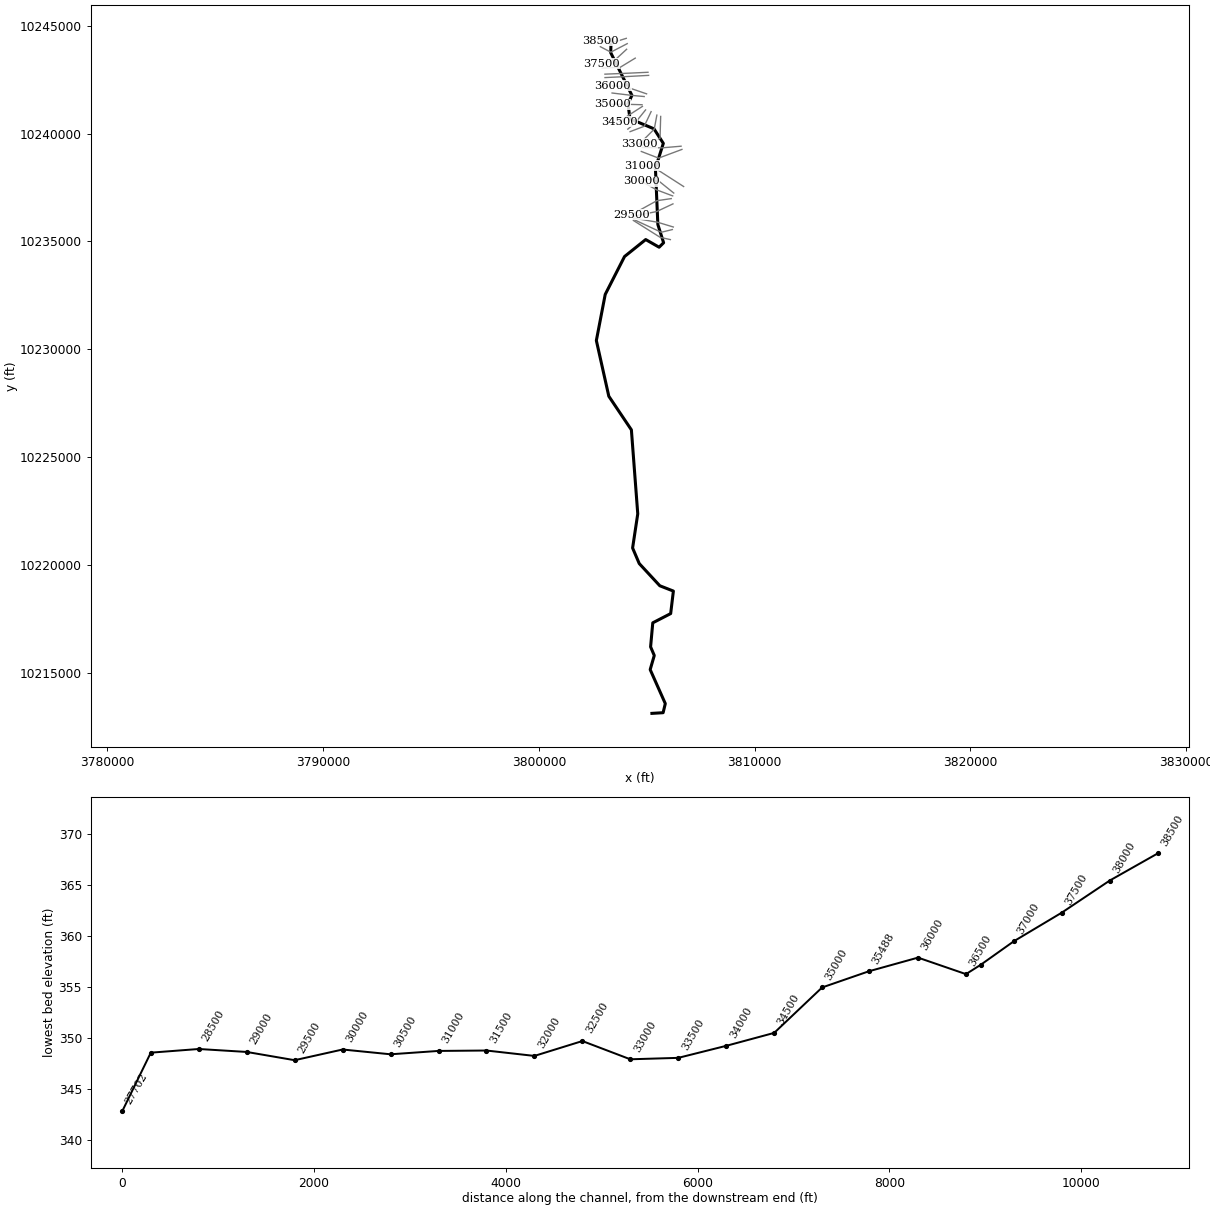
--- PRAIRIE BRANCH.prj (project) ---

Proj Title=PRAIRIE BRANCH Base Level Engineering
Current Plan=p01
Default Exp/Contr=0.3,0.1
English Units
Geom File=g01
Flow File=f01
Plan File=p01
Y Axis Title=Elevation
X Axis Title(PF)=Main Channel Distance
X Axis Title(XS)=Station
BEGIN DESCRIPTION:
PRAIRIE BRANCH
END DESCRIPTION:
DSS File=dss
DSS Export Rating Curves= 0
DSS Export Rating Curve Sorted= 0
DSS Export Volume Flow Curves= 0
DXF OffsetX= 0
DXF OffsetY= 0
DXF ScaleX= 1
DXF ScaleY= 10

--- PRAIRIE BRANCH.p01 (plan) ---

Plan Title=Multiple Run
Program Version=4.10
Short Identifier=Multiple Run
Geom File=g01
Flow File=f01
Subcritical Flow
K Sum by GR= 0
Std Step Tol= 0.01
Critical Tol= 0.01
Num of Std Step Trials= 20
Max Error Tol= 0.3
Flow Tol Ratio= 0.001
Split Flow NTrial= 30
Split Flow Tol= 0.02
Split Flow Ratio= 0.02
Log Output Level= 0
Friction Slope Method= 1
Unsteady Friction Slope Method= 2
Unsteady Bridges Friction Slope Method= 1
Parabolic Critical Depth
Global Vel Dist= 1 , 1 , 1
Global Log Level= 0
CheckData=True
Encroach Param=-1 ,0,0, 0
BEGIN DESCRIPTION:
Multiple Run
END DESCRIPTION:
Computation Interval=1HOUR
Output Interval=1HOUR
Run HTab= 0
Run UNet= 0
Run PostProcess= 0
Run WQNet= 0
UNET Theta= 1
UNET Theta Warmup= 1
UNET ZTol= 0.02
UNET ZSATol= 0.05
UNET MxIter= 20
UNET MaxInSteps= 0
UNET DtIC= 0
UNET DtMin= 0
UNET MaxCRTS= 20
UNET WFStab= 2
UNET SFStab= 1
UNET WFX= 1
UNET SFX= 1
UNET DSS MLevel= 4
UNET DZMax Abort= 100
UNET Convert EG Bridges= 0
UNET Use Existing IB Tables=-1
UNET Froude Reduction=False
UNET Froude Limit= 1
UNET Froude Power= 10
UNET Time Slicing=0,0, 5
UNET Junction Losses=0
Instantaneous Interval=1HOUR
DSS File=dss
Write IC File= 0
Write IC File at Sim End=0
Echo Input=False
Echo Parameters=False
Echo Output=False
Write Detailed= 0
WQ AD Non Conservative
WQ ULTIMATE=-1
WQ Max Comp Step=1HOUR
WQ Output Interval=15MIN
WQ Output Selected Increments= 0
WQ Output face flow=0
WQ Output face velocity=0
WQ Output face area=0
WQ Output face dispersion=0
WQ Output cell volume=0
WQ Output cell surface area=0
WQ Output cell continuity=0
WQ Output cumulative cell continuity=0
WQ Output face conc=0
WQ Output face dconc_dx=0
WQ Output face courant=0
WQ Output face peclet=0
WQ Output face adv mass=0
WQ Output face disp mass=0
WQ Output cell mass=0
WQ Output cell source sink temp=0
WQ Output cell source sink nsm=0
WQ Output MaxMinRange=-1
WQ Daily Max Min Mean=-1
WQ Daily Range=0
WQ Daily Time=0
WQ Create Restart=0
WQ Fixed Restart=0
WQ System Summary=0
WQ Use Fixed Temperature=0
Sorting and Armoring Iterations= 10
XS Update Threshold= 0.02
Hydraulics Update Threshold= 0.02
Energy Slope Method= 1
Volume Change Method= 0
XS Weighting Method= 0
Number of US Weighted Cross Sections= 1
Number of DS Weighted Cross Sections= 1
Upstream XS Weight=0.25
Main XS Weight=0.5
Downstream XS Weight=0.25
Number of DS XS's Weighted with US Boundary= 1
Upstream Boundary Weight= 1
Weight of XSs Associated with US Boundary= 0
Number of US XS's Weighted with DS Boundary= 1
Downstream Boundary Weight= 0.5
Weight of XSs Associated with DS Boundary= 0.5
Sediment Output Level= 4
Mass or Volume Output= 0
Output Increment Type= 1
Profile and TS Output Increment= 10
XS Output Flag= 0
XS Output Increment= 10
Disregard all LS=0
Disregard all Conn=0
Disregard all Breaches=0
Disregard all Pumps=0

--- PRAIRIE BRANCH.f01 (steady flow) ---

Flow Title=Multiple
Program Version=4.10
Number of Profiles= 7
Profile Names=10-year,25-year,50-year,1pct_min,100-year,1pct_plu,500-year
River Rch & RM=PRAIRIE BRANCH,Reach-1         ,38500
     901    1256    1732     786    2375    7172    4616
River Rch & RM=PRAIRIE BRANCH,Reach-1         ,38000
    1050    1460    2010     909    2746    8293    5299
River Rch & RM=PRAIRIE BRANCH,Reach-1         ,32000
    1337    1877    2599    1182    3569   10778    6957
River Rch & RM=PRAIRIE BRANCH,Reach-1         ,30500
    1526    2140    2960    1342    4053   12240    7866
River Rch & RM=PRAIRIE BRANCH,Reach-1         ,25000
    1934    2756    3854    1766    5333   16105   10571
River Rch & RM=PRAIRIE BRANCH,Reach-1         ,23000
    2234    3188    4460    2043    6171   18636   12227
River Rch & RM=PRAIRIE BRANCH,Reach-1         ,19500
    2421    3474    4881    2245    6781   20478   13542
River Rch & RM=PRAIRIE BRANCH,Reach-1         ,16500
    3072    4427    6236    2874    8679   26210   17393
River Rch & RM=PRAIRIE BRANCH,Reach-1         ,9695
    3139    4525    6376    2937    8871   26790   17778
River Rch & RM=PRAIRIE BRANCH,Reach-1         ,7475
    4556    6663    9478    4406   13307   40186   27140
Boundary for River Rch & Prof#=PRAIRIE BRANCH,Reach-1         , 1
Up Type= 0
Dn Type= 3
Dn Slope=0.002
Boundary for River Rch & Prof#=PRAIRIE BRANCH,Reach-1         , 2
Up Type= 0
Dn Type= 3
Dn Slope=0.002
Boundary for River Rch & Prof#=PRAIRIE BRANCH,Reach-1         , 3
Up Type= 0
Dn Type= 3
Dn Slope=0.002
Boundary for River Rch & Prof#=PRAIRIE BRANCH,Reach-1         , 4
Up Type= 0
Dn Type= 3
Dn Slope=0.002
Boundary for River Rch & Prof#=PRAIRIE BRANCH,Reach-1         , 5
Up Type= 0
Dn Type= 3
Dn Slope=0.002
Boundary for River Rch & Prof#=PRAIRIE BRANCH,Reach-1         , 6
Up Type= 0
Dn Type= 3
Dn Slope=0.002
Boundary for River Rch & Prof#=PRAIRIE BRANCH,Reach-1         , 7
Up Type= 0
Dn Type= 3
Dn Slope=0.002
DSS Import GetInterval= 0
DSS Import GetPeak= 0
DSS Import FillOption= 0

--- PRAIRIE BRANCH.g01 (geometry) ---

Geom Title=Existing Conditions
Program Version=4.10

River Reach=PRAIRIE BRANCH  ,Reach-1
Reach XY= 30
      3803348.23     10244366.84      3803329.49     10243748.39
       3804313.5     10241768.67      3804128.58     10241389.64
      3804220.89     10240686.05      3805335.35     10240219.94
      3805767.34     10239545.49      3805402.09     10238391.17
      3805514.59      10235782.8      3805781.22      10234939.1
      3805572.69     10234732.09      3804951.02     10235087.21
      3803969.84     10234299.92      3803074.63     10232544.29
      3802663.62     10230406.93      3803241.55     10227823.48
      3804287.78     10226266.77      3804582.76     10222373.82
      3804343.78     10220790.15      3804651.82     10220068.97
       3805605.5     10219039.52      3806234.06     10218793.89
      3806108.37      10217750.3      3805278.89     10217321.73
       3805177.9     10216208.68      3805348.39     10215808.17
      3805158.63     10215153.79      3805859.74     10213577.77
      3805758.28     10213155.95      3805239.08     10213124.76

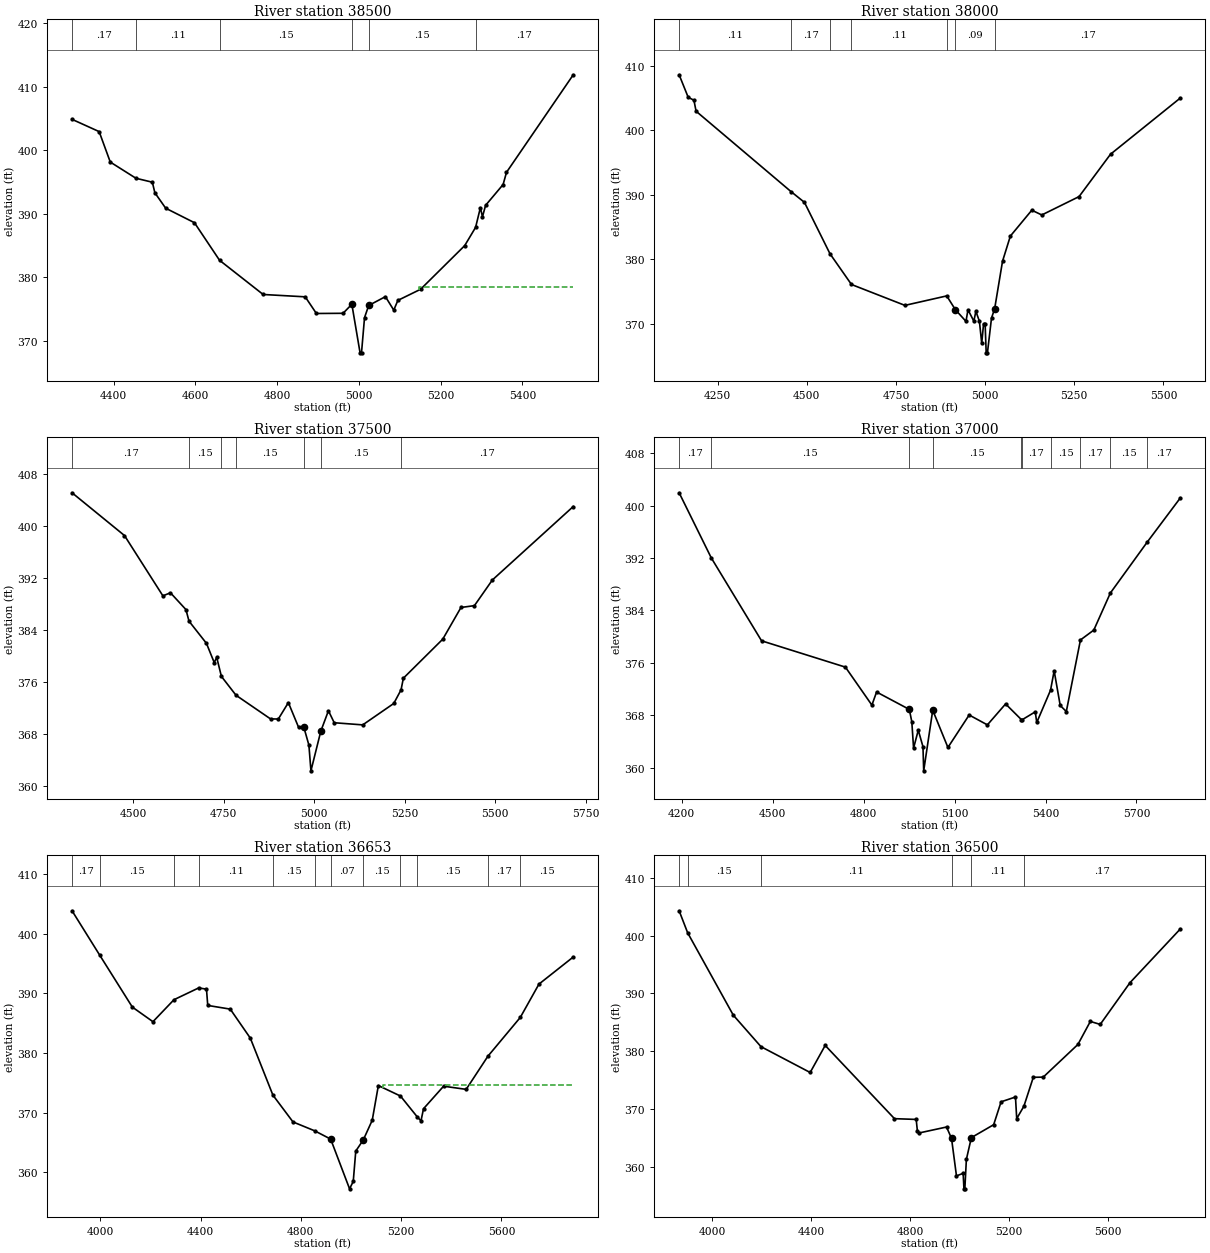
Type RM Length L Ch R = 1 ,38500   ,500,500,500
BEGIN DESCRIPTION:
PRAIRIE BRANCH 77.0
END DESCRIPTION:
XS GIS Cut Line= 3
      3804051.18     10244414.14      3803381.39     10244205.96
      3802867.83     10244311.08
#Sta/Elev= 30
  4298.6  404.86  4364.9  402.93  4392.1  398.14  4454.9  395.59    4495  394.97
  4501.1  393.31  4527.6  390.88  4597.9   388.6  4659.3  382.69  4765.9  377.31
  4868.8  376.94  4896.1  374.32  4961.3  374.35  4982.8  375.77  5002.9  368.13
  5006.4  368.13  5013.8  373.67    5024  375.58  5064.9  376.97  5085.3  374.85
  5095.3  376.38  5150.9  378.13  5258.8     385  5285.4  387.87  5297.1  390.97
  5302.2  389.53  5309.8  391.33  5352.7  394.61  5360.9  396.52  5524.2  411.87
#Mann= 6 ,-1 , 0
  4298.6     .17       0  4454.9     .11       0  4659.3     .15       0
  4982.8     .09       0    5024     .15       0  5285.4     .17       0
#XS Ineff= 2 , 0
       0                  5145.8       0   378.5
Permanent Ineff=
       F       F
Bank Sta=4982.8,5024
XS Rating Curve= 0 ,0
Exp/Cntr=0.3,0.1

Type RM Length L Ch R = 1 ,38000   ,500,500,500
BEGIN DESCRIPTION:
PRAIRIE BRANCH 76.0
END DESCRIPTION:
XS GIS Cut Line= 3
       3804094.7     10244168.13      3803333.68     10243772.11
      3802849.37     10244027.24
#Sta/Elev= 30
  4142.1  408.59  4167.5   405.1  4183.6  404.64  4189.6  402.94  4455.9  390.47
  4493.4  388.81    4565  380.84  4625.3  376.07  4775.1  372.83  4892.4   374.3
  4916.4  372.18  4946.3  370.35    4952  372.15  4968.4  370.38  4974.1  371.92
    4984  370.36  4990.5  366.94  4995.7  369.99    5000  369.99    5003  365.47
  5006.5  365.47  5017.9  370.85  5026.8  372.33  5048.8  379.67  5070.8  383.58
  5130.9  387.59  5158.9  386.85  5263.4   389.7  5351.6  396.27  5547.4  404.99
#Mann= 7 ,-1 , 0
  4142.1     .11       0  4455.9     .17       0    4565     .15       0
  4625.3     .11       0  4892.4     .17       0  4916.4     .09       0
  5026.8     .17       0
Bank Sta=4916.4,5026.8
XS Rating Curve= 0 ,0
Exp/Cntr=0.3,0.1

Type RM Length L Ch R = 1 ,37500   ,500,500,500
BEGIN DESCRIPTION:
PRAIRIE BRANCH 75.0
END DESCRIPTION:
XS GIS Cut Line= 3
      3804066.55     10243906.79      3803575.28     10243453.41
      3802895.55     10243230.32
#Sta/Elev= 30
  4331.5  405.04  4476.3  398.47  4582.3  389.21  4603.3  389.67  4645.9   387.1
  4654.5  385.31  4702.6  381.91  4724.1  378.95  4730.9  379.76  4743.9  376.83
  4784.3  373.93  4879.5   370.3    4901  370.28  4928.8   372.8  4957.2  368.98
  4971.3  369.06  4985.5  366.27  4991.1  362.32  5018.3   368.4  5039.4  371.55
  5055.4  369.71  5134.1  369.38  5219.8  372.67  5239.9  374.76  5246.3  376.55
  5355.1  382.55  5405.4  387.42  5442.5   387.7    5492  391.64  5715.4  402.93
#Mann= 7 ,-1 , 0
  4331.5     .17       0  4654.5     .15       0  4743.9     .17       0
  4784.3     .15       0  4971.3     .09       0  5018.3     .15       0
  5239.9     .17       0
#XS Ineff= 2 , 0
       0  4928.8   372.8               0
Permanent Ineff=
       F       F
Bank Sta=4971.3,5018.3
XS Rating Curve= 0 ,0
Exp/Cntr=0.3,0.1

Type RM Length L Ch R = 1 ,37000   ,347,347,347
BEGIN DESCRIPTION:
PRAIRIE BRANCH 74.0
END DESCRIPTION:
XS GIS Cut Line= 3
      3804466.27      10243496.8      3803775.73      10243075.9
      3802932.15     10243030.49
#Sta/Elev= 30
  4191.3  401.98  4297.4  392.03  4463.2  379.37  4739.9  375.35  4827.2  369.55
  4842.7  371.55  4950.7  368.89  4958.9     367  4964.7  362.98  4980.2  365.72
  4995.7   363.2  4998.1  359.51  5027.9  368.77    5078  363.08  5148.1  368.04
  5208.2  366.53  5268.3  369.73  5320.2  367.34  5322.8  367.31  5366.1  368.52
  5371.1   366.9  5416.5  371.82  5428.5  374.78  5448.5  369.49  5468.6  368.57
  5515.2   379.5  5559.3  381.01  5613.9  386.67  5734.9  394.41  5844.8   401.2
#Mann= 10 ,-1 , 0
  4191.3     .17       0  4297.4     .15       0  4950.7     .09       0
  5027.9     .15       0  5320.2     .15       0  5322.8     .17       0
  5416.5     .15       0  5515.2     .17       0  5613.9     .15       0
  5734.9     .17       0
#XS Ineff= 3 ,-1
  5027.9  5268.3  368.77  5268.3  5428.5  369.73  5428.5  5498.6  374.78
Permanent Ineff=
       F       F       F
Bank Sta=4950.7,5027.9
XS Rating Curve= 0 ,0
Exp/Cntr=0.3,0.1

Type RM Length L Ch R = 1 ,36653   ,153,153,153
BEGIN DESCRIPTION:
Mapping XS fbee3031
END DESCRIPTION:
XS GIS Cut Line= 3
      3805058.14     10242840.83      3803948.67     10242789.58
      3803061.14     10242753.78
#Sta/Elev= 30
  3887.5  403.87    3998  396.41    4128   387.7  4210.2  385.25    4294  388.94
  4392.6  390.92  4423.7  390.71  4428.7  387.98  4518.5  387.36  4598.5  382.49
  4688.6  372.92  4768.7  368.42  4855.2  366.93  4918.9  365.54  4994.3  357.19
    5009  358.44    5019  363.53    5049   365.4  5084.7  368.71  5109.1  374.53
  5197.3  372.77  5265.2  369.22  5279.2  368.61  5289.2  370.64  5369.3  374.42
  5459.3  373.89  5546.1  379.46  5675.2  385.97  5749.6  391.56  5886.4  396.11
#Mann= 12 ,-1 , 0
  3887.5     .17       0    3998     .15       0    4294     .17       0
  4392.6     .11       0  4688.6     .15       0  4855.2     .11       0
  4918.9     .07       0    5049     .15       0  5197.3     .17       0
  5265.2     .15       0  5546.1     .17       0  5675.2     .15       0
#XS Ineff= 2 , 0
       0                  5129.1       0  374.63
Permanent Ineff=
       F       F
Bank Sta=4918.9,5049
XS Rating Curve= 0 ,0
Exp/Cntr=0.3,0.1

Type RM Length L Ch R = 1 ,36500   ,500,500,500
BEGIN DESCRIPTION:
PRAIRIE BRANCH 73.0
END DESCRIPTION:
XS GIS Cut Line= 3
      3805086.34     10242697.34      3803954.86     10242636.83
      3803064.65     10242594.84
#Sta/Elev= 30
  3866.9  404.27  3901.4  400.46  4085.7  386.25  4197.4  380.82  4396.1  376.36
  4456.8  381.03  4736.6  368.39  4824.3  368.26  4829.3  366.21  4836.8  365.93
  4946.9  366.95    4967  364.99    4987  358.51    5014  358.96  5017.2  356.28
  5020.8  356.28    5027  361.36  5047.1  365.12  5137.2  367.35  5167.2   371.3
  5225.3  372.13  5230.3   368.4  5259.3  370.54  5297.3  375.53  5337.4  375.56
  5477.5   381.2  5527.6  385.17  5567.6  384.66  5687.8  391.86  5891.2  401.14
#Mann= 6 ,-1 , 0
  3866.9     .17       0  3901.4     .15       0  4197.4     .11       0
    4967     .07       0  5047.1     .11       0  5259.3     .17       0
Bank Sta=4967,5047.1
XS Rating Curve= 0 ,0
Exp/Cntr=0.3,0.1

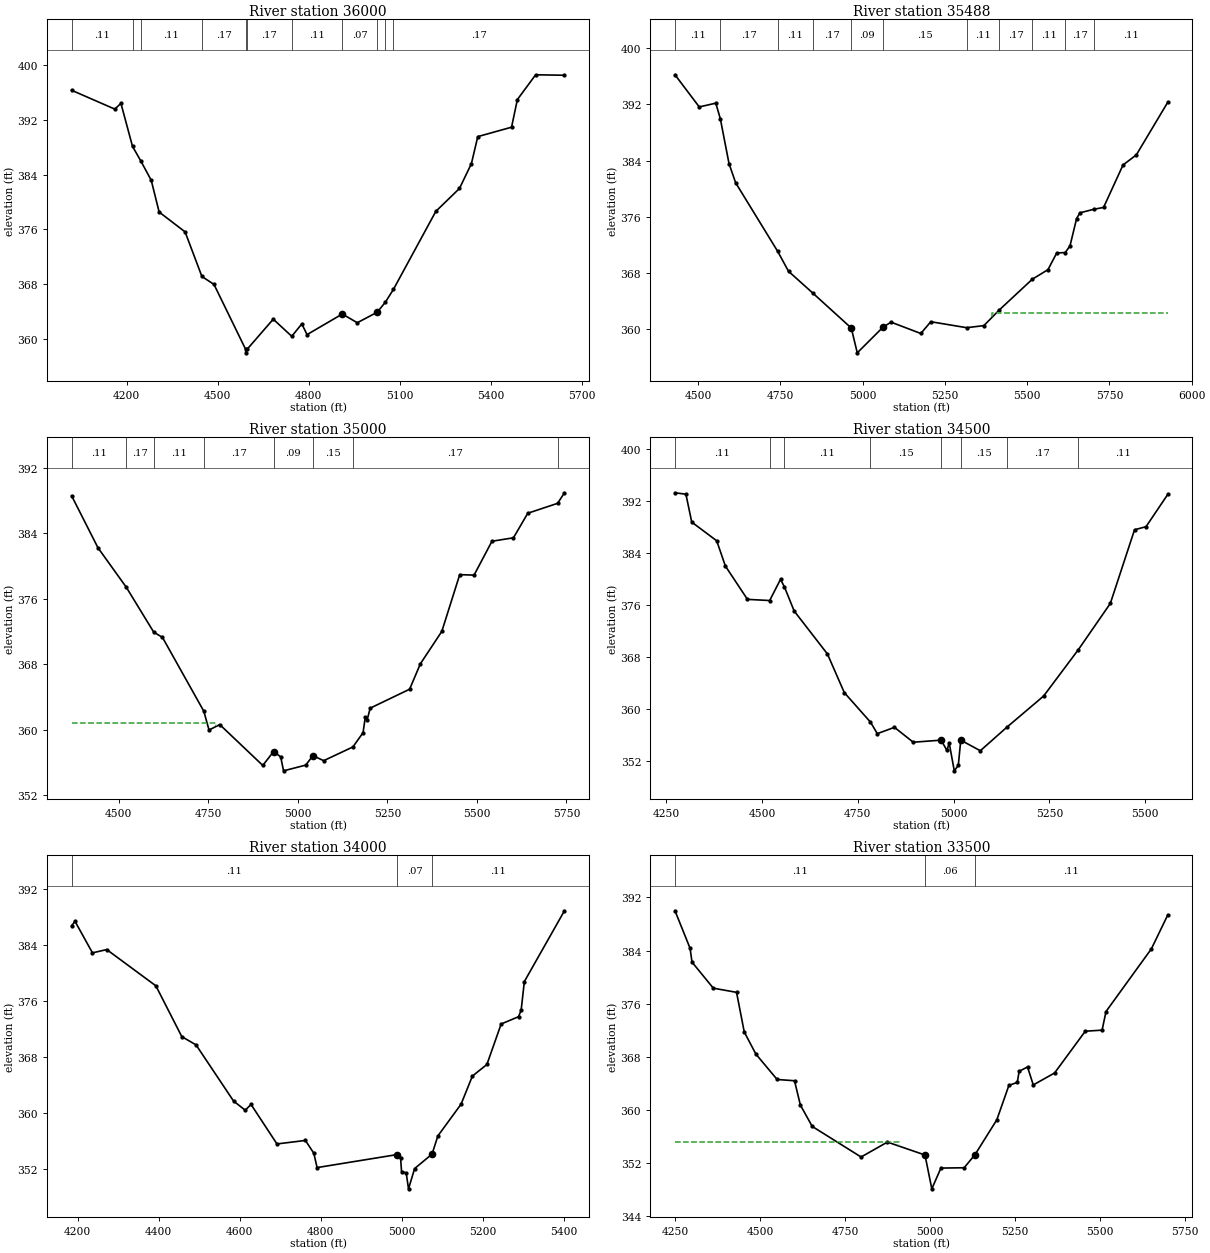
Type RM Length L Ch R = 1 ,36000   ,512,512,512
BEGIN DESCRIPTION:
PRAIRIE BRANCH 72.0
END DESCRIPTION:
XS GIS Cut Line= 3
      3804991.53     10241841.51       3804063.2     10242158.65
       3803423.4     10242210.48
#Sta/Elev= 30
    4019  396.37  4161.2  393.61  4181.4  394.45  4219.5  388.15    4246  386.08
  4281.2  383.18  4307.2  378.53  4392.7  375.62    4448  369.09  4487.9  367.92
  4592.2   358.4  4592.5   357.9  4596.5   358.4    4683  362.83    4744  360.32
    4777  362.14  4794.3  360.57  4910.5  363.59  4959.6  362.31  5025.4  363.85
  5052.3  365.33  5078.9  367.21  5218.4  378.63  5296.3  381.99  5335.5  385.62
  5356.5  389.58  5467.7  390.96  5486.9  395.01  5547.1  398.64  5641.9  398.57
#Mann= 11 ,-1 , 0
    4019     .11       0  4219.5     .17       0    4246     .11       0
    4448     .17       0  4592.2     .11       0  4596.5     .17       0
    4744     .11       0  4910.5     .07       0  5025.4     .15       0
  5052.3     .15       0  5078.9     .17       0
Bank Sta=4910.5,5025.4
XS Rating Curve= 0 ,0
Exp/Cntr=0.3,0.1

Type RM Length L Ch R = 1 ,35488   ,488,488,488
BEGIN DESCRIPTION:
PRAIRIE BRANCH 71.0
END DESCRIPTION:
XS GIS Cut Line= 3
      3804881.36     10241715.95       3804313.5     10241768.67
       3803392.7     10241879.93
#Sta/Elev= 30
  4429.7  396.24  4503.5  391.65  4553.7  392.19  4567.5  389.97  4593.9  383.57
    4614  380.83  4741.7  371.05  4774.7   368.2  4848.5  365.09  4965.5   360.1
  4983.7  356.56  5061.4   360.2  5086.3  360.94  5176.9  359.32  5207.1     361
  5315.9  360.15  5368.3  360.44  5415.8   362.7  5515.8  367.07  5563.3  368.43
  5589.9  370.81  5615.7  370.87  5630.2  371.82  5650.3  375.72  5660.4  376.54
  5702.9  377.05  5732.3  377.31  5791.4  383.37  5831.7   384.8  5927.5  392.33
#Mann= 11 ,-1 , 0
  4429.7     .11       0  4567.5     .17       0  4741.7     .11       0
  4848.5     .17       0  4965.5     .09       0  5061.4     .15       0
  5315.9     .11       0  5415.8     .17       0  5515.8     .11       0
  5615.7     .17       0  5702.9     .11       0
#XS Ineff= 2 , 0
       0                  5394.3       0  362.24
Permanent Ineff=
       F       F
Bank Sta=4965.5,5061.4
XS Rating Curve= 0 ,0
Exp/Cntr=0.3,0.1

Type RM Length L Ch R = 1 ,35000   ,500,500,500
BEGIN DESCRIPTION:
PRAIRIE BRANCH 70.0
END DESCRIPTION:
XS GIS Cut Line= 3
       3804781.4     10241336.71      3804150.06      10241354.8
      3803405.48     10241359.77
#Sta/Elev= 30
  4368.4  388.57    4442  382.22  4521.2  377.39  4597.6  371.92  4622.1  371.27
  4737.6  362.25  4752.1  359.96  4782.1  360.62  4902.2  355.63  4932.2  357.32
  4952.2  356.68  4960.2  354.97  5022.2  355.67  5042.2  356.83  5072.2  356.21
  5153.9  357.89  5182.2  359.63  5188.5  361.53  5193.5  361.17  5202.2  362.63
  5312.2  364.94  5342.2  368.04  5402.2  372.01  5452.2  378.94  5492.2  378.88
  5542.2  383.02  5602.2  383.44  5642.2  386.44  5725.5  387.65  5744.6  388.94
#Mann= 8 ,-1 , 0
  4368.4     .11       0  4521.2     .17       0  4597.6     .11       0
  4737.6     .17       0  4932.2     .09       0  5042.2     .15       0
  5153.9     .17       0  5725.5     .11       0
#XS Ineff= 2 , 0
       0  4772.1  360.82               0
Permanent Ineff=
       F       F
Bank Sta=4932.2,5042.2
XS Rating Curve= 0 ,0
Exp/Cntr=0.3,0.1

Type RM Length L Ch R = 1 ,34500   ,500,500,500
BEGIN DESCRIPTION:
PRAIRIE BRANCH 69.0
END DESCRIPTION:
XS GIS Cut Line= 3
      3804799.37     10241259.83      3804188.14     10240866.78
      3803723.85     10240555.64
#Sta/Elev= 30
  4273.3  393.27  4301.8  393.05    4317  388.76  4382.1  385.89  4404.8     382
  4462.3  376.88  4520.3   376.7  4548.6  379.96  4558.9  378.78  4584.2  375.09
    4671  368.48    4715  362.54  4783.3     358  4801.1  356.23  4845.8   357.2
  4894.8  354.91  4967.5  355.23  4982.7  353.65  4988.6   354.8  5001.9  350.51
  5012.4  351.36  5018.8  355.23  5069.8   353.6  5138.3  357.18  5234.9  362.01
  5325.5  369.14    5409  376.26  5472.1  387.58  5502.1  388.06  5558.9  393.03
#Mann= 8 ,-1 , 0
  4273.3     .11       0  4520.3     .17       0  4558.9     .11       0
  4783.3     .15       0  4967.5     .07       0  5018.8     .15       0
  5138.3     .17       0  5325.5     .11       0
Bank Sta=4967.5,5018.8
XS Rating Curve= 0 ,0
Exp/Cntr=0.3,0.1

Type RM Length L Ch R = 1 ,34000   ,500,500,500
BEGIN DESCRIPTION:
PRAIRIE BRANCH 68.0
END DESCRIPTION:
XS GIS Cut Line= 3
      3804945.43     10241095.84      3804432.35     10240462.36
      3804122.74     10240206.11
#Sta/Elev= 30
  4184.8  386.74  4193.1  387.38  4236.3  382.88  4271.5  383.35  4392.9  378.18
  4456.9  370.94  4492.1  369.76  4584.8  361.75  4613.5  360.45  4627.9  361.27
  4691.9  355.64  4762.2  356.14    4783  354.31    4791  352.27  4989.3  354.13
  4997.2  353.68  4999.6   351.7  5011.1  351.51  5016.8  349.24  5031.9  352.13
  5074.9  354.19  5089.3  356.78  5146.6  361.31  5174.6  365.32  5210.4  366.97
  5245.6  372.74  5288.6  373.78    5295  374.72  5302.9  378.79  5401.9  388.88
#Mann= 3 , 0 , 0
  4184.8     .11       0  4989.3     .07       0  5074.9     .11       0
#XS Ineff= 2 , 0
       0  4762.2  356.14               0
Permanent Ineff=
       F       F
Bank Sta=4989.3,5074.9
XS Rating Curve= 0 ,0
Exp/Cntr=0.3,0.1

Type RM Length L Ch R = 1 ,33500   ,500,500,500
BEGIN DESCRIPTION:
PRAIRIE BRANCH 67.0
END DESCRIPTION:
XS GIS Cut Line= 3
      3805201.66     10241016.39      3804882.02     10240338.02
      3804227.98     10240088.84
#Sta/Elev= 30
  4250.1  389.99  4294.5  384.33  4300.2  382.25  4362.8  378.32  4431.2  377.69
  4453.9  371.71  4488.1  368.38  4550.6  364.55  4601.7  364.36    4619  360.69
  4653.9  357.47  4797.6  352.86    4875  355.11  4985.6  353.16  5005.6  348.06
  5032.4  351.19  5100.8  351.24  5132.9  353.23  5196.9  358.47  5232.4  363.66
  5257.1  364.11  5262.5  365.78  5287.2  366.44  5304.1  363.73  5366.8  365.53
  5457.1  371.83  5506.6  371.99  5518.1   374.8  5651.7  384.26  5699.9  389.37
#Mann= 3 , 0 , 0
  4250.1     .11       0  4985.6     .06       0  5132.9     .11       0
#XS Ineff= 2 , 0
       0    4909  355.12               0
Permanent Ineff=
       F       F
Bank Sta=4985.6,5132.9
XS Rating Curve= 0 ,0
Exp/Cntr=0.3,0.1

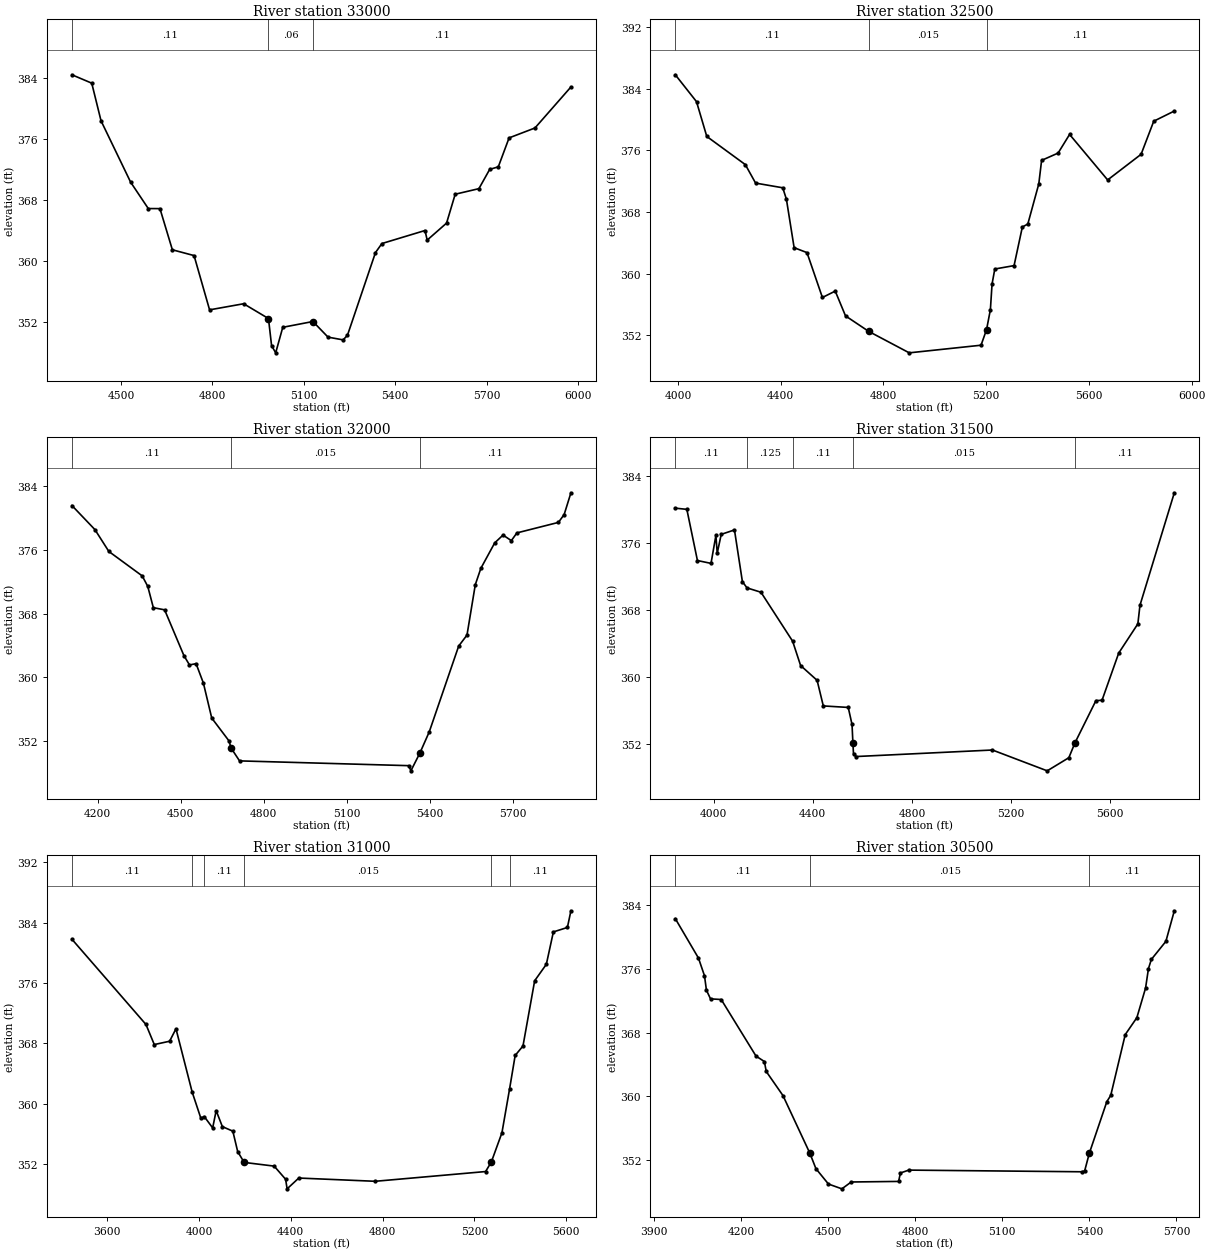
Type RM Length L Ch R = 1 ,33000   ,500,500,500
BEGIN DESCRIPTION:
PRAIRIE BRANCH 66.0
END DESCRIPTION:
XS GIS Cut Line= 3
      3805468.17     10240855.01      3805347.29     10240205.26
      3804656.51     10239515.48
#Sta/Elev= 30
  4339.1   384.4  4404.1   383.3  4434.6  378.36  4531.7  370.31  4589.6  366.85
  4627.9  366.84  4668.6  361.44  4739.8  360.68  4790.7  353.56  4902.5  354.36
  4983.9  352.42  4994.1  348.87  5007.6  347.92  5030.8  351.27  5129.8  352.03
  5179.3  349.98  5228.8  349.62    5243  350.22  5334.9  361.07  5356.1  362.26
  5497.5  363.97  5504.6  362.71  5568.2  364.94  5596.5  368.73  5674.3  369.46
  5709.7  371.99  5737.9  372.32  5773.3  376.12  5858.2  377.42  5976.2   382.8
#Mann= 3 , 0 , 0
  4339.1     .11       0  4983.9     .06       0  5129.8     .11       0
#XS Ineff= 2 , 0
       0  4902.5  354.36               0
Permanent Ineff=
       F       F
Bank Sta=4983.9,5129.8
XS Rating Curve= 0 ,0
Exp/Cntr=0.3,0.1

Type RM Length L Ch R = 1 ,32500   ,500,500,500
BEGIN DESCRIPTION:
PRAIRIE BRANCH 65.0
END DESCRIPTION:
XS GIS Cut Line= 3
      3805644.97     10240793.52      3805615.74     10239783.44
      3804745.57     10239448.24
#Sta/Elev= 30
  3989.5  385.83    4072  382.34    4112  377.82  4262.1  374.16  4302.1  371.76
  4407.8  371.15  4422.1  369.66  4452.1  363.37  4502.2  362.73  4562.2   356.9
  4612.2  357.73  4652.2  354.51  4742.3   352.5  4900.3  349.71  5179.9   350.7
  5201.4  352.73  5216.3  355.31  5222.8  358.65  5233.5   360.6  5308.5  361.04
  5340.7  366.05  5362.1  366.45  5404.8  371.66  5415.7  374.71    5480  375.66
  5524.7  378.08  5672.9  372.17  5803.1   375.5  5852.4   379.8  5932.5  381.12
#Mann= 3 , 0 , 0
  3989.5     .11       0  4742.3    .015       0  5201.4     .11       0
Bank Sta=4742.3,5201.4
XS Rating Curve= 0 ,0
Exp/Cntr=0.3,0.1

Type RM Length L Ch R = 1 ,32000   ,500,500,500
BEGIN DESCRIPTION:
PRAIRIE BRANCH 64.0
END DESCRIPTION:
XS GIS Cut Line= 3
      3806590.69     10239414.34      3805701.27     10239337.89
      3804792.77     10239356.66
#Sta/Elev= 30
  4107.3  381.57  4190.4  378.54  4240.6   375.8  4361.1  372.73  4381.1  371.41
  4401.2  368.74  4441.9  368.47  4511.6  362.72  4531.7  361.55  4555.5  361.71
  4581.9  359.27    4612  354.88  4674.1  352.02  4682.3  351.09  4712.4   349.5
  5323.5   348.9  5330.9  348.25  5363.5  350.49  5397.3  353.15  5503.5  363.92
  5533.5   365.3  5563.5  371.63  5583.5  373.68  5633.6  376.88  5663.6  377.86
  5693.6  377.16  5713.6  378.13  5863.6  379.45  5884.3  380.44  5908.7  383.17
#Mann= 3 , 0 , 0
  4107.3     .11       0  4682.3    .015       0  5363.5     .11       0
Bank Sta=4682.3,5363.5
XS Rating Curve= 0 ,0
Exp/Cntr=0.3,0.1

Type RM Length L Ch R = 1 ,31500   ,500,500,500
BEGIN DESCRIPTION:
PRAIRIE BRANCH 63.0
END DESCRIPTION:
XS GIS Cut Line= 3
      3806631.39     10239265.08      3805549.64     10238861.43
      3804748.55     10239170.09
#Sta/Elev= 30
  3845.4  380.18  3891.9  380.04  3934.6  373.92  3989.4  373.58  4009.1  376.92
  4014.4  374.79  4030.6  377.05    4084  377.58    4116   371.4  4134.6  370.65
  4190.9  370.13  4318.6  364.28  4350.8  361.37  4417.4   359.6  4442.4  356.54
    4543  356.36  4558.3  354.32 4561.75  352.15  4564.3  350.76    4575  350.49
  5124.7  351.27  5345.7  348.78    5433  350.35  5457.7  352.13  5542.2  357.17
  5566.9  357.22  5634.2  362.86  5711.4  366.35  5719.9  368.57  5858.5  382.02
#Mann= 5 ,-1 , 0
  3845.4     .11       0  4134.6    .125       0  4318.6     .11       0
 4561.75    .015       0  5457.7     .11       0
Bank Sta=4561.75,5457.7
XS Rating Curve= 0 ,0
Exp/Cntr=0.3,0.1

Type RM Length L Ch R = 1 ,31000   ,500,500,500
BEGIN DESCRIPTION:
PRAIRIE BRANCH 62.0
END DESCRIPTION:
XS GIS Cut Line= 3
      3806709.35     10237545.14       3805402.3     10238384.23
      3804792.73     10238501.77
#Sta/Elev= 30
  3446.8   381.8  3769.4  370.51  3805.6  367.85  3872.3  368.29  3900.1  369.94
  3970.6  361.56  4008.4   358.1  4023.4  358.31    4060  356.81  4075.2   359.1
  4102.2  356.98  4147.8  356.38    4169  353.67  4197.2  352.24  4327.9  351.75
  4377.7  350.01  4384.3  348.74  4435.2  350.17  4768.2  349.74    5249  351.03
  5274.1   352.3  5320.2  356.16  5353.5  361.97  5377.9  366.41  5411.9  367.66
  5462.8   376.3  5513.7  378.48  5544.3  382.77  5605.4  383.36  5620.8  385.57
#Mann= 6 ,-1 , 0
  3446.8     .11       0  3970.6    .125       0  4023.4     .11       0
  4197.2    .015       0  5274.1     .12       0  5353.5     .11       0
Bank Sta=4197.2,5274.1
XS Rating Curve= 0 ,0
Exp/Cntr=0.3,0.1

Type RM Length L Ch R = 1 ,30500   ,500,500,500
BEGIN DESCRIPTION:
PRAIRIE BRANCH 61.0
END DESCRIPTION:
XS GIS Cut Line= 3
      3806251.38     10237243.21      3805451.31     10237886.64
      3804758.79     10237870.79
#Sta/Elev= 30
  3973.3   382.3    4053  377.36  4073.8  375.14  4080.5  373.33  4094.6  372.24
  4131.4  372.16  4251.4  365.06  4280.2  364.38  4286.6  363.13  4344.2  360.11
    4437  352.87  4457.8  350.94    4501  349.01  4547.2  348.41  4579.4  349.27
  4742.6  349.34    4749   350.4  4777.8  350.76  5373.6  350.55  5383.6  350.64
 5399.79  352.87  5460.2  359.35  5473.6  360.13  5523.6  367.76  5563.6  369.88
  5593.6  373.59  5603.6  376.04  5613.6  377.19  5663.6  379.45  5692.7  383.29
#Mann= 3 ,-1 , 0
  3973.3     .11       0    4437    .015       0 5399.79     .11       0
Bank Sta=4437,5399.79
XS Rating Curve= 0 ,0
Exp/Cntr=0.3,0.1

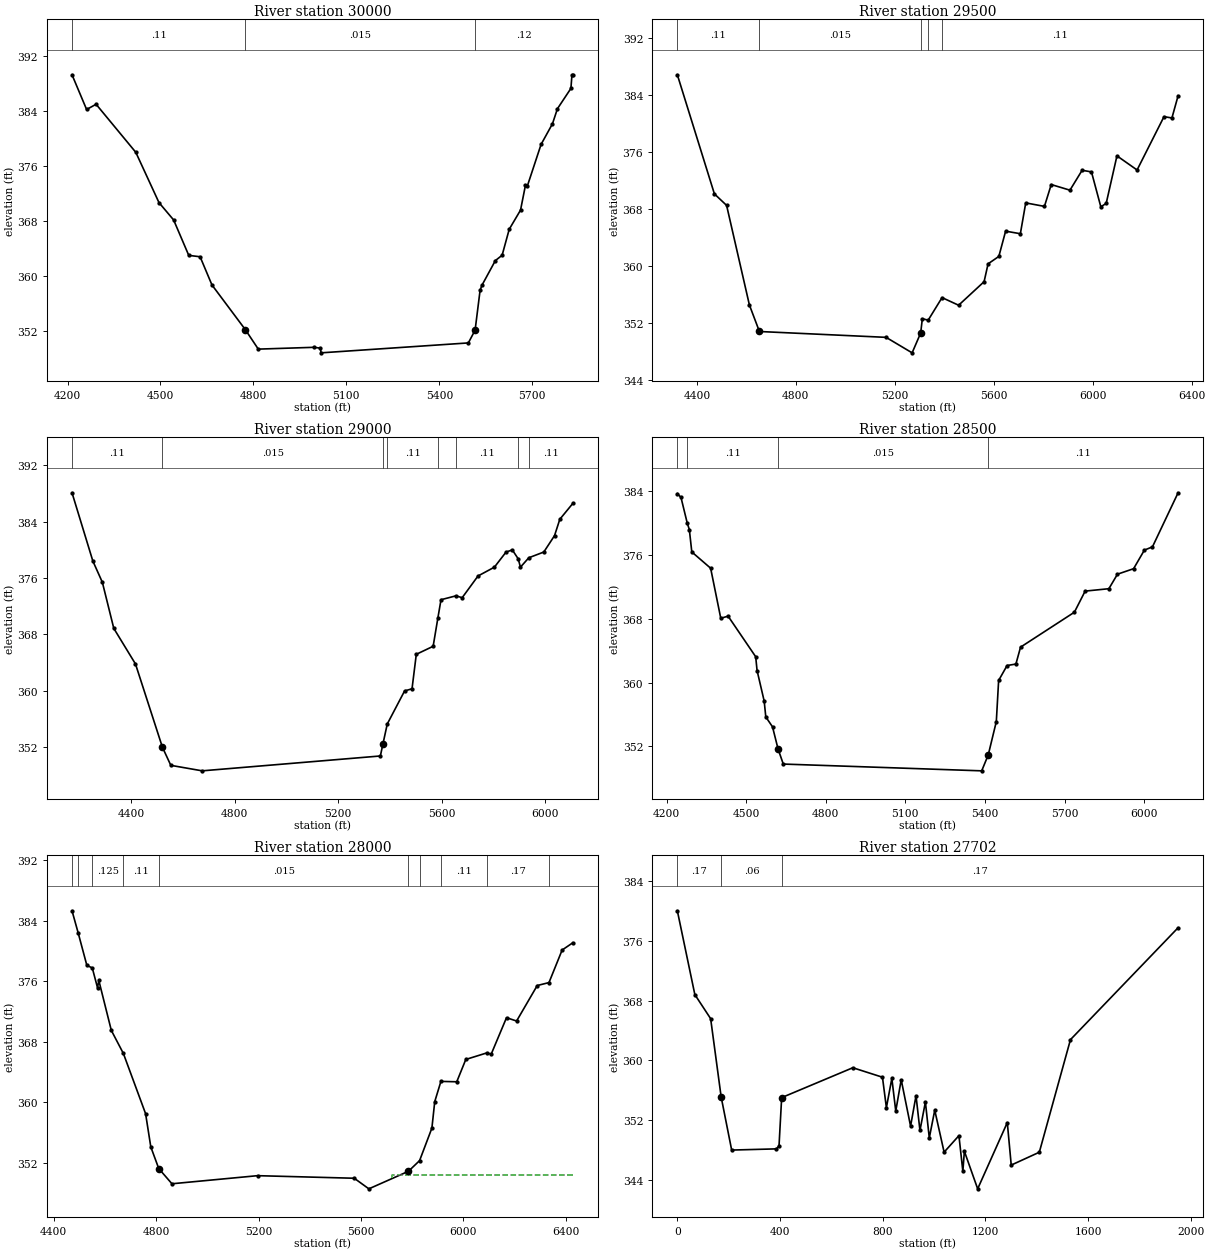
Type RM Length L Ch R = 1 ,30000   ,500,500,500
BEGIN DESCRIPTION:
PRAIRIE BRANCH 60.0
END DESCRIPTION:
XS GIS Cut Line= 3
      3806200.55     10237110.88      3805465.31     10237387.36
      3804738.37     10237789.38
#Sta/Elev= 30
  4214.5  389.25  4261.6  384.21  4292.2  384.97  4420.4  377.99  4495.2  370.69
  4542.5  368.17  4591.3  363.03  4627.9  362.83  4666.1  358.74  4773.7  352.26
  4815.7  349.42  4994.1  349.68  5016.1  349.57  5018.3  348.88  5493.7  350.32
  5515.5  352.18  5531.5  357.94  5537.2  358.66  5580.8  362.27  5602.7  363.05
  5625.6  366.82  5662.1   369.6  5678.1  373.23  5683.8  373.06  5728.4  379.14
  5765.2  382.14  5781.2  384.32  5824.7  387.27  5828.1  389.24  5830.7  389.24
#Mann= 3 ,-1 , 0
  4214.5     .11       0  4773.7    .015       0  5515.5     .12       0
Bank Sta=4773.7,5515.5
XS Rating Curve= 0 ,0
Exp/Cntr=0.3,0.1

Type RM Length L Ch R = 1 ,29500   ,500,500,500
BEGIN DESCRIPTION:
PRAIRIE BRANCH 59.0
END DESCRIPTION:
XS GIS Cut Line= 3
      3806136.11     10236985.37      3805464.32     10236887.36
      3804287.63     10236235.88
#Sta/Elev= 30
  4321.1  386.79  4470.9   370.1  4520.2  368.49  4612.4  354.53  4652.8  350.82
  5164.8     350    5270  347.83  5304.6  350.61  5311.3  352.61  5334.9  352.41
    5391  355.57  5457.9   354.5  5560.9   357.8    5577   360.3  5620.5  361.34
  5647.9  364.88  5707.5  364.52  5729.2  368.84  5804.8  368.35  5832.3  371.41
  5907.9  370.62  5957.1  373.41  5994.9  373.18  6032.7  368.29  6054.4  368.77
  6097.9  375.43  6179.2  373.45    6288  380.92  6320.1  380.74    6345  383.85
#Mann= 5 ,-1 , 0
  4321.1     .11       0  4652.8    .015       0  5304.6    .125       0
  5334.9    .125       0    5391     .11       0
Bank Sta=4652.8,5304.6
XS Rating Curve= 0 ,0
Exp/Cntr=0.3,0.1

Type RM Length L Ch R = 1 ,29000   ,500,500,500
BEGIN DESCRIPTION:
PRAIRIE BRANCH 58.0
END DESCRIPTION:
XS GIS Cut Line= 3
      3806214.07      10236741.1      3805463.33     10236387.36
      3804378.81      10236164.4
#Sta/Elev= 30
  4170.1  388.11  4250.6  378.43  4287.5   375.4  4331.7  368.86  4415.6  363.81
  4519.7     352  4552.3  349.42  4673.6  348.64  5362.9  350.75  5372.5   352.4
  5389.6  355.29  5456.6  359.98  5485.4  360.29  5501.9  365.18  5567.1  366.32
  5585.3  370.32  5597.5  372.93  5655.2  373.48  5679.4  373.22  5740.7   376.3
    5804  377.55  5849.2   379.7  5873.4     380  5896.2  378.73  5904.7  377.55
  5937.3  378.89  5995.2   379.7  6036.7  382.03  6057.1  384.35  6107.2  386.59
#Mann= 8 ,-1 , 0
  4170.1     .11       0  4519.7    .015       0  5372.5    .125       0
  5389.6     .11       0  5585.3    .125       0  5655.2     .11       0
  5896.2    .125       0  5937.3     .11       0
Bank Sta=4519.7,5372.5
XS Rating Curve= 0 ,0
Exp/Cntr=0.3,0.1

Type RM Length L Ch R = 1 ,28500   ,500,500,500
BEGIN DESCRIPTION:
PRAIRIE BRANCH 57.0
END DESCRIPTION:
XS GIS Cut Line= 3
       3806231.1     10235669.09      3805504.44     10235889.32
      3804392.59     10236079.55
#Sta/Elev= 30
  4240.7   383.7  4254.5  383.21    4278     380  4285.9  379.19  4295.2  376.38
  4366.2  374.34  4404.4  368.06    4432  368.33    4536  363.24  4541.2  361.51
    4568  357.68  4574.1  355.69  4599.4  354.45  4620.3  351.67    4640  349.78
  5387.8  348.93  5412.5  350.93  5442.9  355.11  5451.6  360.26  5483.5  362.14
  5516.7  362.32  5534.2  364.44  5737.1  368.82  5777.7  371.47  5867.1  371.77
  5899.5  373.59  5960.3  374.28  6000.9  376.61  6031.4  377.02    6128   383.8
#Mann= 4 ,-1 , 0
  4240.7    .125       0    4278     .11       0  4620.3    .015       0
  5412.5     .11       0
Bank Sta=4620.3,5412.5
XS Rating Curve= 0 ,0
Exp/Cntr=0.3,0.1

Type RM Length L Ch R = 1 ,28000   ,298,298,298
BEGIN DESCRIPTION:
PRAIRIE BRANCH 56.0
END DESCRIPTION:
XS GIS Cut Line= 3
      3806186.98     10235550.38      3805673.62     10235424.77
      3804378.81     10236025.31
#Sta/Elev= 30
  4471.5  385.32  4495.2  382.44  4529.5   378.1  4550.6  377.77  4571.1  375.15
  4576.2  376.11    4625  369.51  4672.1  366.46  4758.9   358.5  4779.2  354.11
  4810.3  351.25  4861.8  349.24  5196.3  350.31  5573.8  349.97  5630.9  348.57
  5785.5  350.89    5829   352.3  5877.1   356.6  5888.2   360.1  5912.3  362.77
  5974.2  362.72  6009.5  365.67    6092  366.54  6108.7  366.37  6168.5  371.19
  6207.9  370.75  6288.5  375.44  6334.4  375.83  6385.7  380.13  6427.3  381.09
#Mann= 10 ,-1 , 0
  4471.5    .125       0  4495.2     .11       0  4550.6    .125       0
  4672.1     .11       0  4810.3    .015       0  5785.5     .15       0
    5829     .17       0  5912.3     .11       0    6092     .17       0
  6334.4     .11       0
#XS Ineff= 2 , 0
       0                  5722.9       0  350.45
Permanent Ineff=
       F       F
Bank Sta=4810.3,5785.5
XS Rating Curve= 0 ,0
Exp/Cntr=0.3,0.1

Type RM Length L Ch R = 1 ,27702   ,202,202,202
XS GIS Cut Line= 3
      3806094.46     10235085.16      3805621.03     10235190.37
       3804379.6      10235972.4
#Sta/Elev= 30
       0  380.04    68.2  368.82   129.7   365.6   170.7  355.11   211.6  348.01
   385.8  348.17     396  348.56   406.3  355.03   683.5  359.03   798.9  357.76
   814.2  353.69   835.4   357.6   850.7  353.24   871.9  357.42   908.4  351.21
   929.6  355.29   944.9  350.63   966.1  354.44   981.3  349.63  1002.5  353.35
    1039  347.73  1096.7  349.94    1112  345.17  1117.9  347.85  1169.7  342.82
  1285.1  351.69  1300.4     346  1409.8  347.72  1531.1  362.79  1950.3  377.77
#Mann= 3 , 0 , 0
       0     .17       0   170.7     .06       0   406.3     .17       0
#XS Ineff= 2 , 0
       0                   406.3       0  355.03
Permanent Ineff=
       F       T
Bank Sta=170.7,406.3
XS Rating Curve= 0 ,0
Exp/Cntr=0.3,0.1