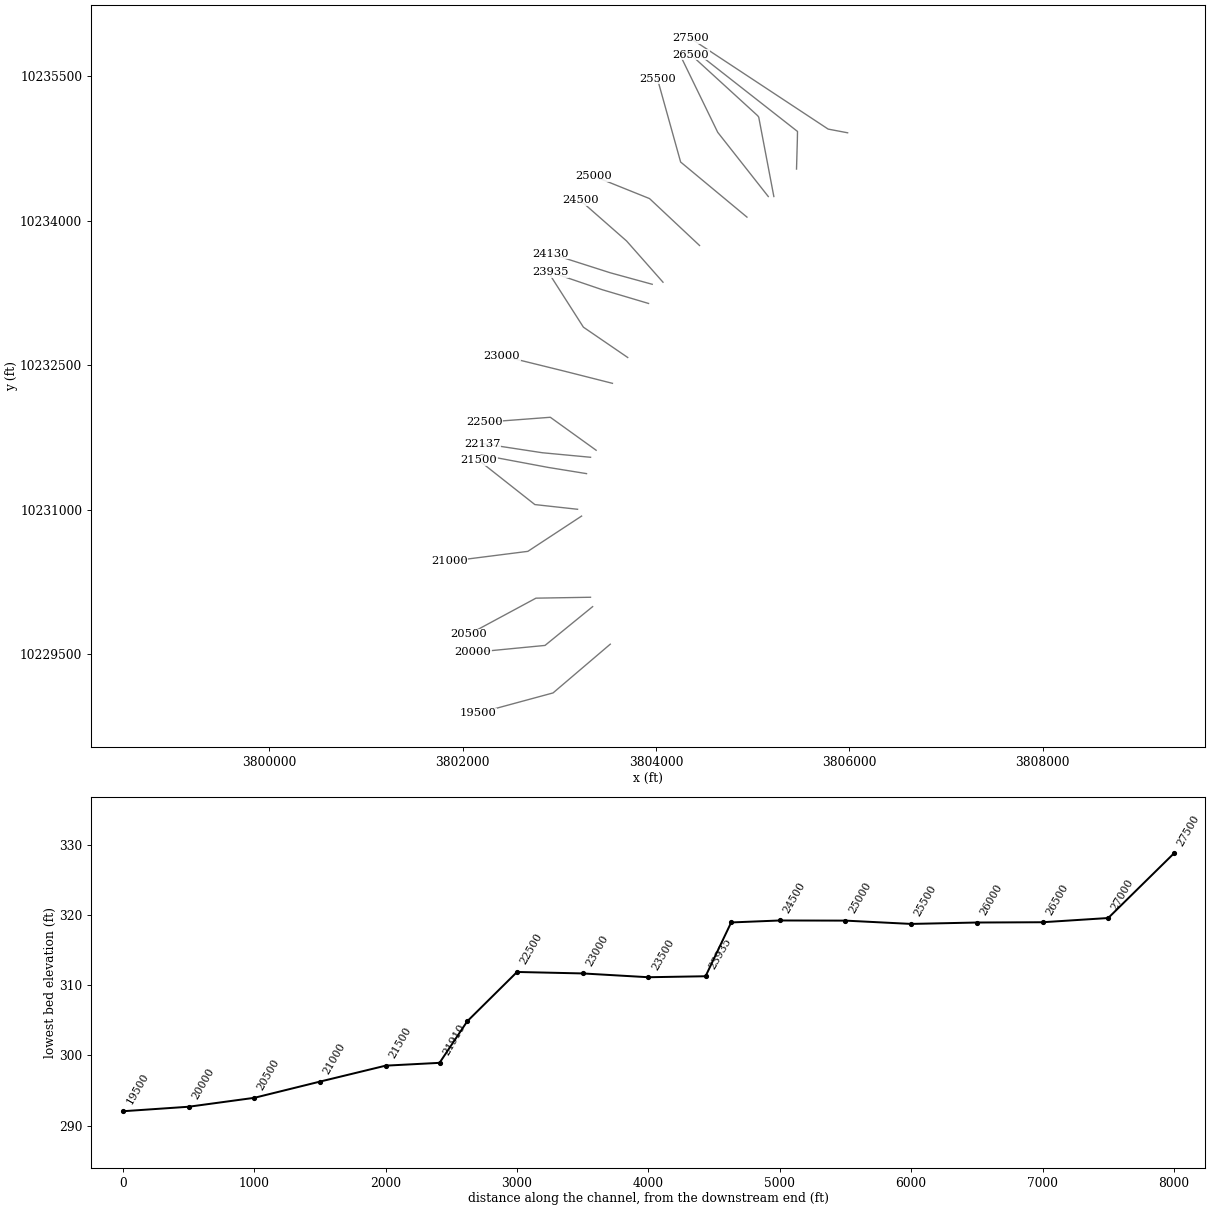
HEC-RAS study PRAIRIE BRANCH.prj: PRAIRIE BRANCH Base Level Engineering

--- PRAIRIE BRANCH.g01 (geometry) --- (continued)

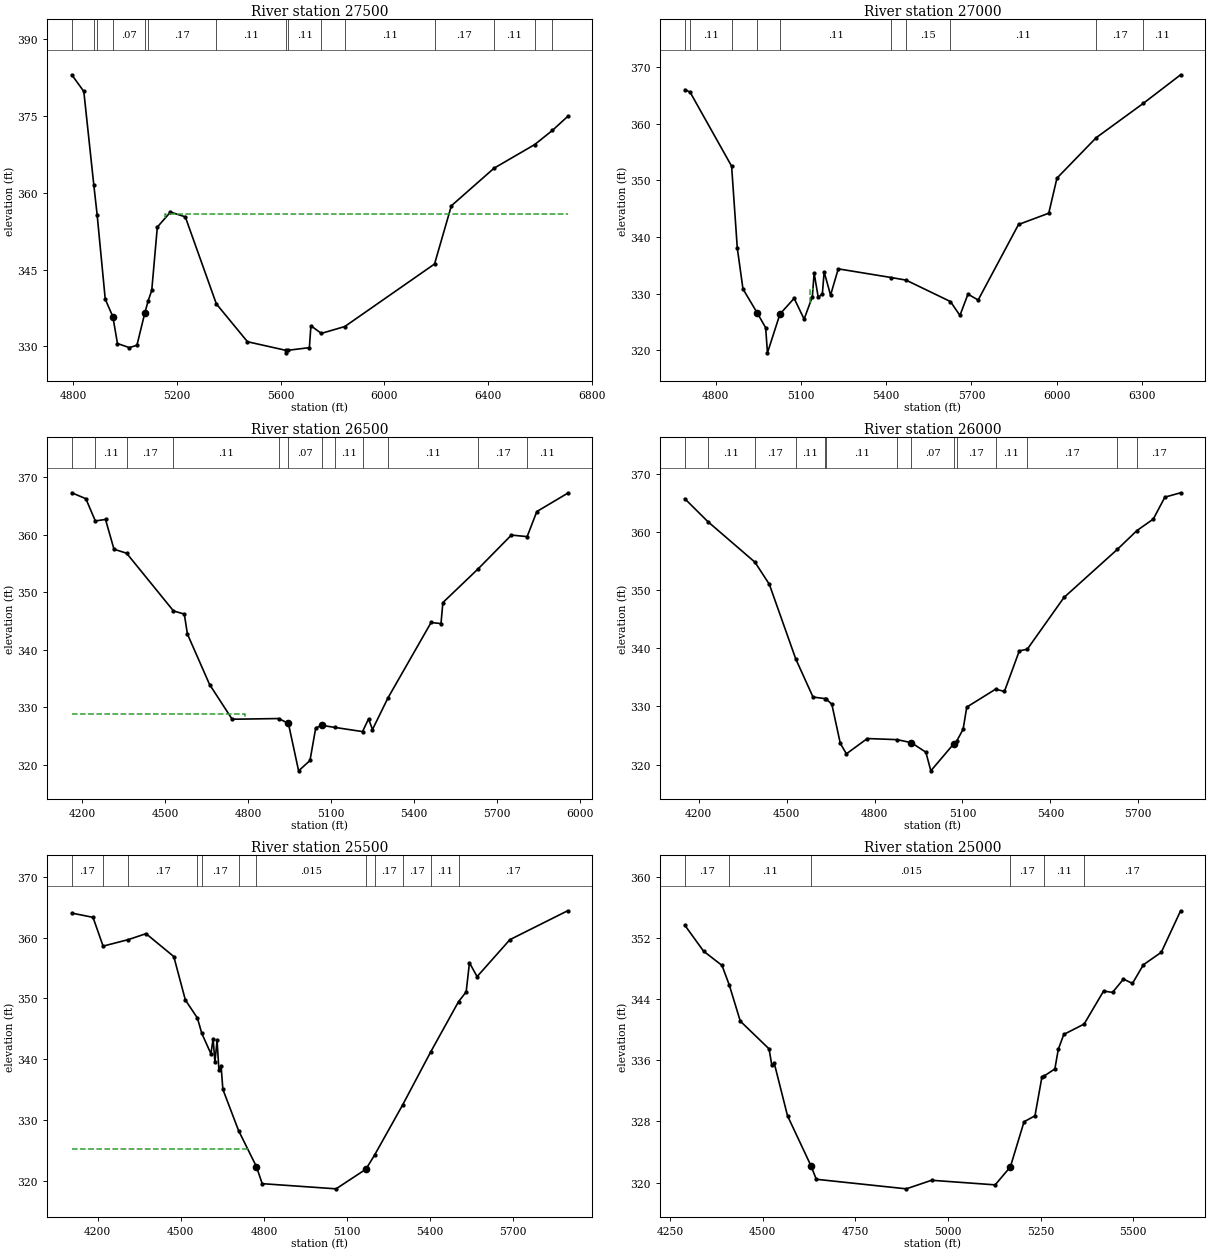
Type RM Length L Ch R = 1 ,27500   ,500,500,500
BEGIN DESCRIPTION:
PRAIRIE BRANCH 55.0
END DESCRIPTION:
XS GIS Cut Line= 3
       3805983.4      10234912.6      3805781.92     10234950.99
       3804358.4     10235893.03
#Sta/Elev= 30
  4794.9  383.09  4841.3  379.84    4880  361.49  4892.7  355.75    4924  339.23
  4953.2  335.84  4971.1  330.57  5016.9  329.77  5046.2  330.24  5076.3  336.49
  5089.7  338.95  5103.3  340.95  5124.8  353.33  5175.5  356.26  5232.7  355.32
  5352.4  338.32  5472.5  330.92  5619.6  329.25  5620.1  328.75  5628.1  329.25
  5711.1  329.76  5717.1  334.04  5757.3  332.55  5847.7  333.89  6193.8  346.11
  6258.7  357.49  6423.2  364.83    6580  369.45  6648.1  372.21    6707  374.94
#Mann= 15 ,-1 , 0
  4794.9     .11       0    4880     .17       0  4892.7     .11       0
  4953.2     .07       0  5076.3     .11       0  5089.7     .17       0
  5352.4     .11       0  5619.6     .11       0  5628.1     .11       0
  5757.3     .15       0  5847.7     .11       0  6193.8     .17       0
  6423.2     .11       0    6580     .17       0  6648.1     .11       0
#XS Ineff= 2 , 0
       0                  5154.5       0  355.98
Permanent Ineff=
       F       F
Bank Sta=4953.2,5076.3
XS Rating Curve= 0 ,0
Exp/Cntr=0.3,0.1

Type RM Length L Ch R = 1 ,27000   ,500,500,500
BEGIN DESCRIPTION:
PRAIRIE BRANCH 54.0
END DESCRIPTION:
XS GIS Cut Line= 4
      3805454.69     10234536.24       3805463.4     10234845.22
      3805464.85     10234926.46      3804399.18     10235764.07
#Sta/Elev= 30
  4690.9  365.98  4709.3  365.58  4855.8  352.49  4875.8  338.04  4895.8  330.82
  4945.8  326.61  4975.7  323.98    4982  319.55  5025.9  326.38  5075.9  329.17
  5111.1   325.5    5140  329.44  5146.4  333.61  5160.8  329.34  5175.3  329.95
  5181.6  333.84  5204.2  329.73  5231.3  334.37  5417.8  332.84  5470.1  332.38
  5626.3   328.6  5659.7  326.15    5688  329.91  5723.8  328.87    5866   342.2
  5972.4  344.19  6001.3  350.38  6139.5  357.52  6305.7  363.59  6436.7  368.62
#Mann= 10 ,-1 , 0
  4690.9     .17       0  4709.3     .11       0  4855.8     .17       0
  4945.8     .07       0  5025.9     .11       0  5417.8     .11       0
  5470.1     .15       0  5626.3     .11       0  6139.5     .17       0
  6305.7     .11       0
#XS Ineff= 2 ,-1
  5131.9  5146.4  330.82  5146.4  5794.4  333.61
Permanent Ineff=
       F       F
Bank Sta=4945.8,5025.9
XS Rating Curve= 0 ,0
Exp/Cntr=0.3,0.1

Type RM Length L Ch R = 1 ,26500   ,500,500,500
BEGIN DESCRIPTION:
PRAIRIE BRANCH 53.0
END DESCRIPTION:
XS GIS Cut Line= 4
      3805220.11     10234251.09      3805063.85     10235074.39
      3805052.44     10235090.27      3804362.31     10235722.95
#Sta/Elev= 30
    4162  367.34  4212.9  366.31  4247.2  362.44  4284.1   362.7  4314.7  357.52
  4360.4  356.82  4529.9  346.78  4569.1  346.23  4580.4  342.75  4660.7  333.96
  4742.2  327.93  4910.7  328.05  4945.7   327.2  4982.6  318.95  5023.8  320.75
  5044.5  326.41  5066.1  326.87  5113.3  326.51  5213.8  325.78  5235.7  327.99
  5249.9  326.14  5305.6  331.62    5462  344.77  5497.7  344.57  5504.5  348.23
  5632.5  354.12  5752.4  359.98  5809.4  359.71  5844.3  364.07  5955.8  367.26
#Mann= 12 ,-1 , 0
    4162     .17       0  4247.2     .11       0  4360.4     .17       0
  4529.9     .11       0  4910.7     .17       0  4945.7     .07       0
  5066.1     .11       0  5113.3     .11       0  5213.8     .17       0
  5305.6     .11       0  5632.5     .17       0  5809.4     .11       0
#XS Ineff= 2 , 0
       0  4789.4  328.87               0
Permanent Ineff=
       F       F
Bank Sta=4945.7,5066.1
XS Rating Curve= 0 ,0
Exp/Cntr=0.3,0.1

Type RM Length L Ch R = 1 ,26000   ,500,500,500
BEGIN DESCRIPTION:
PRAIRIE BRANCH 52.0
END DESCRIPTION:
XS GIS Cut Line= 3
      3805162.42      10234251.1       3804639.3     10234917.76
        3804271.     10235677.71
#Sta/Elev= 30
  4152.6  365.75  4231.3  361.81  4392.1  354.82    4441  351.03  4531.2  338.18
  4590.2  331.61  4631.7  331.34  4634.6  331.29  4654.4  330.37  4683.3  323.63
  4704.1  321.84  4775.4  324.47  4877.1  324.28  4925.5  323.76  4975.2  322.12
  4992.2  318.91  5070.4  323.56    5080  323.99  5102.3  326.07  5114.8  329.88
    5213  332.96  5243.3  332.58  5294.1  339.56  5321.2  339.84  5446.5  348.75
  5628.2  357.01  5695.5  360.27  5751.2  362.24  5790.8  366.02  5844.5  366.77
#Mann= 14 ,-1 , 0
  4152.6     .17       0  4231.3     .11       0  4392.1     .17       0
  4531.2     .11       0  4631.7     .15       0  4634.6     .11       0
  4877.1     .15       0  4925.5     .07       0  5070.4     .15       0
    5080     .17       0    5213     .11       0  5321.2     .17       0
  5628.2     .11       0  5695.5     .17       0
Bank Sta=4925.5,5070.4
XS Rating Curve= 0 ,0
Exp/Cntr=0.3,0.1

Type RM Length L Ch R = 1 ,25500   ,500,500,500
BEGIN DESCRIPTION:
PRAIRIE BRANCH 51.0
END DESCRIPTION:
XS GIS Cut Line= 3
      3804941.97     10234037.32       3804255.6     10234609.21
      3804015.81     10235472.32
#Sta/Elev= 30
  4106.6  364.02  4183.2  363.32  4219.7  358.59  4311.2  359.67  4374.5  360.64
  4474.7  356.88  4516.4  349.75    4560  346.77  4575.6  344.27  4608.8   340.9
  4616.6  343.36  4623.1  339.52  4630.9  343.09  4637.5  338.27  4645.3  338.96
  4651.8  335.06  4708.4  328.29  4772.8  322.37  4793.7  319.56  5060.3  318.71
    5168  321.94  5199.5  324.28  5300.4  332.49  5401.3  341.17  5502.2  349.47
  5529.7  351.07  5541.6  355.86  5569.1  353.58  5687.4  359.65  5895.8   364.4
#Mann= 12 ,-1 , 0
  4106.6     .17       0  4219.7     .11       0  4311.2     .17       0
    4560     .11       0  4575.6     .17       0  4708.4     .11       0
  4772.8    .015       0    5168     .11       0  5199.5     .17       0
  5300.4     .17       0  5401.3     .11       0  5502.2     .17       0
#XS Ineff= 2 , 0
       0  4744.2  325.33               0
Permanent Ineff=
       F       F
Bank Sta=4772.8,5168
XS Rating Curve= 0 ,0
Exp/Cntr=0.3,0.1

Type RM Length L Ch R = 1 ,25000   ,500,500,500
BEGIN DESCRIPTION:
PRAIRIE BRANCH 50.0
END DESCRIPTION:
XS GIS Cut Line= 3
      3804451.28     10233742.77      3803933.87     10234229.69
      3803351.75     10234464.52
#Sta/Elev= 30
  4289.5  353.66  4340.2  350.26    4390  348.39  4409.7  345.82  4439.3  341.11
    4517  337.48  4524.3  335.37  4531.2  335.57  4566.8  328.73  4630.3  322.17
  4644.4  320.43  4887.3  319.18  4955.6   320.3  5127.2   319.7  5168.2  322.05
  5205.1  327.95  5234.6  328.73  5253.4  333.81  5259.2  333.93  5288.3  334.86
  5297.6  337.43  5312.4  339.37  5367.3  340.73  5419.8  345.04    5444  344.87
  5473.5  346.61  5497.7  346.04  5527.2  348.48  5575.5  350.11  5627.7  355.54
#Mann= 6 ,-1 , 0
  4289.5     .17       0  4409.7     .11       0  4630.3    .015       0
  5168.2     .17       0  5259.2     .11       0  5367.3     .17       0
Bank Sta=4630.3,5168.2
XS Rating Curve= 0 ,0
Exp/Cntr=0.3,0.1

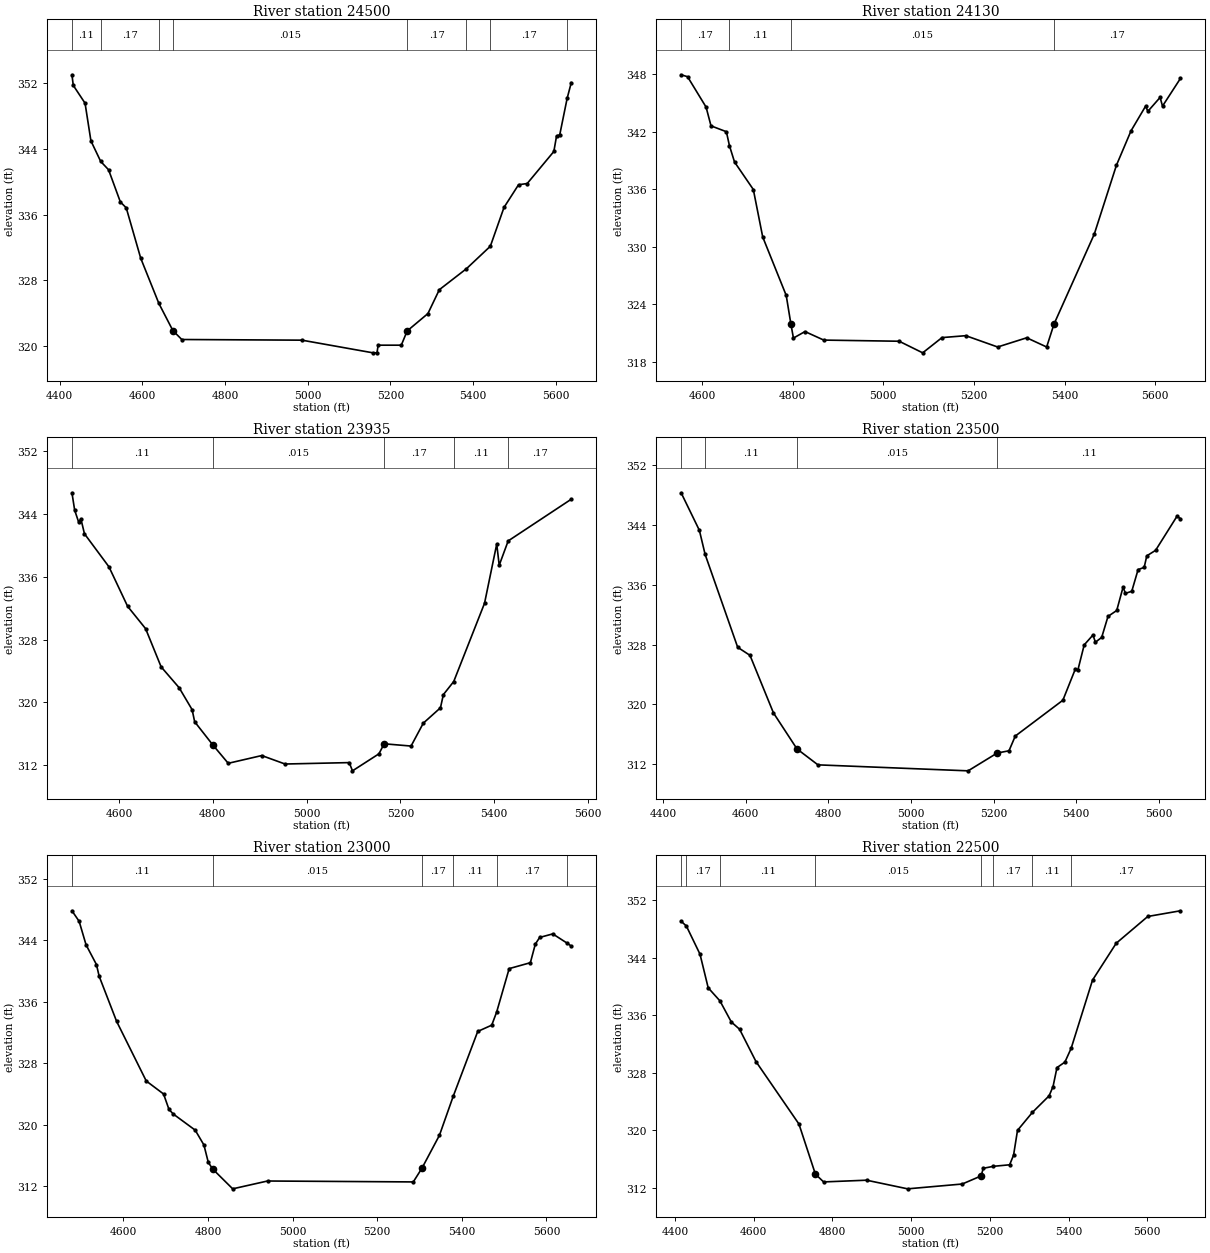
Type RM Length L Ch R = 1 ,24500   ,370,370,370
BEGIN DESCRIPTION:
PRAIRIE BRANCH 49.0
END DESCRIPTION:
XS GIS Cut Line= 3
      3804073.28     10233361.68      3803696.39      10233789.7
      3803217.87     10234211.06
#Sta/Elev= 30
  4429.7  352.98  4432.9  351.69  4461.4  349.53  4475.6  344.95  4499.3  342.45
  4518.3  341.44  4546.8  337.53    4561  336.82  4596.1  330.69  4639.9  325.21
  4673.9   321.9  4695.4  320.82    4986  320.74    5158   319.2  5167.6   319.2
  5170.4  320.13  5226.4  320.13  5240.6  321.86  5290.8  323.97  5318.4  326.87
    5384  329.42  5441.8  332.15  5474.9  336.87    5510  339.62    5531  339.77
  5595.4  343.66    5602  345.55  5609.6  345.67  5627.6  350.12  5637.6  352.03
#Mann= 8 ,-1 , 0
  4429.7     .11       0  4499.3     .17       0  4639.9     .11       0
  4673.9    .015       0  5240.6     .17       0    5384     .11       0
  5441.8     .17       0  5627.6     .11       0
Bank Sta=4673.9,5240.6
XS Rating Curve= 0 ,0
Exp/Cntr=0.3,0.1

Type RM Length L Ch R = 1 ,24130   ,195,195,195
BEGIN DESCRIPTION:
Mapping XS 02c46687
END DESCRIPTION:
XS GIS Cut Line= 3
      3803961.51     10233340.22      3803527.24     10233459.65
      3802906.66     10233658.67
#Sta/Elev= 30
  4553.6  347.93  4567.8  347.73  4608.7  344.56  4619.6   342.6  4653.5  341.99
  4660.3  340.53  4671.5  338.83    4713  335.96  4733.7  331.01  4785.6  324.91
  4795.9  321.93  4801.5  320.46    4827  321.14  4868.5  320.25  5034.9  320.13
  5086.8  318.92  5129.4  320.51  5181.9  320.71  5252.2  319.53  5316.4  320.49
  5360.4  319.53 5376.54  321.91  5465.4  331.29  5514.4  338.49  5546.6  342.08
  5578.7  344.65  5583.9  344.12  5610.8  345.57  5616.1  344.66  5655.7  347.55
#Mann= 4 ,-1 , 0
  4553.6     .17       0  4660.3     .11       0  4795.9    .015       0
 5376.54     .17       0
Bank Sta=4795.9,5376.54
XS Rating Curve= 0 ,0
Exp/Cntr=0.3,0.1

Type RM Length L Ch R = 1 ,23935   ,435,435,435
BEGIN DESCRIPTION:
PRAIRIE BRANCH 48.0
END DESCRIPTION:
XS GIS Cut Line= 3
      3803923.45     10233141.22        3803444.     10233284.15
      3802909.65     10233466.48
#Sta/Elev= 30
  4499.7  346.72  4505.5   344.5  4513.7  343.03  4518.9  343.36  4526.4  341.49
  4578.6  337.28  4618.4  332.24  4656.8  329.39  4689.9  324.52  4728.3  321.86
    4756  319.06  4761.4  317.52  4799.8  314.59    4833  312.22  4904.5  313.21
  4954.2  312.13    5091  312.31    5098  311.26  5154.4  313.43  5165.5  314.71
  5222.9  314.42    5249  317.34  5285.6   319.3  5291.8  320.98  5313.9  322.65
  5379.6  332.63  5405.6  340.18  5410.9  337.48    5430  340.58  5564.6   345.9
#Mann= 5 ,-1 , 0
  4499.7     .11       0  4799.8    .015       0  5165.5     .17       0
  5313.9     .11       0    5430     .17       0
Bank Sta=4799.8,5165.5
XS Rating Curve= 0 ,0
Exp/Cntr=0.3,0.1

Type RM Length L Ch R = 1 ,23500   ,500,500,500
BEGIN DESCRIPTION:
PRAIRIE BRANCH 47.0
END DESCRIPTION:
XS GIS Cut Line= 3
       3803708.2      10232580.3      3803249.72       10232895.
      3802899.43     10233445.15
#Sta/Elev= 30
  4443.9   348.3  4488.1  343.28    4502  340.06  4580.8  327.64  4610.6  326.56
  4667.4  318.86  4724.3  314.05    4775  311.92  5138.4  311.12  5208.7   313.5
  5237.3   313.8  5252.5  315.77  5367.7  320.56  5398.1  324.77  5404.1  324.62
  5419.3  327.96  5440.5  329.28  5446.4  328.32  5461.6  328.96  5476.9  331.77
    5498  332.56  5513.3  335.67  5519.2  334.85  5534.4  335.13  5549.7  338.03
  5564.4  338.32  5570.8  339.87    5592   340.6  5643.6  345.14  5652.2  344.85
#Mann= 4 ,-1 , 0
  4443.9     .17       0    4502     .11       0  4724.3    .015       0
  5208.7     .11       0
Bank Sta=4724.3,5208.7
XS Rating Curve= 0 ,0
Exp/Cntr=0.3,0.1

Type RM Length L Ch R = 1 ,23000   ,500,500,500
BEGIN DESCRIPTION:
PRAIRIE BRANCH 46.0
END DESCRIPTION:
XS GIS Cut Line= 3
      3803550.18     10232312.11      3803044.92     10232440.45
      3802405.32     10232598.33
#Sta/Elev= 30
  4478.7  347.86  4495.7  346.49  4512.1  343.42  4536.6  340.86    4543  339.34
  4584.3  333.46  4654.3   325.7  4695.2  324.01  4708.1  321.99  4718.4  321.39
    4770   319.3  4790.6  317.37  4800.9  315.11  4811.3  314.24  4858.6  311.66
  4940.9  312.68  5285.4  312.56    5306  314.36  5347.2  318.63  5379.7   323.7
  5437.7  332.15  5470.8  332.97  5482.4  334.67    5512  340.33  5562.1   341.1
  5573.8  343.52  5584.1  344.39    5615  344.85  5649.4  343.63  5658.8  343.26
#Mann= 6 ,-1 , 0
  4478.7     .11       0  4811.3    .015       0    5306     .17       0
  5379.7     .11       0  5482.4     .17       0  5649.4     .11       0
Bank Sta=4811.3,5306
XS Rating Curve= 0 ,0
Exp/Cntr=0.3,0.1

Type RM Length L Ch R = 1 ,22500   ,379,379,379
BEGIN DESCRIPTION:
PRAIRIE BRANCH 45.0
END DESCRIPTION:
XS GIS Cut Line= 3
      3803381.28     10231617.68      3802907.43     10231959.72
      3802225.08     10231908.17
#Sta/Elev= 30
  4415.6  349.04    4429  348.37  4463.6  344.46  4484.4  339.79  4514.2  337.98
  4543.2  335.04  4564.1  334.04  4605.9  329.54    4715  320.87  4756.8  313.91
  4777.7  312.83  4886.8  313.07  4991.1  311.87  5129.9  312.54  5178.1  313.67
  5183.1  314.72  5209.3     315  5250.3  315.21  5260.3  316.55  5270.3  319.99
    5308  322.48  5350.6  324.79  5360.6  326.08  5370.6  328.71  5390.7  329.47
  5406.7   331.4  5460.9  340.86  5521.1  345.98  5601.3   349.7  5684.3  350.49
#Mann= 8 ,-1 , 0
  4415.6     .11       0    4429     .17       0  4514.2     .11       0
  4756.8    .015       0  5178.1     .17       0  5209.3     .17       0
    5308     .11       0  5406.7     .17       0
Bank Sta=4756.8,5178.1
XS Rating Curve= 0 ,0
Exp/Cntr=0.3,0.1

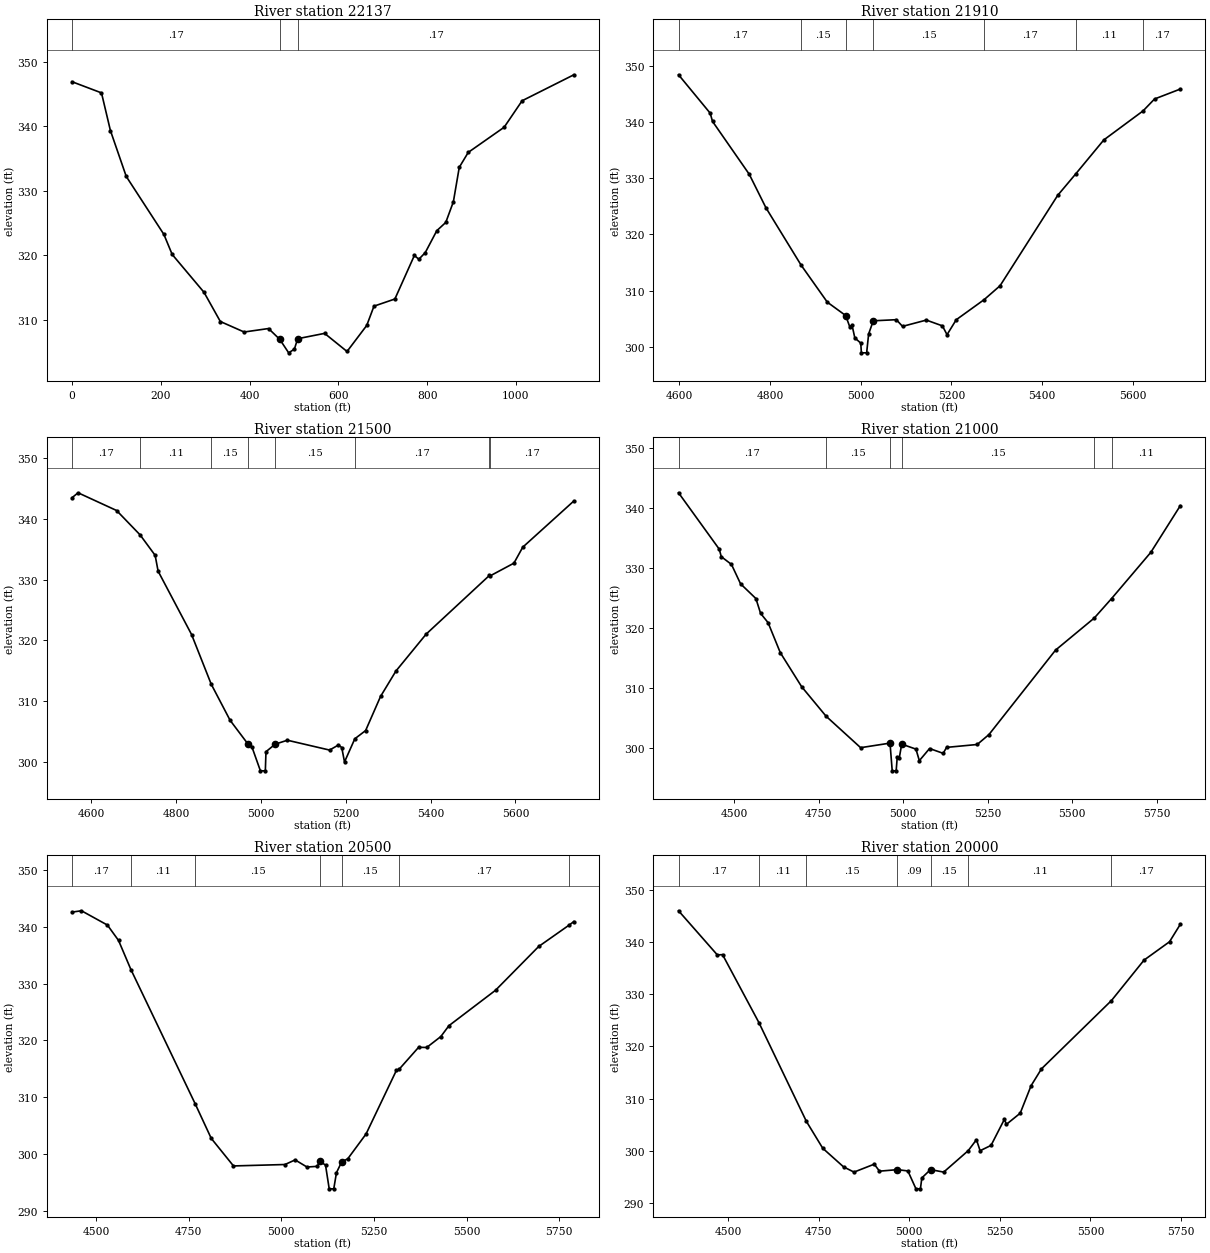
Type RM Length L Ch R = 1 ,22137   ,211,211,211
XS GIS Cut Line= 3
      3803323.83     10231544.56      3802825.01     10231591.58
       3802202.3     10231686.92
#Sta/Elev= 30
       0   346.9    66.3  345.17    86.4  339.33   122.1  332.21   206.9  323.22
   225.6  320.11   297.3  314.24   334.1  309.71   387.7  308.08   442.7  308.62
     468  306.94   488.1  304.85     501  305.43   508.3  307.04     569  307.87
   619.6  305.06     664   309.1   680.3  312.09   727.4   313.2   771.3  319.95
   781.4  319.37   795.8  320.39   821.9   323.8   842.1  325.08   859.2  328.28
   872.5  333.63   892.7  335.94   973.6  339.84  1014.1  343.95  1130.7  347.98
#Mann= 3 , 0 , 0
       0     .17       0     468     .06       0   508.3     .17       0
Bank Sta=468,508.3
XS Rating Curve= 0 ,0
Exp/Cntr=0.3,0.1

Type RM Length L Ch R = 1 ,21910   ,410,410,410
BEGIN DESCRIPTION:
PRAIRIE BRANCH 44.0
END DESCRIPTION:
XS GIS Cut Line= 3
      3803281.87     10231374.91      3802884.97     10231439.33
      3802191.89     10231569.54
#Sta/Elev= 30
  4597.9  348.42  4667.7  341.59  4672.9  340.12  4753.9  330.72  4790.9  324.73
  4868.3  314.55  4926.2  307.95  4966.7  305.57  4975.7  303.57  4980.8  303.85
  4986.9  301.59    5000  300.66  5001.4  298.93    5013  298.93  5017.4  302.29
  5027.6  304.63  5078.5  304.83  5092.2  303.64  5144.7  304.76  5180.2  303.73
  5190.4  302.16  5210.7  304.82  5272.3   308.4  5307.4  310.87  5434.6  326.96
  5474.6   330.8  5536.3  336.82  5623.1     342  5648.3  344.11  5705.2  345.88
#Mann= 7 ,-1 , 0
  4597.9     .17       0  4868.3     .15       0  4966.7     .09       0
  5027.6     .15       0  5272.3     .17       0  5474.6     .11       0
  5623.1     .17       0
Bank Sta=4966.7,5027.6
XS Rating Curve= 0 ,0
Exp/Cntr=0.3,0.1

Type RM Length L Ch R = 1 ,21500   ,500,500,500
BEGIN DESCRIPTION:
PRAIRIE BRANCH 43.0
END DESCRIPTION:
XS GIS Cut Line= 3
      3803189.33     10231004.79      3802747.42     10231053.62
      3802169.09     10231511.26
#Sta/Elev= 30
  4555.4  343.51  4569.5  344.32  4660.3   341.4  4715.6  337.39  4751.1  334.02
  4758.1  331.41  4836.9  320.98  4883.2   312.8  4927.7  306.85  4969.4  302.98
  4979.4  302.41  4999.1  298.53  5010.7  298.53  5012.2  301.68  5033.8  302.92
  5062.6  303.57    5162  301.95  5182.8  302.78  5190.7  302.37  5197.2  299.99
  5221.5  303.81  5246.9  305.16  5282.1  310.78  5318.3  314.96  5389.6  321.05
  5538.6  330.71  5540.4  330.64  5596.3  332.73  5617.1  335.36  5737.5  342.97
#Mann= 8 ,-1 , 0
  4555.4     .17       0  4715.6     .11       0  4883.2     .15       0
  4969.4     .09       0  5033.8     .15       0  5221.5     .17       0
  5538.6     .11       0  5540.4     .17       0
Bank Sta=4969.4,5033.8
XS Rating Curve= 0 ,0
Exp/Cntr=0.3,0.1

Type RM Length L Ch R = 1 ,21000   ,500,500,500
BEGIN DESCRIPTION:
PRAIRIE BRANCH 42.0
END DESCRIPTION:
XS GIS Cut Line= 3
      3803230.78      10230934.2      3802675.02     10230568.12
       3801861.3      10230464.4
#Sta/Elev= 30
  4334.5  342.49  4455.1  333.11    4461  331.87  4491.2  330.58  4518.2  327.35
  4563.5  324.91  4577.5  322.44  4599.6   320.9  4635.8  315.91    4699  310.25
  4771.4  305.34  4873.7  300.11  4960.7  300.87  4967.2  296.26  4978.9  296.26
  4982.1  298.56  4988.1   298.4  4995.3   300.7  5037.5  299.87  5047.5  297.95
  5077.8  299.97  5118.1  299.17  5128.2  300.16  5218.9  300.64  5253.8   302.3
  5450.8  316.33  5565.4  321.66  5616.7   324.9    5733  332.59  5820.3  340.35
#Mann= 6 ,-1 , 0
  4334.5     .17       0  4771.4     .15       0  4960.7     .09       0
  4995.3     .15       0  5565.4     .17       0  5616.7     .11       0
Bank Sta=4960.7,4995.3
XS Rating Curve= 0 ,0
Exp/Cntr=0.3,0.1

Type RM Length L Ch R = 1 ,20500   ,500,500,500
BEGIN DESCRIPTION:
PRAIRIE BRANCH 41.0
END DESCRIPTION:
XS GIS Cut Line= 3
      3803323.26     10230091.66      3802758.93     10230082.27
      3802064.37     10229706.92
#Sta/Elev= 30
  4435.6  342.54    4461  342.77    4531  340.26    4561  337.56  4594.3  332.46
    4768  308.85  4811.1  302.81  4871.1  297.97    5010  298.22  5037.5  299.03
  5069.4  297.78  5097.5   297.9  5103.5  298.76  5119.4  298.14  5129.4  293.95
  5141.7  293.95    5149  296.79  5163.2   298.7  5179.4  299.22  5228.8  303.58
  5310.7  314.75  5317.6  314.91  5370.6   318.8  5392.5  318.77  5430.6  320.69
  5452.5   322.6  5578.1  328.81  5694.6   336.5    5777  340.27  5789.5  340.88
#Mann= 7 ,-1 , 0
  4435.6     .17       0  4594.3     .11       0    4768     .15       0
  5103.5     .09       0  5163.2     .15       0  5317.6     .17       0
    5777     .11       0
Bank Sta=5103.5,5163.2
XS Rating Curve= 0 ,0
Exp/Cntr=0.3,0.1

Type RM Length L Ch R = 1 ,20000   ,500,500,500
BEGIN DESCRIPTION:
PRAIRIE BRANCH 40.0
END DESCRIPTION:
XS GIS Cut Line= 3
       3803345.2     10229994.26      3802852.48     10229591.63
      3802108.18     10229519.43
#Sta/Elev= 30
  4363.7     346  4470.8  337.53  4485.1  337.59  4585.4  324.56  4716.4  305.61
  4761.5  300.46  4818.9  296.89  4847.7  295.89  4903.6  297.41    4918  296.07
  4967.5  296.36  4996.3  296.11  5018.6  292.68  5030.9  292.68  5034.8  294.77
  5058.7  296.37  5095.1  295.89  5162.7     300  5185.5   302.1  5195.5  299.99
  5225.7  301.01  5262.8  306.05  5267.8  305.03  5306.1  307.18  5336.2  312.46
  5364.8  315.69  5557.9  328.79  5647.7  336.54    5718  340.06  5747.8  343.41
#Mann= 7 ,-1 , 0
  4363.7     .17       0  4585.4     .11       0  4716.4     .15       0
  4967.5     .09       0  5058.7     .15       0  5162.7     .11       0
  5557.9     .17       0
Bank Sta=4967.5,5058.7
XS Rating Curve= 0 ,0
Exp/Cntr=0.3,0.1

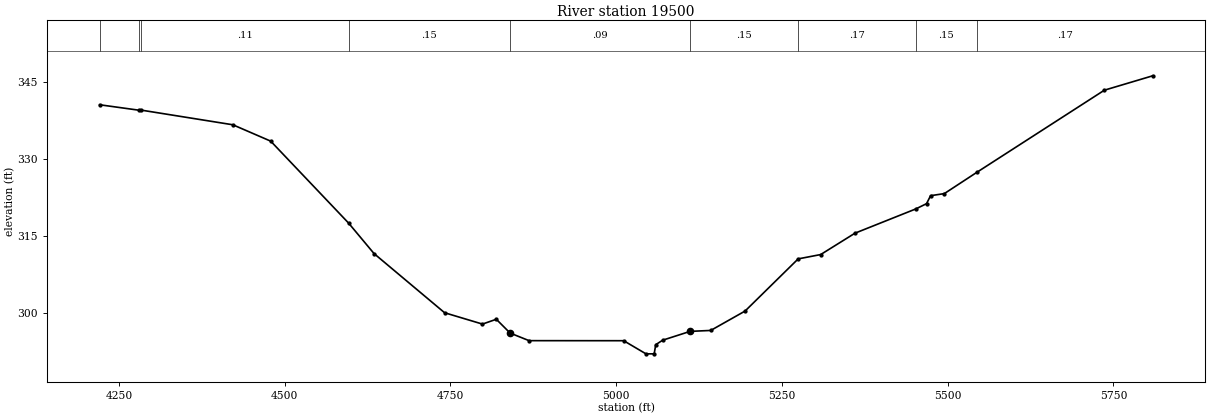
Type RM Length L Ch R = 1 ,19500   ,500,500,500
BEGIN DESCRIPTION:
PRAIRIE BRANCH 39.0
END DESCRIPTION:
XS GIS Cut Line= 3
       3803527.8     10229604.65      3802935.57     10229098.58
      3802154.49     10228886.34
#Sta/Elev= 30
    4221  340.59  4279.7  339.54  4283.5  339.55  4421.9  336.69    4479   333.5
  4596.4  317.54  4634.9  311.58  4741.3  300.05  4798.4  297.84  4819.3  298.78
  4840.1  296.09  4868.7  294.61  5011.4   294.6    5045  292.04  5057.4  292.04
  5059.8  293.83  5070.2   294.7  5111.6  296.42  5142.7   296.6  5194.5  300.38
  5274.6  310.55  5308.5  311.39  5360.3  315.56  5451.7  320.27  5468.2  321.31
  5474.3  322.87    5495  323.27  5544.3  327.44  5736.4  343.43  5809.4  346.24
#Mann= 9 ,-1 , 0
    4221     .11       0  4279.7     .15       0  4283.5     .11       0
  4596.4     .15       0  4840.1     .09       0  5111.6     .15       0
  5274.6     .17       0  5451.7     .15       0  5544.3     .17       0
Bank Sta=4840.1,5111.6
XS Rating Curve= 0 ,0
Exp/Cntr=0.3,0.1