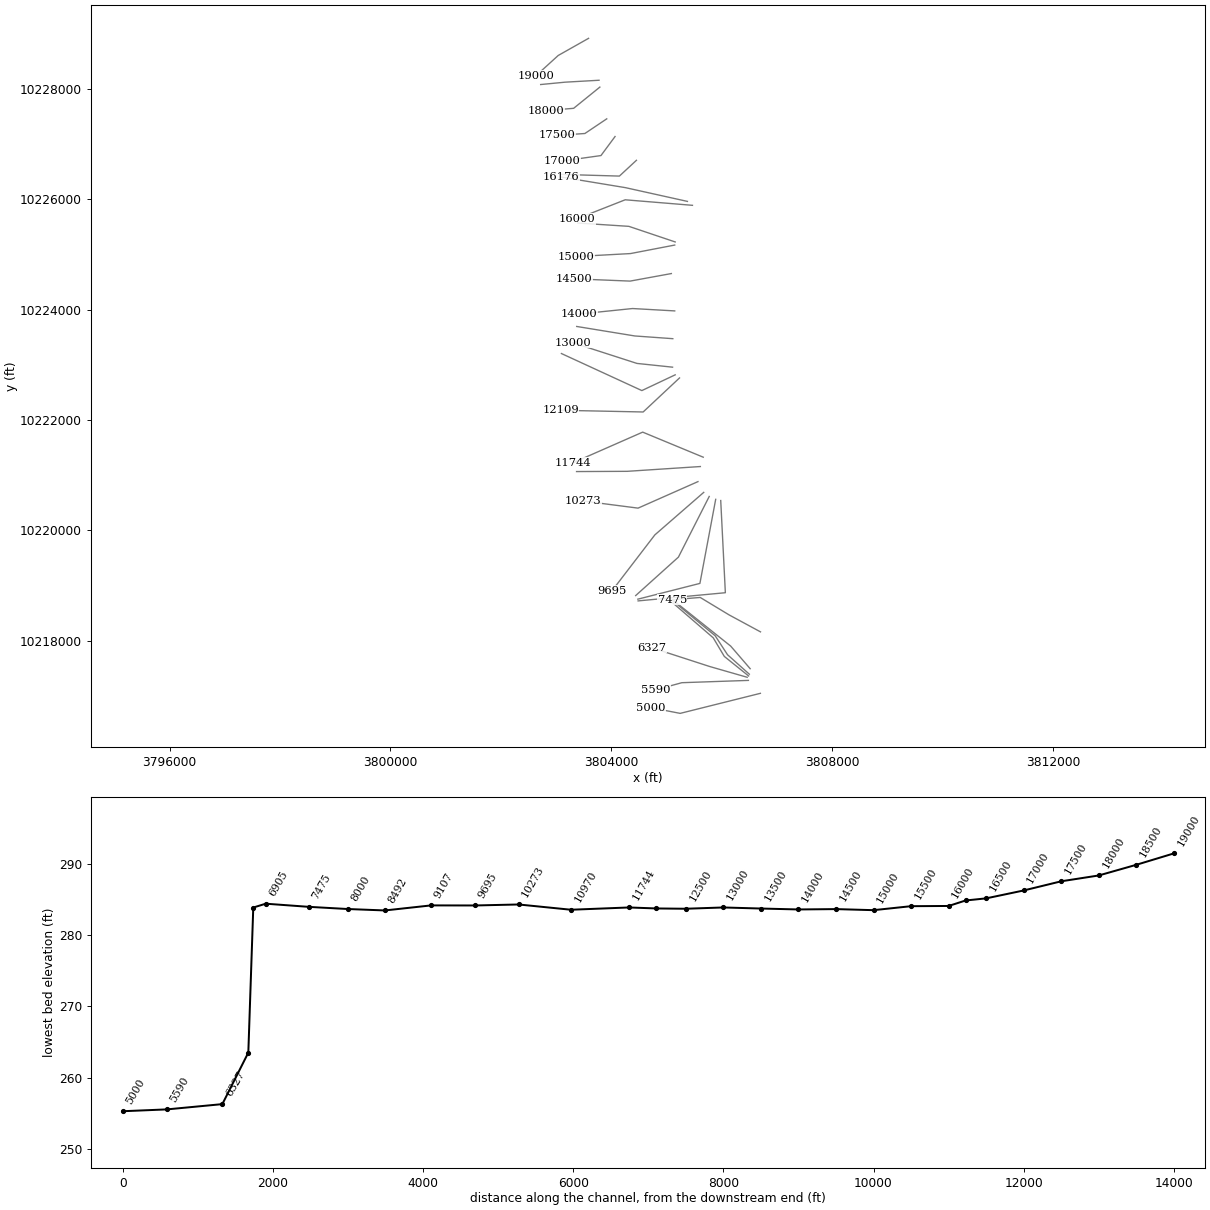
HEC-RAS study PRAIRIE BRANCH.prj: PRAIRIE BRANCH Base Level Engineering

--- PRAIRIE BRANCH.g01 (geometry) --- (continued)

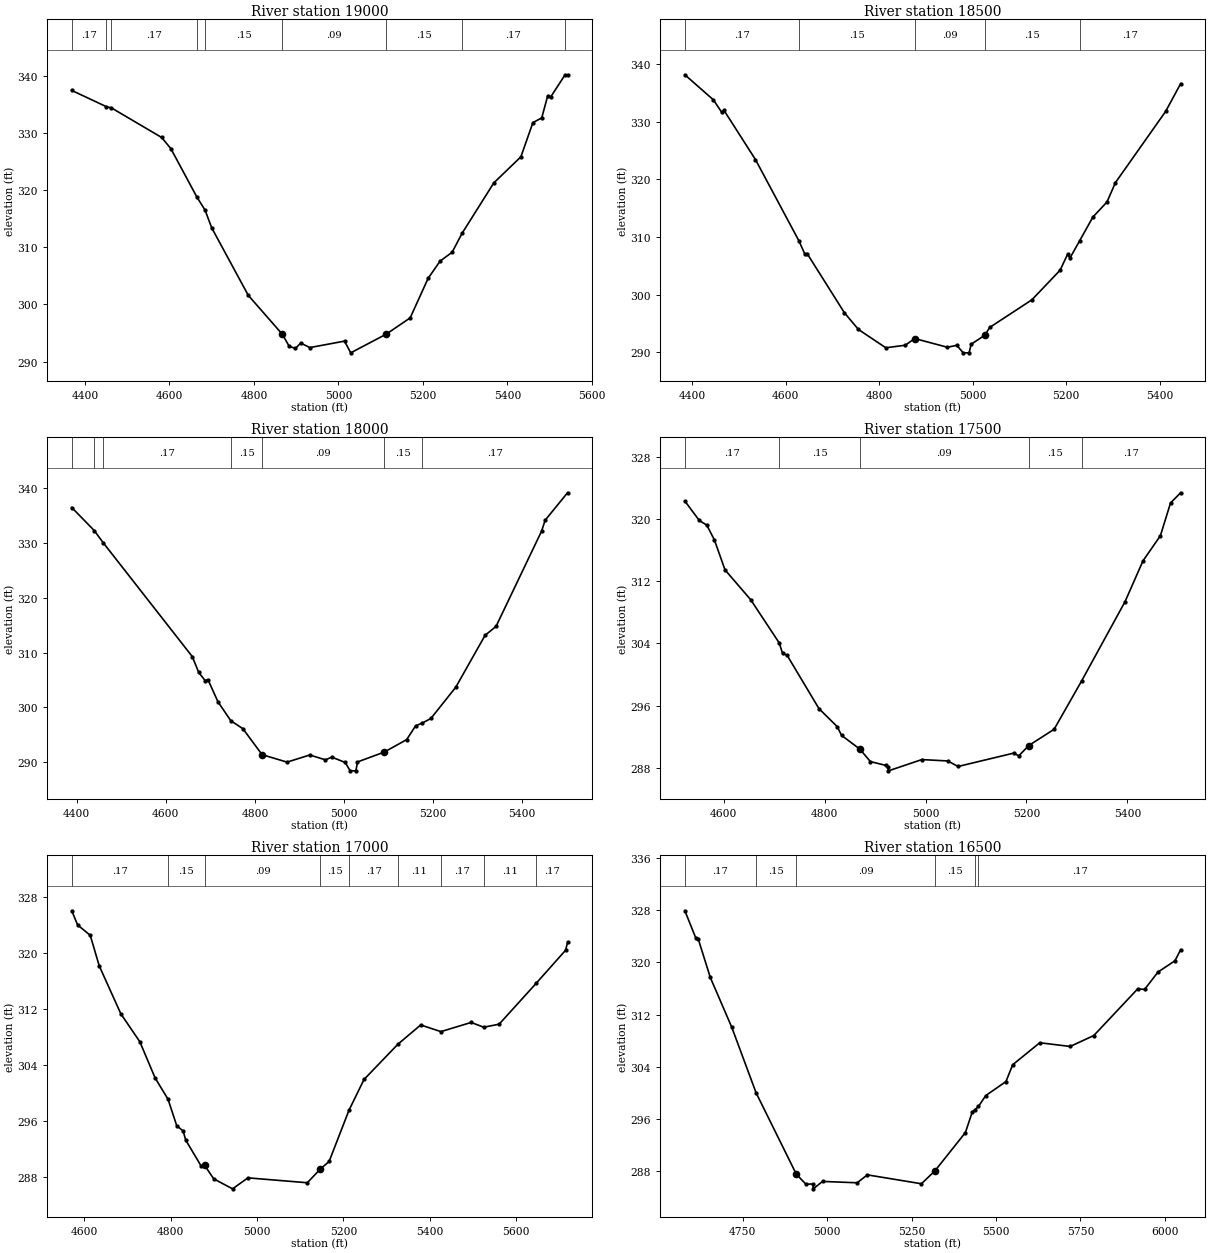
Type RM Length L Ch R = 1 ,19000   ,500,500,500
BEGIN DESCRIPTION:
PRAIRIE BRANCH 38.0
END DESCRIPTION:
XS GIS Cut Line= 3
      3803588.71     10228920.44      3803039.08     10228609.88
      3802637.98     10228244.75
#Sta/Elev= 30
  4368.7  337.39  4450.8  334.55  4462.4  334.35  4581.5  329.17  4603.2  327.23
  4665.1  318.73  4684.3  316.47  4699.9  313.39  4786.5  301.58  4867.4  294.75
  4883.3  292.68    4898  292.28  4910.7  293.22  4932.5  292.44  5014.5  293.57
  5029.1  291.52  5113.1  294.78  5169.9  297.63  5212.4  304.55  5240.8  307.56
  5269.2   309.1  5292.7  312.41  5367.9  321.23    5432  325.79  5460.4  331.76
  5481.4   332.6  5495.6  336.48  5502.3  336.22  5536.2  340.08  5542.4  340.13
#Mann= 9 ,-1 , 0
  4368.7     .17       0  4450.8     .11       0  4462.4     .17       0
  4665.1     .11       0  4684.3     .15       0  4867.4     .09       0
  5113.1     .15       0  5292.7     .17       0  5536.2     .11       0
Bank Sta=4867.4,5113.1
XS Rating Curve= 0 ,0
Exp/Cntr=0.3,0.1

Type RM Length L Ch R = 1 ,18500   ,500,500,500
BEGIN DESCRIPTION:
PRAIRIE BRANCH 37.0
END DESCRIPTION:
XS GIS Cut Line= 3
      3803778.65      10228160.7      3803163.75     10228125.67
      3802721.11     10228082.95
#Sta/Elev= 30
  4384.1  338.16    4445  333.82  4462.8  331.67  4467.8  331.99  4535.1  323.45
  4628.2  309.33  4640.8  307.04  4645.8  307.12  4725.5  296.86  4755.5  293.97
  4813.9   290.8  4855.7  291.24  4875.7   292.4  4945.8  290.89  4965.8  291.23
  4979.6  289.92  4992.2  289.92  4996.5  291.41    5026  292.99  5036.1  294.32
  5126.5  299.12  5186.8  304.25  5202.9  307.02  5207.9  306.36  5228.7  309.37
  5257.1  313.49  5287.2   316.1  5305.2  319.45  5412.5  331.79  5444.7  336.61
#Mann= 5 ,-1 , 0
  4384.1     .17       0  4628.2     .15       0  4875.7     .09       0
    5026     .15       0  5228.7     .17       0
Bank Sta=4875.7,5026
XS Rating Curve= 0 ,0
Exp/Cntr=0.3,0.1

Type RM Length L Ch R = 1 ,18000   ,500,500,500
BEGIN DESCRIPTION:
PRAIRIE BRANCH 36.0
END DESCRIPTION:
XS GIS Cut Line= 3
       3803793.2     10228036.49       3803318.2     10227651.86
      3802817.86     10227611.07
#Sta/Elev= 30
  4388.8  336.49  4439.2  332.29  4459.4  330.06  4659.5  309.27  4673.9  306.38
  4688.3   304.9  4694.7  305.06  4717.1  301.02    4746  297.56  4773.1  296.11
  4816.2  291.37  4872.2  290.01  4923.2  291.31  4958.5  290.43  4972.8  290.92
  5002.7  289.95  5014.1  288.42  5026.8  288.42  5030.4  290.04  5090.6  291.85
  5140.8  294.12  5160.9  296.64    5176  297.15  5195.2  297.98  5251.2   303.7
  5316.9  313.16  5341.5  314.79  5443.7  332.17  5451.8  334.17    5502  339.18
#Mann= 7 ,-1 , 0
  4388.8     .17       0  4439.2     .11       0  4459.4     .17       0
    4746     .15       0  4816.2     .09       0  5090.6     .15       0
    5176     .17       0
Bank Sta=4816.2,5090.6
XS Rating Curve= 0 ,0
Exp/Cntr=0.3,0.1

Type RM Length L Ch R = 1 ,17500   ,500,500,500
BEGIN DESCRIPTION:
PRAIRIE BRANCH 35.0
END DESCRIPTION:
XS GIS Cut Line= 3
      3803917.85     10227461.07      3803522.09     10227195.32
      3803017.86     10227161.07
#Sta/Elev= 30
  4523.3  322.31  4551.8  319.82  4566.8  319.21  4581.8  317.31  4602.8  313.46
  4653.8  309.61  4710.3  304.05  4716.8   302.7  4725.8  302.47  4788.9  295.61
  4824.9   293.3  4833.8  292.16  4869.8   290.4  4890.9  288.79  4920.8  288.31
    4926   288.1  4926.5   287.6  4992.8  289.05  5044.3  288.87  5064.4  288.16
  5174.6  289.88  5184.7  289.53  5204.7  290.86  5254.8  292.95  5309.1  299.15
  5395.2  309.36  5430.9  314.63  5465.3  317.85  5485.4  322.07  5505.4  323.38
#Mann= 5 ,-1 , 0
  4523.3     .17       0  4710.3     .15       0  4869.8     .09       0
  5204.7     .15       0  5309.1     .17       0
Bank Sta=4869.8,5204.7
XS Rating Curve= 0 ,0
Exp/Cntr=0.3,0.1

Type RM Length L Ch R = 1 ,17000   ,500,500,500
BEGIN DESCRIPTION:
PRAIRIE BRANCH 34.0
END DESCRIPTION:
XS GIS Cut Line= 3
      3804068.36      10227140.4      3803813.02      10226795.3
      3803101.03     10226695.08
#Sta/Elev= 30
  4570.7  326.05  4584.2  324.03  4613.5  322.54  4634.3  318.18  4684.4  311.32
  4728.3  307.34  4763.8  302.15  4793.6  299.13  4813.9  295.32  4828.5   294.6
  4834.7  293.27  4870.2  289.59  4878.6  289.65  4899.5  287.74  4943.1  286.31
  4978.8  287.88  5116.3  287.18  5146.6  289.15  5166.8  290.22  5212.8  297.54
  5247.6  301.94  5326.5     307  5378.9  309.73  5425.7  308.78  5495.8  310.09
  5524.8  309.41  5560.6  309.84  5646.2  315.67  5714.5  320.41    5719  321.52
#Mann= 9 ,-1 , 0
  4570.7     .17       0  4793.6     .15       0  4878.6     .09       0
  5146.6     .15       0  5212.8     .17       0  5326.5     .11       0
  5425.7     .17       0  5524.8     .11       0  5646.2     .17       0
Bank Sta=4878.6,5146.6
XS Rating Curve= 0 ,0
Exp/Cntr=0.3,0.1

Type RM Length L Ch R = 1 ,16500   ,274,274,274
BEGIN DESCRIPTION:
PRAIRIE BRANCH 33.0
END DESCRIPTION:
XS GIS Cut Line= 3
      3804455.56     10226709.45      3804147.14     10226423.33
      3803101.08     10226453.71
#Sta/Elev= 30
  4579.3  327.95    4612  323.71  4618.8  323.62  4654.5   317.7    4718  310.05
    4790  299.97  4909.1  287.45  4937.4  285.92  4958.4  285.94  4959.2   285.2
  4986.7  286.34  5089.3  286.13  5119.3  287.35  5279.4  285.98  5319.4  287.97
  5409.5  293.85  5429.5  296.96    5438  297.37  5448.2  297.86  5469.5  299.53
  5529.5  301.69  5549.5  304.28  5629.6  307.66  5719.6  307.09  5789.6  308.77
  5919.7  315.96  5939.7  315.85  5979.7  318.54  6029.7  320.26  6046.5  321.96
#Mann= 6 ,-1 , 0
  4579.3     .17       0    4790     .15       0  4909.1     .09       0
  5319.4     .15       0    5438     .15       0  5448.2     .17       0
Bank Sta=4909.1,5319.4
XS Rating Curve= 0 ,0
Exp/Cntr=0.3,0.1

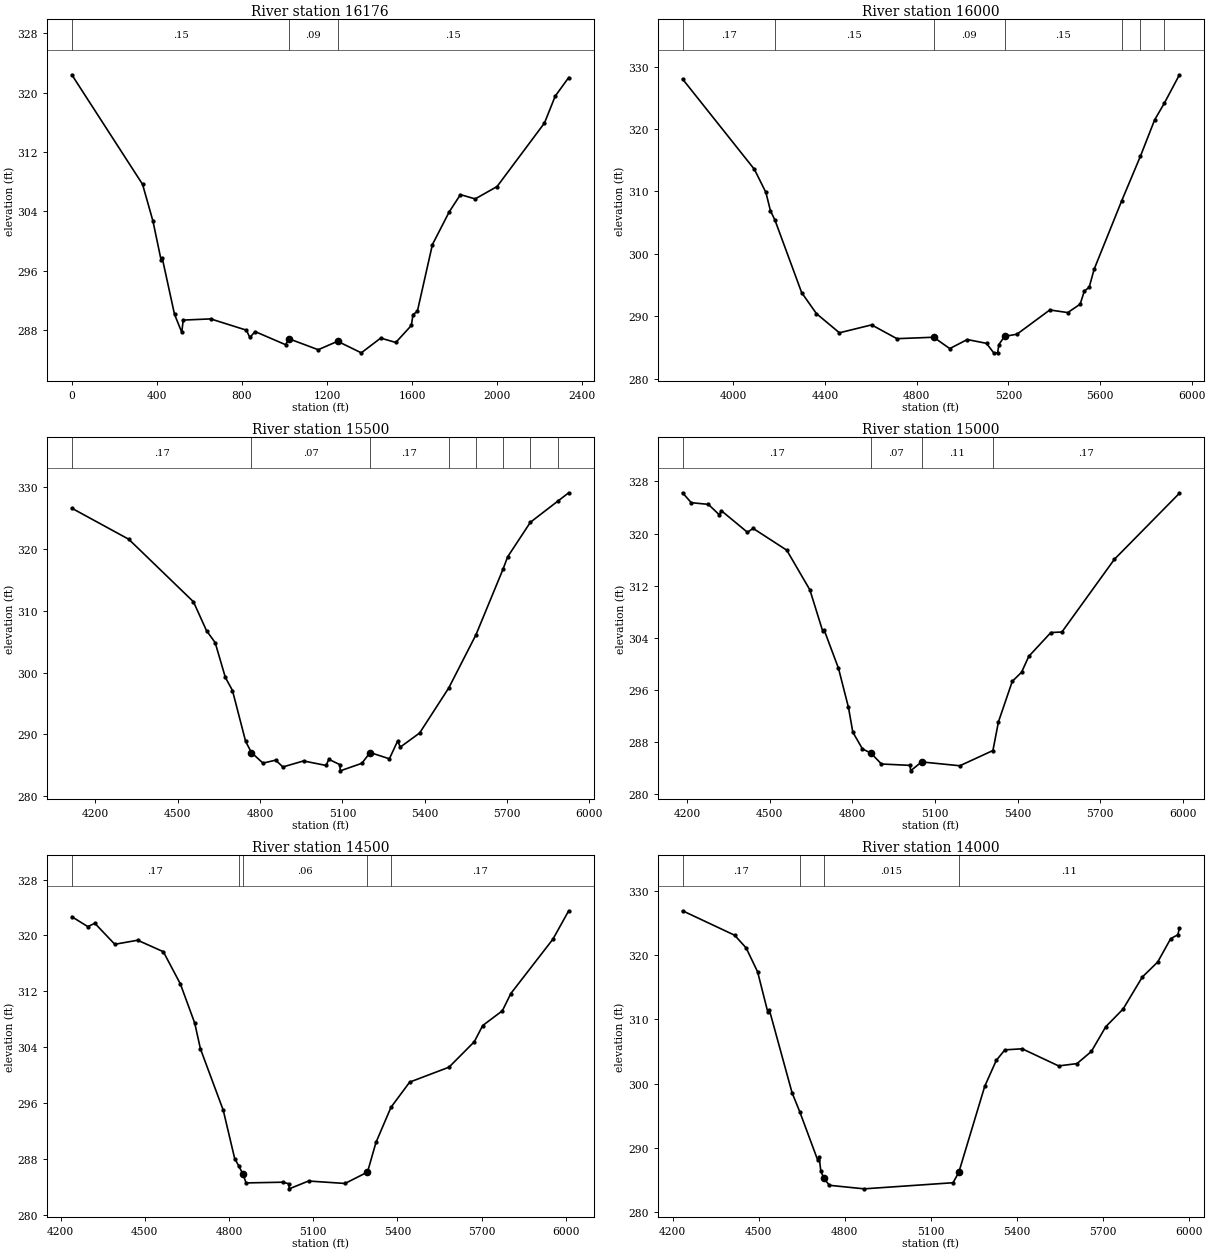
Type RM Length L Ch R = 1 ,16176   ,226,226,226
XS GIS Cut Line= 3
       3805379.4     10225964.36      3804255.33     10226213.86
      3803085.31     10226407.28
#Sta/Elev= 30
       0  322.42   332.7  307.64   381.4   302.7   419.8  297.44     425  297.73
     483   290.1   517.2  287.67     524  289.32     653  289.48   821.1  287.96
   837.5  286.97     862  287.77  1005.4     286    1022  286.79    1159  285.32
  1250.2  286.46  1361.7   284.9  1452.9  286.89  1523.9   286.3    1597  288.59
    1605  290.07  1625.3  290.49  1696.2  299.51  1775.2  303.92    1828  306.25
  1897.3  305.67  2000.3  307.34  2223.3  315.91  2273.9  319.54  2337.3  322.05
#Mann= 3 , 0 , 0
       0     .15       0    1022     .09       0  1250.2     .15       0
Bank Sta=1022,1250.2
XS Rating Curve= 0 ,0
Exp/Cntr=0.3,0.1

Type RM Length L Ch R = 1 ,16000   ,500,500,500
BEGIN DESCRIPTION:
PRAIRIE BRANCH 32.0
END DESCRIPTION:
XS GIS Cut Line= 3
      3805470.37     10225893.38      3804252.28     10225993.59
      3803371.35     10225646.63
#Sta/Elev= 30
  3777.8     328  4091.4  313.53  4141.5  309.84  4161.6  306.88  4181.2  305.39
  4297.8  293.77  4362.3  290.41  4462.6  287.34  4603.1  288.61  4713.5   286.4
    4874  286.63  4944.2  284.81  5020.7  286.26  5104.6  285.65    5136  284.13
    5153  284.13  5158.8  285.46  5183.2  286.77  5237.3  287.11  5380.9     291
  5459.3  290.58  5513.5  291.93  5531.4     294  5552.9  294.65  5574.4  297.52
    5694  308.42  5776.8  315.66  5838.4  321.44  5881.3  324.16  5946.8  328.68
#Mann= 7 ,-1 , 0
  3777.8     .17       0  4181.2     .15       0    4874     .09       0
  5183.2     .15       0    5694     .11       0  5776.8     .15       0
  5881.3     .17       0
Bank Sta=4874,5183.2
XS Rating Curve= 0 ,0
Exp/Cntr=0.3,0.1

Type RM Length L Ch R = 1 ,15500   ,500,500,500
BEGIN DESCRIPTION:
PRAIRIE BRANCH 31.0
END DESCRIPTION:
XS GIS Cut Line= 3
      3805157.87     10225229.32      3804318.23     10225512.18
      3803395.78     10225572.19
#Sta/Elev= 30
    4114   326.6  4321.4  321.58  4557.2  311.46  4604.8  306.78  4636.3  304.85
  4673.3  299.23  4699.3   297.1  4747.1  288.89  4768.3  287.06  4810.5  285.35
  4856.8  285.83    4883  284.73  4958.2   285.7  5040.5  284.97  5050.5  285.97
  5090.6   285.1  5092.1   284.1  5170.7  285.32  5200.8  287.06    5271  286.05
    5301  288.91    5311  287.95  5381.2  290.22  5487.3  297.51  5586.5  306.12
  5685.6  316.79  5701.9  318.73  5784.8  324.33    5884  327.72  5924.4   329.1
#Mann= 8 ,-1 , 0
    4114     .17       0  4768.3     .07       0  5200.8     .17       0
  5487.3     .11       0  5586.5     .15       0  5685.6     .17       0
  5784.8     .15       0    5884     .11       0
Bank Sta=4768.3,5200.8
XS Rating Curve= 0 ,0
Exp/Cntr=0.3,0.1

Type RM Length L Ch R = 1 ,15000   ,500,500,500
BEGIN DESCRIPTION:
PRAIRIE BRANCH 30.0
END DESCRIPTION:
XS GIS Cut Line= 3
      3805149.24      10225172.9      3804347.63     10225018.69
      3803361.92     10224964.61
#Sta/Elev= 30
  4183.7  326.26  4215.2  324.74  4277.3  324.48  4317.5  322.86  4324.1  323.52
  4419.3  320.19  4439.7  320.79  4561.9  317.44  4645.9  311.34  4692.7  304.96
  4697.8  305.16  4749.7  299.29  4785.9  293.28  4801.7  289.48  4836.8   286.9
  4867.4  286.27  4905.5  284.59  5009.8  284.38  5011.3  283.54  5051.4  284.91
  5190.1  284.32  5310.2  286.66  5330.3  291.07  5380.4  297.28  5414.2  298.69
  5440.4  301.13  5520.6  304.79  5560.6  304.87  5750.9  316.03  5987.2  326.19
#Mann= 4 ,-1 , 0
  4183.7     .17       0  4867.4     .07       0  5051.4     .11       0
  5310.2     .17       0
Bank Sta=4867.4,5051.4
XS Rating Curve= 0 ,0
Exp/Cntr=0.3,0.1

Type RM Length L Ch R = 1 ,14500   ,500,500,500
BEGIN DESCRIPTION:
PRAIRIE BRANCH 29.0
END DESCRIPTION:
XS GIS Cut Line= 3
      3805088.45      10224656.4      3804340.84     10224519.71
      3803331.78     10224560.87
#Sta/Elev= 30
    4240  322.68    4297  321.26  4321.9  321.74  4393.1  318.73  4474.4  319.31
  4565.9  317.67  4626.4  313.07  4677.7  307.45  4698.1  303.75  4779.4  294.95
  4820.1  288.03  4834.7  286.97  4849.5   285.8  4860.7  284.54  4992.9  284.64
    5013  284.41  5014.4  283.69  5083.1  284.81  5213.2  284.46  5293.2  286.09
  5323.3  290.33  5376.8  295.37  5443.4  298.98  5583.5  301.12  5673.5  304.76
  5703.6  307.09  5773.6   309.2  5803.7  311.67  5953.8  319.47  6009.9  323.53
#Mann= 5 ,-1 , 0
    4240     .17       0  4834.7     .11       0  4849.5     .06       0
  5293.2     .11       0  5376.8     .17       0
Bank Sta=4849.5,5293.2
XS Rating Curve= 0 ,0
Exp/Cntr=0.3,0.1

Type RM Length L Ch R = 1 ,14000   ,500,500,500
BEGIN DESCRIPTION:
PRAIRIE BRANCH 28.0
END DESCRIPTION:
XS GIS Cut Line= 3
      3805149.18     10223979.32      3804384.89     10224022.32
      3803422.31     10223922.95
#Sta/Elev= 30
  4234.5  326.87  4416.1  323.07  4456.2   321.1  4496.2  317.39    4532  311.09
    4537   311.5  4616.4  298.59    4643  295.66  4706.2  288.08  4711.2  288.54
  4716.6  286.46  4726.6  285.34  4746.6  284.19  4868.2  283.64    5178  284.59
  5198.1  286.21  5288.6  299.59  5328.8  303.61  5358.9  305.25  5419.3  305.41
  5546.3  302.75  5610.3  303.11  5660.5     305  5710.8  308.85  5771.1  311.59
  5838.2  316.57  5891.8   318.9  5937.1  322.53  5962.1  323.14  5967.7  324.18
#Mann= 4 ,-1 , 0
  4234.5     .17       0    4643     .11       0  4726.6    .015       0
  5198.1     .11       0
Bank Sta=4726.6,5198.1
XS Rating Curve= 0 ,0
Exp/Cntr=0.3,0.1

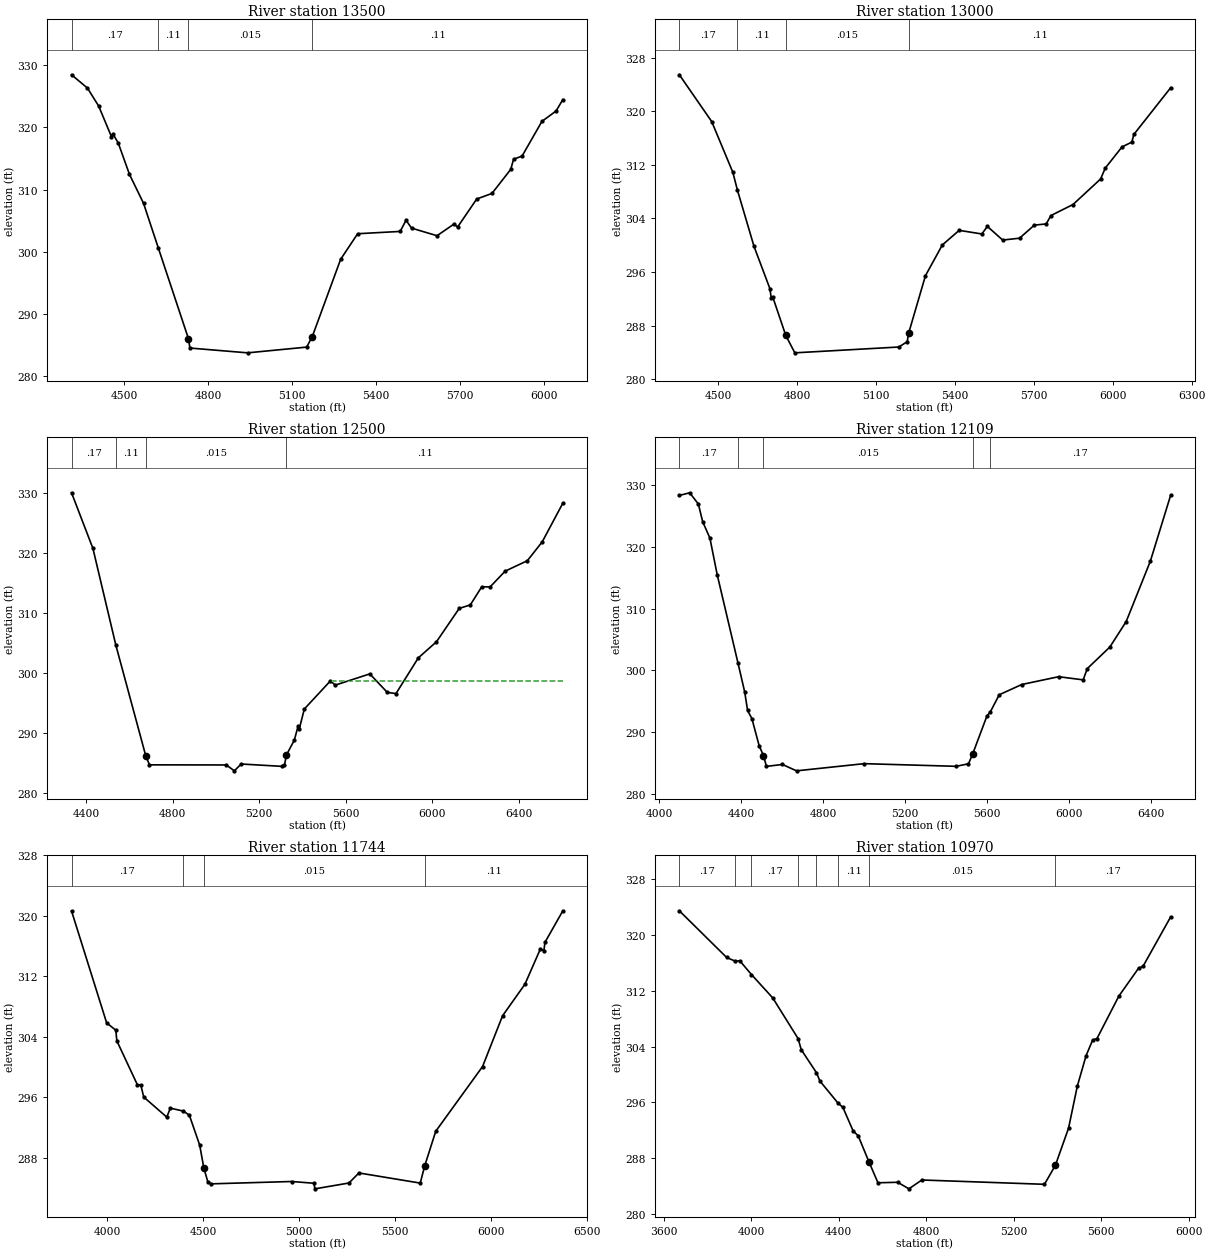
Type RM Length L Ch R = 1 ,13500   ,500,500,500
BEGIN DESCRIPTION:
PRAIRIE BRANCH 27.0
END DESCRIPTION:
XS GIS Cut Line= 3
      3805114.45     10223475.85      3804427.21     10223525.01
      3803373.99     10223697.21
#Sta/Elev= 30
    4311  328.45  4367.7  326.32  4407.8  323.44  4453.6  318.51  4458.7  318.98
    4478  317.48  4518.1  312.44  4568.3   307.8  4620.8  300.67  4728.7  286.07
  4734.1  284.54  4940.5  283.77  5151.3  284.69  5171.6  286.39  5272.9   298.8
  5333.7  302.91  5485.7  303.28  5506.7  305.08  5526.3  303.81  5617.4  302.59
  5678.2  304.47  5690.9  303.98  5759.3  308.49  5813.7  309.38  5880.9  313.25
    5891  314.88  5921.4  315.39  5992.4  320.96    6043  322.63  6067.2  324.47
#Mann= 4 ,-1 , 0
    4311     .17       0  4620.8     .11       0  4728.7    .015       0
  5171.6     .11       0
Bank Sta=4728.7,5171.6
XS Rating Curve= 0 ,0
Exp/Cntr=0.3,0.1

Type RM Length L Ch R = 1 ,13000   ,500,500,500
BEGIN DESCRIPTION:
PRAIRIE BRANCH 26.5
END DESCRIPTION:
XS GIS Cut Line= 3
      3805110.16     10222959.35      3804465.73     10223027.26
      3803304.62     10223402.05
#Sta/Elev= 30
    4352  325.44    4475  318.46  4555.4  310.88    4573   308.2  4635.9  299.82
  4696.2  293.52  4701.8  292.04  4706.8  292.31  4756.5  286.54  4791.1  283.92
  5186.6  284.79  5218.4  285.58  5223.8  286.85  5287.9  295.45    5352  300.03
  5416.1  302.21  5502.2  301.67  5523.2   302.8  5581.5  300.76  5645.6  301.04
  5701.8  302.99    5747  303.17  5764.9  304.42  5848.9  306.07    5954  309.89
  5971.3   311.5  6035.3  314.67  6072.6  315.39  6080.1  316.53  6220.1   323.5
#Mann= 4 ,-1 , 0
    4352     .17       0    4573     .11       0  4756.5    .015       0
  5223.8     .11       0
Bank Sta=4756.5,5223.8
XS Rating Curve= 0 ,0
Exp/Cntr=0.3,0.1

Type RM Length L Ch R = 1 ,12500   ,391,391,391
BEGIN DESCRIPTION:
PRAIRIE BRANCH 25.0
END DESCRIPTION:
XS GIS Cut Line= 3
      3805157.86     10222820.44      3804553.87     10222535.09
        3803097.     10223206.41
#Sta/Elev= 30
    4332  330.12  4430.9  320.83  4536.9   304.7  4675.2  286.24  4692.4  284.74
  5047.6  284.72  5084.9  283.74  5116.5  284.88  5303.9  284.49  5316.7  284.71
  5325.9   286.4  5362.6  288.89  5380.1  291.28  5385.6  290.79  5408.5  294.05
  5528.8  298.73  5551.8  298.04  5711.3  299.91  5792.4  296.82  5832.4  296.63
  5935.6  302.58  6019.6  305.27  6124.8  310.83  6176.2  311.42  6228.8  314.43
  6268.1  314.43  6336.9  317.04  6439.8  318.79  6508.6  321.93  6604.1  328.39
#Mann= 4 ,-1 , 0
    4332     .17       0  4536.9     .11       0  4675.2    .015       0
  5325.9     .11       0
#XS Ineff= 2 , 0
       0                  5535.1       0  298.79
Permanent Ineff=
       F       F
Bank Sta=4675.2,5325.9
XS Rating Curve= 0 ,0
Exp/Cntr=0.3,0.1

Type RM Length L Ch R = 1 ,12109   ,365,365,365
BEGIN DESCRIPTION:
PRAIRIE BRANCH 24.5
END DESCRIPTION:
XS GIS Cut Line= 3
      3805236.04     10222764.05      3804577.46     10222147.13
      3803080.88     10222178.06
#Sta/Elev= 30
  4097.6  328.28  4148.1  328.71  4190.6  326.89  4211.6  324.03  4246.8   321.4
  4282.4  315.49  4384.3  301.16  4416.8  296.52  4430.9  293.53    4452  292.22
  4487.6  287.81  4508.6  286.24  4522.8   284.5  4600.9  284.81  4669.8  283.78
    5000  284.94  5449.7  284.51  5509.7  284.92  5529.7  286.47  5599.7  292.64
  5616.2   293.3  5659.7  296.07  5769.8  297.73  5949.8  298.99  6069.8  298.48
  6089.8   300.3  6199.9  303.78  6279.9  307.91  6397.8  317.66  6496.9  328.31
#Mann= 5 ,-1 , 0
  4097.6     .17       0  4384.3     .11       0  4508.6    .015       0
  5529.7     .11       0  5616.2     .17       0
Bank Sta=4508.6,5529.7
XS Rating Curve= 0 ,0
Exp/Cntr=0.3,0.1

Type RM Length L Ch R = 1 ,11744   ,774,774,774
BEGIN DESCRIPTION:
PRAIRIE BRANCH 26.0
END DESCRIPTION:
XS GIS Cut Line= 3
      3805665.71     10221327.41      3804568.92     10221781.83
      3803308.94     10221227.58
#Sta/Elev= 30
  3812.8  320.65    3996  305.86  4043.8  304.89  4049.2  303.48  4156.9  297.65
  4174.1  297.67  4189.3  296.06  4309.8   293.4  4328.2  294.59  4395.6   294.2
  4427.5  293.66  4481.6  289.69  4503.2  286.66  4524.9  284.76    4541  284.58
    4961  284.89  5077.6  284.66  5082.7  283.92  5260.3  284.69  5312.4  286.02
  5632.3  284.68  5655.6  286.96  5713.2  291.53  5957.6  300.09  6061.9   306.8
  6178.6  310.97  6259.5  315.65  6277.4  315.38  6282.9   316.5  6376.5  320.68
#Mann= 4 ,-1 , 0
  3812.8     .17       0  4395.6     .11       0  4503.2    .015       0
  5655.6     .11       0
Bank Sta=4503.2,5655.6
XS Rating Curve= 0 ,0
Exp/Cntr=0.3,0.1

Type RM Length L Ch R = 1 ,10970   ,697,697,697
BEGIN DESCRIPTION:
PRAIRIE BRANCH 24.0
END DESCRIPTION:
XS GIS Cut Line= 3
      3805613.62     10221158.13      3804287.86     10221071.22
      3803371.27       10221067.
#Sta/Elev= 30
  3671.4   323.5  3887.6   316.8  3926.8  316.27  3947.8  316.32    4001  314.35
  4098.1     311  4214.2  305.16  4228.4  303.57  4297.9  300.27    4314  299.06
  4396.6   295.9  4418.8  295.29  4465.6  291.91  4488.9   291.2    4539  287.39
  4579.1  284.47  4669.3  284.54  4720.5   283.6  4779.5  284.87    5340  284.25
    5390  286.99    5450   292.3    5490  298.32    5530   302.7    5560  304.94
    5580  305.17    5680  311.26    5770  315.26    5790  315.51  5916.6  322.62
#Mann= 8 ,-1 , 0
  3671.4     .17       0  3926.8     .11       0    4001     .17       0
  4214.2     .11       0  4297.9     .17       0  4396.6     .11       0
    4539    .015       0    5390     .17       0
Bank Sta=4539,5390
XS Rating Curve= 0 ,0
Exp/Cntr=0.3,0.1

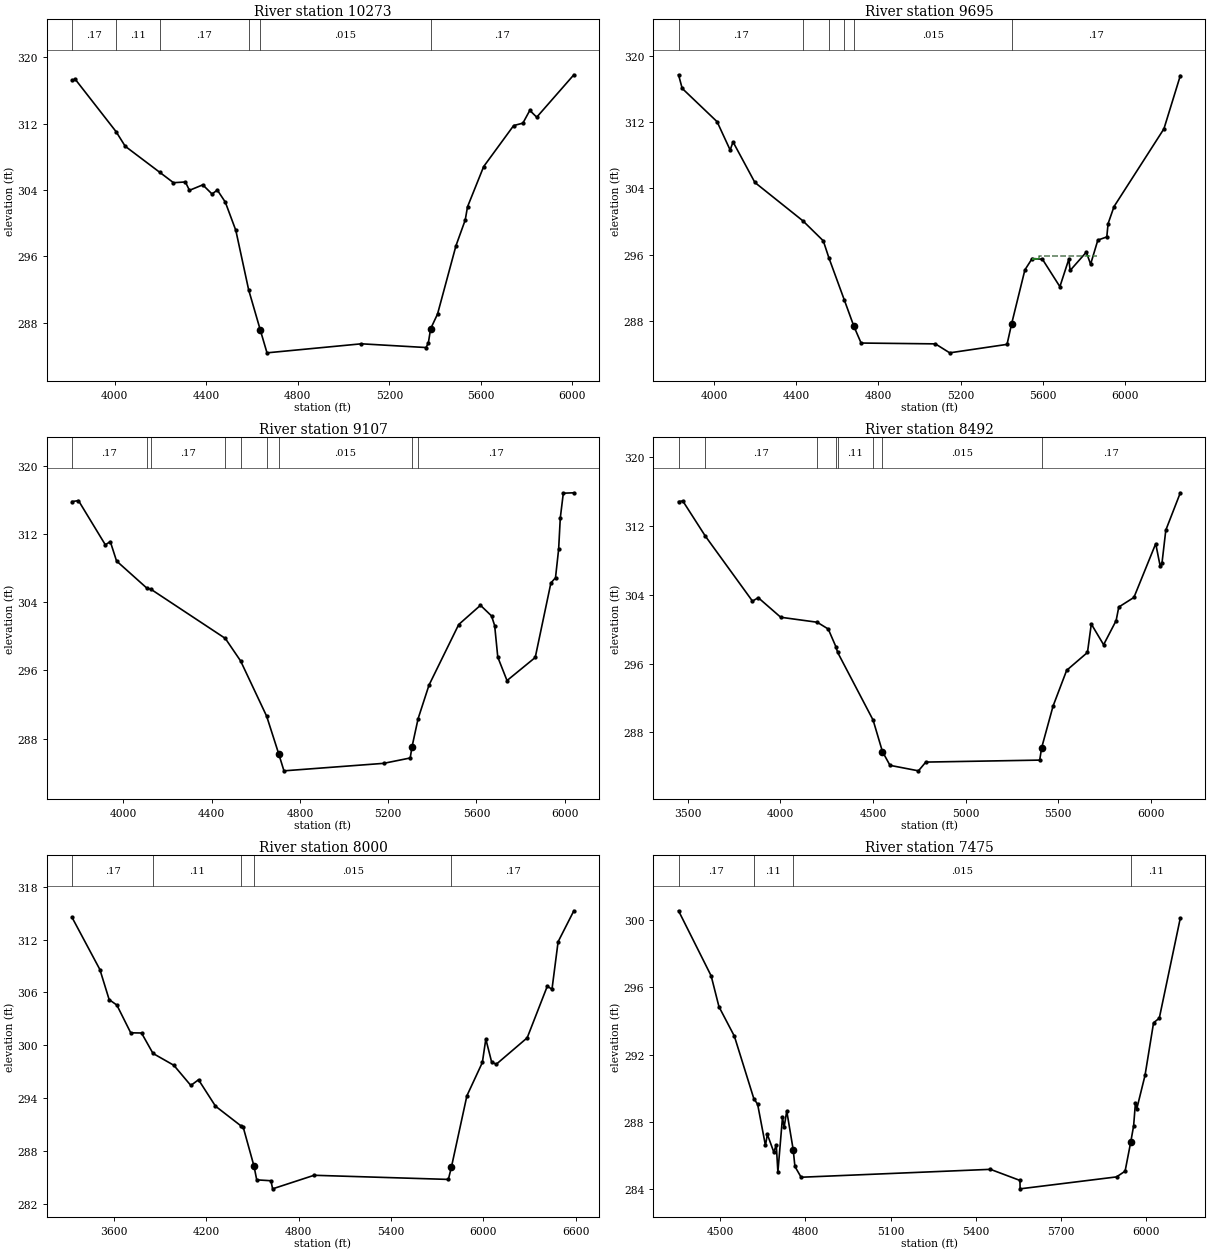
Type RM Length L Ch R = 1 ,10273   ,578,578,578
BEGIN DESCRIPTION:
PRAIRIE BRANCH 22.0
END DESCRIPTION:
XS GIS Cut Line= 3
       3805570.2     10220884.69      3804485.18     10220404.08
      3803486.89     10220533.13
#Sta/Elev= 30
  3813.3  317.22  3826.8  317.38  4005.5  311.05  4045.6  309.28  4196.8  306.13
  4256.6  304.88  4308.6  304.97  4326.4  303.96  4384.6  304.62    4425  303.52
  4448.3  303.99    4483  302.54  4529.1  299.12  4585.2  291.94  4636.2  287.08
  4665.3  284.34    5078  285.43  5360.3  284.98  5370.4  285.51  5380.5  287.24
  5410.7  289.02  5491.4  297.28  5531.7  300.37  5541.8  301.97  5612.4  306.83
  5743.5  311.78  5783.8  312.07    5814  313.61  5844.3  312.79  6006.6  317.91
#Mann= 6 ,-1 , 0
  3813.3     .17       0  4005.5     .11       0  4196.8     .17       0
  4585.2     .11       0  4636.2    .015       0  5380.5     .17       0
Bank Sta=4636.2,5380.5
XS Rating Curve= 0 ,0
Exp/Cntr=0.3,0.1

Type RM Length L Ch R = 1 ,9695    ,588,588,588
BEGIN DESCRIPTION:
PRAIRIE BRANCH 20.0
END DESCRIPTION:
XS GIS Cut Line= 3
       3805674.4      10220689.4      3804789.04     10219918.73
      3804016.42      10218909.9
#Sta/Elev= 30
  3826.2  317.69    3844  316.05    4014  312.04  4077.6  308.63  4091.8   309.6
  4198.1  304.72    4432   300.1  4531.4  297.69  4558.7  295.64  4634.5  290.52
  4680.5  287.39  4715.6  285.38  5077.4  285.28  5147.2   284.2  5426.5  285.22
  5449.2  287.73  5513.5  294.19  5548.9  295.56  5598.8  295.48    5684  292.17
  5727.6  295.49  5733.9  294.12  5812.8  296.33  5833.6  294.87  5868.9  297.78
  5912.5  298.16  5918.8  299.76  5947.8  301.82  6190.8  311.18  6270.7  317.59
#Mann= 6 ,-1 , 0
  3826.2     .17       0    4432     .11       0  4558.7     .17       0
  4634.5     .11       0  4680.5    .015       0  5449.2     .17       0
#XS Ineff= 2 ,-1
  5548.9  5584.3  295.56  5584.3  5862.6  295.81
Permanent Ineff=
       F       F
Bank Sta=4680.5,5449.2
XS Rating Curve= 0 ,0
Exp/Cntr=0.3,0.1

Type RM Length L Ch R = 1 ,9107    ,615,615,615
BEGIN DESCRIPTION:
PRAIRIE BRANCH 19.0
END DESCRIPTION:
XS GIS Cut Line= 3
       3805774.2     10220615.58      3805216.15     10219515.98
       3804442.3     10218819.22
#Sta/Elev= 30
  3766.9  315.83    3796  315.94  3917.7  310.75  3940.2  311.13  3968.5  308.85
  4105.2  305.68    4125  305.52  4461.4  299.76  4530.7  297.12  4648.8  290.63
  4703.1  286.24  4727.3  284.21  5179.3  285.09  5299.6  285.72  5307.1  286.96
  5335.4  290.34  5384.8  294.28  5519.4  301.39    5618  303.65  5668.1   302.4
  5682.3  301.27  5696.5  297.56  5738.3  294.81  5866.2  297.52  5937.2  306.27
  5958.1  306.88  5972.3  310.24  5979.8  313.91  5993.5  316.81  6041.3  316.86
#Mann= 9 ,-1 , 0
  3766.9     .17       0  4105.2     .11       0    4125     .17       0
  4461.4     .11       0  4530.7     .17       0  4648.8     .11       0
  4703.1    .015       0  5307.1     .11       0  5335.4     .17       0
#XS Ineff= 2 , 0
       0                    5618       0  303.65
Permanent Ineff=
       F       F
Bank Sta=4703.1,5307.1
XS Rating Curve= 0 ,0
Exp/Cntr=0.3,0.1

Type RM Length L Ch R = 1 ,8492    ,492,492,492
BEGIN DESCRIPTION:
PRAIRIE BRANCH 17.0
END DESCRIPTION:
XS GIS Cut Line= 3
       3805891.4     10220563.54       3805605.5     10219039.52
      3804481.83     10218753.88
#Sta/Elev= 30
  3449.4  314.87  3472.3  314.94  3593.9  310.85  3848.7  303.27  3879.9  303.67
  4001.3  301.39  4198.1  300.81  4257.9  300.02  4298.8  297.98  4308.9  297.29
  4500.2  289.41  4550.7  285.74  4591.4  284.14  4745.1   283.5  4784.8  284.52
    5400  284.75  5410.3  286.18  5472.2  291.05  5545.6  295.21  5657.9  297.29
  5678.6   300.6  5745.1  298.19  5812.7     301    5827  302.58  5908.8   303.7
  6026.5  309.96    6050  307.41  6060.3  307.69    6081  311.54  6159.4  315.89
#Mann= 8 ,-1 , 0
  3449.4     .11       0  3593.9     .17       0  4198.1     .11       0
  4298.8     .17       0  4308.9     .11       0  4500.2     .17       0
  4550.7    .015       0  5410.3     .17       0
Bank Sta=4550.7,5410.3
XS Rating Curve= 0 ,0
Exp/Cntr=0.3,0.1

Type RM Length L Ch R = 1 ,8000    ,525,525,525
BEGIN DESCRIPTION:
PRAIRIE BRANCH 16.0
END DESCRIPTION:
XS GIS Cut Line= 3
      3805982.55     10220541.78      3806066.45     10218870.69
       3804485.9     10218722.38
#Sta/Elev= 30
  3326.8  314.52  3507.7   308.6  3567.8  305.19  3617.9  304.57    3708  301.42
  3778.1   301.4  3852.7  299.08  3988.3  297.73  4098.5  295.44  4148.5  296.09
  4258.7  293.09  4424.4  290.85  4438.9   290.7    4509  286.28  4526.7  284.72
  4619.1  284.62    4630   283.7  4899.5  285.24    5772  284.77  5792.1  286.19
  5892.5  294.27  5992.9  298.05  6015.4  300.71  6053.2   298.1  6083.3  297.85
  6284.2  300.85  6414.8  306.71  6445.4  306.37  6485.1  311.76  6587.5  315.28
#Mann= 5 ,-1 , 0
  3326.8     .17       0  3852.7     .11       0  4424.4     .17       0
    4509    .015       0  5792.1     .17       0
#XS Ineff= 2 , 0
       0  4148.5  296.09               0
Permanent Ineff=
       F       F
Bank Sta=4509,5792.1
XS Rating Curve= 0 ,0
Exp/Cntr=0.3,0.1

Type RM Length L Ch R = 1 ,7475    ,570,570,570
BEGIN DESCRIPTION:
PRAIRIE BRANCH 15.0
END DESCRIPTION:
XS GIS Cut Line= 4
      3806702.97     10218161.01      3806134.27     10218468.48
      3805610.92     10218784.88      3805103.99     10218743.21
#Sta/Elev= 30
  4353.5  300.55  4468.3  296.68  4495.9  294.84  4550.1  293.09  4618.5  289.38
    4632  289.04  4659.5  286.59  4666.3  287.25    4689  286.19  4697.6  286.63
  4703.3  285.01  4719.5  288.26  4725.2  287.67  4734.5  288.64  4757.2  286.34
  4763.3  285.34  4785.1   284.7  5451.5  285.17  5555.6  284.51  5556.1  284.01
  5895.6  284.72  5925.7  285.06  5945.7   286.8  5955.8  287.76    5962  289.09
    5967  288.78  5995.9  290.76    6026  293.89  6046.1  294.16  6120.2  300.12
#Mann= 4 ,-1 , 0
  4353.5     .17       0  4618.5     .11       0  4757.2    .015       0
  5945.7     .11       0
Bank Sta=4757.2,5945.7
XS Rating Curve= 0 ,0
Exp/Cntr=0.3,0.1

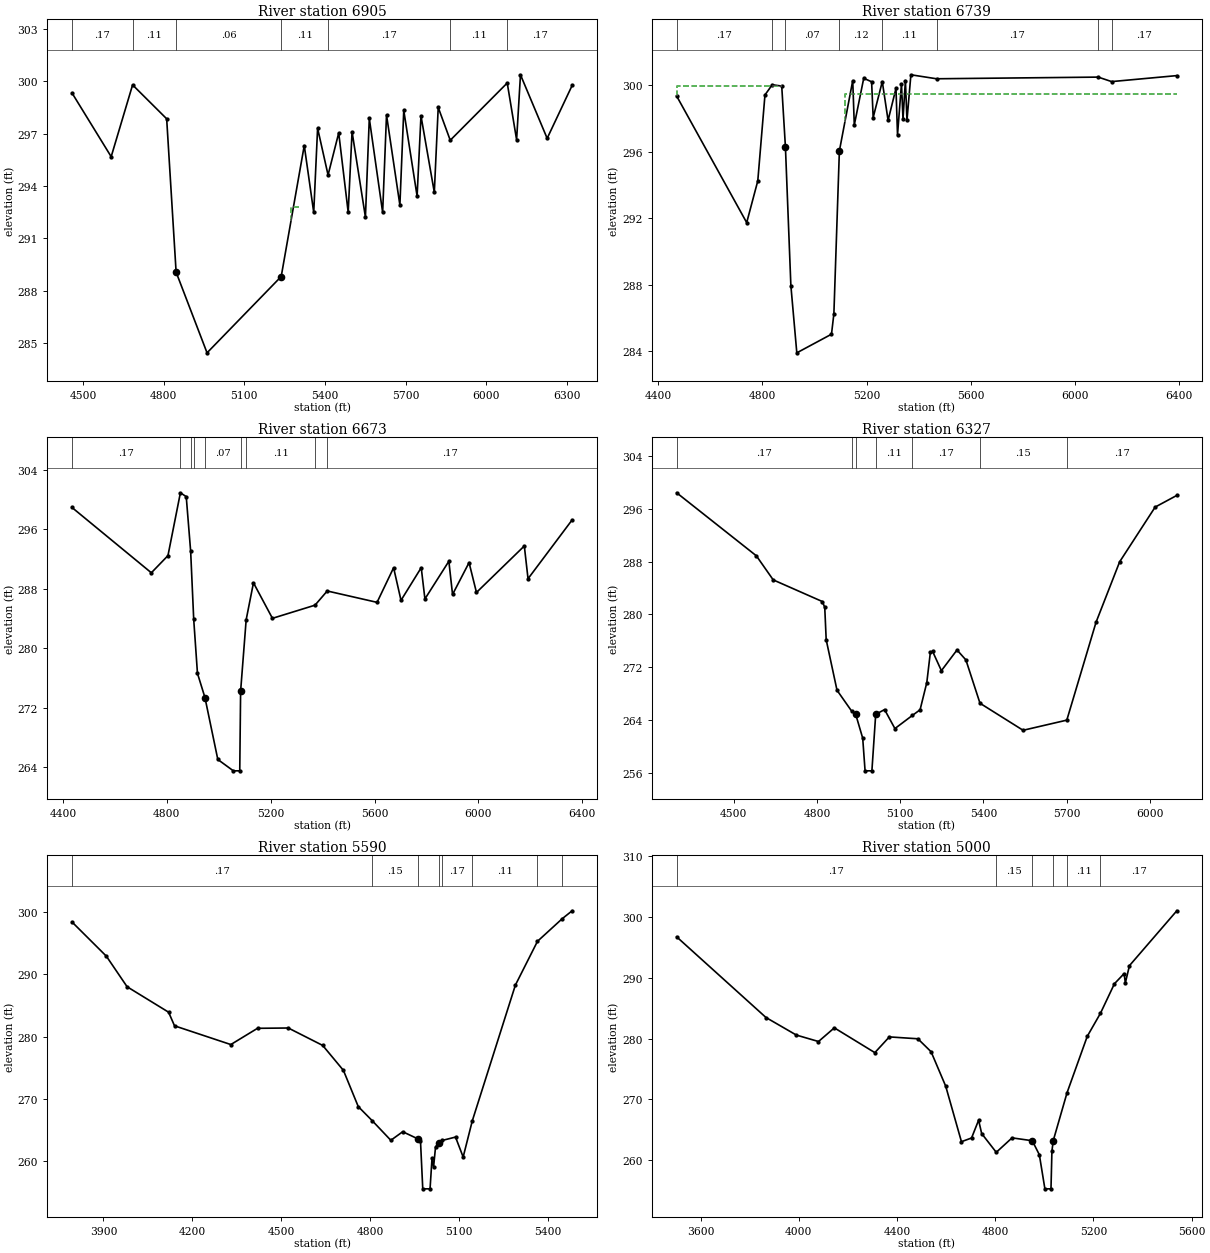
Type RM Length L Ch R = 1 ,6905    ,166,166,166
BEGIN DESCRIPTION:
PRAIRIE BRANCH 13.5
END DESCRIPTION:
XS GIS Cut Line= 3
      3806515.93     10217493.33      3806163.28     10217902.94
       3805132.6     10218725.86
#Sta/Elev= 30
  4459.5  299.33  4605.2  295.68  4684.8  299.79  4811.5  297.85  4846.6  289.07
  4961.6  284.45  5237.3  288.82    5323  296.32  5358.2  292.49  5372.6  297.31
  5411.5  294.63  5451.1  297.04  5486.3   292.5  5500.7  297.11  5550.4  292.22
  5564.8  297.87  5614.4  292.49  5628.8  298.07  5678.5  292.91  5692.9  298.33
  5742.5  293.42  5756.9  298.02  5806.5  293.64    5821   298.5  5865.7  296.62
  6077.6   299.9  6112.4  296.65  6126.8  300.37    6226  296.73  6318.9  299.76
#Mann= 7 ,-1 , 0
  4459.5     .17       0  4684.8     .11       0  4846.6     .06       0
  5237.3     .11       0  5411.5     .17       0  5865.7     .11       0
  6077.6     .17       0
#XS Ineff= 3 ,-1
  5273.4  5308.6  292.81  5308.6    5323  295.01    5323  5998.7  296.32
Permanent Ineff=
       F       F       F
Bank Sta=4846.6,5237.3
XS Rating Curve= 0 ,0
Exp/Cntr=0.3,0.1

Type RM Length L Ch R = 1 ,6739    ,66,66,66
BEGIN DESCRIPTION:
PRAIRIE BRANCH 14.0
END DESCRIPTION:
XS GIS Cut Line= 4
      3806500.31     10217394.08      3806105.49     10217746.91
      3805881.84     10218090.67      3805125.06     10218715.65
#Sta/Elev= 30
  4470.5  299.35  4739.5  291.74  4782.1  294.25  4809.7  299.42  4837.7  300.03
  4874.1  299.95  4888.3  296.28  4909.2  287.95    4932  283.91  5065.2  285.03
  5074.4  286.26  5095.5  296.05  5146.8  300.28  5152.8  297.61    5189  300.42
  5219.3  300.21  5225.3  298.06  5260.3  300.22  5282.6  297.89  5312.9  299.81
  5318.8  297.01    5334  300.09  5339.9  297.96  5349.1  300.28  5355.1  297.89
  5370.2  300.63  5468.7  300.39  6089.7  300.49  6141.2  300.22  6391.6  300.58
#Mann= 8 ,-1 , 0
  4470.5     .17       0  4837.7     .11       0  4888.3     .07       0
  5095.5     .12       0  5260.3     .11       0  5468.7     .17       0
  6089.7     .11       0  6141.2     .17       0
#XS Ineff= 2 , 0
       0  4874.1  299.95  5116.6       0  299.49
Permanent Ineff=
       F       F
Bank Sta=4888.3,5095.5
XS Rating Curve= 0 ,0
Exp/Cntr=0.3,0.1

Type RM Length L Ch R = 1 ,6673    ,346,346,346
BEGIN DESCRIPTION:
PRAIRIE BRANCH 13.0
END DESCRIPTION:
XS GIS Cut Line= 4
      3806487.62     10217361.73      3806047.25     10217716.35
      3805846.51     10218053.43      3805113.91     10218686.87
#Sta/Elev= 30
  4434.6  298.96  4740.2  290.17  4804.2  292.48  4852.1  300.94  4874.6  300.42
  4891.6  293.07  4903.4  283.89  4917.8  276.64  4946.6  273.38  4996.2  265.04
  5056.1  263.51  5080.7  263.51    5084  274.23  5105.4  283.85  5133.5  288.82
  5206.6  284.04  5370.5  285.81  5417.6  287.72  5609.5  286.19  5673.2  290.85
  5701.7  286.46  5779.6  290.86  5793.8  286.65    5886  291.72  5900.2  287.25
  5963.8  291.54  5992.3  287.52  6176.6  293.78  6190.9  289.37  6360.8  297.29
#Mann= 9 ,-1 , 0
  4434.6     .17       0  4852.1     .11       0  4891.6     .17       0
  4903.4     .11       0  4946.6     .07       0    5084     .11       0
  5105.4     .11       0  5370.5     .11       0  5417.6     .17       0
Bank Sta=4946.6,5084
XS Rating Curve= 0 ,0
Exp/Cntr=0.3,0.1

Type RM Length L Ch R = 1 ,6327    ,737,737,737
BEGIN DESCRIPTION:
PRAIRIE BRANCH 12.0
END DESCRIPTION:
XS GIS Cut Line= 3
       3806462.2      10217337.7      3805784.22     10217532.48
      3804740.95     10217870.95
#Sta/Elev= 30
  4294.6  298.44  4581.8  288.88  4642.5  285.23  4819.3  281.95  4828.2  281.07
  4833.4  276.15  4872.4  268.49  4924.6  265.36  4939.8  264.83    4965  261.22
  4973.5  256.27  4998.1  256.27  5011.8  264.84  5043.8  265.56    5081  262.68
  5143.8  264.67  5171.7  265.53  5195.9  269.65  5208.9  274.29    5217  274.37
  5248.5  271.46  5304.8   274.6  5336.8  273.09  5387.6  266.52  5542.9  262.42
  5700.4  263.96  5805.7   278.8  5890.8  287.97  6018.7  296.27  6096.8  298.04
#Mann= 7 ,-1 , 0
  4294.6     .17       0  4924.6     .15       0  4939.8     .07       0
  5011.8     .11       0  5143.8     .17       0  5387.6     .15       0
  5700.4     .17       0
#XS Ineff= 2 , 0
       0                    5217       0  274.37
Permanent Ineff=
       F       F
Bank Sta=4939.8,5011.8
XS Rating Curve= 0 ,0
Exp/Cntr=0.3,0.1

Type RM Length L Ch R = 1 ,5590    ,590,590,590
BEGIN DESCRIPTION:
PRAIRIE BRANCH 11.0
END DESCRIPTION:
XS GIS Cut Line= 3
      3806483.85     10217281.27      3805278.37     10217239.59
      3804812.93     10217112.02
#Sta/Elev= 30
  3793.8  298.42  3909.9  292.92  3979.9  288.01    4120  283.92    4140  281.73
  4330.1  278.72  4420.2  281.33  4524.2  281.38  4640.3  278.58  4710.3  274.57
  4760.4  268.75  4807.4  266.49  4870.4  263.33  4910.5  264.71  4960.5  263.59
  4970.5  263.26  4978.2  255.53  5002.8  255.53  5009.5  260.46  5014.7  259.03
  5021.3  262.24  5031.6  262.96  5044.1  263.31  5088.8  263.85  5114.6  260.64
  5145.4  266.45  5290.9  288.27  5365.5  295.31  5449.2  298.95  5482.6  300.22
#Mann= 8 ,-1 , 0
  3793.8     .17       0  4807.4     .15       0  4960.5     .09       0
  5031.6     .15       0  5044.1     .17       0  5145.4     .11       0
  5365.5     .17       0  5449.2     .11       0
Bank Sta=4960.5,5031.6
XS Rating Curve= 0 ,0
Exp/Cntr=0.3,0.1

Type RM Length L Ch R = 1 ,5000    ,352,352,352
BEGIN DESCRIPTION:
PRAIRIE BRANCH 10.0
END DESCRIPTION:
XS GIS Cut Line= 3
      3806700.88     10217046.89      3805248.26     10216683.44
      3804718.45     10216786.28
#Sta/Elev= 30
  3502.6  296.75  3866.5  283.47  3990.2  280.58  4080.3  279.52  4144.8  281.77
  4309.8  277.69  4368.8  280.28    4485  279.97  4538.8  277.84  4598.4  272.17
  4662.5  263.03  4703.7  263.64  4732.4  266.57  4744.9  264.37  4804.3  261.28
  4868.6  263.66    4951  263.19  4979.8  260.88  5002.4  255.27  5027.2  255.27
    5031  261.47 5036.38   263.2  5092.7   271.1    5175  280.38  5228.7  284.17
  5285.6  289.03    5325   290.7  5330.1  289.18  5346.8  292.01  5539.7  301.04
#Mann= 6 ,-1 , 0
  3502.6     .17       0  4804.3     .15       0    4951     .09       0
 5036.38     .15       0  5092.7     .11       0  5228.7     .17       0
Bank Sta=4951,5036.38
XS Rating Curve= 0 ,0
Exp/Cntr=0.3,0.1