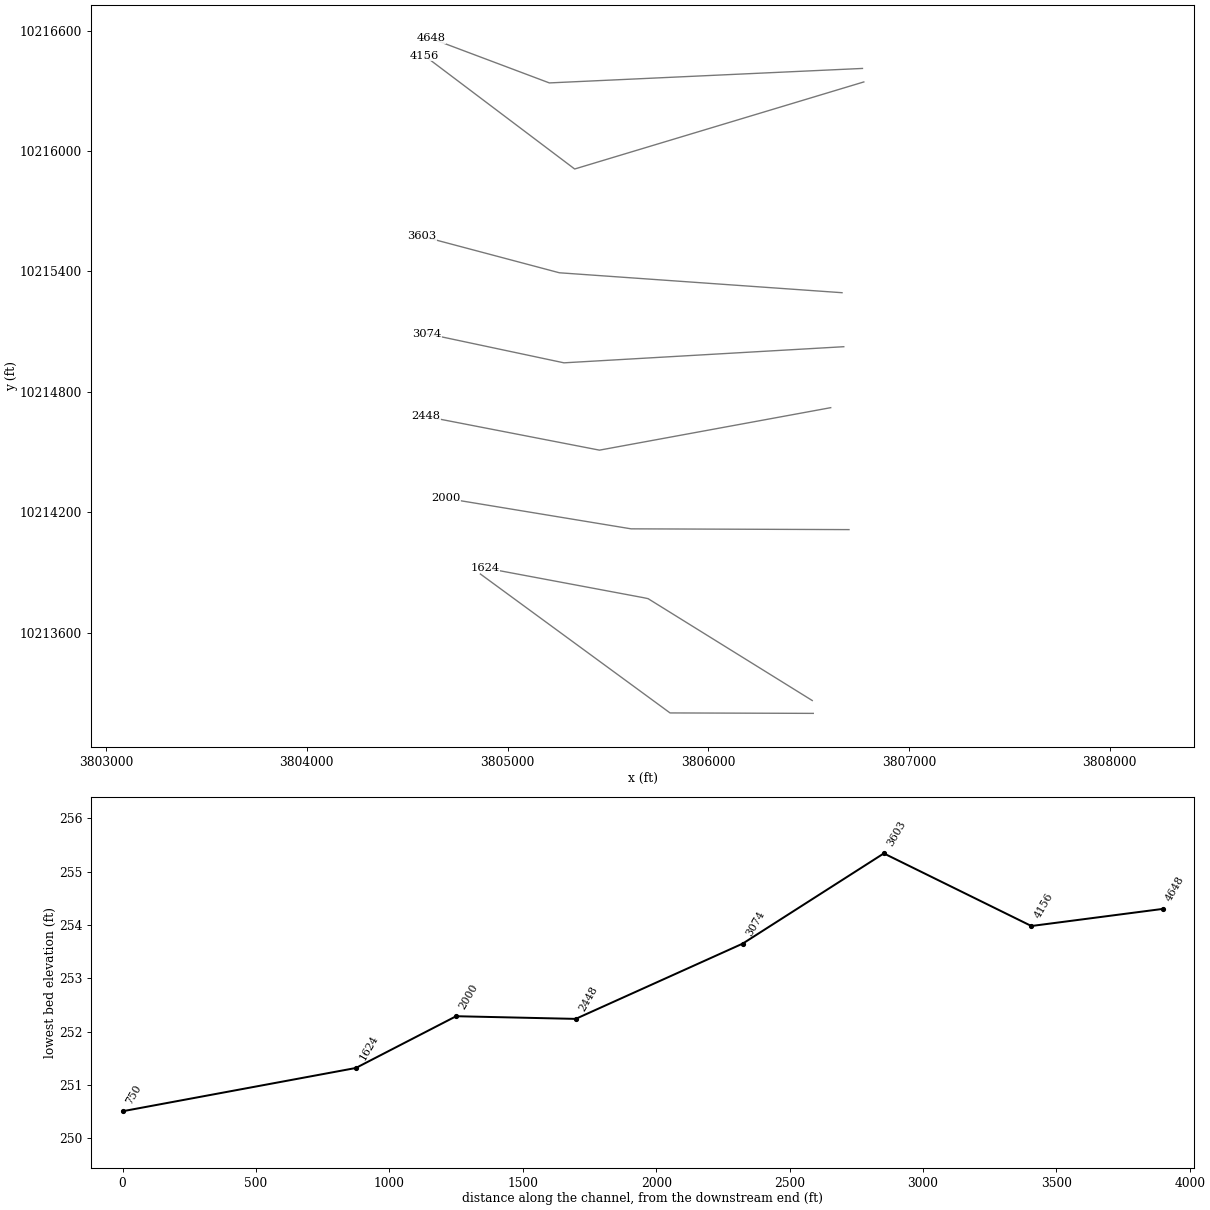
HEC-RAS study PRAIRIE BRANCH.prj: PRAIRIE BRANCH Base Level Engineering

--- PRAIRIE BRANCH.g01 (geometry) --- (continued)

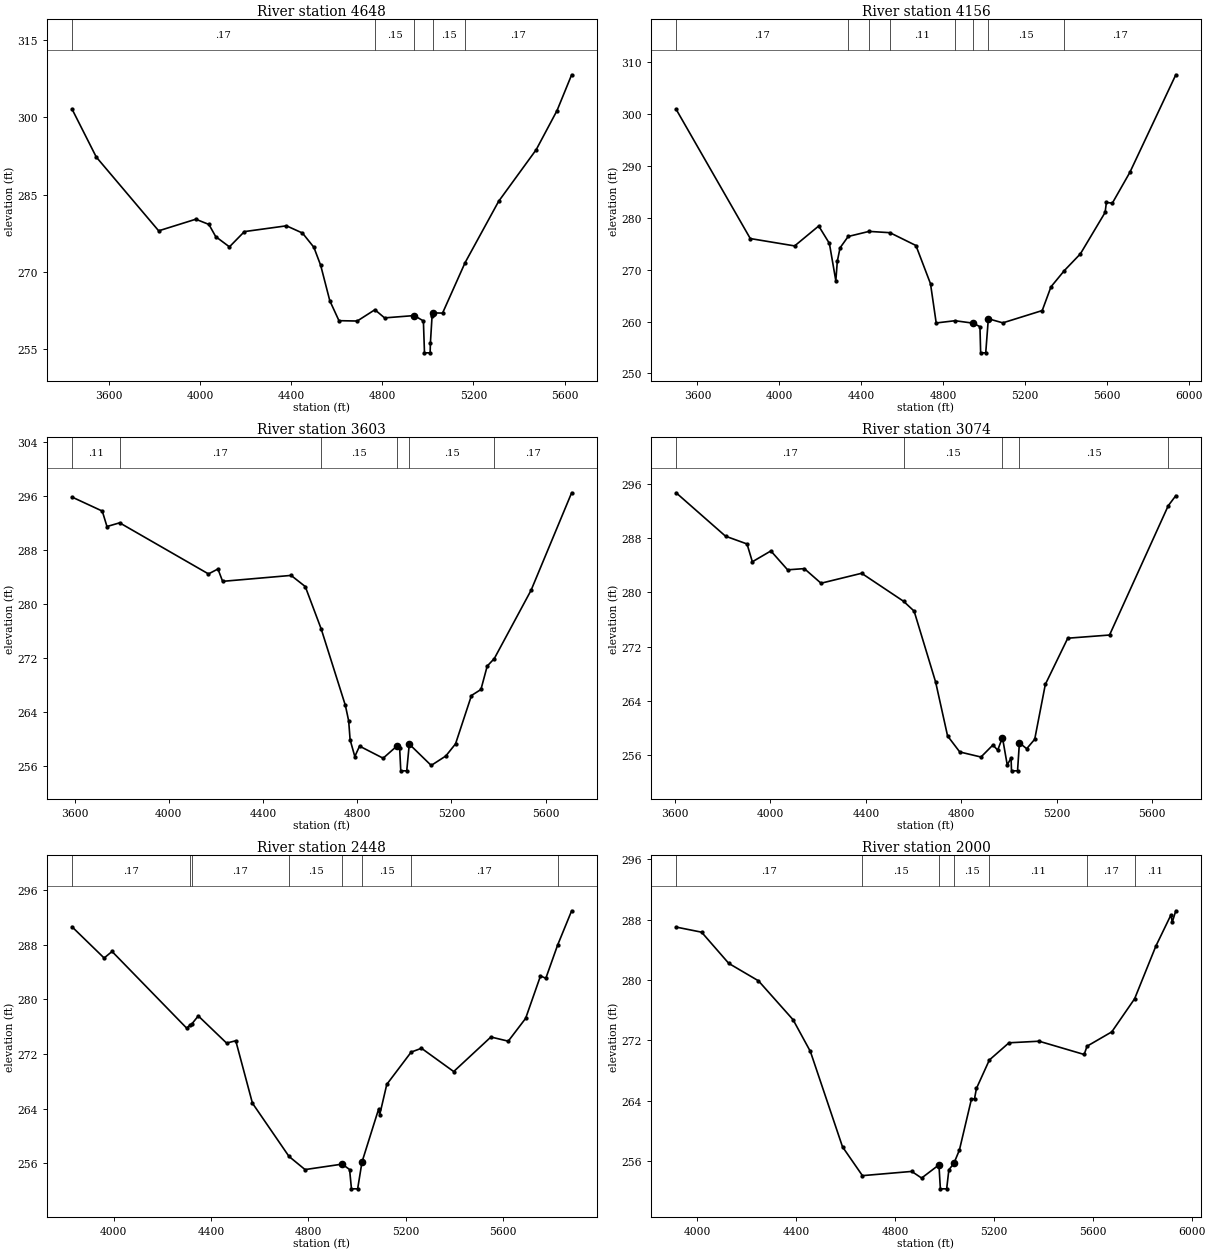
Type RM Length L Ch R = 1 ,4648    ,492,492,492
BEGIN DESCRIPTION:
PRAIRIE BRANCH 9.0
END DESCRIPTION:
XS GIS Cut Line= 3
      3806767.89     10216411.07      3805208.36      10216338.9
      3804617.87     10216561.07
#Sta/Elev= 30
  3438.8  301.61  3545.5  292.28  3819.2  277.97    3982  280.22  4039.5  279.21
  4069.5  276.84  4129.6  274.86  4195.3  277.82  4379.8  278.94  4449.9  277.54
    4500  274.78    4530  271.26    4570   264.4  4610.1  260.54  4690.2  260.47
  4767.7  262.66  4810.3  261.08  4940.4  261.53  4980.5  260.49  4985.3   254.3
  5010.1   254.3  5011.2  256.17  5018.5  261.38  5023.8  262.05  5064.6  262.01
  5163.5   271.8  5310.4  283.68  5475.4  293.71  5566.8   301.3  5630.9  308.24
#Mann= 5 ,-1 , 0
  3438.8     .17       0  4767.7     .15       0  4940.4     .09       0
  5023.8     .15       0  5163.5     .17       0
Bank Sta=4940.4,5023.8
XS Rating Curve= 0 ,0
Exp/Cntr=0.3,0.1

Type RM Length L Ch R = 1 ,4156    ,553,553,553
BEGIN DESCRIPTION:
PRAIRIE BRANCH 8.0
END DESCRIPTION:
XS GIS Cut Line= 3
      3806774.66     10216343.77      3805334.48     10215909.95
      3804587.16     10216474.01
#Sta/Elev= 30
  3495.9  300.93  3858.1  276.01  4074.8  274.59  4192.3  278.43  4244.5  275.07
  4275.9  267.88  4283.2  271.65  4296.7  274.23  4336.3  276.41  4438.2  277.39
  4540.2  277.14  4667.1  274.67  4738.3   267.3  4766.1  259.74  4857.8  260.17
  4946.8   259.7  4979.8  259.02  4983.2  253.98    5008  253.98  5020.7  260.55
  5091.5  259.76  5283.9  262.13  5326.7  266.71  5392.3  269.85  5470.3  273.06
    5591  281.04  5597.3  282.97  5626.4  282.84  5711.8  288.76  5936.3  307.58
#Mann= 8 ,-1 , 0
  3495.9     .17       0  4336.3     .11       0  4438.2     .17       0
  4540.2     .11       0  4857.8     .15       0  4946.8     .09       0
  5020.7     .15       0  5392.3     .17       0
#XS Ineff= 2 , 0
       0  4738.3   267.3  5347.5       0  267.29
Permanent Ineff=
       F       F
Bank Sta=4946.8,5020.7
XS Rating Curve= 0 ,0
Exp/Cntr=0.3,0.1

Type RM Length L Ch R = 1 ,3603    ,529,529,529
BEGIN DESCRIPTION:
PRAIRIE BRANCH 7.0
END DESCRIPTION:
XS GIS Cut Line= 3
       3806666.2     10215293.43       3805258.3     10215392.76
       3804571.3     10215575.16
#Sta/Elev= 30
  3588.6   295.9  3717.3  293.82  3737.3  291.53  3791.1  292.08  4168.4  284.51
  4208.5  285.24  4228.5  283.41  4519.3  284.29  4579.4  282.64  4647.3  276.34
  4749.8  265.03  4763.8  262.74  4769.9  259.94  4789.9  257.46    4810     259
  4910.2  257.21  4970.4  259.07  4980.4  258.67  4985.1  255.34  5010.4  255.34
  5021.2   259.3  5114.3  256.14  5176.4  257.54  5217.7  259.34  5285.3   266.5
  5325.5  267.39  5352.2  270.86  5382.3  271.97  5538.5  282.09  5710.8  296.53
#Mann= 6 ,-1 , 0
  3588.6     .11       0  3791.1     .17       0  4647.3     .15       0
  4970.4     .09       0  5021.2     .15       0  5382.3     .17       0
#XS Ineff= 2 , 0
       0                  5285.3       0   266.5
Permanent Ineff=
       F       F
Bank Sta=4970.4,5021.2
XS Rating Curve= 0 ,0
Exp/Cntr=0.3,0.1

Type RM Length L Ch R = 1 ,3074    ,626,626,626
BEGIN DESCRIPTION:
PRAIRIE BRANCH 6.0
END DESCRIPTION:
XS GIS Cut Line= 3
      3806674.83     10215024.33      3805281.14     10214943.98
      3804595.91     10215089.43
#Sta/Elev= 30
    3604  294.72  3811.3  288.31  3901.5  287.16  3923.9  284.53  4001.6  286.13
  4071.8  283.34  4141.9  283.52    4212  281.36  4382.3  282.83  4558.1   278.7
  4602.6  277.24  4692.8  266.77  4742.9  258.81    4794  256.44  4883.1  255.69
  4933.2  257.47  4953.2   256.7  4973.2  258.57  4993.3  254.52  5009.3  255.55
  5011.2  253.65  5036.5  253.65  5044.3  257.78  5074.9  256.92  5108.5  258.31
  5153.1  266.42  5247.2  273.24  5422.5  273.71  5668.8  292.81  5700.5  294.29
#Mann= 5 ,-1 , 0
    3604     .17       0  4558.1     .15       0  4973.2     .09       0
  5044.3     .15       0  5668.8     .11       0
Bank Sta=4973.2,5044.3
XS Rating Curve= 0 ,0
Exp/Cntr=0.3,0.1

Type RM Length L Ch R = 1 ,2448    ,448,448,448
BEGIN DESCRIPTION:
PRAIRIE BRANCH 5.0
END DESCRIPTION:
XS GIS Cut Line= 3
      3806609.81     10214720.52        3805458.     10214508.85
      3804592.17     10214676.99
#Sta/Elev= 30
  3828.9  290.63  3961.1  286.05  3993.6  287.01  4299.9  275.79  4315.7  276.26
  4321.2  276.38  4347.9  277.57  4464.2  273.59  4501.9  273.93  4570.4  264.79
  4720.6  256.99  4786.6  255.06  4939.1  255.86  4969.6  255.07  4977.3  252.24
  5002.7  252.24  5020.5  256.16  5088.5  263.88  5093.6  263.12  5122.4  267.54
  5222.6  272.27    5265  272.83  5397.4  269.42  5550.2  274.48  5621.5  273.87
  5692.9  277.21    5754  283.43  5775.9  283.08  5824.2  287.93    5882  292.97
#Mann= 8 ,-1 , 0
  3828.9     .17       0  4315.7     .11       0  4321.2     .17       0
  4720.6     .15       0  4939.1     .09       0  5020.5     .15       0
  5222.6     .17       0  5824.2     .11       0
#XS Ineff= 2 , 0
       0                  5088.5       0  263.88
Permanent Ineff=
       F       F
Bank Sta=4939.1,5020.5
XS Rating Curve= 0 ,0
Exp/Cntr=0.3,0.1

Type RM Length L Ch R = 1 ,2000    ,376,376,376
BEGIN DESCRIPTION:
PRAIRIE BRANCH 4.0
END DESCRIPTION:
XS GIS Cut Line= 3
      3806700.91     10214112.87      3805615.51     10214116.69
      3804692.09       10214269.
#Sta/Elev= 30
  3914.6  287.01  4017.7  286.33  4127.7  282.19  4247.7  279.88  4387.7  274.72
  4457.7  270.51  4587.7  257.86  4668.3  254.04  4867.7   254.6  4907.7  253.72
  4977.7  255.47  4983.6  252.29    5009  252.29  5017.9  254.81  5038.2  255.67
  5060.6  257.44  5109.1  264.17  5121.7  264.24  5129.4   265.6  5181.7  269.38
  5261.1  271.66  5382.8  271.87  5565.2  270.11  5576.9  271.21  5676.9  273.11
  5769.3   277.5  5855.2  284.48  5916.4  288.63  5921.4  287.65  5935.9  289.17
#Mann= 7 ,-1 , 0
  3914.6     .17       0  4668.3     .15       0  4977.7     .09       0
  5038.2     .15       0  5181.7     .11       0  5576.9     .17       0
  5769.3     .11       0
Bank Sta=4977.7,5038.2
XS Rating Curve= 0 ,0
Exp/Cntr=0.3,0.1

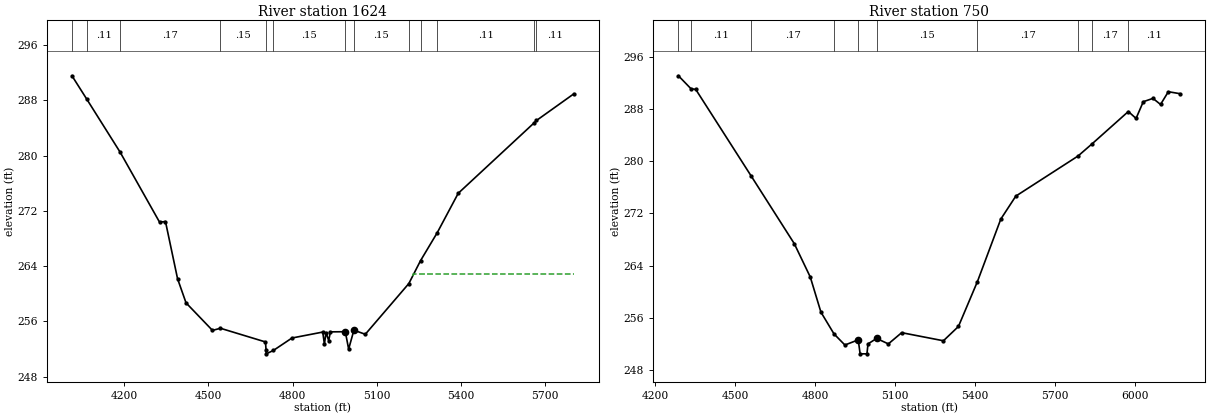
Type RM Length L Ch R = 1 ,1624    ,874,874,874
BEGIN DESCRIPTION:
PRAIRIE BRANCH 3.0
END DESCRIPTION:
XS GIS Cut Line= 4
      3806517.87     10213261.06      3805700.22     10213768.73
       3805676.2     10213773.86      3804886.66      10213921.9
#Sta/Elev= 30
    4013  291.55  4066.6  288.12  4185.1  280.48  4325.4  270.38  4346.6  270.46
  4389.7  262.19  4419.9   258.7  4514.3  254.71  4542.7  255.02  4703.3  253.04
  4705.5  251.82    4706  251.32  4731.9  251.82  4797.8  253.61  4907.6  254.47
  4913.5  252.74  4919.4  254.39  4928.9  253.23  4934.8   254.5  4988.1  254.52
    5000  252.01  5018.7  254.74  5059.4  254.15  5214.7  261.49  5256.4   264.8
  5315.9  268.84  5390.9  274.55  5660.6   284.7  5669.9  285.08  5803.3  288.94
#Mann= 13 ,-1 , 0
    4013     .17       0  4066.6     .11       0  4185.1     .17       0
  4542.7     .15       0  4705.5     .12       0  4731.9     .15       0
  4988.1     .09       0  5018.7     .15       0  5214.7     .11       0
  5256.4     .17       0  5315.9     .11       0  5660.6     .17       0
  5669.9     .11       0
#XS Ineff= 2 , 0
       0                  5228.1       0  262.94
Permanent Ineff=
       F       F
Bank Sta=4988.1,5018.7
XS Rating Curve= 0 ,0
Exp/Cntr=0.3,0.1

Type RM Length L Ch R = 1 ,750     ,0,0,0
BEGIN DESCRIPTION:
PRAIRIE BRANCH 1.0
END DESCRIPTION:
XS GIS Cut Line= 3
      3806522.98     10213197.07      3805809.58     10213199.28
      3804864.98     10213891.52
#Sta/Elev= 30
  4286.6  293.07  4333.7  291.09  4351.7  290.98  4559.3  277.76  4721.7  267.37
  4781.7  262.27  4821.7  256.89  4870.8  253.56  4911.7  251.86  4961.7  252.65
  4968.9  250.51  4994.5  250.51  4998.4  252.03  5030.8  252.87  5074.8  252.03
  5124.9  253.75  5281.6  252.51    5338   254.7  5409.4  261.58    5497  271.13
  5553.4  274.65  5787.1  280.79  5839.7  282.65  5975.9   287.6  6004.9  286.54
    6032   289.1  6068.4  289.61  6096.8  288.68  6126.1  290.63  6171.1  290.32
#Mann= 10 ,-1 , 0
  4286.6     .17       0  4333.7     .11       0  4559.3     .17       0
  4870.8     .15       0  4961.7     .09       0  5030.8     .15       0
  5409.4     .17       0  5787.1     .11       0  5839.7     .17       0
  5975.9     .11       0
Bank Sta=4961.7,5030.8
XS Rating Curve= 0 ,0
Exp/Cntr=0.3,0.1

Chan Stop Cuts=-1
Use User Specified Reach Order=0
Composite Channel Slope=5