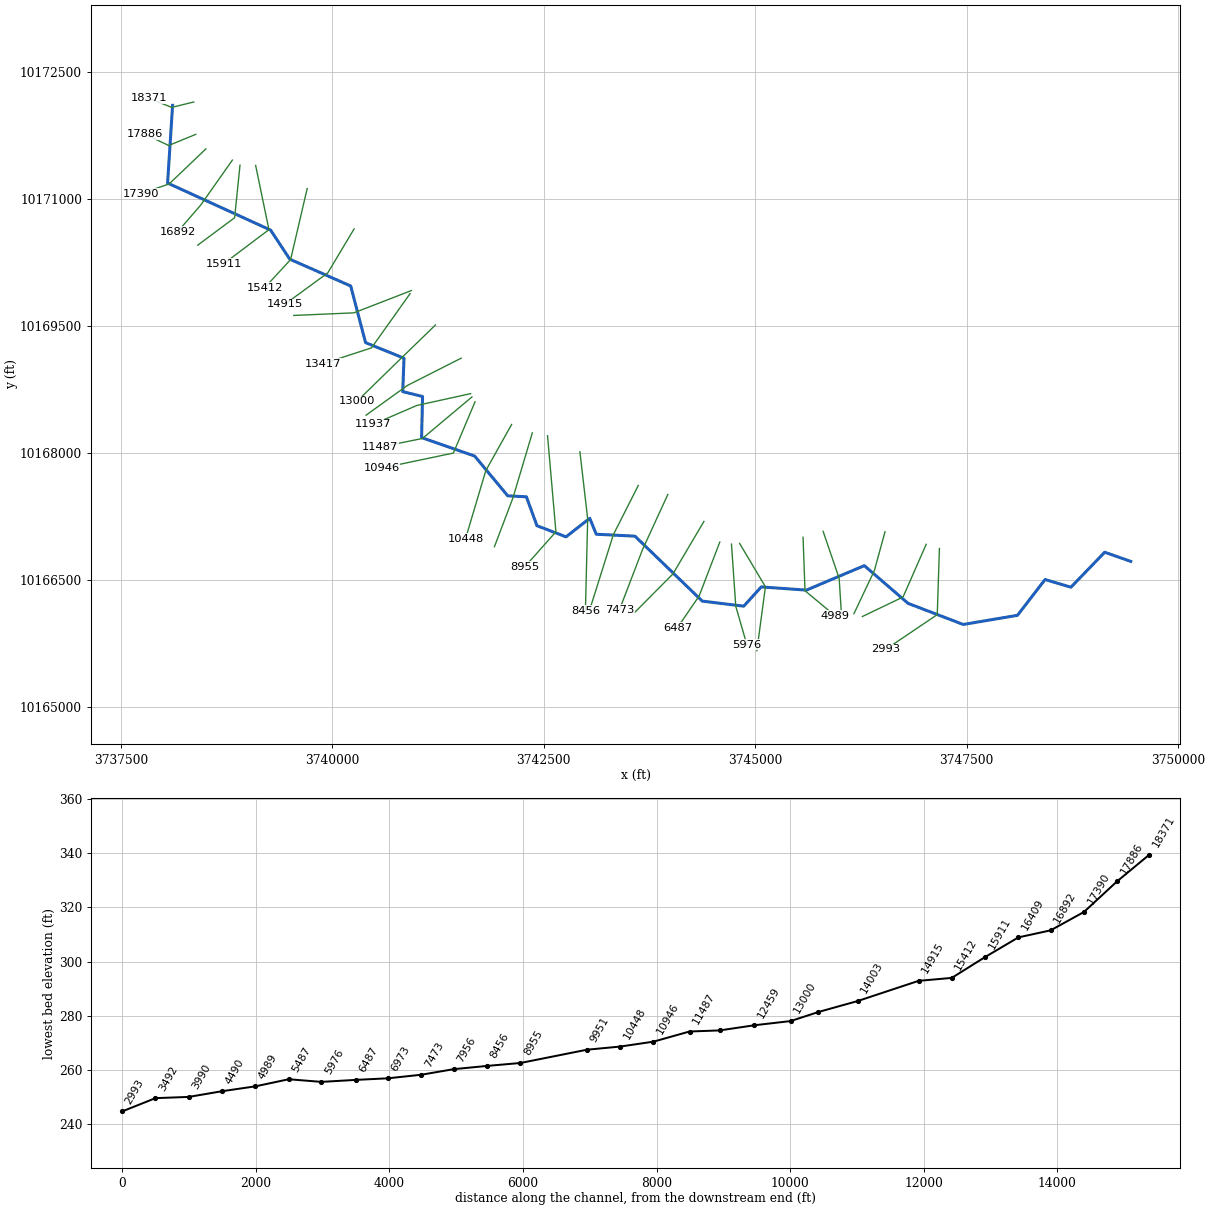
--- SAND BRANCH NO 2.prj (project) ---

Proj Title=SAND BRANCH NO 2 Base Level Engineering
Current Plan=p01
Default Exp/Contr=0.3,0.1
English Units
Geom File=g01
Flow File=f01
Plan File=p01
Y Axis Title=Elevation
X Axis Title(PF)=Main Channel Distance
X Axis Title(XS)=Station
BEGIN DESCRIPTION:
SAND BRANCH NO 2
END DESCRIPTION:
DSS Export Rating Curves= 0
DSS Export Rating Curve Sorted= 0
DSS Export Volume Flow Curves= 0
DXF OffsetX= 0
DXF OffsetY= 0
DXF ScaleX= 1
DXF ScaleY= 10

--- SAND BRANCH NO 2.p01 (plan) ---

Plan Title=Multiple Run
Short Identifier=Multiple
Geom File=g01
Flow File=f01
Subcritical Flow
K Sum by GR= 0
Std Step Tol= 0.01
Critical Tol= 0.01
Num of Std Step Trials= 20
Max Error Tol= 0.3
Flow Tol Ratio= 0.001
Split Flow NTrial= 30
Split Flow Tol= 0.02
Split Flow Ratio= 0.02
Log Output Level= 0
Friction Slope Method= 1
Unsteady Friction Slope Method= 2
Unsteady Bridges Friction Slope Method= 1
Parabolic Critical Depth
Global Vel Dist=  1 , 1 , 1
Global Log Level= 0
CheckData=True
Encroach Param= -1, 0, 0, 0
BEGIN DESCRIPTION:
Multiple Run
END DESCRIPTION:

--- SAND BRANCH NO 2.f01 (steady flow) ---

Flow Title=Multiple
Program Version=4.10
Number of Profiles= 7
Profile Names=10-year,25-year,50-year,1pct_min,100-year,1pct_plu,500-year
River Rch & RM=SAND BRANCH NO 2,Reach-1         ,18371
     192     243     315     135     408    1232     703
River Rch & RM=SAND BRANCH NO 2,Reach-1         ,15911
     804    1111    1521     686    2071    6254    3966
River Rch & RM=SAND BRANCH NO 2,Reach-1         ,8955
     988    1363    1863     836    2526    7628    4804
Boundary for River Rch & Prof#=SAND BRANCH NO 2,Reach-1         , 1
Up Type= 0
Dn Type= 3
Dn Slope=0.009
Boundary for River Rch & Prof#=SAND BRANCH NO 2,Reach-1         , 2
Up Type= 0
Dn Type= 3
Dn Slope=0.009
Boundary for River Rch & Prof#=SAND BRANCH NO 2,Reach-1         , 3
Up Type= 0
Dn Type= 3
Dn Slope=0.009
Boundary for River Rch & Prof#=SAND BRANCH NO 2,Reach-1         , 4
Up Type= 0
Dn Type= 3
Dn Slope=0.009
Boundary for River Rch & Prof#=SAND BRANCH NO 2,Reach-1         , 5
Up Type= 0
Dn Type= 3
Dn Slope=0.009
Boundary for River Rch & Prof#=SAND BRANCH NO 2,Reach-1         , 6
Up Type= 0
Dn Type= 3
Dn Slope=0.009
Boundary for River Rch & Prof#=SAND BRANCH NO 2,Reach-1         , 7
Up Type= 0
Dn Type= 3
Dn Slope=0.009
DSS Import GetInterval= 0
DSS Import GetPeak= 0
DSS Import FillOption= 0

--- SAND BRANCH NO 2.g01 (geometry) ---

Geom Title=Existing Conditions
Program Version=4.10

River Reach=SAND BRANCH NO 2,Reach-1
Reach XY= 30
      3738111.15     10172108.91      3738051.85     10171189.98
       3739269.8      10170633.6      3739496.64     10170289.83
      3740216.59      10169973.1      3740392.16     10169303.71
      3740846.79     10169118.81      3740831.65     10168723.84
      3741066.28      10168666.7      3741054.64     10168180.62
      3741682.13     10167962.25       3742073.3     10167492.22
       3742293.7     10167480.63      3742418.42     10167139.01
      3742762.04     10167007.32      3743042.23     10167226.58
      3743119.86     10167038.26      3743577.37     10167015.17
      3744372.42      10166247.6      3744863.06     10166187.59
      3745069.82     10166415.27      3745604.13     10166377.57
      3746288.22     10166666.92       3746805.9     10166220.59
      3747457.64     10165971.32      3748099.08     10166079.46
      3748425.09     10166502.78      3748730.95     10166411.76
      3749129.88     10166825.34      3749438.23     10166716.84

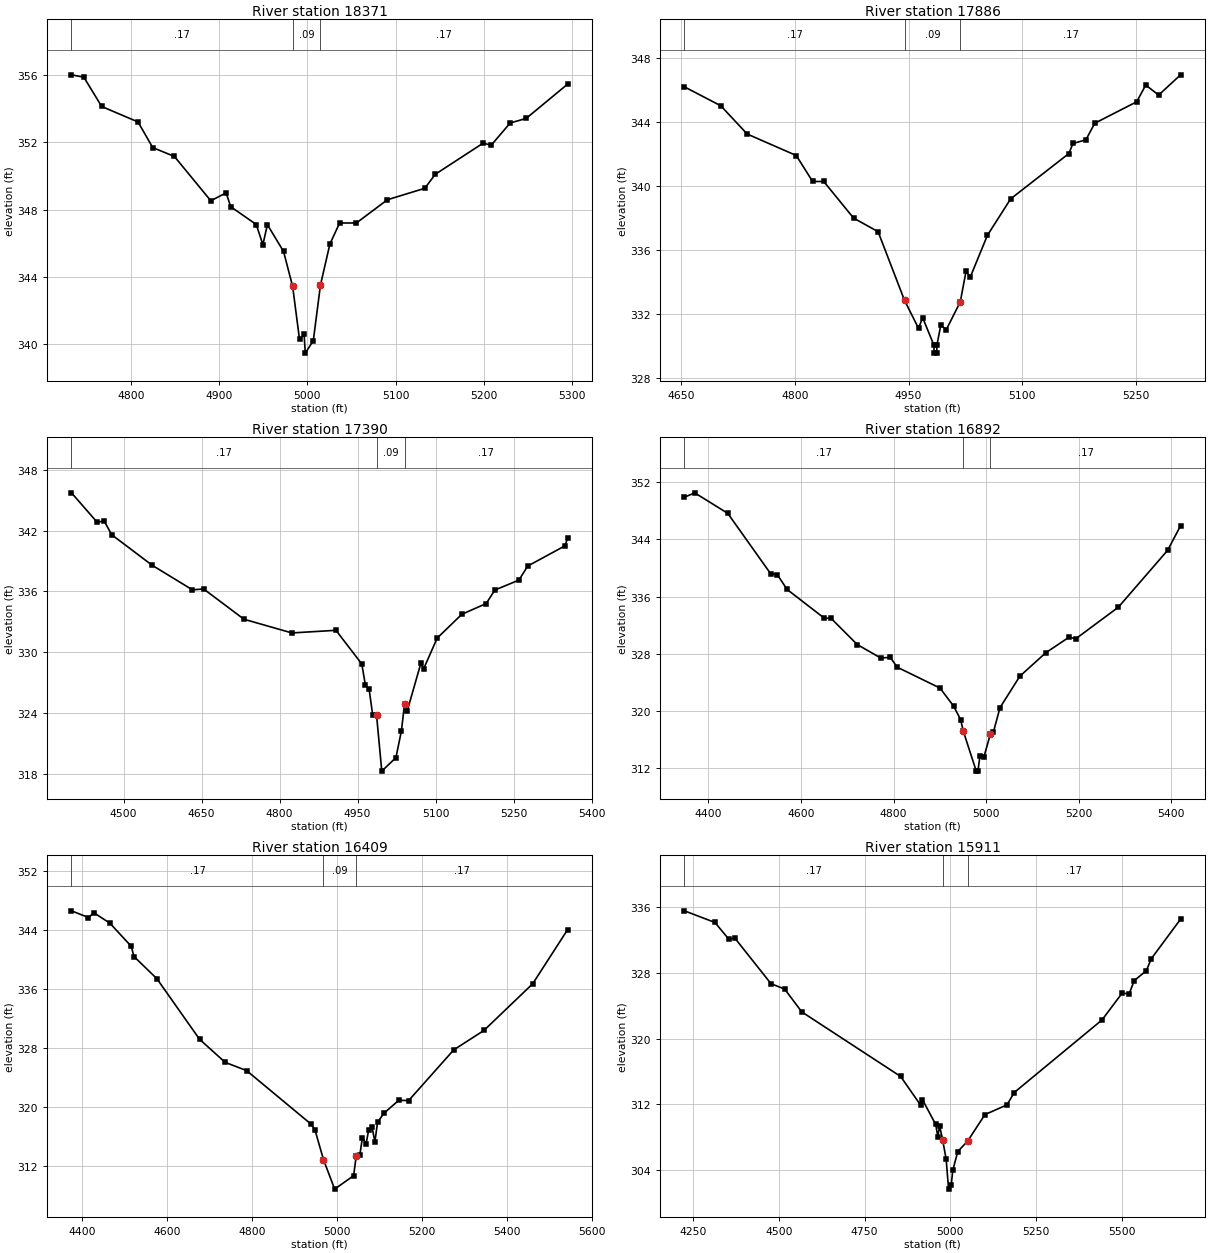
Type RM Length L Ch R = 1 ,18371   ,485,485,485
BEGIN DESCRIPTION:
SAND BRANCH NO 2 35.0
END DESCRIPTION:
XS GIS Cut Line= 3
       3738361.1     10172148.29       3738101.6     10172084.61
      3737827.27     10172192.55
#Sta/Elev= 30
  4732.8     356  4746.8  355.86    4767  354.12  4808.2   353.2  4824.8  351.68
  4849.4  351.15  4890.6  348.52    4908  348.99  4913.1  348.17  4942.1  347.11
  4949.6  345.91  4954.7   347.1    4973  345.51  4983.3  343.43  4991.1  340.28
  4996.3  340.58  4997.6  339.47  5006.7  340.21  5014.8  343.51  5025.5  345.95
  5036.5   347.2  5055.5   347.2  5090.6  348.58    5133  349.26  5144.8  350.09
    5199  351.94  5208.2  351.82  5229.7  353.14  5247.8  353.41  5294.8  355.45
#Mann= 3 , 0 , 0
  4732.8     .17       0  4983.3     .09       0  5014.8     .17       0
Bank Sta=4983.3,5014.8
XS Rating Curve= 0 ,0
Exp/Cntr=0.3,0.1

Type RM Length L Ch R = 1 ,17886   ,496,496,496
BEGIN DESCRIPTION:
SAND BRANCH NO 2 34.0
END DESCRIPTION:
XS GIS Cut Line= 3
      3738384.56     10171765.49      3738064.44     10171633.91
      3737785.55      10171768.1
#Sta/Elev= 30
  4653.9  346.18    4702     345  4736.8  343.24  4801.7   341.9  4823.3  340.28
    4838  340.28  4877.4     338  4909.8  337.15  4944.7  332.87  4963.2  331.13
  4968.7  331.79  4983.5  330.08  4983.8  329.58  4987.3  329.58  4987.5  330.08
  4992.6  331.31    5000  331.05  5018.4  332.78    5026  334.68  5031.6  334.32
  5054.2  336.92    5085   339.2  5161.8  342.02  5167.3  342.65  5184.4  342.88
    5196  343.91  5251.5  345.25  5263.4  346.29  5280.5  345.67  5309.5  346.93
#Mann= 3 , 0 , 0
  4653.9     .17       0  4944.7     .09       0  5018.4     .17       0
Bank Sta=4944.7,5018.4
XS Rating Curve= 0 ,0
Exp/Cntr=0.3,0.1

Type RM Length L Ch R = 1 ,17390   ,498,498,498
BEGIN DESCRIPTION:
SAND BRANCH NO 2 33.0
END DESCRIPTION:
XS GIS Cut Line= 3
      3738504.35     10171593.62      3738070.32     10171179.21
      3737735.18     10171065.53
#Sta/Elev= 30
  4399.9  345.73  4448.9  342.85    4463  342.93  4477.2   341.6  4554.9  338.59
  4632.5  336.16  4653.9  336.25  4731.6  333.26  4823.7  331.91  4908.4  332.17
  4958.1  328.85    4965  326.76  4972.2  326.36  4979.1  323.78  4986.4  323.83
  4996.5  318.28  5023.7  319.61  5034.3  322.26  5040.2  324.86  5045.5  324.23
  5071.6  328.91  5076.9  328.36    5103   331.4  5150.4  333.75  5197.3  334.81
  5213.8  336.14  5260.1  337.12  5277.2  338.51    5349  340.51  5353.9  341.31
#Mann= 3 , 0 , 0
  4399.9     .17       0  4986.4     .09       0  5040.2     .17       0
Bank Sta=4986.4,5040.2
XS Rating Curve= 0 ,0
Exp/Cntr=0.3,0.1

Type RM Length L Ch R = 1 ,16892   ,483,483,483
BEGIN DESCRIPTION:
SAND BRANCH NO 2 32.0
END DESCRIPTION:
XS GIS Cut Line= 3
      3738817.84     10171461.05      3738442.72     10170928.38
      3738167.86     10170611.08
#Sta/Elev= 30
  4348.5  349.92  4370.7  350.54  4442.1  347.66  4534.4  339.22  4549.2  339.05
  4570.2  336.99  4650.3  332.97  4665.1  332.94  4721.7  329.26  4772.2  327.38
  4793.1  327.46  4807.9  326.09  4900.3  323.16  4929.9  320.61  4944.7  318.75
  4950.8  317.08  4978.6  311.51  4982.1  311.51  4986.5   313.6  4995.2  313.52
  5009.1  316.71  5015.7  317.01  5029.9  320.42  5072.7  324.82  5128.7  328.11
  5179.1   330.3  5193.3  330.06  5285.4   334.5  5391.8  342.48  5419.8  345.93
#Mann= 3 , 0 , 0
  4348.5     .17       0  4950.8     .09       0  5009.1     .17       0
Bank Sta=4950.8,5009.1
XS Rating Curve= 0 ,0
Exp/Cntr=0.3,0.1

Type RM Length L Ch R = 1 ,16409   ,498,498,498
BEGIN DESCRIPTION:
SAND BRANCH NO 2 31.0
END DESCRIPTION:
XS GIS Cut Line= 3
      3738907.98     10171400.91      3738844.48     10170780.05
      3738408.28     10170455.81
#Sta/Elev= 30
  4375.9  346.61  4415.9   345.7  4428.6  346.35  4466.2  344.94  4516.5  341.81
    4523  340.42  4576.8  337.42  4677.3  329.21  4737.6  326.08  4787.9  324.97
  4938.7  317.76  4948.7  316.98  4968.8  312.92  4995.2  308.91  5039.8  310.73
    5046  313.42  5054.4  313.53  5060.6   315.9    5069     315  5075.3  316.94
    5083  317.31  5089.9  315.34  5096.1  317.95  5110.7  319.17  5146.2  320.95
  5169.2   320.9  5275.5  327.78  5346.4   330.4  5461.2  336.73  5543.5  344.07
#Mann= 3 , 0 , 0
  4375.9     .17       0  4968.8     .09       0    5046     .17       0
#XS Ineff= 2 , 0
       0                  5060.6       0   315.9
Permanent Ineff=
       F       F
Bank Sta=4968.8,5046
XS Rating Curve= 0 ,0
Exp/Cntr=0.3,0.1

Type RM Length L Ch R = 1 ,15911   ,499,499,499
BEGIN DESCRIPTION:
SAND BRANCH NO 2 30.0
END DESCRIPTION:
XS GIS Cut Line= 3
      3739092.87     10171398.27      3739250.01     10170638.85
      3738713.98     10170235.23
#Sta/Elev= 30
  4224.5  335.57  4313.5  334.15  4354.4  332.09  4371.1  332.27  4476.9  326.69
  4516.6  326.04  4566.8  323.25  4854.8  315.39  4913.1  311.89  4918.2  312.58
  4956.9  309.55  4963.3  308.06  4968.4  309.36  4977.3  307.65  4987.5  305.31
  4994.6  301.66  5002.3  302.16  5006.8  303.94  5021.4  306.24  5050.5  307.53
  5100.5  310.74    5165  311.93  5185.9  313.43    5442  322.28  5500.3  325.53
  5521.1  325.47  5535.7  327.06  5571.1  328.28  5585.6  329.74    5671  334.56
#Mann= 3 , 0 , 0
  4224.5     .17       0  4977.3     .09       0  5050.5     .17       0
Bank Sta=4977.3,5050.5
XS Rating Curve= 0 ,0
Exp/Cntr=0.3,0.1

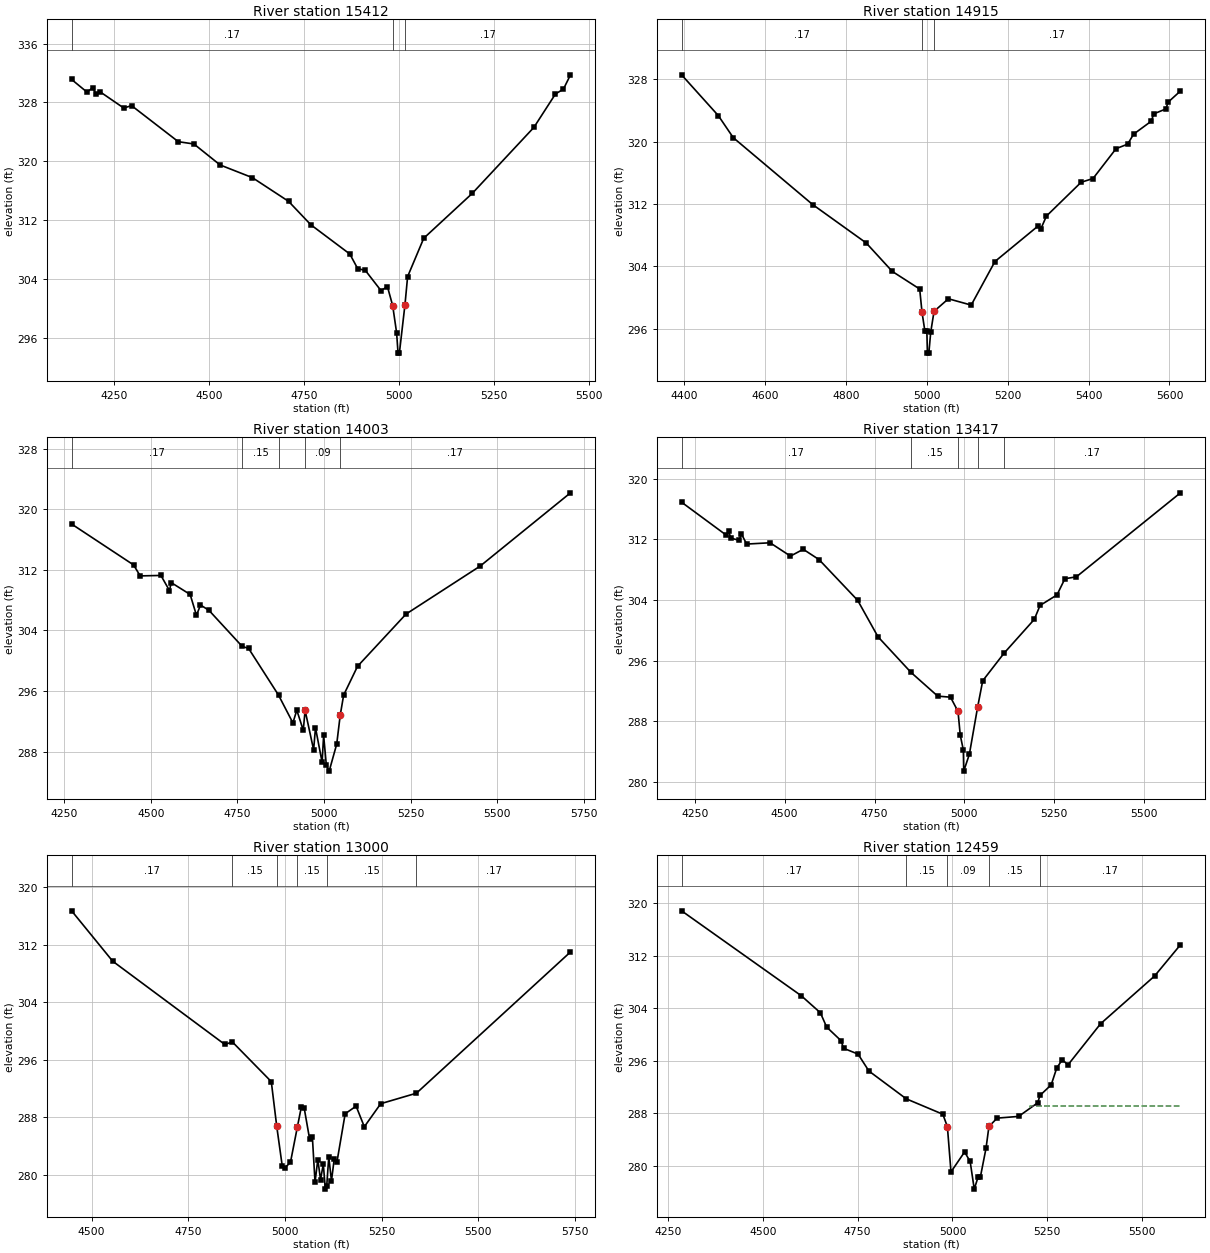
Type RM Length L Ch R = 1 ,15412   ,497,497,497
BEGIN DESCRIPTION:
SAND BRANCH NO 2 29.0
END DESCRIPTION:
XS GIS Cut Line= 3
      3739702.24     10171124.83      3739506.29     10170285.09
      3739199.66       10169953.
#Sta/Elev= 30
  4137.7  331.12  4178.3   329.4  4192.9  329.99  4203.2  329.09  4213.4  329.42
  4275.1  327.24  4295.6  327.57  4418.8  322.67  4459.9  322.36  4528.9  319.51
  4613.9  317.79  4709.3  314.57  4767.9  311.39  4870.6  307.42  4891.2  305.45
  4911.7  305.18  4952.8  302.45  4969.7     303  4983.6   300.4  4993.9  296.73
  4997.7  293.96  5001.2  293.96    5016  300.56  5022.9  304.35  5065.4  309.56
    5193  315.64  5355.7  324.62  5412.4  329.15  5433.4  329.81    5452  331.75
#Mann= 3 , 0 , 0
  4137.7     .17       0  4983.6     .09       0    5016     .17       0
Bank Sta=4983.6,5016
XS Rating Curve= 0 ,0
Exp/Cntr=0.3,0.1

Type RM Length L Ch R = 1 ,14915   ,912,912,912
BEGIN DESCRIPTION:
SAND BRANCH NO 2 28.0
END DESCRIPTION:
XS GIS Cut Line= 3
      3740256.91     10170648.26      3739945.64     10170127.72
      3739439.24     10169757.68
#Sta/Elev= 30
  4393.5  328.56  4484.3  323.33  4521.3   320.5  4717.7  311.92    4850     307
  4914.5  303.35  4982.3  301.09  4988.1  298.09  4995.1  295.71    5000  295.71
  5001.4  292.87  5004.9  292.87  5009.6  295.56  5017.8  298.23  5053.3  299.84
  5109.7  299.03  5168.4  304.62    5275  309.17  5282.1  308.83  5295.8  310.45
  5381.5  314.78  5410.9  315.26  5467.9  319.09  5496.6  319.67  5511.3  320.95
  5554.6   322.6  5561.5  323.56  5590.8  324.18    5597  325.07  5627.2  326.49
#Mann= 3 ,-1 , 0
  4393.5     .17       0  4988.1     .09       0  5017.8     .17       0
Bank Sta=4988.1,5017.8
XS Rating Curve= 0 ,0
Exp/Cntr=0.3,0.1

Type RM Length L Ch R = 1 ,14003   ,586,586,586
BEGIN DESCRIPTION:
SAND BRANCH NO 2 26.0
END DESCRIPTION:
XS GIS Cut Line= 3
      3740934.03     10169919.13      3740254.64     10169655.38
      3739543.39     10169624.85
#Sta/Elev= 30
  4271.2  318.05  4450.1  312.65  4469.3   311.2  4529.1  311.26  4553.7  309.27
    4559  310.31  4613.5  308.75  4631.8  305.99  4643.4  307.36  4667.9  306.65
    4764  301.88  4782.2  301.63  4868.7  295.46  4910.3  291.79  4921.5  293.47
  4940.2  290.81  4945.5  293.44  4970.1  288.23  4975.5  291.15  4994.6  286.58
    4999  290.14  5006.8  286.21    5015  285.42  5036.8  288.99  5046.8  292.77
  5056.8  295.46  5096.9  299.26    5237  306.16  5451.2   312.5  5711.9  322.17
#Mann= 5 ,-1 , 0
  4271.2     .17       0    4764     .15       0  4868.7     .17       0
  4945.5     .09       0  5046.8     .17       0
Bank Sta=4945.5,5046.8
XS Rating Curve= 0 ,0
Exp/Cntr=0.3,0.1

Type RM Length L Ch R = 1 ,13417   ,417,417,417
BEGIN DESCRIPTION:
SAND BRANCH NO 2 25.0
END DESCRIPTION:
XS GIS Cut Line= 3
      3740918.39     10169882.67      3740462.68     10169241.41
       3739891.3     10169055.05
#Sta/Elev= 30
  4213.3  316.92  4337.8  312.56  4343.9  313.12  4350.2  312.17  4373.4  311.89
  4379.6  312.74  4394.3  311.39  4459.5  311.56  4516.1   309.8  4551.7   310.7
  4595.6  309.34    4703  303.96  4759.6  299.14  4851.5  294.43  4925.7   291.3
  4961.3  291.16  4982.2  289.28  4988.4  286.15    4997  284.19  4998.1  281.39
  5013.8  283.62  5036.6  289.81  5050.9  293.33  5110.4  296.98  5194.4  301.44
  5210.4  303.28  5257.5  304.67  5279.5  306.81  5311.4  307.06    5601  318.16
#Mann= 5 ,-1 , 0
  4213.3     .17       0  4851.5     .15       0  4982.2     .09       0
  5036.6     .15       0  5110.4     .17       0
#XS Ineff= 2 , 0
       0  4961.3  291.16               0
Permanent Ineff=
       F       F
Bank Sta=4982.2,5036.6
XS Rating Curve= 0 ,0
Exp/Cntr=0.3,0.1

Type RM Length L Ch R = 1 ,13000   ,541,541,541
BEGIN DESCRIPTION:
SAND BRANCH NO 2 26.5
END DESCRIPTION:
XS GIS Cut Line= 3
      3741217.86     10169511.08      3740821.68     10169127.12
      3740293.38     10168611.82
#Sta/Elev= 30
  4448.3  316.73  4554.4  309.73  4844.3  298.15    4864  298.49  4964.5  292.98
  4978.6  286.76  4992.8  281.25  4999.2  280.96  5014.1  281.76 5032.03   286.7
  5042.4  289.51  5049.4  289.36  5063.5  285.02  5070.7   285.3  5077.6  278.99
  5084.8  282.15  5091.8  279.36    5099  281.51  5104.2  278.03  5107.9  278.53
  5113.1  282.51  5120.1  279.18  5127.2  282.22  5134.2  281.79  5155.5  288.51
  5183.8  289.57    5205   286.7  5247.4  289.91  5339.7  291.37    5738  311.01
#Mann= 6 ,-1 , 0
  4448.3     .17       0    4864     .15       0  4978.6     .09       0
 5032.03     .15       0  5107.9     .15       0  5339.7     .17       0
#XS Ineff= 2 , 0
       0                  5042.4       0  289.51
Permanent Ineff=
       F       T
Bank Sta=4978.6,5032.03
XS Rating Curve= 0 ,0
Exp/Cntr=0.3,0.1

Type RM Length L Ch R = 1 ,12459   ,522,522,522
BEGIN DESCRIPTION:
SAND BRANCH NO 2 24.0
END DESCRIPTION:
XS GIS Cut Line= 3
      3741522.57     10169119.65      3740885.88     10168796.74
      3740398.22     10168445.64
#Sta/Elev= 30
  4286.1  318.82  4601.6   305.9  4651.8  303.32  4668.4  301.14  4706.3  299.07
    4713  297.91  4751.1  297.03  4779.8  294.45  4878.3  290.22  4974.6  287.88
  4986.6  285.99  4996.1  279.11  5031.9  282.14  5046.6   280.7  5057.4  276.49
  5067.5  278.33  5073.6  278.35  5088.4   282.7  5096.1  286.02  5117.8  287.29
  5174.3  287.55  5224.6  289.62  5230.6  290.74  5260.2  292.35  5274.9  294.93
  5289.6  296.18  5304.3  295.38  5390.3  301.64  5532.6   308.9  5600.9  313.66
#Mann= 5 ,-1 , 0
  4286.1     .17       0  4878.3     .15       0  4986.6     .09       0
  5096.1     .15       0  5230.6     .17       0
#XS Ineff= 2 , 0
       0                  5203.7       0   289.1
Permanent Ineff=
       F       F
Bank Sta=4986.6,5096.1
XS Rating Curve= 0 ,0
Exp/Cntr=0.3,0.1

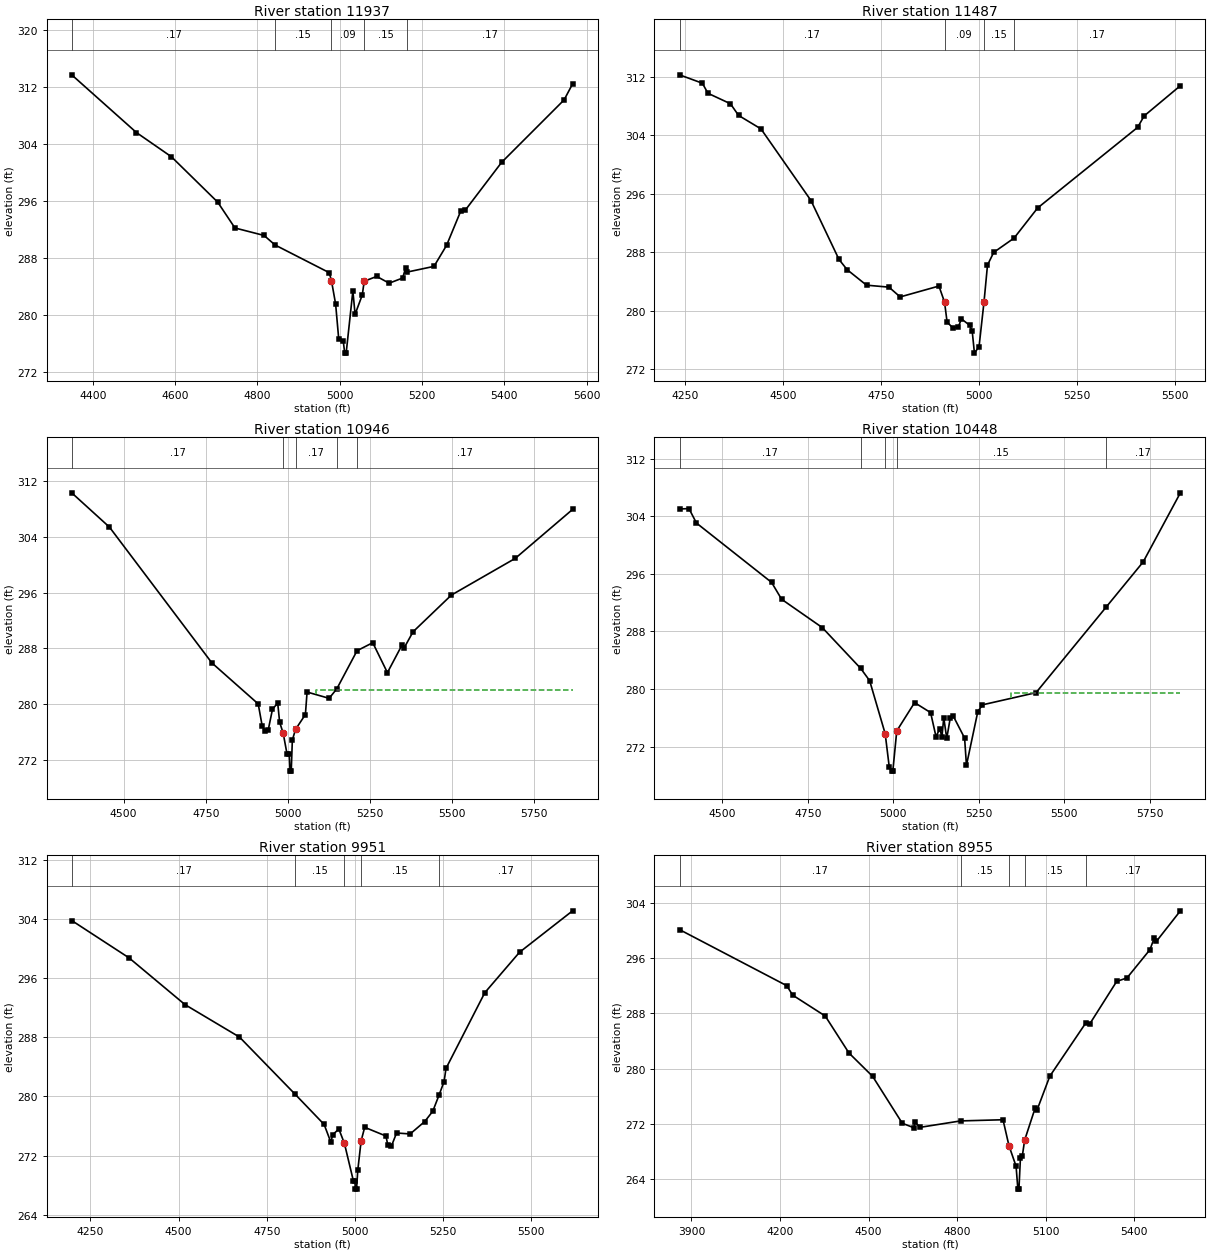
Type RM Length L Ch R = 1 ,11937   ,450,450,450
BEGIN DESCRIPTION:
SAND BRANCH NO 2 23.0
END DESCRIPTION:
XS GIS Cut Line= 3
      3741634.53     10168700.37      3740998.23     10168560.47
      3740478.57     10168335.91
#Sta/Elev= 30
  4348.5  313.65    4506  305.54  4590.8  302.15  4703.5  295.77  4745.3  292.15
  4816.1   291.1  4842.9  289.76  4974.4  285.88  4979.9  284.77  4990.1  281.46
  4997.6  276.58  5008.5  276.33  5012.2  274.58  5015.7  274.58    5032  283.31
  5037.4  280.03  5054.9  282.75 5059.53  284.67  5089.9  285.35  5120.2   284.4
  5152.9  285.12  5160.4  286.54  5163.2  285.95  5229.2  286.76  5259.8  289.71
  5294.5  294.56  5305.4  294.66  5393.6  301.36  5545.5  310.13  5566.1  312.37
#Mann= 5 ,-1 , 0
  4348.5     .17       0  4842.9     .15       0  4979.9     .09       0
 5059.53     .15       0  5163.2     .17       0
#XS Ineff= 2 , 0
       0                  5160.4       0  286.54
Permanent Ineff=
       F       F
Bank Sta=4979.9,5059.53
XS Rating Curve= 0 ,0
Exp/Cntr=0.3,0.1

Type RM Length L Ch R = 1 ,11487   ,541,541,541
BEGIN DESCRIPTION:
SAND BRANCH NO 2 22.0
END DESCRIPTION:
XS GIS Cut Line= 3
      3741650.18     10168661.33      3741064.39     10168170.26
      3740560.98     10168067.96
#Sta/Elev= 30
  4235.6  312.31  4293.9  311.16  4308.2  309.78  4365.5  308.35  4386.3  306.75
  4443.5   304.9    4571  295.09  4642.6  287.01  4663.4  285.61  4712.8  283.49
  4770.1  283.22  4798.7  281.88  4897.6  283.37  4911.9  281.17  4918.4  278.44
  4932.7  277.65    4947  277.72  4954.8  278.88  4975.6  278.01  4982.4  277.23
  4988.2  274.18    5000  275.08 5012.64   281.2  5021.5  286.24  5037.3  287.98
  5089.3  289.94  5149.5  294.07  5404.6  305.11  5421.3  306.68  5513.7  310.82
#Mann= 4 ,-1 , 0
  4235.6     .17       0  4911.9     .09       0 5012.64     .15       0
  5089.3     .17       0
Bank Sta=4911.9,5012.64
XS Rating Curve= 0 ,0
Exp/Cntr=0.3,0.1

Type RM Length L Ch R = 1 ,10946   ,498,498,498
BEGIN DESCRIPTION:
SAND BRANCH NO 2 21.0
END DESCRIPTION:
XS GIS Cut Line= 3
       3741686.6     10168603.97      3741430.65      10167997.9
      3740582.67     10167820.21
#Sta/Elev= 30
  4342.1   310.3  4456.9  305.39  4768.6  285.94  4909.7  280.06  4921.6  276.95
  4931.4  276.22  4939.9  276.26  4953.1  279.29    4969  280.19  4974.9  277.44
  4985.7  275.86  4997.2  272.94    5004  272.94  5006.7  270.43  5010.2  270.43
  5013.6  274.88  5023.3  276.41  5053.3  278.54  5058.4  281.76  5125.5  280.86
    5149  282.23  5210.5  287.68  5258.3  288.83  5302.9  284.54  5347.7  288.53
  5352.8     288  5380.9  290.39  5497.5  295.65    5692  300.91  5866.4  307.92
#Mann= 5 ,-1 , 0
  4342.1     .17       0  4985.7     .09       0  5023.3     .17       0
    5149     .15       0  5210.5     .17       0
#XS Ineff= 2 , 0
       0    4969  280.19  5084.6       0  282.03
Permanent Ineff=
       F       F
Bank Sta=4985.7,5023.3
XS Rating Curve= 0 ,0
Exp/Cntr=0.3,0.1

Type RM Length L Ch R = 1 ,10448   ,497,497,497
BEGIN DESCRIPTION:
SAND BRANCH NO 2 20.0
END DESCRIPTION:
XS GIS Cut Line= 3
      3742118.91     10168335.78       3741813.9     10167790.83
      3741574.65     10166986.87
#Sta/Elev= 30
  4375.5     305  4403.2  305.05  4424.9  303.05  4644.5  294.81  4673.8  292.47
  4792.6  288.54  4904.9  282.87    4931  281.17  4976.4  273.81  4988.3  269.18
  4995.2  268.62  4998.7  268.62  5010.2   274.2  5062.3  278.13  5109.1  276.74
  5124.9   273.4  5135.4  274.47  5142.3  273.42  5147.5  276.04  5156.2  273.16
  5166.7  276.05  5175.4  276.25  5208.4  273.21  5213.8  269.43    5247  276.88
  5260.6  277.82  5417.1  279.51  5621.2  291.34  5730.1  297.65  5838.8  307.24
#Mann= 5 ,-1 , 0
  4375.5     .17       0  4904.9     .15       0  4976.4     .09       0
  5010.2     .15       0  5621.2     .17       0
#XS Ineff= 2 , 0
       0                  5344.1       0  279.42
Permanent Ineff=
       F       F
Bank Sta=4976.4,5010.2
XS Rating Curve= 0 ,0
Exp/Cntr=0.3,0.1

Type RM Length L Ch R = 1 ,9951    ,996,996,996
BEGIN DESCRIPTION:
SAND BRANCH NO 2 19.0
END DESCRIPTION:
XS GIS Cut Line= 3
       3742363.7     10168236.83      3742134.34     10167467.49
      3741915.79      10166890.5
#Sta/Elev= 30
  4197.2  303.78  4359.7  298.73  4518.3  292.41  4672.8  288.02  4830.5  280.29
  4912.8   276.2  4931.8   273.8    4937  274.82  4954.5  275.58  4970.2  273.65
  4995.5  268.61    5000  268.61  5001.1  267.46  5004.6  267.46  5008.2  270.05
  5017.6  273.98  5027.7  275.82    5088  274.64  5093.3  273.41  5103.1  273.23
  5118.1  275.05  5156.6  274.92  5197.9   276.6  5220.7  277.99  5238.3  280.15
  5252.8  282.01  5258.2  283.78  5368.2  294.02  5466.7  299.49    5617  305.09
#Mann= 5 ,-1 , 0
  4197.2     .17       0  4830.5     .15       0  4970.2     .09       0
  5017.6     .15       0  5238.3     .17       0
Bank Sta=4970.2,5017.6
XS Rating Curve= 0 ,0
Exp/Cntr=0.3,0.1

Type RM Length L Ch R = 1 ,8955    ,499,499,499
BEGIN DESCRIPTION:
SAND BRANCH NO 2 18.0
END DESCRIPTION:
XS GIS Cut Line= 3
      3742543.39       10168203.      3742642.78     10167066.94
       3742272.7     10166651.06
#Sta/Elev= 30
  3859.6  300.15  4222.9  292.03    4243  290.66  4353.4  287.63  4433.7  282.28
    4514  278.89  4614.4   272.1  4653.1  271.46  4658.1  272.23  4674.6  271.51
  4811.9  272.44  4955.7  272.61  4975.8  268.87    5000  265.87  5006.1  262.56
  5009.7  262.56  5014.7  267.03  5021.4  267.43    5029  269.65  5064.1  274.24
  5071.6  274.08  5114.2  278.91  5237.2  286.69  5248.8  286.43  5340.8  292.64
    5376  293.16  5453.7  297.25  5467.9   298.9  5475.5  298.45  5556.7  302.87
#Mann= 5 ,-1 , 0
  3859.6     .17       0  4811.9     .15       0  4975.8     .09       0
    5029     .15       0  5237.2     .17       0
Bank Sta=4975.8,5029
XS Rating Curve= 0 ,0
Exp/Cntr=0.3,0.1

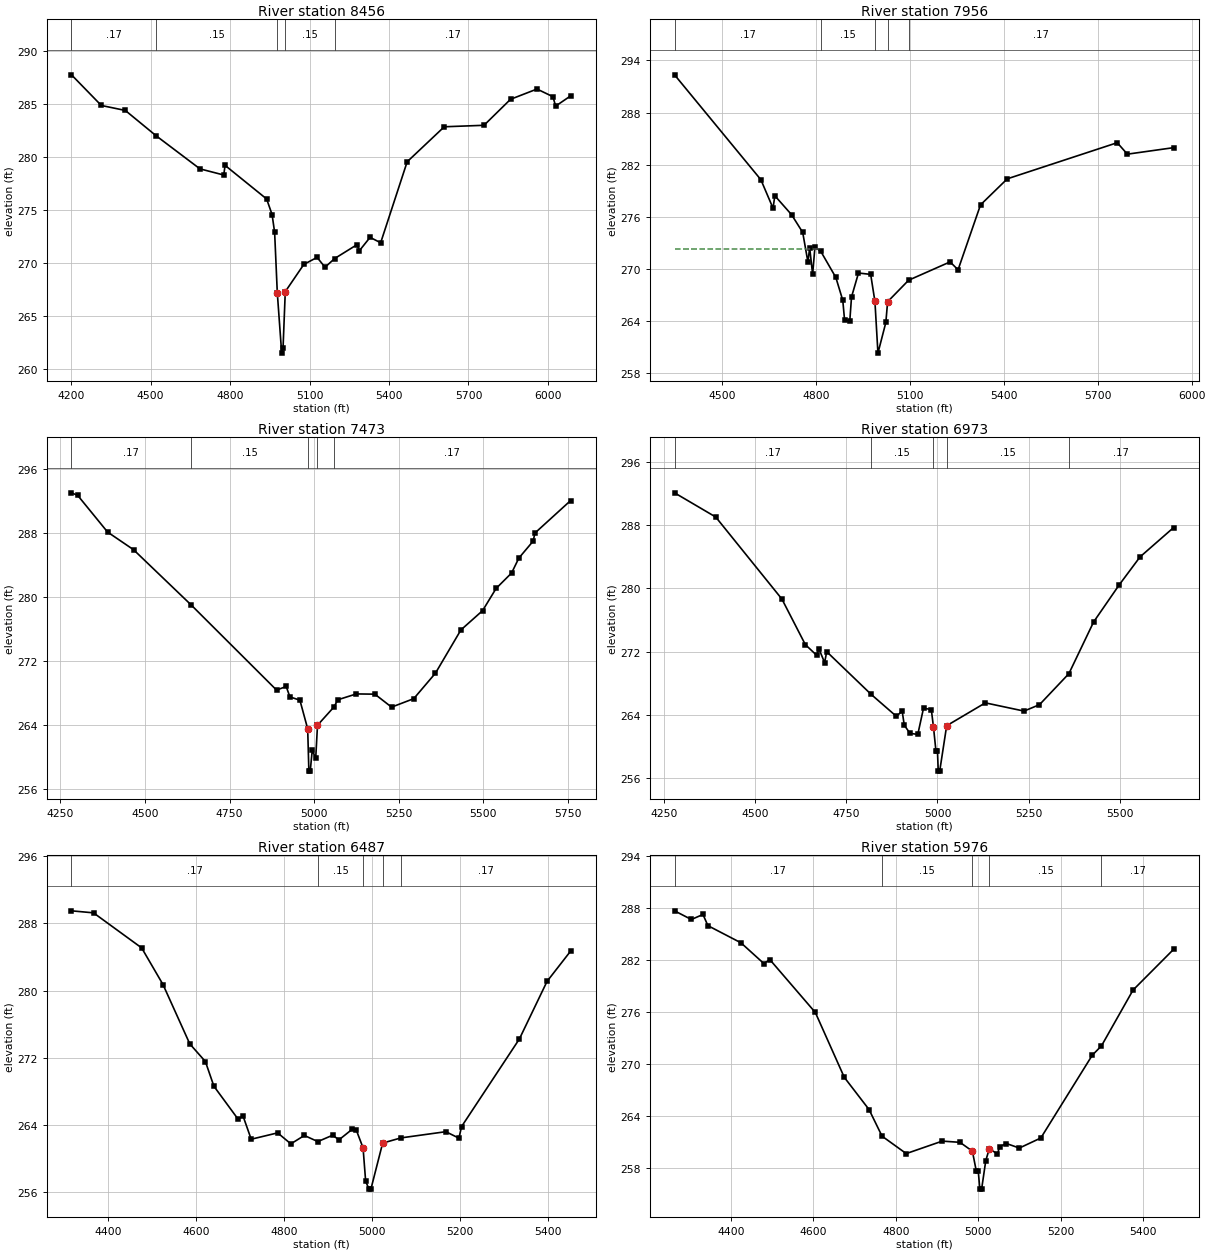
Type RM Length L Ch R = 1 ,8456    ,500,500,500
BEGIN DESCRIPTION:
SAND BRANCH NO 2 17.0
END DESCRIPTION:
XS GIS Cut Line= 3
       3742926.2     10168012.89      3743018.15      10167219.5
      3742991.35     10166134.33
#Sta/Elev= 30
  4201.3  287.73  4313.9  284.84  4404.5  284.37  4521.4  281.97  4686.3  278.86
  4776.1  278.28  4781.1  279.19    4938  276.02  4958.6  274.55  4968.2  272.87
  4978.3  267.16  4994.8  261.48    5000  261.98  5008.4  267.28  5078.5  269.85
  5128.5  270.51  5158.5  269.58  5194.7   270.4  5278.5   271.7  5288.5  271.15
  5328.5   272.4  5368.5  271.89  5468.6  279.53  5608.6  282.83  5758.7  282.97
  5858.7  285.42  5958.7  286.39  6018.7  285.67  6029.2  284.78  6085.5  285.74
#Mann= 5 ,-1 , 0
  4201.3     .17       0  4521.4     .15       0  4978.3     .09       0
  5008.4     .15       0  5194.7     .17       0
#XS Ineff= 2 , 0
       0                  5328.5       0   272.4
Permanent Ineff=
       F       F
Bank Sta=4978.3,5008.4
XS Rating Curve= 0 ,0
Exp/Cntr=0.3,0.1

Type RM Length L Ch R = 1 ,7956    ,483,483,483
BEGIN DESCRIPTION:
SAND BRANCH NO 2 16.0
END DESCRIPTION:
XS GIS Cut Line= 3
      3743616.29     10167614.41      3743321.72     10167033.31
      3743038.73      10166134.4
#Sta/Elev= 30
  4348.5  292.34  4624.2  280.26  4663.1  276.97  4668.8  278.41  4722.2  276.23
  4757.8  274.19  4774.5  270.77  4780.1  272.42  4789.5  269.34  4796.8  272.48
  4815.3  272.02  4863.6     269  4885.8  266.36  4891.5   264.1  4908.1  263.93
  4913.7  266.75    4936  269.51  4974.9  269.35 4988.47  266.23  4998.1  260.28
  5023.3  263.81    5029   266.2  5096.1  268.68  5228.5  270.79    5254  269.88
  5325.7  277.36  5411.2  280.36  5762.3  284.52  5794.7   283.2  5942.4  283.95
#Mann= 5 ,-1 , 0
  4348.5     .17       0  4815.3     .15       0 4988.47     .09       0
    5029     .15       0  5096.1     .17       0
#XS Ineff= 2 , 0
       0  4811.9  272.22  5228.5       0  270.79
Permanent Ineff=
       F       F
Bank Sta=4988.47,5029
XS Rating Curve= 0 ,0
Exp/Cntr=0.3,0.1

Type RM Length L Ch R = 1 ,7473    ,500,500,500
BEGIN DESCRIPTION:
SAND BRANCH NO 2 15.0
END DESCRIPTION:
XS GIS Cut Line= 3
      3743965.27     10167507.68      3743666.18     10166856.04
      3743394.97     10166148.33
#Sta/Elev= 30
    4283  292.98  4301.3  292.66  4389.7  288.08  4466.3  285.88  4636.9  278.97
    4889  268.35  4917.5   268.8  4928.4   267.5    4958  267.09    4981  263.51
  4984.5  258.23  4988.5  258.23  4994.5  260.84  5004.7  259.82    5010  263.96
  5058.8  266.25  5070.1  267.14  5124.8  267.87  5179.5  267.84  5228.9  266.22
  5294.5  267.28  5358.7  270.47  5433.8  275.86  5497.9  278.27  5537.8  281.04
  5583.6  282.97    5605  284.83  5647.3  286.95  5652.6  287.96  5757.9  292.01
#Mann= 5 ,-1 , 0
    4283     .17       0  4636.9     .15       0    4981     .09       0
    5010     .15       0  5058.8     .17       0
#XS Ineff= 2 , 0
       0  4917.5   268.8               0
Permanent Ineff=
       F       F
Bank Sta=4981,5010
XS Rating Curve= 0 ,0
Exp/Cntr=0.3,0.1

Type RM Length L Ch R = 1 ,6973    ,486,486,486
BEGIN DESCRIPTION:
SAND BRANCH NO 2 14.0
END DESCRIPTION:
XS GIS Cut Line= 3
      3744392.33     10167189.92      3744025.98     10166568.82
      3743569.44     10166109.24
#Sta/Elev= 30
  4278.9  292.09  4391.9  289.03  4573.4  278.66  4637.7   272.9    4669  271.54
  4674.8  272.38  4690.5  270.63  4696.3  272.01  4818.2  266.61  4887.6  263.83
  4903.2  264.52    4909  262.72  4924.7  261.69  4946.1  261.55  4961.8  264.87
  4983.2  264.69    4989  262.53  4995.8   259.5    5000   259.5  5002.2  256.91
  5006.2  256.91  5025.3  262.65  5131.4  265.54  5237.5   264.5  5279.9  265.31
  5360.5  269.23  5428.4  275.77  5499.1  280.49  5555.7  283.99  5647.8   287.7
#Mann= 5 ,-1 , 0
  4278.9     .17       0  4818.2     .15       0    4989     .09       0
  5025.3     .15       0  5360.5     .17       0
Bank Sta=4989,5025.3
XS Rating Curve= 0 ,0
Exp/Cntr=0.3,0.1

Type RM Length L Ch R = 1 ,6487    ,511,511,511
BEGIN DESCRIPTION:
SAND BRANCH NO 2 13.0
END DESCRIPTION:
XS GIS Cut Line= 3
      3744579.84     10166945.15      3744335.42      10166307.6
      3744080.32     10165935.44
#Sta/Elev= 30
  4317.2  289.51  4367.2  289.27  4476.6  285.09  4525.1  280.72    4586  273.64
  4621.4  271.54  4640.8  268.59  4695.5  264.68  4707.1  265.02  4725.5  262.27
  4785.6  263.03  4815.6  261.72  4846.3  262.72  4876.9  261.99  4910.6  262.75
    4925   262.2    4955  263.46  4964.2  263.38  4979.7  261.24  4985.6  257.24
  4993.4  256.32  4997.5  256.32  5024.2  261.81  5065.8  262.43  5167.7  263.17
  5197.5   262.4  5203.5  263.78  5334.9  274.23  5397.8   281.1  5451.2   284.7
#Mann= 5 ,-1 , 0
  4317.2     .17       0  4876.9     .15       0  4979.7     .09       0
  5024.2     .15       0  5065.8     .17       0
#XS Ineff= 2 , 0
       0  4707.1  265.02               0
Permanent Ineff=
       F       F
Bank Sta=4979.7,5024.2
XS Rating Curve= 0 ,0
Exp/Cntr=0.3,0.1

Type RM Length L Ch R = 1 ,5976    ,489,489,489
BEGIN DESCRIPTION:
SAND BRANCH NO 2 12.0
END DESCRIPTION:
XS GIS Cut Line= 3
      3744717.87     10166921.75      3744768.74     10166186.81
      3744900.17      10165731.6
#Sta/Elev= 30
  4263.3   287.7  4304.1   286.7  4332.3  287.28  4344.2  285.99  4424.4  284.01
  4479.9  281.62  4494.5  282.07  4604.8  275.97    4675  268.49  4735.1  264.77
  4766.6   261.7  4825.3  259.69  4912.6  261.13  4955.6  260.99  4985.7  259.97
  4995.4  257.63    5000  257.63  5003.8  255.59  5008.1  255.59  5018.2  258.88
  5026.8  260.26  5046.6  259.64  5051.8   260.5  5068.4  260.85  5099.6  260.33
  5151.7  261.49  5276.6  271.05  5298.8  272.12  5375.4  278.56  5473.8  283.26
#Mann= 5 ,-1 , 0
  4263.3     .17       0  4766.6     .15       0  4985.7     .09       0
  5026.8     .15       0  5298.8     .17       0
Bank Sta=4985.7,5026.8
XS Rating Curve= 0 ,0
Exp/Cntr=0.3,0.1

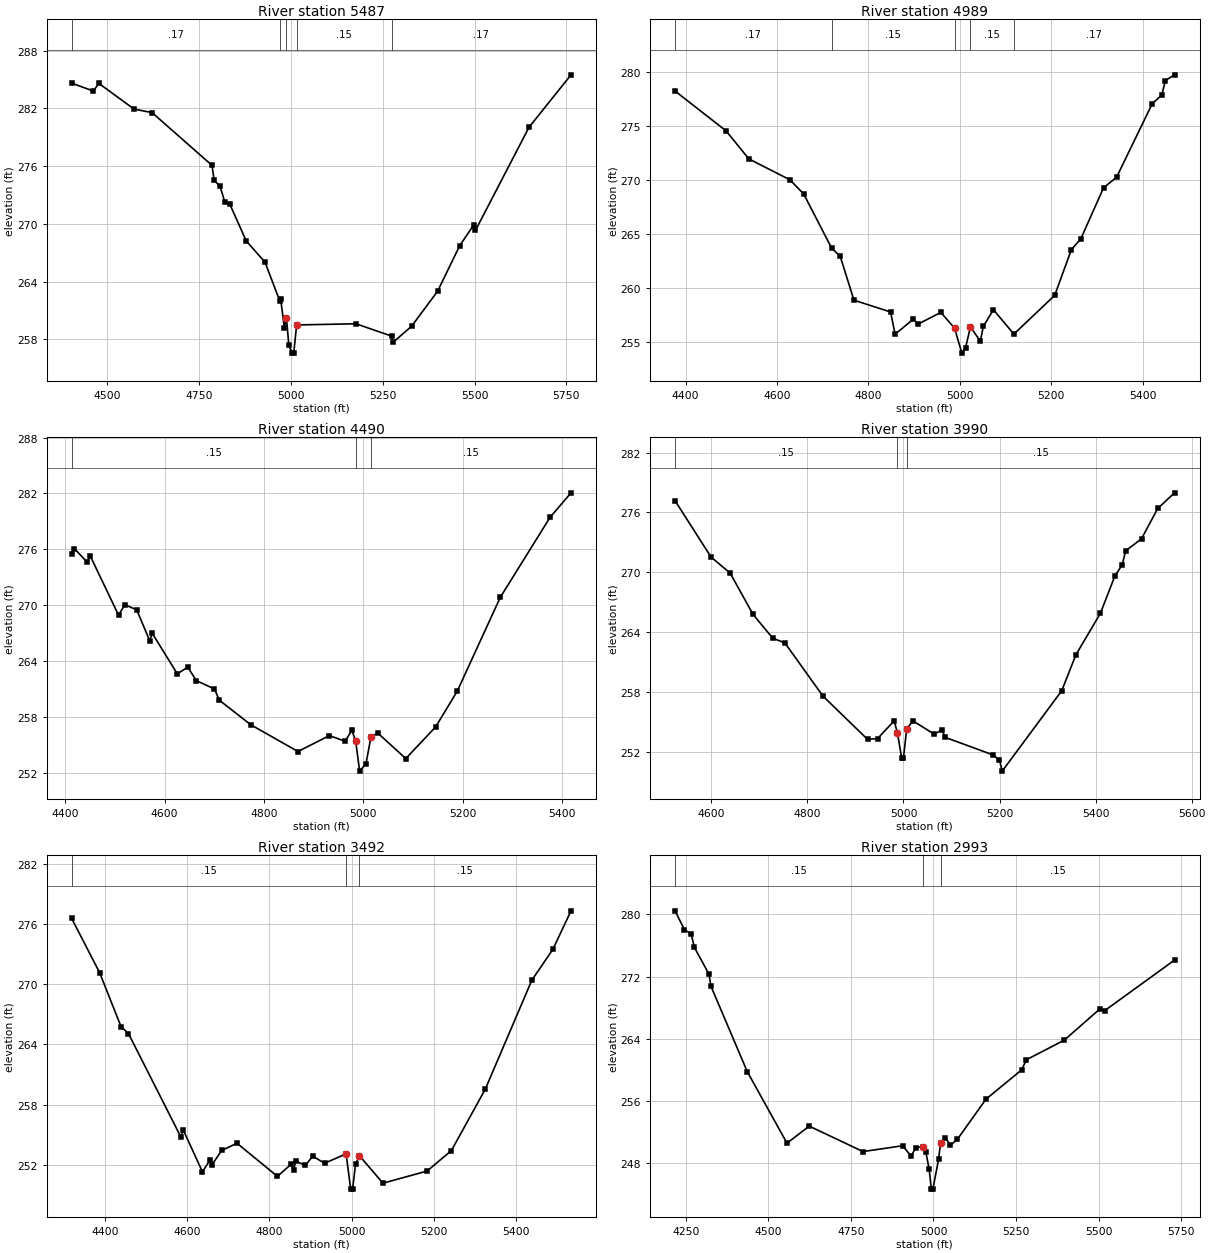
Type RM Length L Ch R = 1 ,5487    ,498,498,498
BEGIN DESCRIPTION:
SAND BRANCH NO 2 11.0
END DESCRIPTION:
XS GIS Cut Line= 3
      3744814.23     10166929.54       3745119.4     10166416.78
      3745017.85     10165661.07
#Sta/Elev= 30
  4403.3  284.63  4462.4  283.81    4478  284.59  4573.4  281.93  4622.6  281.56
  4785.5  276.08  4791.5  274.51  4807.1  273.94  4820.5  272.27  4834.3  272.02
  4878.6  268.23  4929.8  266.01  4970.1  261.97  4972.6  262.14  4982.4   259.2
  4988.2   260.2  4994.6  257.39  5003.6  256.56  5007.9  256.56  5015.9  259.49
  5177.3  259.61  5274.2  258.33  5278.8   257.7  5328.6  259.35  5399.3  262.99
  5459.8  267.74  5497.4  269.87  5502.5  269.32  5648.2  280.04  5762.5  285.49
#Mann= 5 ,-1 , 0
  4403.3     .17       0  4970.1     .15       0  4988.2     .09       0
  5015.9     .15       0  5274.2     .17       0
Bank Sta=4988.2,5015.9
XS Rating Curve= 0 ,0
Exp/Cntr=0.3,0.1

Type RM Length L Ch R = 1 ,4989    ,499,499,499
BEGIN DESCRIPTION:
SAND BRANCH NO 2 10.0
END DESCRIPTION:
XS GIS Cut Line= 3
      3745564.22     10167002.46      3745587.23     10166370.08
      3745941.38     10166075.74
#Sta/Elev= 30
  4376.7  278.21  4488.2  274.53  4538.2  271.93  4628.3  269.99  4658.3  268.68
  4719.2  263.69  4738.3   262.9  4768.3  258.85  4848.4  257.76  4858.4   255.7
  4898.4   257.1  4908.4  256.63  4958.5  257.72  4988.5  256.26  5004.4  253.95
  5012.6  254.45  5023.3  256.39  5044.9  255.04  5051.4  256.42  5073.6  257.97
  5118.3  255.71  5207.7   259.3  5244.2  263.53    5265  264.54  5314.5  269.25
  5343.1  270.23  5421.2  277.04  5442.1  277.84  5449.9  279.18    5470  279.71
#Mann= 5 ,-1 , 0
  4376.7     .17       0  4719.2     .15       0  4988.5     .09       0
  5023.3     .15       0  5118.3     .17       0
Bank Sta=4988.5,5023.3
XS Rating Curve= 0 ,0
Exp/Cntr=0.3,0.1

Type RM Length L Ch R = 1 ,4490    ,500,500,500
BEGIN DESCRIPTION:
SAND BRANCH NO 2 9.0
END DESCRIPTION:
XS GIS Cut Line= 3
      3745801.22     10167072.73      3745991.02     10166516.62
      3746017.35     10166098.85
#Sta/Elev= 30
  4412.4  275.44  4418.4  276.06  4444.5  274.58  4449.8  275.32  4507.1  268.92
  4519.8  270.04  4543.8  269.49  4569.8  266.18  4575.1  266.96  4625.5  262.61
  4646.6  263.33  4663.8  261.88  4700.4  260.98    4710  259.78  4773.4  257.14
  4868.5  254.26  4931.9  255.97  4963.6  255.36  4977.1  256.55  4984.7   255.4
  4992.8  252.15  5005.6  252.96  5015.6  255.83  5029.2  256.25  5085.7   253.5
  5145.8   256.9  5189.5  260.76  5276.1  270.83  5376.3  279.43  5418.6  282.07
#Mann= 3 , 0 , 0
  4412.4     .15       0  4984.7     .07       0  5015.6     .15       0
Bank Sta=4984.7,5015.6
XS Rating Curve= 0 ,0
Exp/Cntr=0.3,0.1

Type RM Length L Ch R = 1 ,3990    ,498,498,498
BEGIN DESCRIPTION:
SAND BRANCH NO 2 8.0
END DESCRIPTION:
XS GIS Cut Line= 3
      3746532.97     10167067.56      3746407.33     10166608.96
       3746165.8     10166098.85
#Sta/Elev= 30
  4524.5  277.17  4599.6  271.51  4639.3   269.9  4686.8  265.77  4728.2  263.36
  4753.1  262.91  4832.4  257.57  4925.2  253.23  4946.2  253.31  4980.7  255.09
  4987.4  253.88  4996.3  251.37    5000  251.37  5006.8  254.28  5019.8  255.08
  5064.1  253.75  5080.6  254.19  5086.2  253.44  5185.8  251.68  5199.9  251.16
  5205.6  250.04  5329.6  258.11  5359.1  261.72  5410.1  265.88  5440.2  269.62
  5455.6  270.75  5462.4  272.13  5495.6  273.35  5529.4  276.39  5564.4  277.96
#Mann= 3 , 0 , 0
  4524.5     .15       0  4987.4     .07       0  5006.8     .15       0
Bank Sta=4987.4,5006.8
XS Rating Curve= 0 ,0
Exp/Cntr=0.3,0.1

Type RM Length L Ch R = 1 ,3492    ,499,499,499
BEGIN DESCRIPTION:
SAND BRANCH NO 2 7.0
END DESCRIPTION:
XS GIS Cut Line= 3
      3747019.97     10166919.17      3746746.33       10166296.
      3746265.86     10166065.49
#Sta/Elev= 30
  4319.4  276.58  4387.6  271.16  4439.8  265.77  4457.7  265.09  4585.4  254.75
  4590.8  255.49  4637.5  251.31  4655.4  252.46  4660.9  252.04  4684.3  253.44
  4721.4  254.16  4819.7  250.86  4852.5  252.06  4858.7  251.49  4864.1  252.36
  4887.5  251.96  4905.4  252.87  4934.2  252.17  4986.4   253.1  4997.7  249.59
  5002.3  249.59  5009.4  252.08    5019  252.91    5076  250.18  5183.1  251.39
  5242.3  253.43  5324.5  259.54  5437.8  270.41  5488.6  273.46  5532.9  277.31
#Mann= 3 , 0 , 0
  4319.4     .15       0  4986.4     .07       0    5019     .15       0
Bank Sta=4986.4,5019
XS Rating Curve= 0 ,0
Exp/Cntr=0.3,0.1

Type RM Length L Ch R = 1 ,2993    ,499,499,499
BEGIN DESCRIPTION:
SAND BRANCH NO 2 6.0
END DESCRIPTION:
XS GIS Cut Line= 3
       3747176.2     10166869.66      3747150.65     10166087.88
      3746546.01     10165679.55
#Sta/Elev= 30
  4217.8  280.47  4246.4  278.03  4266.4  277.52  4276.4  275.77  4320.9  272.29
  4326.4  270.78  4436.5  259.78  4556.6  250.59    4624  252.78  4786.7  249.51
  4906.8  250.26  4932.1  248.93  4946.8  250.01  4966.8  250.15  4976.8  249.46
  4986.8  247.28  4993.6  244.68  4998.2  244.68  5015.3   248.5  5021.3  250.55
  5036.3  251.28  5051.2  250.32  5072.2  251.08  5159.1  256.26    5267  260.02
  5280.9  261.31  5395.9  263.84  5503.8  267.86  5518.8  267.65  5729.6  274.14
#Mann= 3 , 0 , 0
  4217.8     .15       0  4966.8     .07       0  5021.3     .15       0
Bank Sta=4966.8,5021.3
XS Rating Curve= 0 ,0
Exp/Cntr=0.3,0.1