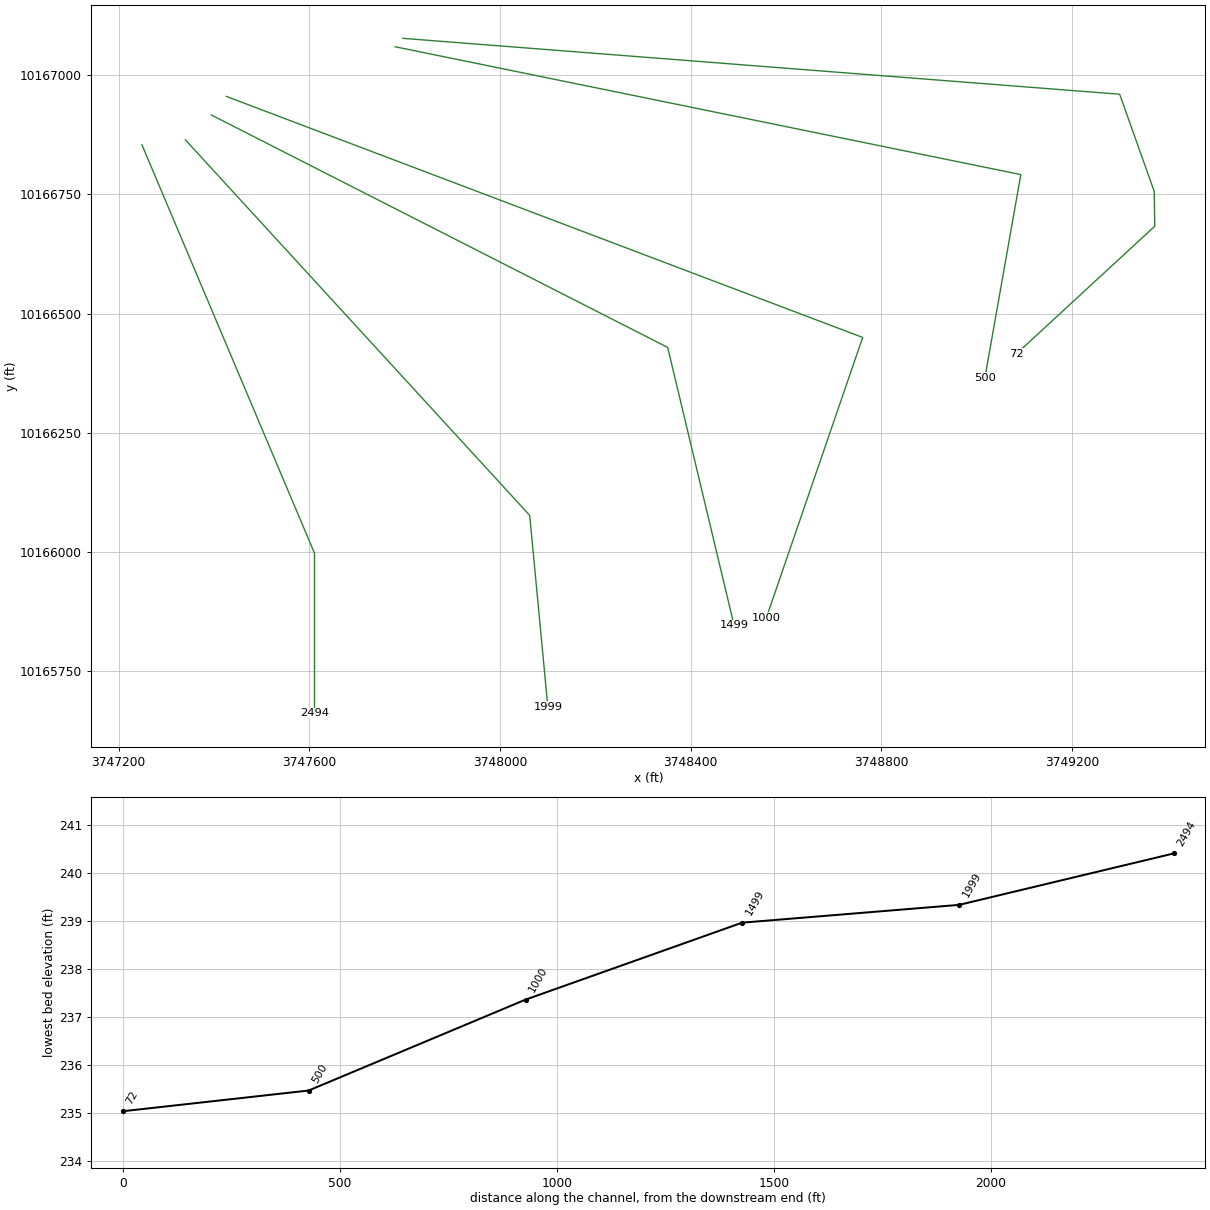
HEC-RAS study SAND BRANCH NO 2.prj: SAND BRANCH NO 2 Base Level Engineering

--- SAND BRANCH NO 2.g01 (geometry) --- (continued)

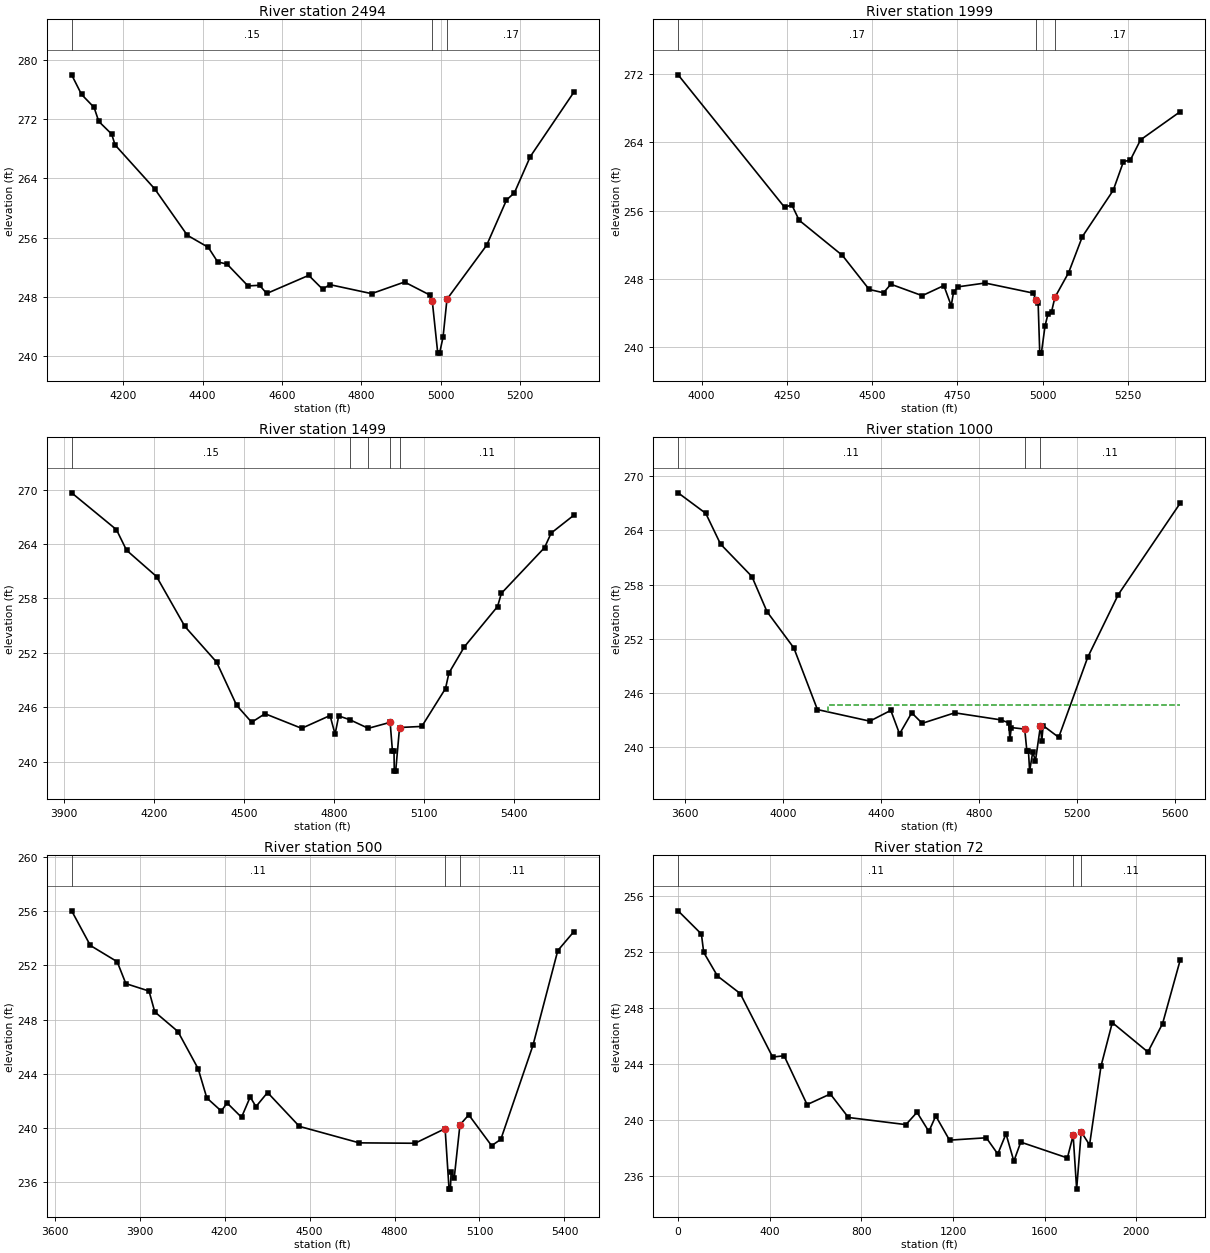
Type RM Length L Ch R = 1 ,2494    ,495,495,495
BEGIN DESCRIPTION:
SAND BRANCH NO 2 5.0
END DESCRIPTION:
XS GIS Cut Line= 3
      3747249.11     10166854.05      3747611.08     10165997.39
       3747611.1     10165661.29
#Sta/Elev= 30
    4070  278.01  4094.9  275.36  4126.5  273.61  4138.4  271.71  4170.9     270
  4179.4  268.54  4279.5  262.59  4361.6  256.33  4414.4   254.7  4438.1  252.73
  4461.8  252.43  4514.6  249.48  4543.8  249.57  4561.8  248.46  4667.7  250.91
  4702.9  249.03  4720.5  249.66  4826.2  248.44  4909.2  250.01  4973.9  248.23
  4979.3  247.38    4993   240.4  4997.6   240.4  5006.3  242.54  5016.3  247.69
  5116.3  254.98  5166.3  261.09  5186.3  262.07  5226.3  266.96  5336.1  275.66
#Mann= 3 , 0 , 0
    4070     .15       0  4979.3     .07       0  5016.3     .17       0
#XS Ineff= 2 , 0
       0  4667.7  250.91               0
Permanent Ineff=
       F       F
Bank Sta=4979.3,5016.3
XS Rating Curve= 0 ,0
Exp/Cntr=0.3,0.1

Type RM Length L Ch R = 1 ,1999    ,500,500,500
BEGIN DESCRIPTION:
SAND BRANCH NO 2 4.0
END DESCRIPTION:
XS GIS Cut Line= 3
      3747340.23     10166864.47      3748062.56     10166076.71
       3748100.6     10165675.21
#Sta/Elev= 30
  3931.2  271.88  4243.4  256.38  4264.4  256.68    4286  254.87    4413  250.75
  4491.3  246.78  4533.3  246.39  4554.8  247.39  4646.7  246.05  4710.2  247.23
  4731.8  244.87  4738.6  246.48  4752.8  247.09  4831.1  247.53  4972.3  246.35
  4979.7  245.58  4986.5  245.23  4991.3  239.33    4996  239.33  5006.9  242.54
  5015.7  243.95  5025.8  244.16  5035.8  245.86    5076  248.75  5116.2  252.96
  5206.6  258.37  5236.7  261.73  5256.8  261.91  5286.9  264.28  5403.3  267.58
#Mann= 3 , 0 , 0
  3931.2     .17       0  4979.7     .07       0  5035.8     .17       0
Bank Sta=4979.7,5035.8
XS Rating Curve= 0 ,0
Exp/Cntr=0.3,0.1

Type RM Length L Ch R = 1 ,1499    ,499,499,499
BEGIN DESCRIPTION:
SAND BRANCH NO 2 3.0
END DESCRIPTION:
XS GIS Cut Line= 3
      3747394.93     10166916.53      3748352.03     10166429.03
       3748491.3     10165846.24
#Sta/Elev= 30
  3925.9  269.65  4075.1  265.59  4108.8  263.32  4208.7  260.42  4303.3  254.91
  4408.9  250.98  4475.6  246.22  4525.7  244.35  4570.2  245.29  4692.3  243.68
  4786.9  245.09  4803.6  243.03  4815.8  245.05  4852.7  244.63  4914.3  243.68
  4987.1  244.34  4994.9  241.14    5000  241.14  5000.9  238.96  5005.6  238.96
  5018.5  243.77  5092.6  243.89  5171.6  248.07    5183  249.78  5234.4  252.67
    5345  257.11  5357.8  258.57  5501.7  263.61  5523.6  265.21  5599.2  267.18
#Mann= 5 ,-1 , 0
  3925.9     .15       0  4852.7     .17       0  4914.3     .11       0
  4987.1     .09       0  5018.5     .11       0
Bank Sta=4987.1,5018.5
XS Rating Curve= 0 ,0
Exp/Cntr=0.3,0.1

Type RM Length L Ch R = 1 ,1000    ,500,500,500
BEGIN DESCRIPTION:
SAND BRANCH NO 2 2.0
END DESCRIPTION:
XS GIS Cut Line= 3
      3747426.24     10166955.57      3748761.09     10166449.95
      3748559.01      10165861.8
#Sta/Elev= 30
  3572.6  268.15  3685.4  265.88  3745.7  262.48  3873.7  258.89  3935.4     255
  4044.8  250.99  4141.1  244.17  4354.9  242.89  4440.5  244.08  4476.2  241.48
  4525.9  243.81  4568.8  242.65  4701.4  243.81  4889.6  243.03  4921.3  242.71
  4926.6  240.92  4932.4  242.18    4987  242.01  4995.6  239.63  5002.1  239.63
    5007  237.36    5020  239.51  5030.6  238.46  5051.3  242.39  5056.6  240.71
  5062.3  242.39  5125.7   241.1    5244  249.95    5369   256.9  5621.9  267.02
#Mann= 3 , 0 , 0
  3572.6     .11       0    4987     .09       0  5051.3     .11       0
#XS Ineff= 2 ,-1
  4183.8  4119.7  244.69  4440.5  4226.6  244.08
Permanent Ineff=
       F       F
Bank Sta=4987,5051.3
XS Rating Curve= 0 ,0
Exp/Cntr=0.3,0.1

Type RM Length L Ch R = 1 ,500     ,428,428,428
BEGIN DESCRIPTION:
SAND BRANCH NO 2 1.0
END DESCRIPTION:
XS GIS Cut Line= 3
      3747780.39     10167059.75      3749092.88      10166791.6
      3749017.49     10166365.22
#Sta/Elev= 30
  3660.4  256.04  3726.4  253.48  3821.1  252.28  3851.7  250.66  3933.5  250.11
  3953.8  248.57  4035.5  247.12  4106.9  244.37  4137.5  242.21  4188.6  241.24
    4209  241.84    4260  240.78  4290.6  242.28    4311  241.57  4351.9  242.61
  4464.1  240.11  4675.6  238.89  4872.4  238.86  4978.6  239.94  4992.5  235.47
  4997.2  235.47    5000  236.77  5010.7  236.28    5031  240.22  5062.1  240.96
  5142.7  238.68  5175.3  239.15  5288.6  246.09  5376.3   253.1    5433   254.5
#Mann= 3 , 0 , 0
  3660.4     .11       0  4978.6     .06       0    5031     .11       0
Bank Sta=4978.6,5031
XS Rating Curve= 0 ,0
Exp/Cntr=0.3,0.1

Type RM Length L Ch R = 1 ,72      ,0,0,0
XS GIS Cut Line= 5
      3747796.46     10167077.43      3749300.22     10166960.16
      3749372.74     10166756.25      3749373.87     10166683.25
      3749083.21     10166415.17
#Sta/Elev= 30
       0  254.93   101.7  253.27   111.7  251.96   171.9  250.27     271  249.02
   412.6  244.48   462.8  244.57   563.1  241.08   664.5  241.84   743.6  240.16
   994.4  239.65    1043  240.53  1094.7  239.16  1124.8  240.27    1185  238.54
  1345.5  238.71  1395.6  237.55  1431.5  238.99  1465.8  237.04  1495.9   238.4
  1699.5  237.27  1724.7  238.88  1739.9  235.04  1759.9  239.13  1796.3   238.2
  1846.3  243.83  1895.6  246.94    2051  244.84  2115.1  246.87  2192.5  251.44
#Mann= 3 , 0 , 0
       0     .11       0  1724.7     .06       0  1759.9     .11       0
Bank Sta=1724.7,1759.9
XS Rating Curve= 0 ,0
Exp/Cntr=0.3,0.1

Chan Stop Cuts=-1
Use User Specified Reach Order=0
Composite Channel Slope=5