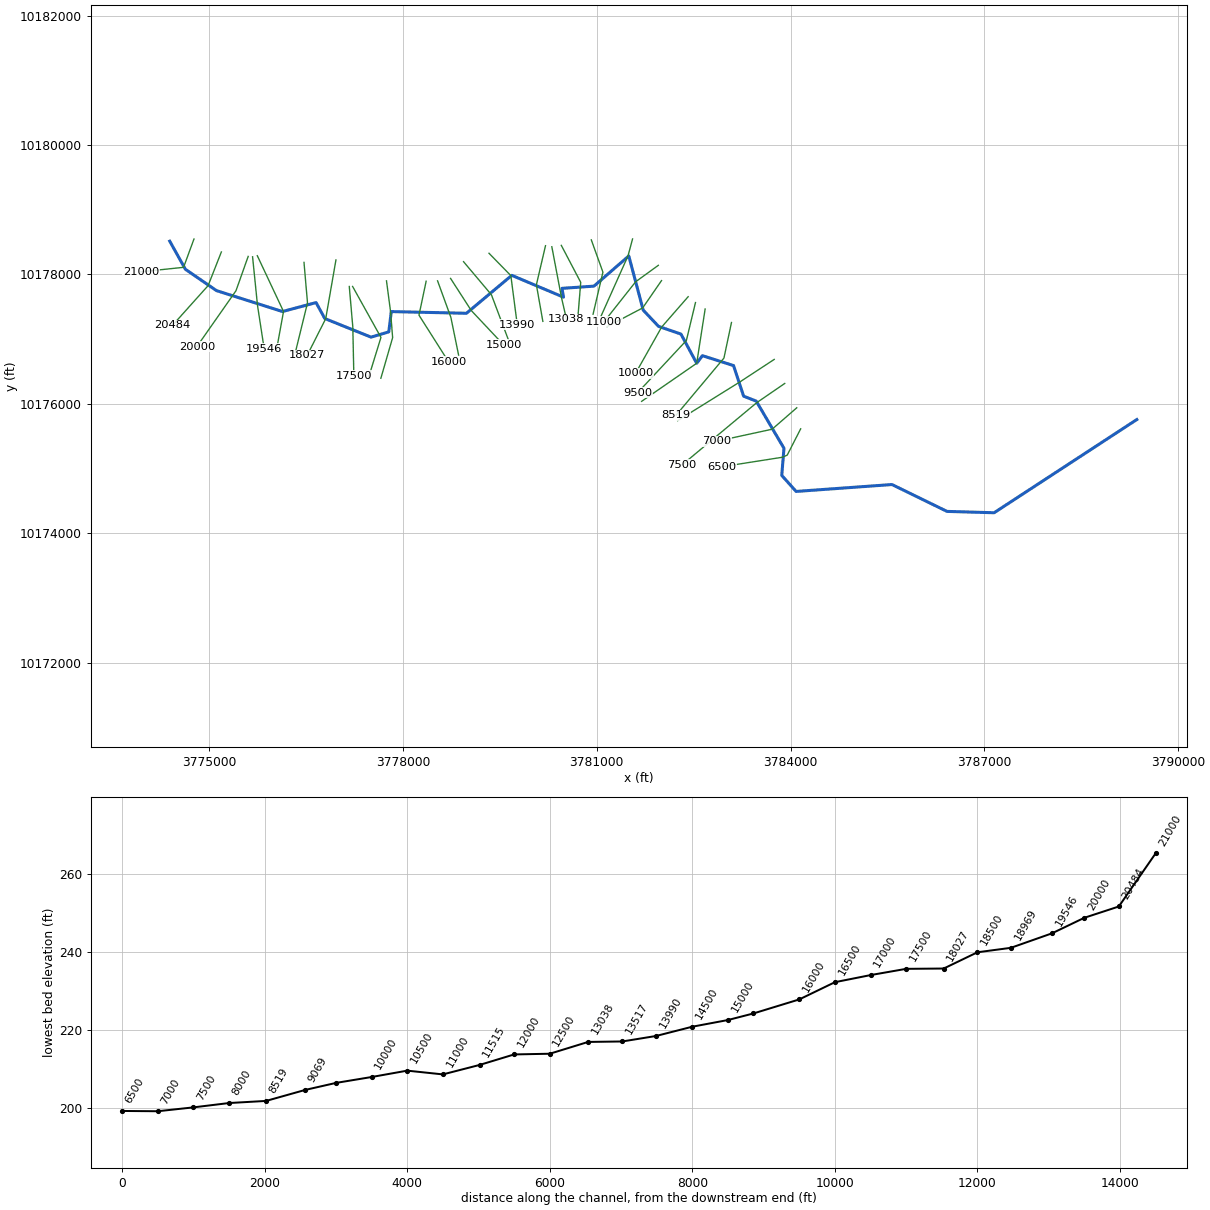
--- SAND BRANCH NO 3.prj (project) ---

Proj Title=SAND BRANCH NO 3 Base Level Engineering
Current Plan=p01
Default Exp/Contr=0.3,0.1
English Units
Geom File=g01
Flow File=f01
Plan File=p01
Y Axis Title=Elevation
X Axis Title(PF)=Main Channel Distance
X Axis Title(XS)=Station
BEGIN DESCRIPTION:
SAND BRANCH NO 3
END DESCRIPTION:
DSS Export Rating Curves= 0
DSS Export Rating Curve Sorted= 0
DSS Export Volume Flow Curves= 0
DXF OffsetX= 0
DXF OffsetY= 0
DXF ScaleX= 1
DXF ScaleY= 10

--- SAND BRANCH NO 3.p01 (plan) ---

Plan Title=Multiple Run
Short Identifier=Multiple
Geom File=g01
Flow File=f01
Subcritical Flow
K Sum by GR= 0
Std Step Tol= 0.01
Critical Tol= 0.01
Num of Std Step Trials= 20
Max Error Tol= 0.3
Flow Tol Ratio= 0.001
Split Flow NTrial= 30
Split Flow Tol= 0.02
Split Flow Ratio= 0.02
Log Output Level= 0
Friction Slope Method= 1
Unsteady Friction Slope Method= 2
Unsteady Bridges Friction Slope Method= 1
Parabolic Critical Depth
Global Vel Dist=  1 , 1 , 1
Global Log Level= 0
CheckData=True
Encroach Param= -1, 0, 0, 0
BEGIN DESCRIPTION:
Multiple Run
END DESCRIPTION:

--- SAND BRANCH NO 3.f01 (steady flow) ---

Flow Title=Multiple
Program Version=4.10
Number of Profiles= 7
Profile Names=10-year,25-year,50-year,1pct_min,100-year,1pct_plu,500-year
River Rch & RM=SAND BRANCH NO 3,Reach-1         ,21000
     257     334     439     191     577    1743    1030
River Rch & RM=SAND BRANCH NO 3,Reach-1         ,20484
     901    1246    1710     771    2328    7030    4465
River Rch & RM=SAND BRANCH NO 3,Reach-1         ,13517
    1065    1469    2007     900    2718    8208    5158
River Rch & RM=SAND BRANCH NO 3,Reach-1         ,4500
    1394    1928    2639    1184    3575   10796    6785
Boundary for River Rch & Prof#=SAND BRANCH NO 3,Reach-1         , 1
Up Type= 0
Dn Type= 3
Dn Slope=0.005
Boundary for River Rch & Prof#=SAND BRANCH NO 3,Reach-1         , 2
Up Type= 0
Dn Type= 3
Dn Slope=0.005
Boundary for River Rch & Prof#=SAND BRANCH NO 3,Reach-1         , 3
Up Type= 0
Dn Type= 3
Dn Slope=0.005
Boundary for River Rch & Prof#=SAND BRANCH NO 3,Reach-1         , 4
Up Type= 0
Dn Type= 3
Dn Slope=0.005
Boundary for River Rch & Prof#=SAND BRANCH NO 3,Reach-1         , 5
Up Type= 0
Dn Type= 3
Dn Slope=0.005
Boundary for River Rch & Prof#=SAND BRANCH NO 3,Reach-1         , 6
Up Type= 0
Dn Type= 3
Dn Slope=0.005
Boundary for River Rch & Prof#=SAND BRANCH NO 3,Reach-1         , 7
Up Type= 0
Dn Type= 3
Dn Slope=0.005
DSS Import GetInterval= 0
DSS Import GetPeak= 0
DSS Import FillOption= 0

--- SAND BRANCH NO 3.g01 (geometry) ---

Geom Title=Existing Conditions
Program Version=4.10

River Reach=SAND BRANCH NO 3,Reach-1
Reach XY= 30
      3774392.86     10178514.04      3774636.01     10178079.22
       3775116.7     10177749.64      3776137.45     10177426.72
      3776657.57     10177564.83       3776792.8     10177318.43
      3777508.28     10177031.08      3777782.88     10177112.19
      3777821.47     10177425.79      3778984.57     10177399.62
      3779686.55     10177985.63      3780486.68     10177648.55
      3780462.63     10177784.91      3780958.22     10177819.02
      3781496.78     10178285.58      3781719.97     10177448.39
      3781957.13     10177197.68      3782304.05     10177078.19
      3782547.76     10176627.27      3782635.91     10176744.79
      3783117.66     10176591.61      3783273.84     10176118.94
      3783469.11     10176042.56      3783898.04      10175313.6
      3783864.17     10174894.38      3784085.75     10174646.83
      3785570.11     10174753.44       3786421.3      10174338.4
      3787150.46     10174317.56      3789358.24     10175757.61

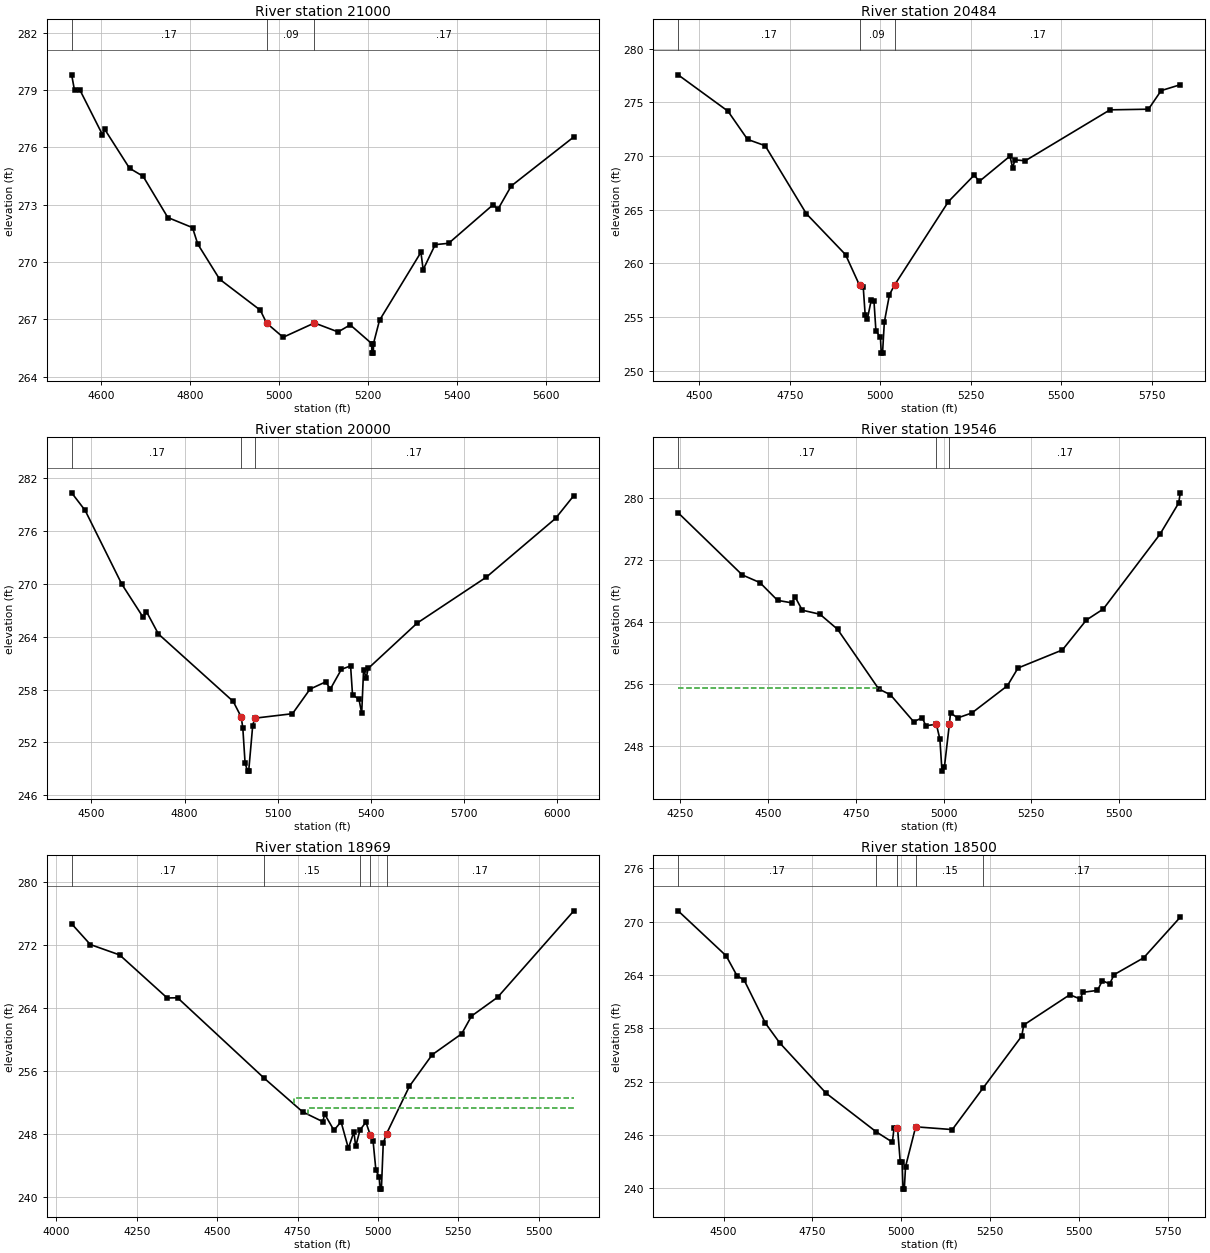
Type RM Length L Ch R = 1 ,21000   ,516,516,516
BEGIN DESCRIPTION:
SAND BRANCH NO 3 38.0
END DESCRIPTION:
XS GIS Cut Line= 3
      3774768.15     10178547.16      3774607.22     10178109.73
      3773947.85     10178040.49
#Sta/Elev= 30
  4533.9   279.8  4540.4  278.98  4552.8  278.99  4603.1  276.67  4608.4  276.94
    4664  274.91  4694.5  274.49  4750.1  272.33  4805.7   271.8  4817.4  270.94
  4866.6   269.1    4958  267.48  4972.3   266.8  5009.4  266.06  5079.8  266.81
  5132.9  266.34  5160.2  266.71  5208.5  265.73  5208.8  265.23  5212.3  265.23
  5212.5  265.73  5226.1  266.95  5319.2  270.51  5324.2   269.6  5351.3  270.91
  5381.5  270.98    5482  273.01  5492.1  272.75  5522.2  273.98    5663  276.55
#Mann= 3 , 0 , 0
  4533.9     .17       0  4972.3     .09       0  5079.8     .17       0
Bank Sta=4972.3,5079.8
XS Rating Curve= 0 ,0
Exp/Cntr=0.3,0.1

Type RM Length L Ch R = 1 ,20484   ,484,484,484
BEGIN DESCRIPTION:
SAND BRANCH NO 3 37.0
END DESCRIPTION:
XS GIS Cut Line= 3
      3775192.03      10178347.3      3774987.18     10177827.29
      3774433.75     10177210.88
#Sta/Elev= 30
  4441.1  277.55  4578.7  274.17  4632.9  271.54  4681.6  270.95  4795.3  264.62
  4903.6  260.81  4942.2  257.96  4952.4  257.84  4957.8  255.21  4963.7  254.79
  4974.4  256.54  4982.2  256.46  4987.5  253.73    5000   253.1  5002.3  251.64
  5005.8  251.64  5010.8  254.53    5025  257.09  5039.2  257.99  5187.9  265.75
    5259  268.21  5273.2  267.63  5357.8  269.98  5365.1  268.91  5371.8  269.63
  5400.2  269.55  5634.2  274.29  5740.4  274.35  5775.5  276.08  5828.4  276.63
#Mann= 3 , 0 , 0
  4441.1     .17       0  4942.2     .09       0  5039.2     .17       0
Bank Sta=4942.2,5039.2
XS Rating Curve= 0 ,0
Exp/Cntr=0.3,0.1

Type RM Length L Ch R = 1 ,20000   ,454,454,454
BEGIN DESCRIPTION:
SAND BRANCH NO 3 36.0
END DESCRIPTION:
XS GIS Cut Line= 3
      3775607.09     10178278.29      3775417.95     10177747.17
      3774812.07     10176883.37
#Sta/Elev= 30
  4436.2   280.3  4479.8   278.3  4597.8  269.95  4666.8  266.18  4677.4  266.83
  4715.8   264.3  4957.1  256.65  4982.7  254.89    4988  253.64  4995.3  249.65
  5003.4  248.75  5006.9  248.75  5019.7  253.85    5026  254.75  5148.1  255.26
  5204.7  258.05  5255.3  258.87  5270.1  258.05  5305.8  260.29  5335.4  260.68
  5341.6  257.42  5362.5  256.88  5371.2  255.31  5377.3  260.24    5386  259.36
  5392.1  260.39  5549.9  265.53    5773  270.74  5996.1   277.4  6055.1  279.99
#Mann= 3 , 0 , 0
  4436.2     .17       0  4982.7     .09       0    5026     .17       0
#XS Ineff= 3 ,-1
  5204.7  5255.3  258.05  5255.3  5305.8  258.87  5335.4    5413  260.68
Permanent Ineff=
       F       F       F
Bank Sta=4982.7,5026
XS Rating Curve= 0 ,0
Exp/Cntr=0.3,0.1

Type RM Length L Ch R = 1 ,19546   ,577,577,577
BEGIN DESCRIPTION:
SAND BRANCH NO 3 35.0
END DESCRIPTION:
XS GIS Cut Line= 3
        3775675.     10178272.87      3775751.37     10177520.74
      3775853.98     10176854.19
#Sta/Elev= 30
    4244   278.1  4426.7  270.08    4477  269.09  4527.2   266.8  4567.5  266.48
  4577.5  267.22  4597.6  265.53  4647.9  265.01  4698.1  263.07  4815.2  255.38
  4848.9  254.61    4915  251.14  4939.4  251.66  4949.4  250.63  4979.6  250.81
  4989.6  248.89  4995.6  244.77  5002.4  245.27 5016.64  250.83  5019.9  252.29
  5040.1  251.63  5080.6  252.27  5181.8  255.78  5212.1  258.07  5338.5   260.4
  5406.8  264.26    5455  265.68  5616.8  275.35  5669.7  279.35  5674.4  280.67
#Mann= 3 , 0 , 0
    4244     .17       0  4979.6     .09       0 5016.64     .17       0
#XS Ineff= 2 , 0
       0  4820.2  255.52               0
Permanent Ineff=
       F       F
Bank Sta=4979.6,5016.64
XS Rating Curve= 0 ,0
Exp/Cntr=0.3,0.1

Type RM Length L Ch R = 1 ,18969   ,469,469,469
BEGIN DESCRIPTION:
SAND BRANCH NO 3 34.0
END DESCRIPTION:
XS GIS Cut Line= 3
      3775748.34     10178289.15      3776154.09      10177427.4
      3776044.38     10176827.96
#Sta/Elev= 30
  4047.5  274.74  4105.6  272.11  4196.8  270.79  4344.6  265.33    4377  265.35
  4647.2  255.11  4765.9  250.87  4828.7  249.62  4834.2  250.59  4863.3  248.53
  4885.4  249.61  4908.1  246.25  4925.4  248.34  4930.9  246.48  4944.4  248.58
  4962.8  249.56  4976.5  247.89  4984.9   247.2  4993.8  243.45  5004.1  242.62
  5007.4  241.06  5010.9  241.06  5016.6  246.87  5026.8  248.08  5097.9  254.11
  5168.8  258.12  5260.6  260.78  5291.1  263.03  5372.4  265.42  5609.4  276.39
#Mann= 5 ,-1 , 0
  4047.5     .17       0  4647.2     .15       0  4944.4     .17       0
  4976.5     .09       0  5026.8     .17       0
#XS Ineff= 2 ,-1
  4783.1  4737.5  251.39  4737.5  4708.6  252.58
Permanent Ineff=
       F       F
Bank Sta=4976.5,5026.8
XS Rating Curve= 0 ,0
Exp/Cntr=0.3,0.1

Type RM Length L Ch R = 1 ,18500   ,473,473,473
BEGIN DESCRIPTION:
SAND BRANCH NO 3 33.0
END DESCRIPTION:
XS GIS Cut Line= 3
      3776470.79     10178185.95      3776524.99     10177560.29
       3776337.7     10176798.06
#Sta/Elev= 30
    4372  271.23  4507.1  266.17  4537.5  263.94  4557.6  263.45  4617.8  258.58
  4657.9  256.37  4788.4  250.71  4929.6  246.36  4974.7  245.21  4979.7  246.83
  4989.2  246.85  4997.1  242.92  5002.2  242.92  5004.9  239.92  5008.4  239.92
  5011.8  242.44  5040.4  246.93  5143.4  246.62    5231  251.35    5339  257.15
  5344.2  258.38    5474  261.79  5503.8   261.3  5510.4  262.06  5551.9  262.28
  5565.6  263.37  5586.2  263.01  5598.6  264.05  5681.7  265.94  5784.9  270.52
#Mann= 5 ,-1 , 0
    4372     .17       0  4929.6     .15       0  4989.2     .09       0
  5040.4     .15       0    5231     .17       0
Bank Sta=4989.2,5040.4
XS Rating Curve= 0 ,0
Exp/Cntr=0.3,0.1

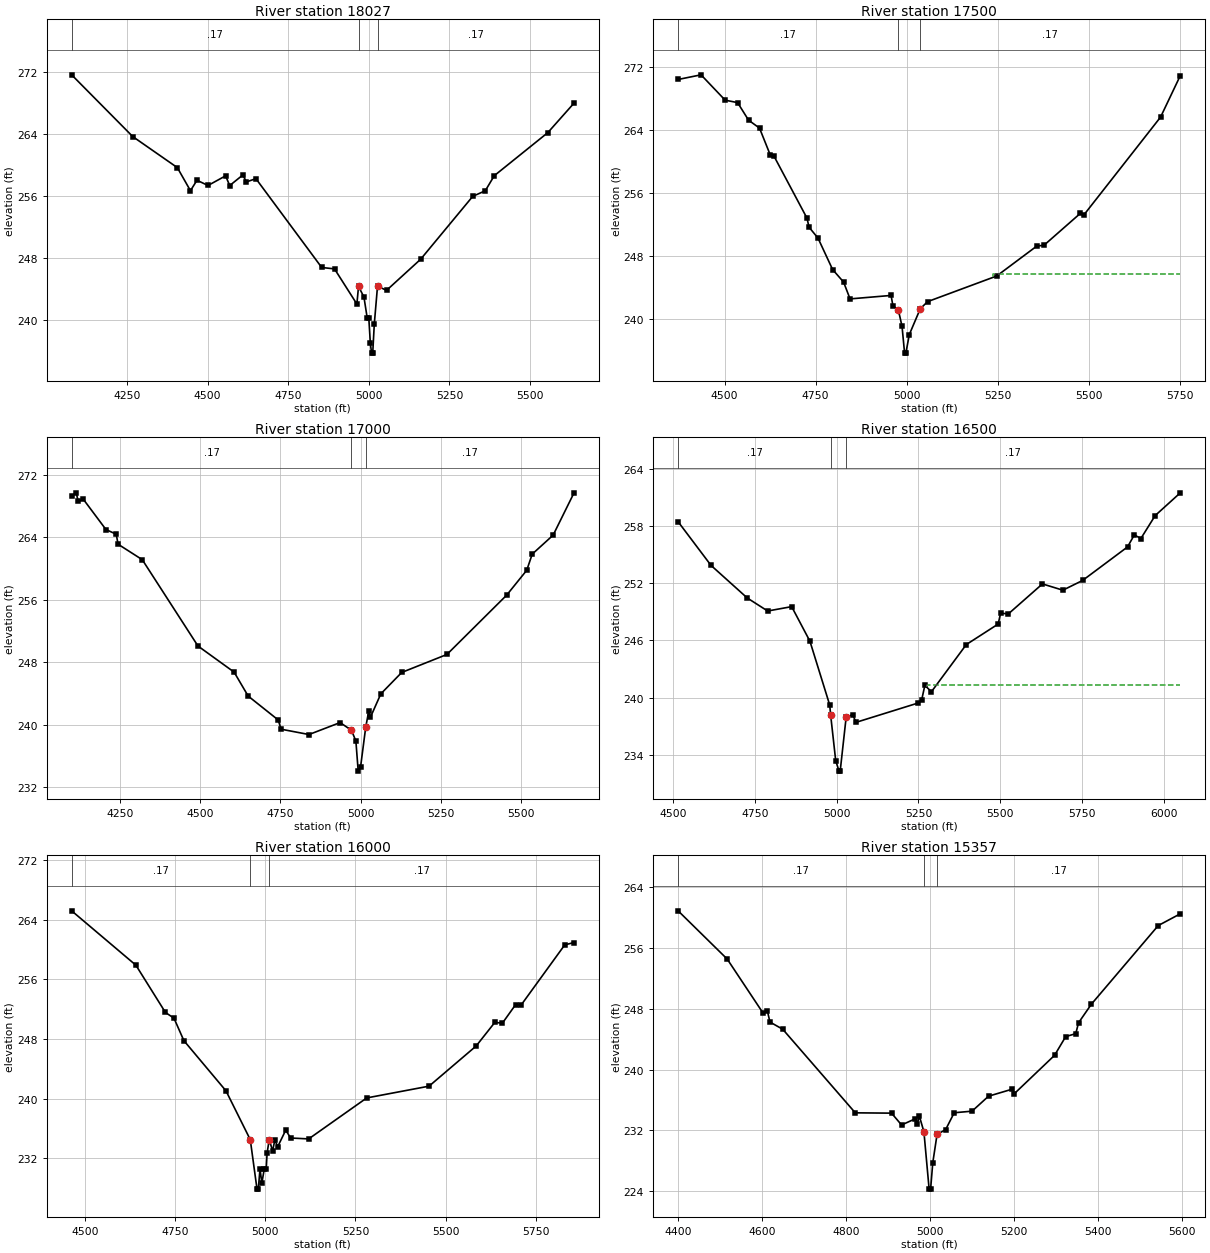
Type RM Length L Ch R = 1 ,18027   ,527,527,527
BEGIN DESCRIPTION:
SAND BRANCH NO 3 32.0
END DESCRIPTION:
XS GIS Cut Line= 3
       3776965.1     10178223.96      3776807.13      10177316.3
      3776519.68     10176749.19
#Sta/Elev= 30
  4078.7   271.6  4268.1  263.65  4406.4  259.65    4447  256.68  4467.3  258.02
  4501.5  257.35    4556  258.59  4568.8  257.34  4609.4   258.7  4620.7  257.81
    4650  258.23    4854  246.79  4893.7  246.61  4963.1  242.08  4968.2  244.35
    4985  242.98    4995  240.32    5000  240.32  5004.9     237  5008.7  235.76
  5012.2  235.76  5017.1  239.51  5027.1  244.39    5055  243.84  5160.8  247.85
  5322.3  255.95  5361.2  256.67  5389.1  258.61  5555.2  264.16  5635.8  267.93
#Mann= 3 , 0 , 0
  4078.7     .17       0  4968.2     .09       0  5027.1     .17       0
Bank Sta=4968.2,5027.1
XS Rating Curve= 0 ,0
Exp/Cntr=0.3,0.1

Type RM Length L Ch R = 1 ,17500   ,500,500,500
BEGIN DESCRIPTION:
SAND BRANCH NO 3 31.0
END DESCRIPTION:
XS GIS Cut Line= 3
      3777171.53     10177813.83      3777226.11     10177188.71
      3777242.14     10176436.88
#Sta/Elev= 30
  4372.5  270.45  4435.5  271.04  4501.7  267.82  4535.9  267.51    4566  265.28
  4596.1  264.27  4626.2  260.79  4636.3  260.67  4726.6  252.82  4732.1  251.68
  4756.7   250.3  4796.9   246.3    4827  244.71  4844.8  242.57  4957.5  243.01
  4962.5  241.71  4977.6  241.15  4987.6  239.08  4994.6  235.68  4998.1  235.68
  5007.6  238.04  5037.6  241.31  5057.7  242.22  5247.7  245.48  5357.7  249.28
  5377.7  249.39  5477.7  253.45  5487.8  253.28  5697.8  265.67    5752  270.94
#Mann= 3 , 0 , 0
  4372.5     .17       0  4977.6     .09       0  5037.6     .17       0
#XS Ineff= 2 , 0
       0                  5237.7       0  245.79
Permanent Ineff=
       F       F
Bank Sta=4977.6,5037.6
XS Rating Curve= 0 ,0
Exp/Cntr=0.3,0.1

Type RM Length L Ch R = 1 ,17000   ,500,500,500
BEGIN DESCRIPTION:
SAND BRANCH NO 3 30.0
END DESCRIPTION:
XS GIS Cut Line= 3
      3777223.11      10177813.9       3777661.6     10177026.46
      3777464.86      10176390.7
#Sta/Elev= 30
  4098.7  269.27  4113.2  269.67  4118.9  268.57  4134.9  268.86  4205.8  264.97
  4237.8  264.38  4243.5   263.1    4319  261.12  4492.8  250.08  4605.6  246.74
  4649.4  243.68  4742.9  240.63  4752.3  239.44  4839.2  238.76  4936.3  240.29
  4971.8   239.3  4985.5  237.92  4992.7  234.08    5000  234.58  5016.1  239.67
  5025.5  241.74  5030.7  240.95  5063.3  243.96  5128.5   246.7  5269.5     249
  5455.8  256.58  5518.6  259.77  5535.6  261.83  5600.9  264.26  5665.5  269.62
#Mann= 3 , 0 , 0
  4098.7     .17       0  4971.8     .09       0  5016.1     .17       0
#XS Ineff= 2 , 0
       0                  5063.3       0  243.96
Permanent Ineff=
       F       F
Bank Sta=4971.8,5016.1
XS Rating Curve= 0 ,0
Exp/Cntr=0.3,0.1

Type RM Length L Ch R = 1 ,16500   ,500,500,500
BEGIN DESCRIPTION:
SAND BRANCH NO 3 29.0
END DESCRIPTION:
XS GIS Cut Line= 4
      3777747.32     10177900.77      3777810.98     10177419.86
      3777842.38      10177023.5       3777660.4     10176396.06
#Sta/Elev= 30
  4514.9  258.49  4615.5   253.9  4726.4  250.47  4788.8   249.1  4862.2  249.56
  4918.1  245.92  4978.6  239.21 4981.43  238.16  4996.9  233.36  5007.1  232.26
  5010.6  232.26  5028.9  237.95  5048.9   238.2    5059  237.39  5249.6  239.43
  5259.6  239.71  5269.6  241.28  5289.7  240.61  5396.3  245.57  5493.8  247.73
  5501.3  248.87  5525.1   248.8  5629.2  251.95  5691.7  251.29  5751.9  252.31
  5889.5  255.84  5910.3  257.11  5930.2  256.72  5974.1  259.14  6050.9  261.53
#Mann= 3 , 0 , 0
  4514.9     .17       0 4981.43     .09       0  5028.9     .17       0
#XS Ineff= 2 , 0
       0                  5275.8       0  241.34
Permanent Ineff=
       F       F
Bank Sta=4981.43,5028.9
XS Rating Curve= 0 ,0
Exp/Cntr=0.3,0.1

Type RM Length L Ch R = 1 ,16000   ,643,643,643
BEGIN DESCRIPTION:
SAND BRANCH NO 3 28.0
END DESCRIPTION:
XS GIS Cut Line= 3
      3778361.15     10177895.37      3778250.13     10177370.37
      3778708.79     10176648.69
#Sta/Elev= 30
  4463.4   265.2  4641.5   257.9  4723.3  251.56    4747  250.79  4774.4  247.78
  4891.1  241.04  4958.4  234.49  4977.1  227.85  4980.6  227.85  4985.4  230.55
  4990.5  228.67  4997.1  230.52  5002.5  230.52  5005.1  232.72    5011  234.51
  5020.3  232.96  5026.3  234.41  5034.7  233.57  5056.7  235.77  5070.3  234.71
  5120.3  234.59  5281.2  240.09  5453.9  241.67  5584.4  247.06    5636  250.22
  5657.2  250.13  5693.6   252.6  5708.8  252.54  5829.9  260.63  5855.1  260.94
#Mann= 3 , 0 , 0
  4463.4     .17       0  4958.4     .09       0    5011     .17       0
#XS Ineff= 2 , 0
       0                  5265.9       0  239.55
Permanent Ineff=
       F       F
Bank Sta=4958.4,5011
XS Rating Curve= 0 ,0
Exp/Cntr=0.3,0.1

Type RM Length L Ch R = 1 ,15357   ,357,357,357
BEGIN DESCRIPTION:
SAND BRANCH NO 3 27.0
END DESCRIPTION:
XS GIS Cut Line= 3
      3778537.67     10177900.81      3778743.56     10177336.81
      3778863.22     10176753.77
#Sta/Elev= 30
  4399.6  260.92  4516.4  254.57  4601.6  247.47  4612.2  247.72  4618.2  246.27
  4648.7  245.32  4821.4  234.31  4907.7  234.27  4931.6  232.71  4963.5  233.51
  4968.8  232.89  4974.2  233.83  4984.8  231.81  4997.2  224.26  5000.7  224.26
  5005.9  227.74  5016.1  231.47  5036.5   232.1  5056.9  234.32  5099.4  234.53
  5138.6   236.5  5195.1  237.43  5200.2  236.84  5295.9  241.89  5322.3  244.35
  5346.3  244.74  5352.9  246.17  5383.6  248.63  5542.7  258.98  5595.2  260.53
#Mann= 3 , 0 , 0
  4399.6     .17       0  4984.8     .09       0  5016.1     .17       0
Bank Sta=4984.8,5016.1
XS Rating Curve= 0 ,0
Exp/Cntr=0.3,0.1

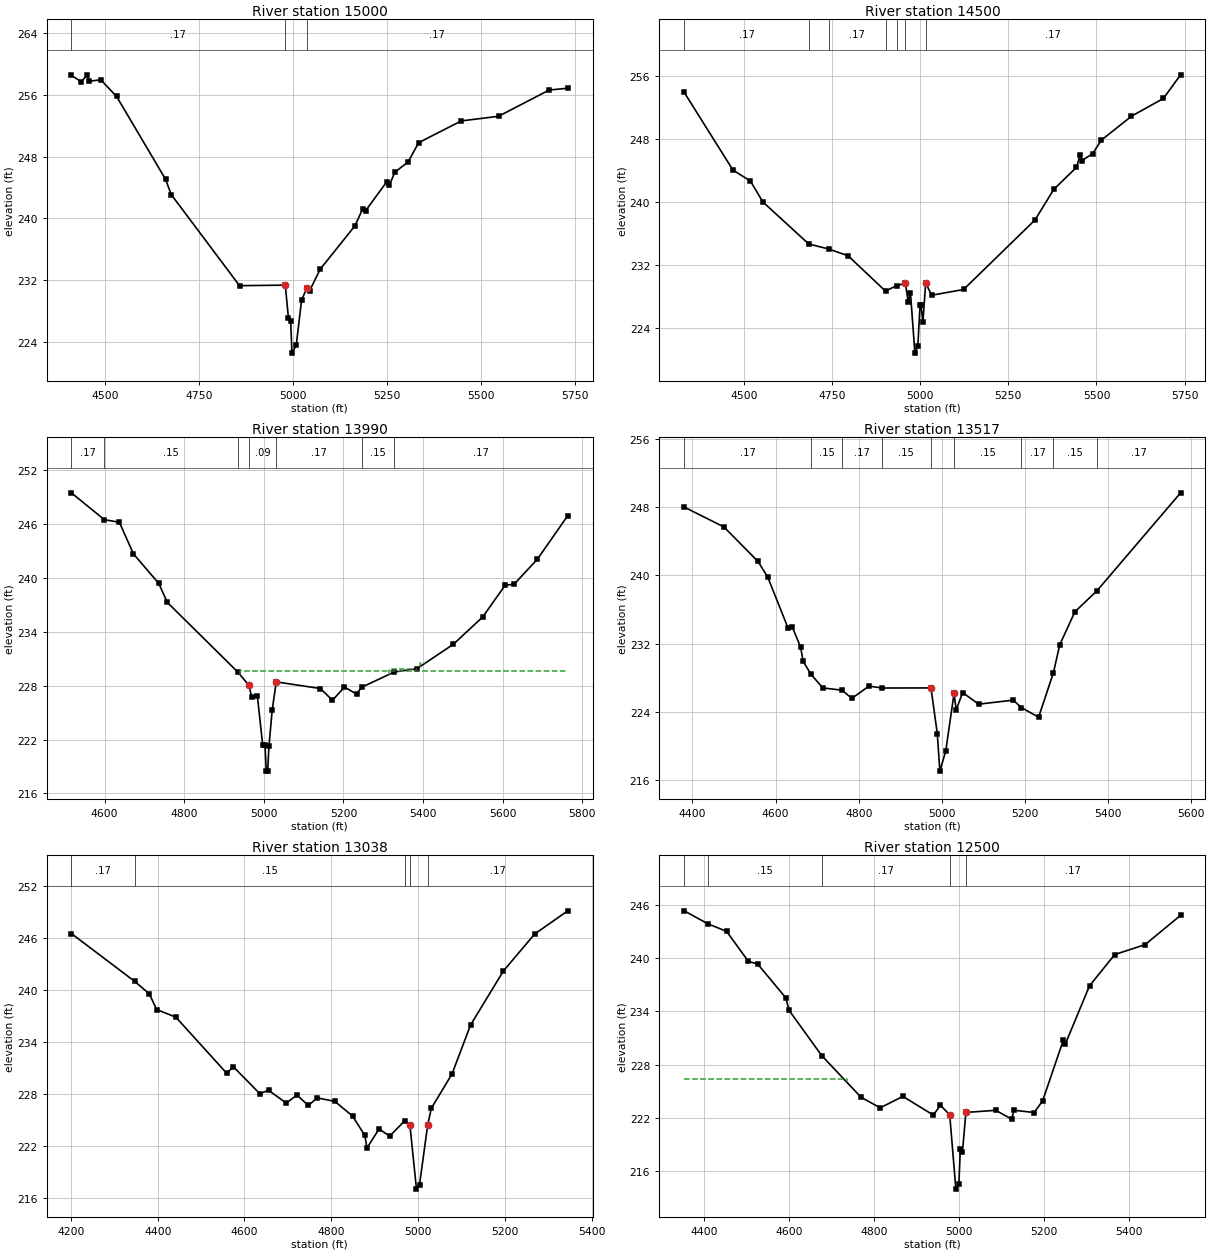
Type RM Length L Ch R = 1 ,15000   ,500,500,500
BEGIN DESCRIPTION:
SAND BRANCH NO 3 26.0
END DESCRIPTION:
XS GIS Cut Line= 3
      3778738.67      10177938.8       3779058.5     10177443.25
       3779558.9     10176912.15
#Sta/Elev= 30
  4410.2   258.5  4436.8  257.66    4452  258.56  4457.9  257.73  4488.3  257.92
  4530.5  255.76  4660.5  245.06  4675.7  243.08  4857.2   231.3  4978.8  231.37
  4987.2  227.16  4993.1  226.78  4996.6  222.58  5008.1  223.63  5022.3  229.48
  5036.4  230.98  5043.7  230.66  5071.7  233.43  5163.9  239.03  5184.9  241.25
  5192.2  240.98  5248.8  244.74  5255.7   244.3  5269.9  245.96  5305.3  247.29
  5333.4  249.79  5446.7   252.6  5545.8   253.2  5680.1  256.59  5729.7  256.83
#Mann= 3 , 0 , 0
  4410.2     .17       0  4978.8     .09       0  5036.4     .17       0
Bank Sta=4978.8,5036.4
XS Rating Curve= 0 ,0
Exp/Cntr=0.3,0.1

Type RM Length L Ch R = 1 ,14500   ,510,510,510
BEGIN DESCRIPTION:
SAND BRANCH NO 3 25.0
END DESCRIPTION:
XS GIS Cut Line= 3
      3778939.62     10178196.86      3779371.06     10177685.83
      3779631.77     10176994.88
#Sta/Elev= 30
  4331.2  253.98  4469.4  244.11  4518.8  242.73    4554  240.08  4684.2  234.73
  4741.7  234.08  4795.8  233.23    4902  228.74  4933.4  229.45  4958.3  229.73
  4966.1  227.42  4972.6  228.53  4985.2  220.87  4993.5  221.74  4999.8  226.96
  5002.5  226.96  5007.8   224.8  5015.8  229.78  5032.6  228.22  5123.2  228.95
  5325.7  237.78  5379.2  241.68  5443.3  244.46  5453.5  246.04  5458.8  245.33
    5489  246.19  5513.9  247.92  5599.1  250.95  5689.7  253.21  5738.5  256.21
#Mann= 7 ,-1 , 0
  4331.2     .17       0  4684.2     .15       0  4741.7     .17       0
    4902     .15       0  4933.4     .17       0  4958.3     .09       0
  5015.8     .17       0
Bank Sta=4958.3,5015.8
XS Rating Curve= 0 ,0
Exp/Cntr=0.3,0.1

Type RM Length L Ch R = 1 ,13990   ,473,473,473
BEGIN DESCRIPTION:
SAND BRANCH NO 3 24.0
END DESCRIPTION:
XS GIS Cut Line= 3
      3779333.46     10178327.21      3779671.58     10177981.89
      3779770.66     10177225.25
#Sta/Elev= 30
  4516.7  249.49  4599.5   246.5  4637.3  246.21  4672.7  242.68  4736.2   239.4
  4757.5  237.29  4934.8  229.52  4962.5  228.05  4969.7   226.7  4983.8  226.87
  4997.1  221.41  5002.9  221.41  5006.1  218.49  5009.6  218.49  5012.9  221.29
    5021  225.29  5031.1  228.43    5142  227.69  5172.3  226.38  5202.5  227.85
  5232.8  227.08  5245.5  227.83    5328  229.54  5384.1  229.89  5475.9  232.62
  5549.7  235.67  5605.9  239.19  5628.6  239.32  5686.6  242.08  5763.1  246.94
#Mann= 7 ,-1 , 0
  4516.7     .17       0  4599.5     .15       0  4934.8     .17       0
  4962.5     .09       0  5031.1     .17       0  5245.5     .15       0
    5328     .17       0
#XS Ineff= 3 ,-1
  4941.4  4913.1  229.69  5313.1  5384.1  229.84    5392  5404.2  230.52
Permanent Ineff=
       F       F       F
Bank Sta=4962.5,5031.1
XS Rating Curve= 0 ,0
Exp/Cntr=0.3,0.1

Type RM Length L Ch R = 1 ,13517   ,479,479,479
BEGIN DESCRIPTION:
SAND BRANCH NO 3 23.0
END DESCRIPTION:
XS GIS Cut Line= 3
      3780208.03     10178443.96      3780066.94     10177840.33
      3780167.06     10177274.72
#Sta/Elev= 30
  4380.1     248  4475.5  245.68  4557.6  241.64    4581  239.81  4629.5  233.89
  4639.8     234  4660.3  231.58    4666  229.97  4684.8  228.44  4713.6  226.83
  4759.5  226.57  4783.6  225.61  4824.7  227.05  4855.1  226.82  4973.8  226.83
    4989  221.48  4995.2  217.09  5009.4  219.46  5029.3  226.19  5034.4  224.26
    5050  226.29  5088.4  224.93  5171.9   225.4  5191.5  224.52  5232.8  223.41
  5268.4  228.61  5283.6  231.88    5320  235.74  5373.3  238.21  5574.4  249.67
#Mann= 9 ,-1 , 0
  4380.1     .17       0  4684.8     .15       0  4759.5     .17       0
  4855.1     .15       0  4973.8     .09       0  5029.3     .15       0
  5191.5     .17       0  5268.4     .15       0  5373.3     .17       0
Bank Sta=4973.8,5029.3
XS Rating Curve= 0 ,0
Exp/Cntr=0.3,0.1

Type RM Length L Ch R = 1 ,13038   ,538,538,538
BEGIN DESCRIPTION:
SAND BRANCH NO 3 22.0
END DESCRIPTION:
XS GIS Cut Line= 3
      3780305.82     10178427.64      3780455.24     10177642.74
        3780533.     10177306.61
#Sta/Elev= 30
    4201  246.49  4346.7  240.97  4380.7  239.52  4397.5  237.71  4441.8  236.83
  4559.2  230.34  4574.2  231.11  4635.2     228  4655.6  228.38  4696.3  226.91
  4720.8  227.83  4747.2  226.63  4767.6  227.51  4808.3   227.1    4849  225.41
  4877.4  223.17  4882.4  221.72  4910.1  223.92  4934.6  223.09  4968.9  224.84
  4981.3  224.34  4996.4  216.97  5003.4  217.47  5022.2  224.36  5030.6   226.3
  5078.4  230.28  5121.1  235.93  5196.7  242.16  5268.6  246.42    5345  249.11
#Mann= 5 ,-1 , 0
    4201     .17       0  4346.7     .15       0  4968.9     .17       0
  4981.3     .09       0  5022.2     .17       0
#XS Ineff= 2 , 0
       0  4720.8  227.83               0
Permanent Ineff=
       F       F
Bank Sta=4981.3,5022.2
XS Rating Curve= 0 ,0
Exp/Cntr=0.3,0.1

Type RM Length L Ch R = 1 ,12500   ,500,500,500
BEGIN DESCRIPTION:
SAND BRANCH NO 3 21.0
END DESCRIPTION:
XS GIS Cut Line= 3
       3780452.5     10178449.37      3780753.25     10177876.97
       3780710.5     10177357.53
#Sta/Elev= 30
  4353.4  245.34  4408.5  243.89  4453.1  243.02  4504.3  239.64  4526.4  239.33
  4592.5  235.52    4600  234.12  4676.9  229.01  4769.4  224.31  4814.6  223.12
  4867.8  224.41  4939.6   222.3    4956  223.42    4978  222.33  4992.5  213.95
  4999.6  214.54  5002.9  218.45  5007.9  218.09    5016   222.6  5086.2  222.84
    5124  221.84    5129  222.85  5176.5  222.59  5196.6   223.9  5245.2  230.74
  5250.2  230.34  5306.9  236.88  5366.3  240.41  5437.4  241.52  5521.2  244.83
#Mann= 5 ,-1 , 0
  4353.4     .17       0  4408.5     .15       0  4676.9     .17       0
    4978     .09       0    5016     .17       0
#XS Ineff= 2 , 0
       0  4735.5   226.4               0
Permanent Ineff=
       F       F
Bank Sta=4978,5016
XS Rating Curve= 0 ,0
Exp/Cntr=0.3,0.1

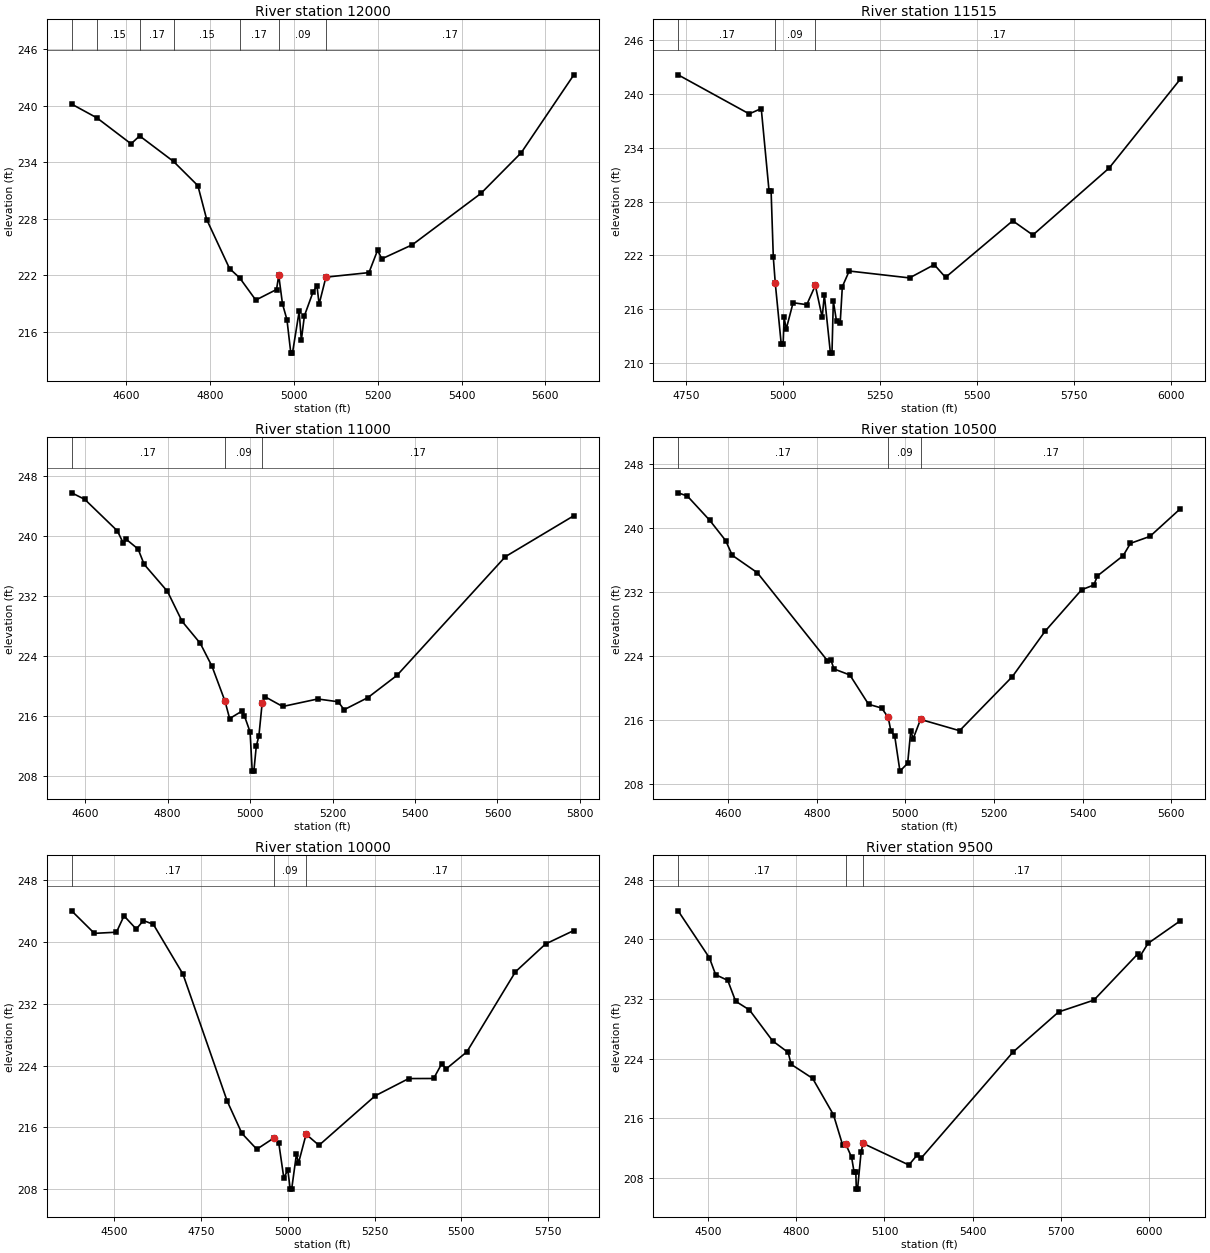
Type RM Length L Ch R = 1 ,12000   ,485,485,485
BEGIN DESCRIPTION:
SAND BRANCH NO 3 20.0
END DESCRIPTION:
XS GIS Cut Line= 3
      3780916.53     10178534.42      3781096.36     10178035.33
      3780943.91     10177385.06
#Sta/Elev= 30
  4469.5  240.15  4529.8  238.69  4611.3  235.94  4631.7  236.78  4712.7  234.07
  4770.7  231.51  4791.9  227.91  4846.3  222.73  4870.5  221.74  4908.9  219.39
  4958.4  220.51  4963.7     222  4972.6  218.99  4983.3  217.31  4992.5  213.77
  4996.4  213.77  5012.4  218.18  5017.6  215.13  5024.9  217.72  5045.5  220.24
  5054.9  220.92    5060  218.95  5076.3  221.82    5179   222.3  5199.5  224.66
  5209.8  223.76  5282.5  225.25    5446  230.68  5542.4     235  5667.9  243.25
#Mann= 7 ,-1 , 0
  4469.5     .17       0  4529.8     .15       0  4631.7     .17       0
  4712.7     .15       0  4870.5     .17       0  4963.7     .09       0
  5076.3     .17       0
#XS Ineff= 2 , 0
       0                  5199.5       0  224.66
Permanent Ineff=
       F       F
Bank Sta=4963.7,5076.3
XS Rating Curve= 0 ,0
Exp/Cntr=0.3,0.1

Type RM Length L Ch R = 1 ,11515   ,515,515,515
BEGIN DESCRIPTION:
SAND BRANCH NO 3 19.0
END DESCRIPTION:
XS GIS Cut Line= 3
      3781555.09       10178548.      3781484.65     10178286.62
      3781065.95     10177352.36
#Sta/Elev= 30
  4729.3  242.16  4912.5   237.8  4943.6  238.39  4963.8  229.15    4969  229.17
  4974.7  221.78 4979.78  218.87  4995.1  212.09    5000  212.09  5002.5  215.06
    5008  213.78  5025.7  216.71  5060.9  216.49    5083  218.64  5100.7  215.07
  5106.2  217.59  5121.9  211.08  5125.9  211.08  5129.4   216.9  5137.6  214.64
  5147.1  214.46  5152.6   218.5  5170.3  220.25  5325.8  219.48  5389.6  220.96
  5418.6  219.54  5591.8  225.86  5643.7  224.27  5840.1  231.74  6023.8  241.68
#Mann= 3 , 0 , 0
  4729.3     .17       0 4979.78     .09       0    5083     .17       0
Bank Sta=4979.78,5083
XS Rating Curve= 0 ,0
Exp/Cntr=0.3,0.1

Type RM Length L Ch R = 1 ,11000   ,500,500,500
BEGIN DESCRIPTION:
SAND BRANCH NO 3 18.0
END DESCRIPTION:
XS GIS Cut Line= 3
      3781953.65     10178140.44      3781603.01     10177886.73
      3781115.77     10177270.85
#Sta/Elev= 30
  4567.2  245.73    4599  244.86  4678.1  240.66  4692.8  238.99    4699  239.57
  4728.4  238.24  4743.1   236.2  4799.6   232.6  4835.1  228.61  4879.2  225.68
  4907.6  222.63 4939.02     218  4950.4  215.66  4979.8  216.64    4986  216.06
    5000  213.88  5005.2  208.66  5009.2  208.66    5015  211.97  5021.4  213.36
  5029.4  217.79  5035.8  218.58  5079.1  217.27    5164  218.27  5213.7   217.9
  5228.1  216.84  5285.9  218.46  5356.4  221.42  5619.3  237.23  5785.3  242.68
#Mann= 3 , 0 , 0
  4567.2     .17       0 4939.02     .09       0  5029.4     .17       0
Bank Sta=4939.02,5029.4
XS Rating Curve= 0 ,0
Exp/Cntr=0.3,0.1

Type RM Length L Ch R = 1 ,10500   ,500,500,500
BEGIN DESCRIPTION:
SAND BRANCH NO 3 17.0
END DESCRIPTION:
XS GIS Cut Line= 3
      3782003.45      10177904.9      3781711.81     10177482.61
      3781161.99     10177194.36
#Sta/Elev= 30
  4486.8  244.38  4507.6  243.98  4558.3  240.94  4594.1  238.42    4609  236.58
  4665.7   234.4  4823.9  223.42  4831.7   223.5  4838.8  222.38  4874.6  221.63
  4916.8  217.97  4946.3   217.5  4961.2  216.33  4967.2  214.64    4976  213.97
  4987.7  209.62  5005.1   210.6  5012.1  214.62  5017.7  213.69  5034.2  216.08
  5122.4  214.67  5241.6  221.43  5315.3  227.08  5397.9  232.27  5425.6  232.87
  5433.5     234  5491.8  236.53  5508.2  238.07  5552.3  238.94  5620.8  242.39
#Mann= 3 , 0 , 0
  4486.8     .17       0  4961.2     .09       0  5034.2     .17       0
Bank Sta=4961.2,5034.2
XS Rating Curve= 0 ,0
Exp/Cntr=0.3,0.1

Type RM Length L Ch R = 1 ,10000   ,500,500,500
BEGIN DESCRIPTION:
SAND BRANCH NO 3 16.0
END DESCRIPTION:
XS GIS Cut Line= 3
       3782415.6     10177655.83      3782005.46     10177186.88
      3781600.38     10176469.21
#Sta/Elev= 30
    4377  244.06  4442.5  241.14  4506.1  241.29  4527.9  243.41  4563.1   241.7
  4583.9   242.8  4612.4  242.31  4697.8  235.85    4825  219.42  4867.7  215.21
  4910.5  213.16  4959.8  214.62    4974  213.92  4988.3  209.46    5000  210.46
  5006.8  207.99    5011  207.99  5024.8  212.55  5030.5  211.34  5052.6   215.1
  5089.7  213.67  5251.5  220.08  5348.3  222.32  5420.1  222.33    5443  224.21
  5456.6  223.59  5515.8  225.78  5655.9  236.16  5742.5  239.76  5824.1  241.51
#Mann= 3 , 0 , 0
    4377     .17       0  4959.8     .09       0  5052.6     .17       0
Bank Sta=4959.8,5052.6
XS Rating Curve= 0 ,0
Exp/Cntr=0.3,0.1

Type RM Length L Ch R = 1 ,9500    ,431,431,431
BEGIN DESCRIPTION:
SAND BRANCH NO 3 15.0
END DESCRIPTION:
XS GIS Cut Line= 3
      3782528.83     10177565.25      3782388.07     10176979.53
      3781632.49     10176170.76
#Sta/Elev= 30
  4397.6  243.82  4504.2  237.51  4525.3  235.25  4566.5  234.49  4593.3  231.69
  4640.4  230.52  4719.2  226.37  4772.1  224.82  4782.4  223.22  4855.4  221.34
  4926.4  216.45  4957.3  212.43  4967.6  212.57  4988.1  210.75  4996.6  208.74
  5002.4  208.74  5004.1  206.48  5008.3  206.48  5020.4  211.47  5027.2  212.61
    5183  209.72  5211.4  211.06  5225.5  210.67  5536.7  224.84  5692.5  230.25
  5812.7  231.84  5961.2     238  5968.6  237.65  5996.9  239.45  6106.8  242.48
#Mann= 3 , 0 , 0
  4397.6     .17       0  4967.6     .09       0  5027.2     .17       0
Bank Sta=4967.6,5027.2
XS Rating Curve= 0 ,0
Exp/Cntr=0.3,0.1

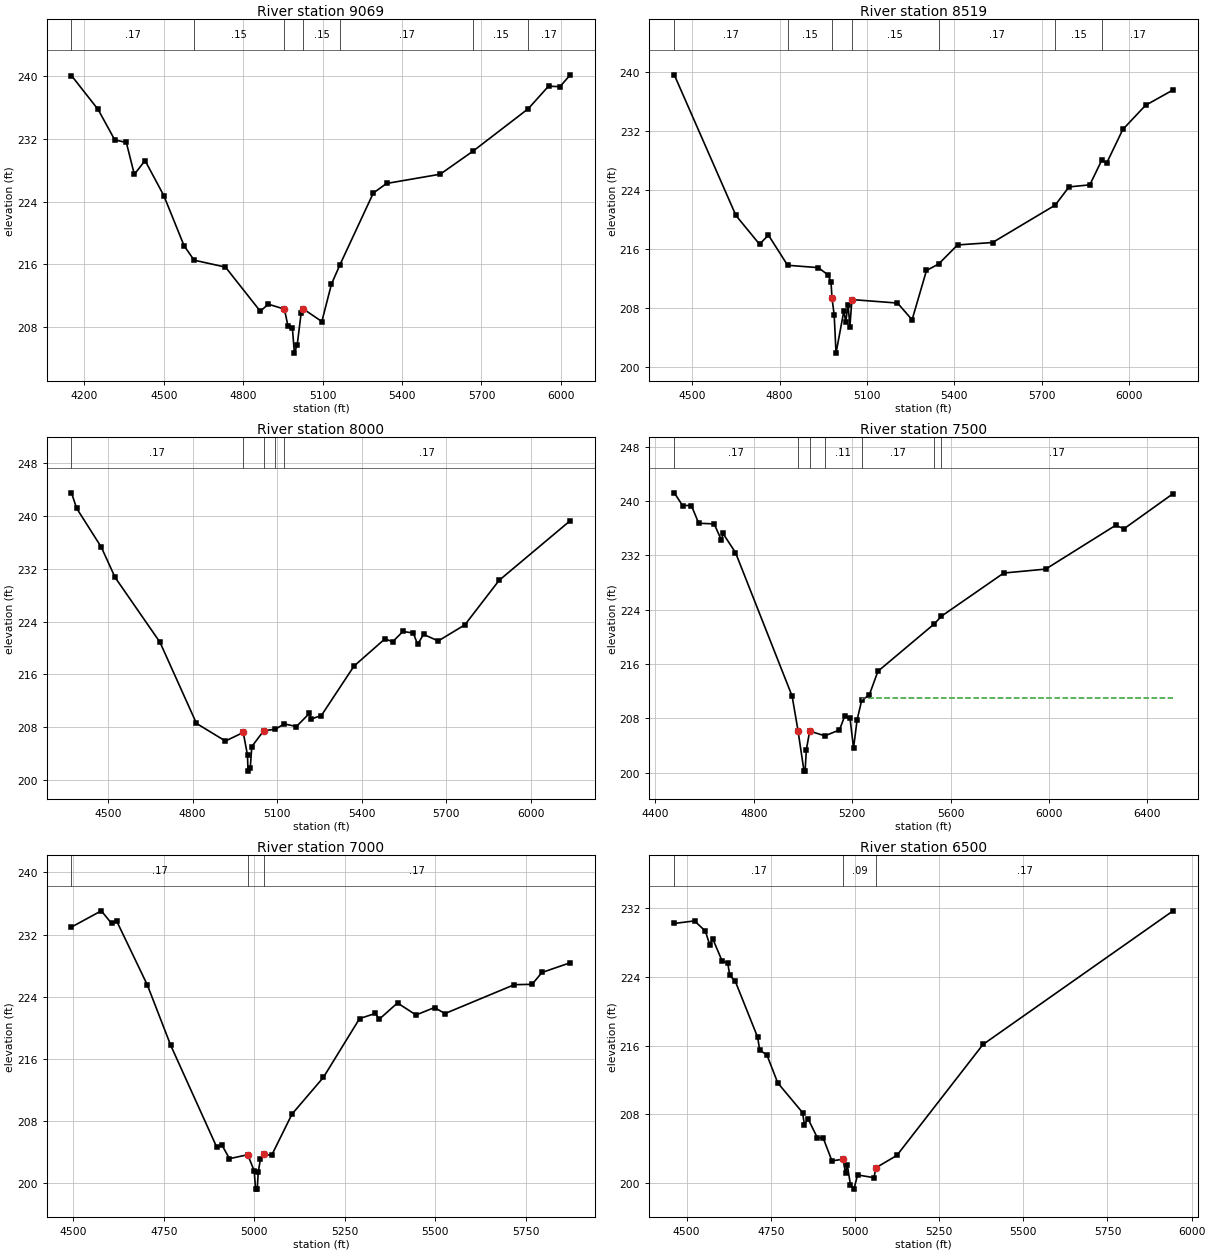
Type RM Length L Ch R = 1 ,9069    ,550,550,550
BEGIN DESCRIPTION:
SAND BRANCH NO 3 14.0
END DESCRIPTION:
XS GIS Cut Line= 3
       3782678.3     10177465.67      3782547.76     10176627.27
      3781695.48     10176038.98
#Sta/Elev= 30
  4151.5  240.07  4252.1  235.75    4315  231.87  4358.6  231.55  4388.9  227.48
  4429.4  229.24  4500.3  224.77  4576.5   218.4  4614.5  216.54    4733  215.66
  4864.6  210.03  4894.9  210.93  4955.7   210.3  4968.9  208.19    4986  207.83
  4993.4  204.69    5004  205.74  5018.9  209.78    5025  210.37  5097.1  208.72
  5133.5   213.5  5165.8  215.98  5291.5   225.1  5341.4  226.32  5544.2   227.5
  5669.3  230.47  5876.8  235.85  5953.2  238.72  5996.3  238.66  6035.6  240.17
#Mann= 7 ,-1 , 0
  4151.5     .17       0  4614.5     .15       0  4955.7     .09       0
    5025     .15       0  5165.8     .17       0  5669.3     .15       0
  5876.8     .17       0
Bank Sta=4955.7,5025
XS Rating Curve= 0 ,0
Exp/Cntr=0.3,0.1

Type RM Length L Ch R = 1 ,8519    ,519,519,519
BEGIN DESCRIPTION:
SAND BRANCH NO 3 13.0
END DESCRIPTION:
XS GIS Cut Line= 3
      3783085.91     10177257.32      3782969.32     10176707.85
      3782229.93     10175826.14
#Sta/Elev= 30
  4438.3  239.66    4650  220.56  4730.9  216.66  4761.6  217.89  4827.4   213.8
  4932.5  213.48    4966   212.5  4976.3  211.53 4979.77  209.37  4987.3  207.02
  4993.6  201.87  5020.5   207.6    5027  206.09  5034.8  208.47  5041.3  205.48
    5048  209.14  5204.6  208.67  5254.7   206.4  5304.1  213.09  5345.7  213.97
  5410.8  216.56  5530.9  216.89  5746.1  221.97  5793.3  224.44  5864.8  224.72
  5905.5  228.05  5922.1  227.63    5978  232.24  6056.1  235.52  6150.7  237.61
#Mann= 7 ,-1 , 0
  4438.3     .17       0  4827.4     .15       0 4979.77     .09       0
    5048     .15       0  5345.7     .17       0  5746.1     .15       0
  5905.5     .17       0
#XS Ineff= 2 , 0
       0                  5304.1       0  213.09
Permanent Ineff=
       F       F
Bank Sta=4979.77,5048
XS Rating Curve= 0 ,0
Exp/Cntr=0.3,0.1

Type RM Length L Ch R = 1 ,8000    ,500,500,500
BEGIN DESCRIPTION:
SAND BRANCH NO 3 12.0
END DESCRIPTION:
XS GIS Cut Line= 3
      3783747.13     10176686.64      3783220.35     10176341.83
      3782252.74     10175740.19
#Sta/Elev= 30
  4370.4  243.51  4388.6  241.17  4476.1  235.28  4524.9   230.7  4684.1  220.87
  4813.7  208.56  4916.3  205.89  4979.5  207.19  4994.6  203.74  4996.3  201.33
  5004.4  201.83  5009.9  205.06  5052.4  207.46  5093.6  207.68  5124.6  208.49
    5168  208.09  5214.1  210.08    5220  209.22  5256.6  209.76  5372.3  217.25
  5482.1  221.38  5509.3  220.94  5545.8   222.5  5582.4  222.26  5597.8  220.56
    5619  222.05    5671  221.06  5765.4   223.5    5887  230.25  6139.4   239.3
#Mann= 5 ,-1 , 0
  4370.4     .17       0  4979.5     .09       0  5052.4     .17       0
  5093.6     .15       0  5124.6     .17       0
Bank Sta=4979.5,5052.4
XS Rating Curve= 0 ,0
Exp/Cntr=0.3,0.1

Type RM Length L Ch R = 1 ,7500    ,500,500,500
BEGIN DESCRIPTION:
SAND BRANCH NO 3 11.0
END DESCRIPTION:
XS GIS Cut Line= 3
      3783910.21     10176315.28      3783478.54     10176019.82
      3782321.68     10175057.18
#Sta/Elev= 30
  4476.9  241.23  4510.5  239.36  4546.4  239.36  4576.2  236.75  4639.1  236.65
  4668.9  234.24    4675  235.24  4725.8  232.43    4956  211.28 4979.96  206.19
  5004.4  200.22  5008.8  200.22  5013.9  203.39  5027.5  206.12  5089.3  205.42
  5148.5  206.29    5170  208.34  5191.5  207.99  5205.8  203.61  5220.1  207.75
  5238.9  210.66  5269.6  211.42  5304.8  214.93  5534.2  221.92  5562.8  223.04
  5816.4  229.41    5987  229.99  6270.8  236.43  6305.9  235.95    6505  241.11
#Mann= 7 ,-1 , 0
  4476.9     .17       0 4979.96     .09       0  5027.5     .17       0
  5089.3     .11       0  5238.9     .17       0  5534.2     .11       0
  5562.8     .17       0
#XS Ineff= 2 , 0
       0                    5241       0  211.03
Permanent Ineff=
       F       F
Bank Sta=4979.96,5027.5
XS Rating Curve= 0 ,0
Exp/Cntr=0.3,0.1

Type RM Length L Ch R = 1 ,7000    ,500,500,500
BEGIN DESCRIPTION:
SAND BRANCH NO 3 10.0
END DESCRIPTION:
XS GIS Cut Line= 3
      3784095.87     10175939.36      3783714.77     10175608.17
      3782861.14     10175423.41
#Sta/Elev= 30
  4495.1  232.97  4577.5  235.06    4606  233.43  4620.2  233.72  4704.7  225.51
  4769.3  217.74  4896.5  204.63  4910.8  204.91  4931.6  203.15    4982  203.66
    5000  201.58  5003.7  199.23  5008.3  199.23  5011.1  201.42  5017.3  203.14
  5027.5  203.71    5048  203.57  5104.4  208.89  5191.2  213.62    5291  221.18
  5334.5  221.85  5345.3   221.1  5395.9   223.2    5447  221.65  5498.2  222.61
  5526.9  221.83  5718.6  225.55  5767.8   225.6  5794.9  227.12  5873.4  228.38
#Mann= 3 , 0 , 0
  4495.1     .17       0    4982     .09       0  5027.5     .17       0
Bank Sta=4982,5027.5
XS Rating Curve= 0 ,0
Exp/Cntr=0.3,0.1

Type RM Length L Ch R = 1 ,6500    ,500,500,500
BEGIN DESCRIPTION:
SAND BRANCH NO 3 9.0
END DESCRIPTION:
XS GIS Cut Line= 4
      3784156.92     10175614.58      3783948.58     10175208.32
      3783875.43     10175175.36      3782941.91     10175029.17
#Sta/Elev= 30
  4463.2  230.19  4523.3  230.49  4555.6   229.3  4568.3  227.73  4577.8  228.38
  4605.6   225.8  4622.2   225.6  4627.8  224.16  4644.4  223.47    4711  216.95
  4716.6  215.51  4738.8  214.86  4770.6  211.65  4844.1  208.21  4849.8   206.8
  4860.5  207.48  4888.5  205.25  4905.1  205.29  4931.5  202.59  4964.4  202.77
  4971.9  201.17  4977.4  202.06  4986.4  199.83  4996.8   199.3  5007.7  200.95
  5056.6  200.63  5061.7  201.77  5124.4  203.22  5380.2  216.12  5944.9  231.66
#Mann= 3 , 0 , 0
  4463.2     .17       0  4964.4     .09       0  5061.7     .17       0
#XS Ineff= 2 , 0
       0  4860.5  207.48               0
Permanent Ineff=
       F       F
Bank Sta=4964.4,5061.7
XS Rating Curve= 0 ,0
Exp/Cntr=0.3,0.1