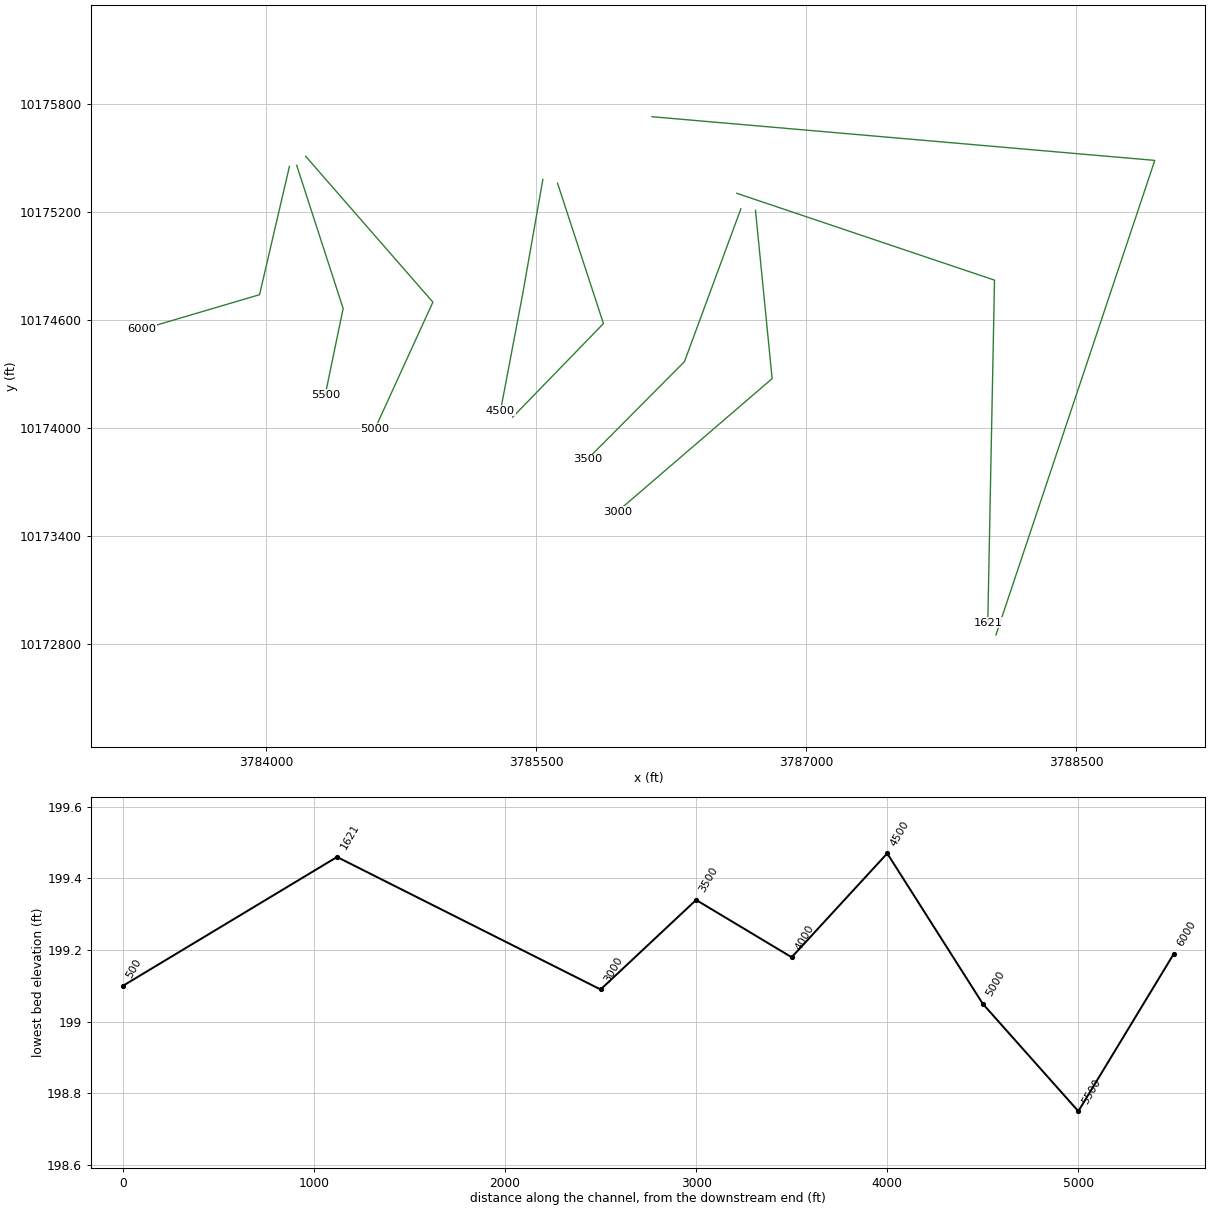
HEC-RAS study SAND BRANCH NO 3.prj: SAND BRANCH NO 3 Base Level Engineering

--- SAND BRANCH NO 3.g01 (geometry) --- (continued)

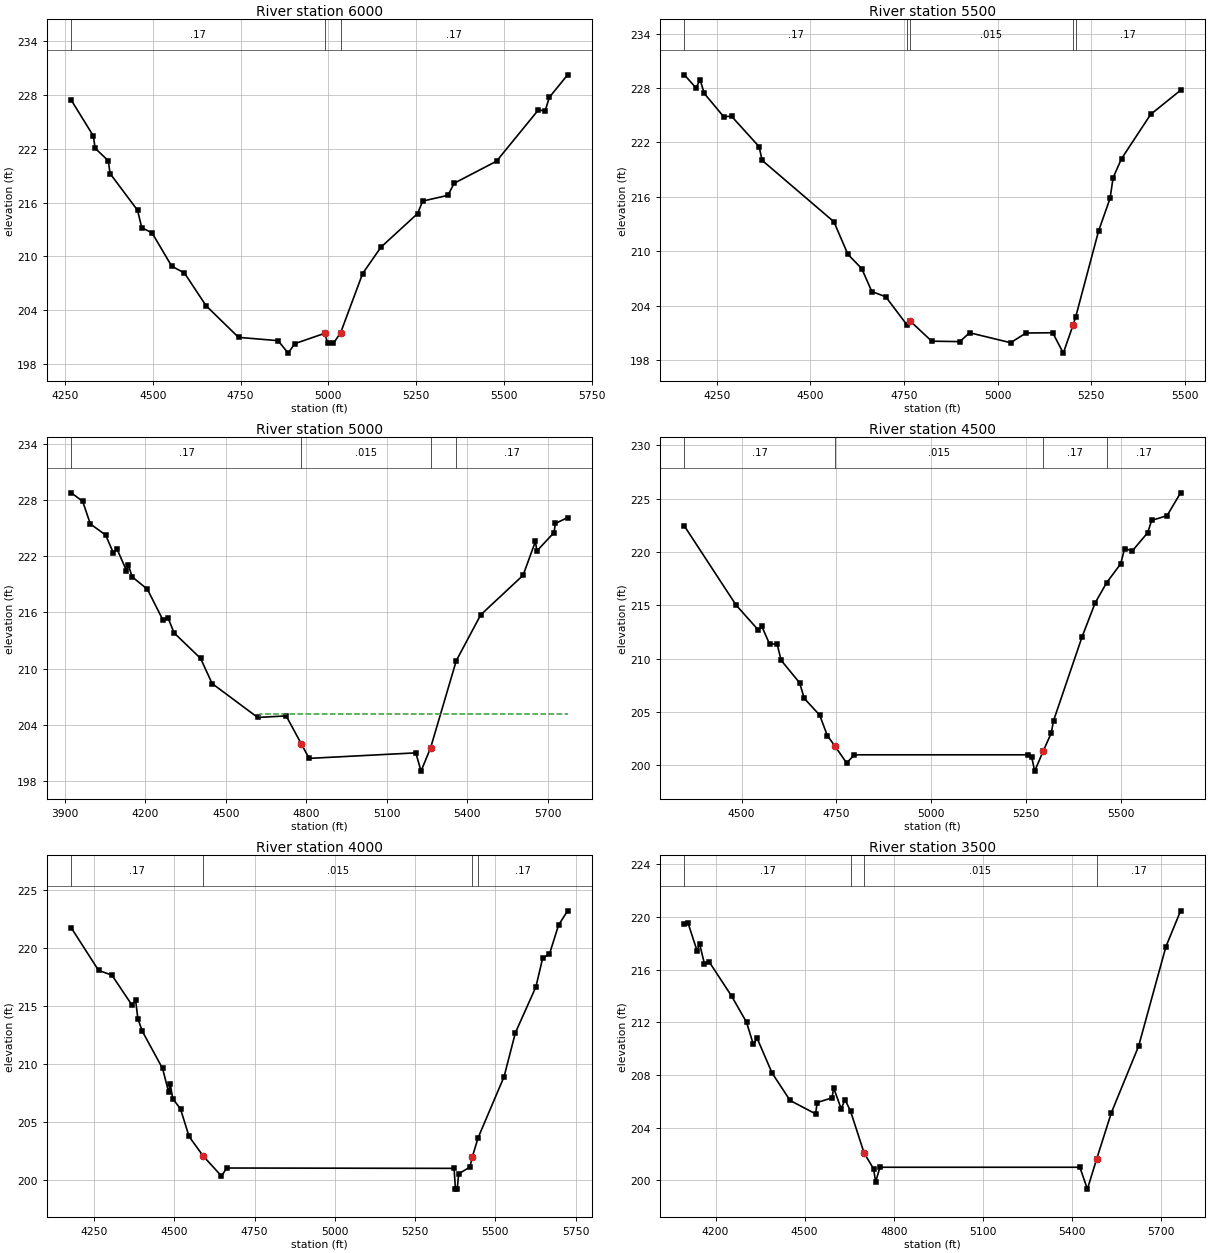
Type RM Length L Ch R = 1 ,6000    ,500,500,500
BEGIN DESCRIPTION:
SAND BRANCH NO 3 8.0
END DESCRIPTION:
XS GIS Cut Line= 3
      3784127.57     10175454.77      3783961.46     10174741.86
      3783307.83     10174548.96
#Sta/Elev= 30
    4268  227.41  4330.6  223.43  4335.7  222.06  4373.1  220.66  4378.3  219.23
  4456.6  215.13  4468.5  213.18  4497.7  212.62  4553.7   208.9  4590.1  208.13
  4651.7  204.48  4744.1  200.95  4856.8  200.58  4885.5  199.19  4904.5  200.25
  4989.6   201.4  4997.8  200.35  5014.2  200.27    5035  201.47  5097.6  208.07
  5149.7  211.01    5254  214.76  5268.7  216.16  5340.5   216.8  5358.3  218.15
  5478.9  220.61  5598.1  226.33  5617.4  226.22  5629.3  227.74  5681.5  230.25
#Mann= 3 , 0 , 0
    4268     .17       0  4989.6     .06       0    5035     .17       0
Bank Sta=4989.6,5035
XS Rating Curve= 0 ,0
Exp/Cntr=0.3,0.1

Type RM Length L Ch R = 1 ,5500    ,500,500,500
BEGIN DESCRIPTION:
SAND BRANCH NO 3 7.0
END DESCRIPTION:
XS GIS Cut Line= 3
      3784167.86     10175461.03      3784426.08     10174665.28
      3784326.85     10174186.66
#Sta/Elev= 30
  4163.4  229.47  4194.9  228.02  4205.4  228.95  4216.6  227.42  4268.5  224.85
  4289.5   224.9  4363.1  221.54  4371.2  220.03  4562.9  213.25  4600.2  209.66
  4637.4  208.07  4664.1  205.55  4701.4  204.97  4759.2   201.8  4765.3  202.34
    4824  200.07  4899.3  200.02  4925.2     201  5034.9   199.9  5075.8  200.97
  5147.3     201  5175.5  198.75 5201.55  201.84  5208.5  202.73  5269.8  212.24
  5300.5  215.84  5308.5  218.11  5331.1  220.22  5408.8   225.1  5488.8  227.77
#Mann= 5 ,-1 , 0
  4163.4     .17       0  4759.2     .15       0  4765.3    .015       0
 5201.55     .17       0  5208.5     .17       0
Bank Sta=4765.3,5201.55
XS Rating Curve= 0 ,0
Exp/Cntr=0.3,0.1

Type RM Length L Ch R = 1 ,5000    ,500,500,500
BEGIN DESCRIPTION:
SAND BRANCH NO 3 6.0
END DESCRIPTION:
XS GIS Cut Line= 3
      3784217.88     10175511.04      3784924.83     10174700.53
      3784603.12     10173996.45
#Sta/Elev= 30
  3924.5  228.75  3966.7  227.84  3995.2  225.43  4052.1  224.25  4080.6  222.37
  4094.9  222.73    4130  220.45  4136.8  221.05  4150.9  219.79  4207.8  218.46
  4264.8  215.23  4285.7  215.34  4307.5   213.8  4406.2  211.08    4449   208.4
  4618.9  204.78  4725.2  204.94  4782.2  201.92  4810.7  200.41  5208.3     201
  5227.7  199.05  5263.3  201.53  5359.1  210.84  5450.2  215.73    5608  219.95
    5654  223.56  5659.5  222.55  5723.1   224.5  5728.6  225.49  5774.1   226.1
#Mann= 4 ,-1 , 0
  3924.5     .17       0  4782.2    .015       0  5263.3     .17       0
  5359.1     .17       0
#XS Ineff= 2 ,-1
  4725.2  4626.5  204.94  4626.5  4604.6  205.18
Permanent Ineff=
       F       F
Bank Sta=4782.2,5263.3
XS Rating Curve= 0 ,0
Exp/Cntr=0.3,0.1

Type RM Length L Ch R = 1 ,4500    ,500,500,500
BEGIN DESCRIPTION:
SAND BRANCH NO 3 5.0
END DESCRIPTION:
XS GIS Cut Line= 3
      3785536.09     10175382.32      3785423.16     10174741.39
      3785300.57     10174096.03
#Sta/Elev= 30
  4349.2  222.46  4485.3  215.05  4544.6  212.68  4553.5  213.03  4573.9  211.38
  4593.7  211.39  4604.3  209.86    4653  207.75  4665.2  206.29  4705.9  204.72
  4726.2  202.79  4746.5   201.8  4776.9  200.23  4797.2     201  5254.8     201
  5264.7  200.76  5272.4  199.47  5295.5   201.4  5315.9  203.02  5322.1   204.2
  5397.3  212.06  5431.6  215.23  5461.9  217.13  5499.1  218.91  5509.3  220.34
  5529.6  220.11  5570.3  221.83  5580.5  222.97  5621.2  223.42  5656.9  225.56
#Mann= 4 ,-1 , 0
  4349.2     .17       0  4746.5    .015       0  5295.5     .17       0
  5461.9     .17       0
Bank Sta=4746.5,5295.5
XS Rating Curve= 0 ,0
Exp/Cntr=0.3,0.1

Type RM Length L Ch R = 1 ,4000    ,500,500,500
BEGIN DESCRIPTION:
SAND BRANCH NO 3 4.0
END DESCRIPTION:
XS GIS Cut Line= 3
      3785617.86     10175361.05      3785872.76     10174581.36
      3785367.85     10174061.07
#Sta/Elev= 30
  4179.7  221.69  4264.6  218.03  4305.9  217.63    4369  215.02  4379.6  215.51
  4386.8  213.88  4400.6  212.79  4463.7  209.58  4482.5  207.56  4487.7  208.21
  4495.3  206.99  4519.6  206.09  4546.2  203.72    4590  202.04  4647.1  200.31
  4663.6     201  5371.4  200.97  5375.6  199.18  5381.2  199.18  5385.6   200.5
  5420.8  201.08    5428  201.94  5446.1   203.6    5527  208.87  5562.3  212.66
  5626.1  216.61  5647.2  219.09  5668.5  219.45  5696.8  221.95    5725  223.17
#Mann= 4 ,-1 , 0
  4179.7     .17       0    4590    .015       0    5428     .17       0
  5446.1     .17       0
Bank Sta=4590,5428
XS Rating Curve= 0 ,0
Exp/Cntr=0.3,0.1

Type RM Length L Ch R = 1 ,3500    ,500,500,500
BEGIN DESCRIPTION:
SAND BRANCH NO 3 3.0
END DESCRIPTION:
XS GIS Cut Line= 3
      3786636.64     10175219.27      3786323.12     10174369.89
       3785782.6     10173826.28
#Sta/Elev= 30
  4094.6  219.44  4107.1  219.54  4137.5  217.43    4146  217.96  4162.6  216.42
    4178   216.6  4253.9  213.99  4304.1  212.01  4327.2  210.32  4339.9  210.79
  4390.1  208.16  4450.9  206.07  4536.9  205.05  4542.2  205.91  4592.4  206.27
  4597.7  207.03  4622.8  205.45  4636.3  206.12  4654.6  205.26  4700.3  202.08
  4732.3  200.88  4739.2  199.88  4753.6     201  5427.2     201  5452.6  199.34
  5483.7  201.62  5533.2  205.13  5625.1  210.19  5717.1  217.74  5766.6  220.46
#Mann= 4 ,-1 , 0
  4094.6     .17       0  4654.6     .11       0  4700.3    .015       0
  5483.7     .17       0
Bank Sta=4700.3,5483.7
XS Rating Curve= 0 ,0
Exp/Cntr=0.3,0.1

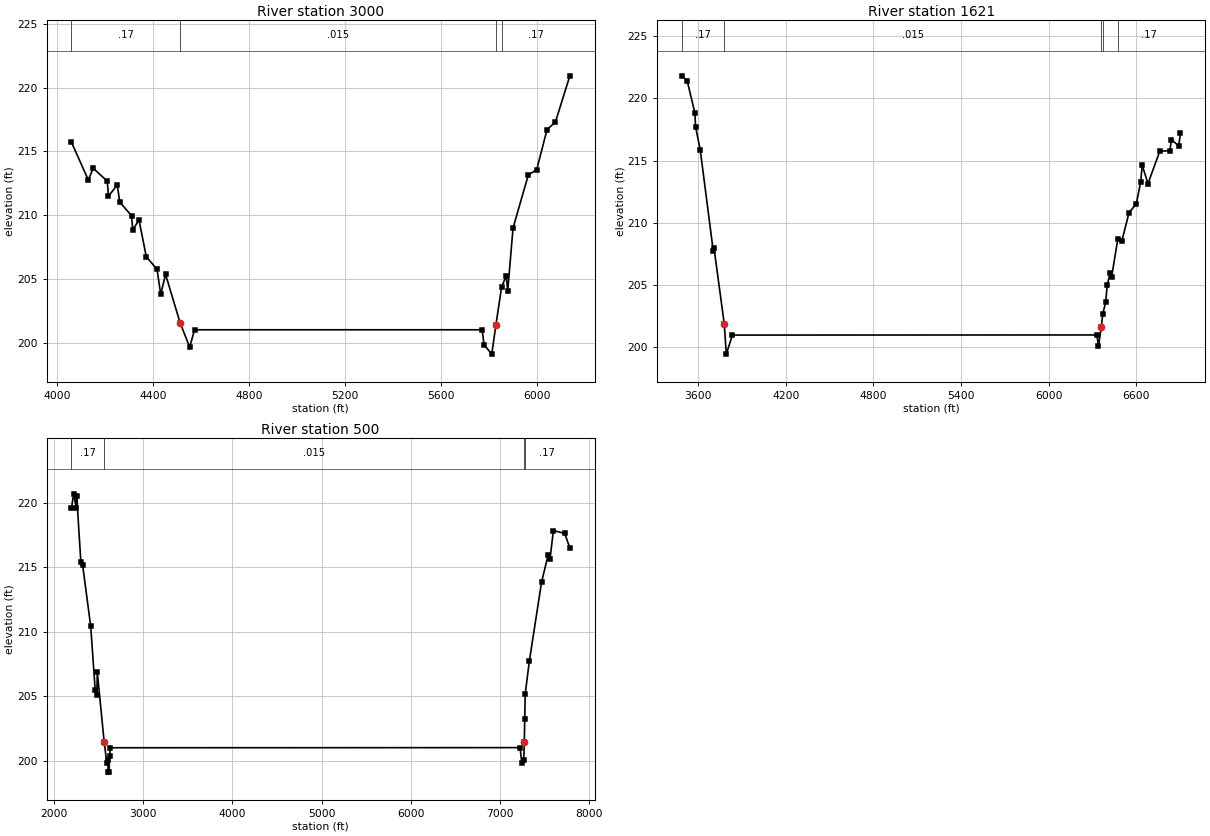
Type RM Length L Ch R = 1 ,3000    ,1379,1379,1379
BEGIN DESCRIPTION:
SAND BRANCH NO 3 2.0
END DESCRIPTION:
XS GIS Cut Line= 3
      3786717.85     10175211.08      3786810.32     10174275.44
      3785949.19     10173535.29
#Sta/Elev= 30
  4059.8  215.71  4130.1  212.75  4150.2  213.67  4208.9  212.66  4213.9  211.47
  4250.7  212.37  4260.8  211.02    4310  209.95    4315  208.85  4341.2  209.61
  4371.3  206.74  4416.1  205.74  4431.6  203.78  4451.7  205.35    4512  201.56
  4552.2  199.64  4572.3     201  5770.4     201    5778  199.82  5810.3  199.09
  5827.4  201.37  5851.1  204.34  5870.2  205.22  5876.8  204.08  5898.8  208.98
  5962.4  213.14  5997.5  213.56  6040.3   216.7  6075.4   217.3  6135.5  220.92
#Mann= 4 ,-1 , 0
  4059.8     .17       0    4512    .015       0  5827.4     .17       0
  5851.1     .17       0
Bank Sta=4512,5827.4
XS Rating Curve= 0 ,0
Exp/Cntr=0.3,0.1

Type RM Length L Ch R = 1 ,1621    ,1121,1121,1121
BEGIN DESCRIPTION:
SAND BRANCH NO 3 1.0
END DESCRIPTION:
XS GIS Cut Line= 3
      3786613.99     10175305.29       3788046.3     10174822.77
      3788008.91     10172918.54
#Sta/Elev= 30
  3488.6  221.81  3524.3  221.37    3576  218.84  3581.2  217.71  3612.7  215.88
  3701.9  207.77  3707.2  207.99  3777.6  201.89  3791.7  199.46  3833.2  200.99
    6332     201    6342  200.08    6362  201.66    6372   202.7    6392  203.63
    6402     205    6422  205.94    6432  205.62  6474.6  208.68    6502  208.51
    6552  210.83    6602  211.53    6632  213.32    6642  214.63    6682  213.16
    6762  215.74  6832.1  215.81  6842.1  216.69  6892.1  216.18  6904.6   217.2
#Mann= 5 ,-1 , 0
  3488.6     .17       0  3777.6    .015       0    6362     .17       0
    6372     .15       0  6474.6     .17       0
Bank Sta=3777.6,6362
XS Rating Curve= 0 ,0
Exp/Cntr=0.3,0.1

Type RM Length L Ch R = 1 ,500     ,0,0,0
BEGIN DESCRIPTION:
SAND BRANCH NO 3 1.5
END DESCRIPTION:
XS GIS Cut Line= 3
      3786142.93     10175731.02        3788937.     10175488.24
      3788054.19     10172850.56
#Sta/Elev= 30
  2195.4  219.59  2220.4  220.68    2249  219.58  2254.1  220.52  2300.7  215.39
  2320.8  215.15  2411.1   210.4  2461.3  205.47    2480  205.05    2485  206.85
  2561.7  201.46  2591.8  199.82    2603  200.03  2607.1   199.1  2616.6   199.1
  2621.9  200.33    2632  200.99    7223     201  7243.2   199.8  7264.2  200.03
 7270.83  201.45  7275.9  203.24  7280.8  205.15  7327.5  207.72  7464.6  213.84
  7538.7  215.96  7559.5  215.64  7596.5  217.83  7722.8  217.61  7781.5   216.5
#Mann= 4 ,-1 , 0
  2195.4     .17       0  2561.7    .015       0 7270.83     .17       0
  7275.9     .17       0
Bank Sta=2561.7,7270.83
XS Rating Curve= 0 ,0
Exp/Cntr=0.3,0.1

Chan Stop Cuts=-1
Use User Specified Reach Order=0
Composite Channel Slope=5