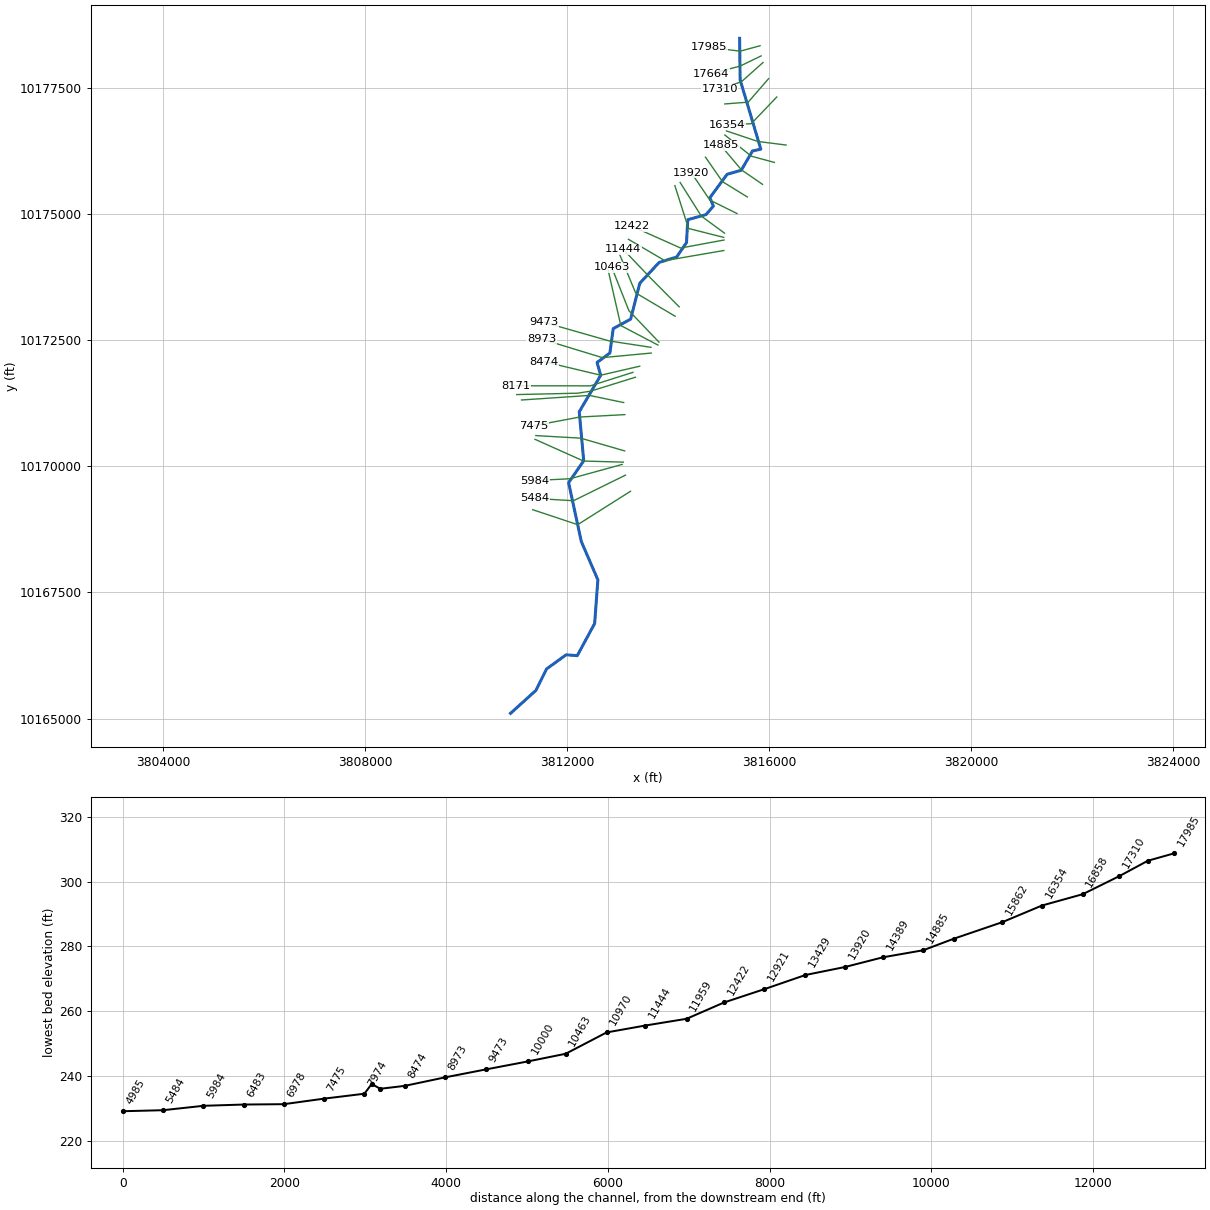
--- SHEPARD BRANCH.prj (project) ---

Proj Title=SHEPARD BRANCH Base Level Engineering
Current Plan=p01
Default Exp/Contr=0.3,0.1
English Units
Geom File=g01
Flow File=f01
Plan File=p01
Y Axis Title=Elevation
X Axis Title(PF)=Main Channel Distance
X Axis Title(XS)=Station
BEGIN DESCRIPTION:
SHEPARD BRANCH
END DESCRIPTION:
DSS Export Rating Curves= 0
DSS Export Rating Curve Sorted= 0
DSS Export Volume Flow Curves= 0
DXF OffsetX= 0
DXF OffsetY= 0
DXF ScaleX= 1
DXF ScaleY= 10

--- SHEPARD BRANCH.p01 (plan) ---

Plan Title=Multiple Run
Short Identifier=Multiple
Geom File=g01
Flow File=f01
Subcritical Flow
K Sum by GR= 0
Std Step Tol= 0.01
Critical Tol= 0.01
Num of Std Step Trials= 20
Max Error Tol= 0.3
Flow Tol Ratio= 0.001
Split Flow NTrial= 30
Split Flow Tol= 0.02
Split Flow Ratio= 0.02
Log Output Level= 0
Friction Slope Method= 1
Unsteady Friction Slope Method= 2
Unsteady Bridges Friction Slope Method= 1
Parabolic Critical Depth
Global Vel Dist=  1 , 1 , 1
Global Log Level= 0
CheckData=True
Encroach Param= -1, 0, 0, 0
BEGIN DESCRIPTION:
Multiple Run
END DESCRIPTION:

--- SHEPARD BRANCH.f01 (steady flow) ---

Flow Title=Multiple
Program Version=4.10
Number of Profiles= 7
Profile Names=10-year,25-year,50-year,1pct_min,100-year,1pct_plu,500-year
River Rch & RM=SHEPARD BRANCH,Reach-1         ,17985
     240     307     399     172     520    1570     906
River Rch & RM=SHEPARD BRANCH,Reach-1         ,16858
    1052    1467    2023     917    2769    8362    5366
River Rch & RM=SHEPARD BRANCH,Reach-1         ,9473
    1233    1718    2366    1070    3231    9757    6226
River Rch & RM=SHEPARD BRANCH,Reach-1         ,1015
    1279    1779    2447    1104    3335   10072    6409
River Rch & RM=SHEPARD BRANCH,Reach-1         ,500
    2823    4048    5683    2610    7882   23803   15692
Boundary for River Rch & Prof#=SHEPARD BRANCH,Reach-1         , 1
Up Type= 0
Dn Type= 3
Dn Slope=0.009
Boundary for River Rch & Prof#=SHEPARD BRANCH,Reach-1         , 2
Up Type= 0
Dn Type= 3
Dn Slope=0.009
Boundary for River Rch & Prof#=SHEPARD BRANCH,Reach-1         , 3
Up Type= 0
Dn Type= 3
Dn Slope=0.009
Boundary for River Rch & Prof#=SHEPARD BRANCH,Reach-1         , 4
Up Type= 0
Dn Type= 3
Dn Slope=0.009
Boundary for River Rch & Prof#=SHEPARD BRANCH,Reach-1         , 5
Up Type= 0
Dn Type= 3
Dn Slope=0.009
Boundary for River Rch & Prof#=SHEPARD BRANCH,Reach-1         , 6
Up Type= 0
Dn Type= 3
Dn Slope=0.009
Boundary for River Rch & Prof#=SHEPARD BRANCH,Reach-1         , 7
Up Type= 0
Dn Type= 3
Dn Slope=0.009
DSS Import GetInterval= 0
DSS Import GetPeak= 0
DSS Import FillOption= 0

--- SHEPARD BRANCH.g01 (geometry) ---

Geom Title=Existing Conditions
Program Version=4.10

River Reach=SHEPARD BRANCH  ,Reach-1
Reach XY= 30
      3815414.89     10178482.17      3815425.09     10177658.75
      3815834.47     10176286.73      3815669.11      10176249.1
      3815447.36     10175867.89      3815168.14     10175787.92
      3814826.02     10175324.54       3814894.5     10175156.77
      3814749.04     10174989.11      3814387.78     10174887.46
      3814363.25     10174434.07      3814168.35     10174148.57
      3813820.83     10174040.75      3813437.81     10173627.49
      3813256.12     10172916.72      3812911.62     10172729.08
      3812845.42     10172245.21      3812591.19     10172058.38
      3812663.38     10171803.74      3812238.75     10171080.71
      3812327.49      10170110.2      3812027.99     10169675.88
      3812279.45     10168510.25      3812607.71     10167750.73
      3812543.76     10166884.91      3812199.56       10166248.
      3811978.07     10166264.55      3811590.56     10165983.34
      3811381.63     10165560.31      3810877.74     10165103.86

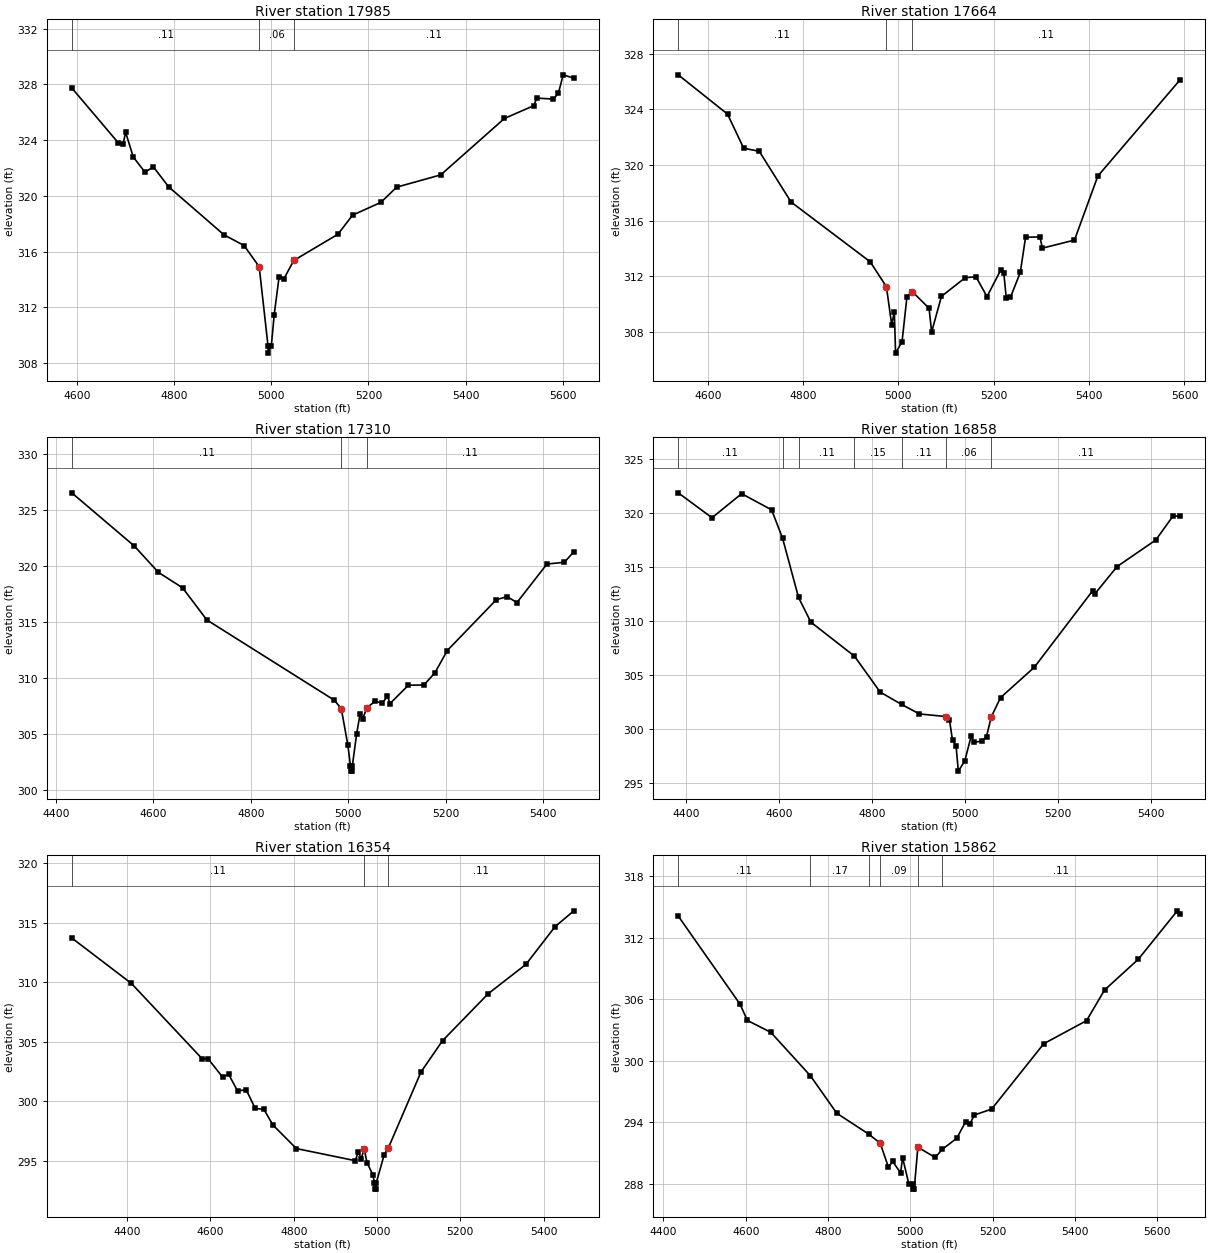
Type RM Length L Ch R = 1 ,17985   ,321,321,321
BEGIN DESCRIPTION:
SHEPARD BRANCH 32.0
END DESCRIPTION:
XS GIS Cut Line= 3
      3815820.05     10178335.08      3815423.83     10178227.37
      3814806.16     10178305.57
#Sta/Elev= 30
  4589.4  327.74  4684.9  323.81  4695.1  323.72  4700.2  324.56    4716  322.78
    4740   321.7  4757.5  322.07  4788.6  320.65  4902.6   317.2    4944  316.43
  4975.1  314.91  4993.3  309.21  4993.6  308.71    5000  309.21    5006  311.48
  5016.1   314.2  5026.2  314.06  5046.3  315.36  5137.1  317.24  5167.3  318.61
  5225.6  319.53    5258  320.62  5348.7   321.5  5479.8  325.55  5540.3  326.47
  5546.1  327.01  5580.6  326.94  5590.7  327.35  5600.7  328.68  5622.6  328.44
#Mann= 3 , 0 , 0
  4589.4     .11       0  4975.1     .06       0  5046.3     .11       0
Bank Sta=4975.1,5046.3
XS Rating Curve= 0 ,0
Exp/Cntr=0.3,0.1

Type RM Length L Ch R = 1 ,17664   ,354,354,354
BEGIN DESCRIPTION:
Mapping XS d9232ae7
END DESCRIPTION:
XS GIS Cut Line= 3
      3815840.88     10178133.68      3815425.19     10177932.29
      3814853.05       10177783.
#Sta/Elev= 30
  4538.1  326.49  4641.5  323.66  4675.3  321.21  4708.1  320.98  4774.8  317.33
  4940.7  313.03  4974.8  311.23  4985.9  308.49  4991.4  309.44    4994  306.45
  5007.6  307.27  5017.9  310.51    5029  310.88  5064.3  309.68  5069.6  307.97
  5090.3  310.54  5140.1  311.88  5162.6  311.95  5185.8  310.52  5214.3  312.41
  5221.1  312.19  5226.2  310.42  5234.9  310.46  5255.6  312.26  5266.7  314.79
  5296.8  314.82    5302  314.01  5369.3  314.59  5418.3   319.2  5591.3  326.15
#Mann= 3 ,-1 , 0
  4538.1     .11       0  4974.8     .06       0    5029     .11       0
Bank Sta=4974.8,5029
XS Rating Curve= 0 ,0
Exp/Cntr=0.3,0.1

Type RM Length L Ch R = 1 ,17310   ,452,452,452
BEGIN DESCRIPTION:
SHEPARD BRANCH 31.0
END DESCRIPTION:
XS GIS Cut Line= 3
      3815877.56     10178002.59      3815453.83     10177624.79
      3815018.18      10177468.3
#Sta/Elev= 30
  4432.3  326.54  4560.7  321.79  4610.1  319.44  4659.7  318.06  4709.6  315.19
  4971.3  308.02  4985.5  307.27    4999  304.02  5004.3  302.19  5004.6  301.69
  5008.1  301.69  5008.3  302.19    5017  305.01    5024  306.76  5029.3  306.35
  5038.2  307.36  5054.8  307.92  5070.1  307.77  5080.2  308.39  5085.5  307.72
  5123.2  309.36  5155.1  309.38  5177.7  310.47  5203.1  312.46  5303.9     317
    5326  317.27  5346.1  316.74  5407.6  320.18  5443.6  320.34  5462.9  321.29
#Mann= 3 , 0 , 0
  4432.3     .11       0  4985.5     .06       0  5038.2     .11       0
#XS Ineff= 2 , 0
       0                    5024       0  306.76
Permanent Ineff=
       F       F
Bank Sta=4985.5,5038.2
XS Rating Curve= 0 ,0
Exp/Cntr=0.3,0.1

Type RM Length L Ch R = 1 ,16858   ,504,504,504
BEGIN DESCRIPTION:
SHEPARD BRANCH 30.0
END DESCRIPTION:
XS GIS Cut Line= 3
      3815988.76     10177683.04      3815584.65     10177217.32
      3815122.01     10177181.92
#Sta/Elev= 30
  4383.4  321.91  4456.1   319.6  4519.8  321.83  4584.4  320.33  4607.9  317.71
  4642.3  312.21  4668.9  309.92  4762.6  306.77    4818  303.44  4864.2  302.29
  4902.5  301.41  4959.5  301.17  4967.1  300.89  4973.7  298.97  4981.3  298.47
  4986.2  296.11    5000  297.04  5014.1  299.39  5019.1  298.78  5036.9  298.89
  5046.9  299.31    5057  301.12    5077  302.92  5149.8  305.74  5275.6  312.85
  5280.6  312.57  5327.8  315.07  5411.3  317.54  5448.1  319.75    5464  319.76
#Mann= 7 ,-1 , 0
  4383.4     .11       0  4607.9     .15       0  4642.3     .11       0
  4762.6     .15       0  4864.2     .11       0  4959.5     .06       0
    5057     .11       0
Bank Sta=4959.5,5057
XS Rating Curve= 0 ,0
Exp/Cntr=0.3,0.1

Type RM Length L Ch R = 1 ,16354   ,492,492,492
BEGIN DESCRIPTION:
SHEPARD BRANCH 29.0
END DESCRIPTION:
XS GIS Cut Line= 3
      3816151.15     10177320.28        3815645.     10176789.96
       3815172.8      10176773.1
#Sta/Elev= 30
  4266.9  313.71  4410.1  309.89    4580  303.56  4594.1  303.57  4629.3  302.01
  4643.5  302.26  4664.9  300.87  4685.9  300.95  4707.3  299.39  4728.4  299.31
  4749.6  298.01  4806.1  296.02  4947.6     295  4954.9  295.73  4961.8  295.17
    4969  295.97  4975.9  294.83  4990.1   293.8  4993.8  293.11    4994  292.61
  4997.5  292.61  4997.8  293.11  5017.2  295.51  5027.2  296.08  5105.6  302.46
  5157.2  305.08  5267.3  309.04  5357.4  311.49  5427.4  314.66  5472.5  315.99
#Mann= 3 , 0 , 0
  4266.9     .11       0    4969     .06       0  5027.2     .11       0
Bank Sta=4969,5027.2
XS Rating Curve= 0 ,0
Exp/Cntr=0.3,0.1

Type RM Length L Ch R = 1 ,15862   ,602,602,602
BEGIN DESCRIPTION:
SHEPARD BRANCH 28.0
END DESCRIPTION:
XS GIS Cut Line= 3
       3816334.6     10176367.56      3815775.09     10176438.55
      3815153.39     10176647.57
#Sta/Elev= 30
    4436  314.11    4586  305.52  4604.1  303.92    4661  302.76  4757.2  298.52
  4821.1  294.87  4898.3  292.84  4926.7  291.95  4946.8  289.59  4956.9  290.16
  4976.2  289.06  4981.2  290.53  4996.1  287.99  5005.6  287.96  5005.9  287.46
  5009.4  287.46  5018.2  291.55  5060.4  290.55  5077.8  291.35  5112.8  292.43
  5134.2  294.03  5144.3  293.78  5155.3  294.69  5197.5  295.27  5324.1  301.65
    5428   303.9  5471.8  306.89    5554   309.9  5648.6  314.62  5655.9  314.29
#Mann= 6 ,-1 , 0
    4436     .11       0  4757.2     .17       0  4898.3     .15       0
  4926.7     .09       0  5018.2     .15       0  5077.8     .11       0
#XS Ineff= 2 , 0
       0                  5155.3       0  294.69
Permanent Ineff=
       F       F
Bank Sta=4926.7,5018.2
XS Rating Curve= 0 ,0
Exp/Cntr=0.3,0.1

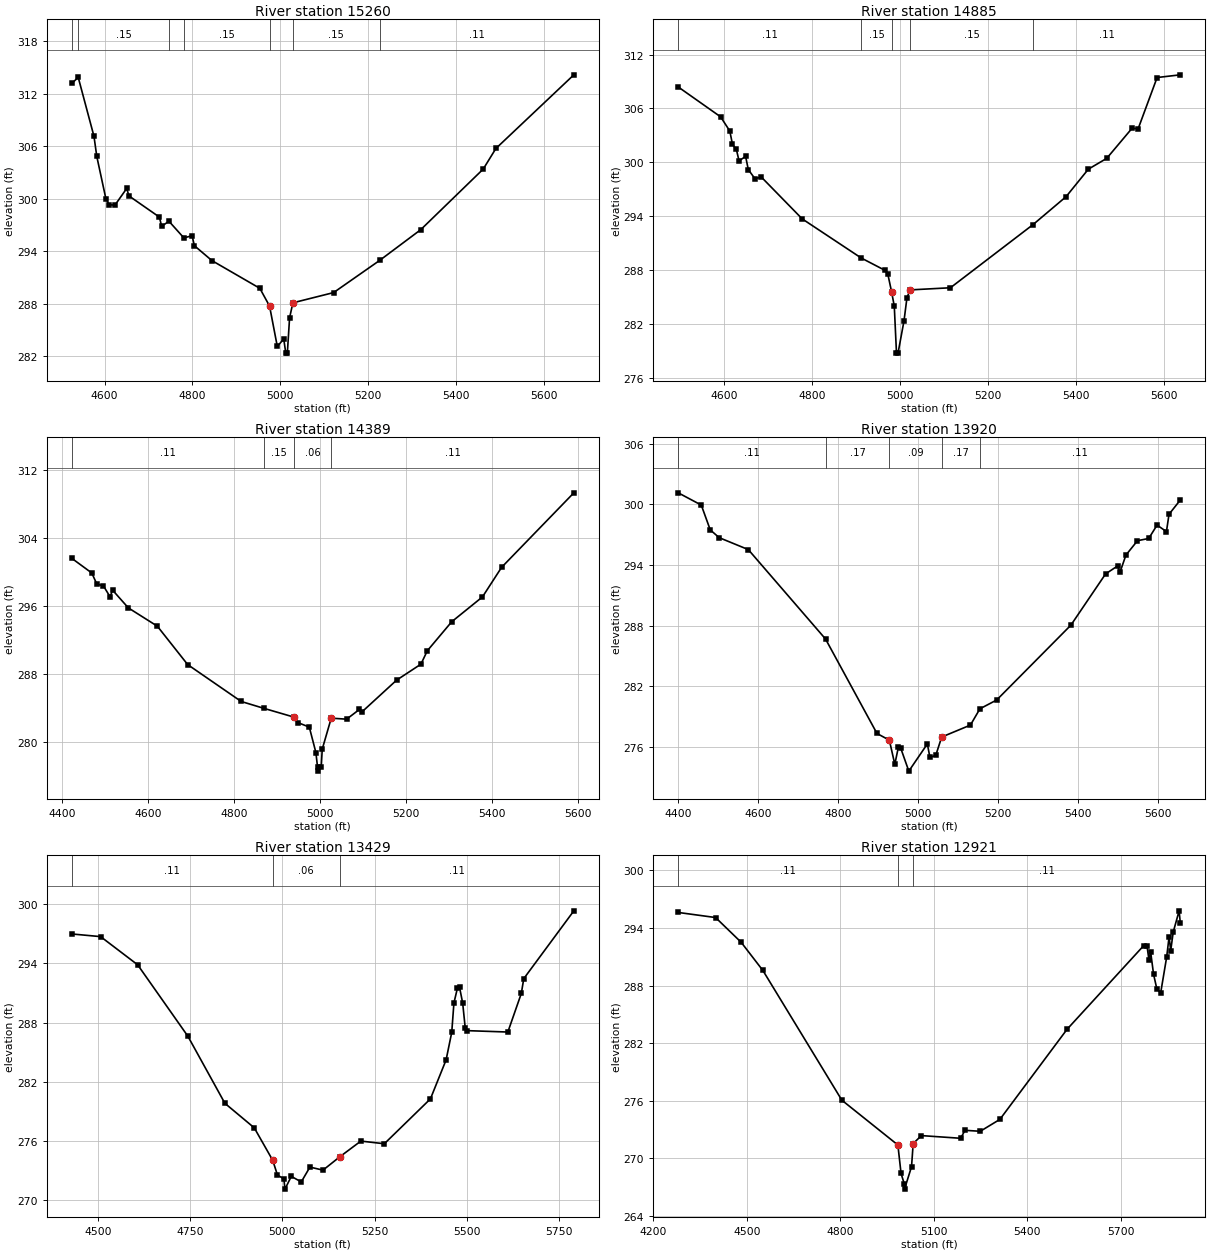
Type RM Length L Ch R = 1 ,15260   ,375,375,375
BEGIN DESCRIPTION:
SHEPARD BRANCH 27.0
END DESCRIPTION:
XS GIS Cut Line= 3
      3816102.83     10176023.18      3815644.62     10176147.22
       3815122.7      10176565.9
#Sta/Elev= 30
  4525.3  313.16    4540  313.85  4575.9  307.11  4582.3  304.81    4603  299.98
  4610.5  299.29  4623.7  299.25  4650.4  301.15  4655.6   300.3  4724.9  297.88
  4730.1  296.82  4746.6  297.41  4780.7   295.5  4799.4  295.75  4804.6  294.61
  4844.5  292.91  4953.7  289.74  4975.9  287.71  4993.5   283.1  5008.2  283.94
  5012.9  282.33  5016.4  282.33  5021.5  286.36    5029  288.08  5121.8  289.25
  5226.8  292.93  5320.3  296.44  5462.7  303.37  5491.5  305.72  5669.1  314.14
#Mann= 7 ,-1 , 0
  4525.3     .11       0    4540     .15       0  4746.6     .17       0
  4780.7     .15       0  4975.9     .09       0    5029     .15       0
  5226.8     .11       0
Bank Sta=4975.9,5029
XS Rating Curve= 0 ,0
Exp/Cntr=0.3,0.1

Type RM Length L Ch R = 1 ,14885   ,496,496,496
BEGIN DESCRIPTION:
SHEPARD BRANCH 26.0
END DESCRIPTION:
XS GIS Cut Line= 3
      3815867.86      10175588.7      3815452.98     10175873.63
      3815041.78     10176359.88
#Sta/Elev= 30
  4496.7  308.39  4592.9  305.07  4613.8  303.49  4619.9     302  4628.7  301.44
  4634.8  300.17  4649.7  300.67  4655.8   299.2  4670.7   298.2  4685.6  298.36
  4778.2  293.72  4912.2  289.37  4966.4  287.99  4972.4  287.63  4981.3  285.58
  4987.3  284.01  4992.3  278.79  4995.8  278.79  5009.4  282.39    5016  284.92
  5022.8  285.82  5114.8  286.06  5302.3  293.08  5377.4  296.19    5428  299.25
  5469.7  300.45  5526.9  303.78  5541.2  303.76  5584.1  309.44  5636.8  309.74
#Mann= 5 ,-1 , 0
  4496.7     .11       0  4912.2     .15       0  4981.3     .09       0
  5022.8     .15       0  5302.3     .11       0
Bank Sta=4981.3,5022.8
XS Rating Curve= 0 ,0
Exp/Cntr=0.3,0.1

Type RM Length L Ch R = 1 ,14389   ,469,469,469
BEGIN DESCRIPTION:
SHEPARD BRANCH 25.0
END DESCRIPTION:
XS GIS Cut Line= 3
      3815567.41     10175338.52      3815075.22     10175642.13
      3814738.72     10176126.63
#Sta/Elev= 30
  4421.7  301.62  4468.2   299.9    4480   298.6  4495.4  298.38  4510.8   297.1
  4516.7  297.88  4553.3   295.8  4620.8  293.65  4691.4  289.14  4815.9  284.81
  4868.2  284.01  4938.2  282.98  4947.2  282.34  4974.4   281.8  4989.7  278.81
  4993.5  277.13  4993.8  276.63  5002.1  277.13  5004.5  279.21  5025.4  282.85
  5061.2  282.73  5090.9  283.87    5097  283.59  5177.4  287.31  5234.1  289.19
  5248.9  290.76  5305.7  294.17  5377.3  297.09  5421.8  300.56  5589.9  309.31
#Mann= 4 ,-1 , 0
  4421.7     .11       0  4868.2     .15       0  4938.2     .06       0
  5025.4     .11       0
Bank Sta=4938.2,5025.4
XS Rating Curve= 0 ,0
Exp/Cntr=0.3,0.1

Type RM Length L Ch R = 1 ,13920   ,491,491,491
BEGIN DESCRIPTION:
SHEPARD BRANCH 24.0
END DESCRIPTION:
XS GIS Cut Line= 3
      3815363.65     10175010.04      3814825.56     10175276.62
      3814457.25     10175819.83
#Sta/Elev= 30
  4399.5  301.13  4457.2  299.92  4479.6  297.47    4502   296.7  4574.9  295.52
  4768.3  286.68    4897  277.35    4928  276.69  4941.6   274.3  4950.5  275.99
    4956  275.95  4976.7  273.63  5023.1  276.32  5029.5  274.99  5044.1  275.18
    5059     277  5130.9  278.18  5154.7  279.79  5196.7  280.66  5382.5  288.06
  5469.3  293.12  5499.2   293.9  5505.3  293.28  5520.2  294.98  5549.1   296.4
  5577.2  296.62  5598.1  297.94  5621.6   297.3    5628  299.01  5656.3  300.42
#Mann= 5 ,-1 , 0
  4399.5     .11       0  4768.3     .17       0    4928     .09       0
    5059     .17       0  5154.7     .11       0
Bank Sta=4928,5059
XS Rating Curve= 0 ,0
Exp/Cntr=0.3,0.1

Type RM Length L Ch R = 1 ,13429   ,508,508,508
BEGIN DESCRIPTION:
SHEPARD BRANCH 23.0
END DESCRIPTION:
XS GIS Cut Line= 3
      3815116.86     10174620.61      3814657.16     10174957.97
      3814236.67     10175625.82
#Sta/Elev= 30
  4429.8  296.96  4507.9  296.69  4608.2  293.84  4744.1  286.62  4844.4  279.83
  4923.9  277.35    4974  274.06  4986.7  272.57    5004  272.19  5007.1  271.15
  5024.1  272.44  5051.2  271.88  5074.6  273.38    5110  273.07  5154.8   274.4
  5212.5  276.01  5276.1  275.74  5400.9  280.28  5443.3  284.22  5458.6  287.01
  5464.5  289.98  5473.9  291.47  5479.8  291.55  5488.2  289.97  5495.1  287.46
    5501  287.18  5610.5  287.04    5647  290.95  5653.6  292.44  5789.2   299.3
#Mann= 3 , 0 , 0
  4429.8     .11       0    4974     .06       0  5154.8     .11       0
#XS Ineff= 2 , 0
       0                  5212.5       0  276.01
Permanent Ineff=
       F       F
Bank Sta=4974,5154.8
XS Rating Curve= 0 ,0
Exp/Cntr=0.3,0.1

Type RM Length L Ch R = 1 ,12921   ,499,499,499
BEGIN DESCRIPTION:
SHEPARD BRANCH 22.0
END DESCRIPTION:
XS GIS Cut Line= 3
      3815101.28     10174537.25      3814403.03     10174713.71
      3814132.67     10175562.81
#Sta/Elev= 30
  4279.8  295.62  4399.7  295.09  4481.8  292.51  4551.5  289.57  4804.9  276.05
  4984.7  271.38  4994.9  268.41  5005.7  267.28    5006  266.78  5028.5  269.12
  5033.8  271.53  5060.2  272.36  5186.1  272.08  5200.1  272.91  5249.1  272.81
  5312.1  274.05  5527.6  283.44  5773.8  292.17  5784.3   292.1  5790.6  290.64
  5795.9   291.5  5805.3  289.17  5815.8  287.65  5828.1  287.24  5847.3  290.97
  5855.1  293.09  5860.3  291.64  5868.3  293.57  5887.3  295.79  5891.1  294.51
#Mann= 3 , 0 , 0
  4279.8     .11       0  4984.7     .07       0  5033.8     .11       0
Bank Sta=4984.7,5033.8
XS Rating Curve= 0 ,0
Exp/Cntr=0.3,0.1

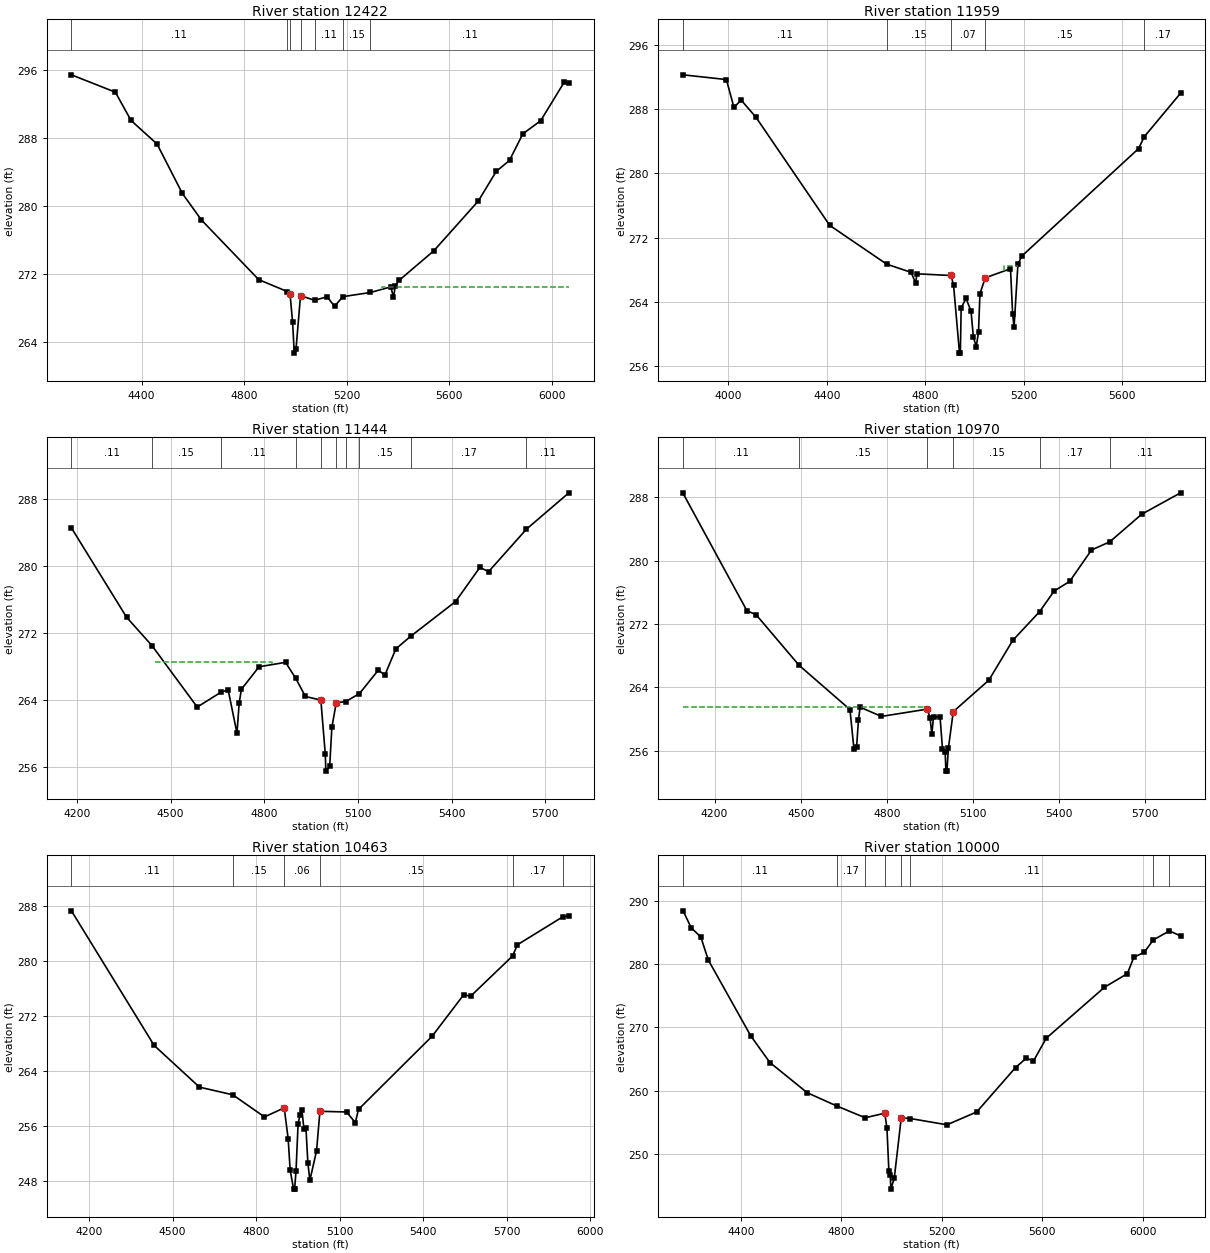
Type RM Length L Ch R = 1 ,12422   ,463,463,463
BEGIN DESCRIPTION:
SHEPARD BRANCH 21.0
END DESCRIPTION:
XS GIS Cut Line= 3
      3815106.48     10174485.17      3814246.96     10174326.21
       3813273.1     10174761.23
#Sta/Elev= 30
  4125.9  295.38  4297.4  293.34  4358.4  290.02  4460.1  287.24  4558.8  281.43
    4633  278.32  4856.7   271.3  4968.2   269.9  4978.8  269.62  4988.9  266.28
  4995.3  262.66  5002.2  263.16  5019.8  269.42  5074.9  268.87  5123.6  269.29
  5152.4  268.16  5184.9   269.3  5292.7  269.79  5372.2  270.45  5382.4  269.22
  5389.9  270.58  5404.3  271.21  5540.1   274.7  5713.6  280.55  5783.2  284.02
  5835.1  285.32    5887  288.44  5956.6  289.98  6049.5  294.56  6066.6  294.38
#Mann= 7 ,-1 , 0
  4125.9     .11       0  4968.2     .15       0  4978.8     .09       0
  5019.8     .15       0  5074.9     .11       0  5184.9     .15       0
  5292.7     .11       0
#XS Ineff= 2 , 0
       0                    5338       0  270.46
Permanent Ineff=
       F       F
Bank Sta=4978.8,5019.8
XS Rating Curve= 0 ,0
Exp/Cntr=0.3,0.1

Type RM Length L Ch R = 1 ,11959   ,515,515,515
BEGIN DESCRIPTION:
SHEPARD BRANCH 20.0
END DESCRIPTION:
XS GIS Cut Line= 3
      3815101.25     10174276.83      3813933.99      10174076.1
      3813211.76     10174500.14
#Sta/Elev= 30
  3815.6  292.25  3991.5  291.66    4022  288.21  4051.7   289.1  4111.7  286.97
  4411.4  273.52  4643.1  268.69  4742.4  267.67  4760.9  266.33    4766  267.49
  4904.8  267.28  4914.9  266.08    4939  257.62  4942.5  257.62  4945.8  263.25
  4965.6  264.43  4985.9  262.84  4995.5   259.6  5007.1  258.41  5016.3  260.26
  5022.1     265  5043.6  266.99  5146.3  268.12    5155  262.47  5160.8  260.86
  5176.5  268.69  5192.1  269.69  5666.9  283.07  5689.8  284.54  5837.5  289.96
#Mann= 5 ,-1 , 0
  3815.6     .11       0  4643.1     .15       0  4904.8     .07       0
  5043.6     .15       0  5689.8     .17       0
#XS Ineff= 4 ,-1
  5117.9  5176.5  268.46
Permanent Ineff=
       F       F       F       F
Bank Sta=4904.8,5043.6
XS Rating Curve= 0 ,0
Exp/Cntr=0.3,0.1

Type RM Length L Ch R = 1 ,11444   ,474,474,474
BEGIN DESCRIPTION:
SHEPARD BRANCH 19.0
END DESCRIPTION:
XS GIS Cut Line= 3
      3814217.83      10173161.1      3813641.17     10173741.26
      3813106.51     10174302.85
#Sta/Elev= 30
    4182  284.52  4358.7  273.87  4440.1  270.48    4585  263.16  4660.3  264.91
    4684  265.23  4712.3  260.04  4719.4  263.63  4726.4  265.27    4783  267.96
  4867.9  268.49  4900.5  266.59  4931.5  264.42    4981  263.99  4995.1  257.61
  4997.1  255.52  5009.4  256.13  5016.3  260.74  5030.4  263.69    5060   263.8
  5104.6  264.76  5165.1  267.56  5186.1  266.97  5221.3   270.1  5269.5  271.62
  5412.6  275.74  5490.3   279.8  5518.6  279.31  5639.4  284.36  5775.4   288.7
#Mann= 10 ,-1 , 0
    4182     .11       0  4440.1     .15       0  4660.3     .11       0
  4900.5     .15       0    4981     .09       0  5030.4     .15       0
    5060     .11       0  5104.6     .15       0  5269.5     .17       0
  5639.4     .11       0
#XS Ineff= 1 ,-1
    4450  4825.4  268.59
Permanent Ineff=
       F
Bank Sta=4981,5030.4
XS Rating Curve= 0 ,0
Exp/Cntr=0.3,0.1

Type RM Length L Ch R = 1 ,10970   ,507,507,507
BEGIN DESCRIPTION:
SHEPARD BRANCH 18.0
END DESCRIPTION:
XS GIS Cut Line= 3
      3814137.69     10172974.77       3813355.1     10173437.97
       3813039.3     10174197.43
#Sta/Elev= 30
  4090.6  288.47  4313.1  273.64  4344.3  273.18  4494.1  266.78  4671.4  261.19
  4685.5  256.18  4694.7  256.51  4701.1  259.87  4706.9  261.48  4781.1  260.32
  4940.9  261.24  4950.3  260.12  4956.6  258.07  4962.4  260.27  4985.2  260.24
  4993.6  256.24  5002.9  255.87  5005.6  253.41  5009.1  253.41  5014.2   256.3
  5031.2  260.92    5155  264.89  5238.2  269.91  5332.1  273.56  5382.4  276.15
  5436.6  277.37  5512.4  281.33    5576  282.36    5687  285.84  5822.5  288.55
#Mann= 6 ,-1 , 0
  4090.6     .11       0  4494.1     .15       0  4940.9     .09       0
  5031.2     .15       0  5332.1     .17       0    5576     .11       0
#XS Ineff= 2 , 0
       0  4927.1  261.55               0
Permanent Ineff=
       T       F
Bank Sta=4940.9,5031.2
XS Rating Curve= 0 ,0
Exp/Cntr=0.3,0.1

Type RM Length L Ch R = 1 ,10463   ,463,463,463
BEGIN DESCRIPTION:
SHEPARD BRANCH 17.0
END DESCRIPTION:
XS GIS Cut Line= 3
      3813817.82      10172461.1      3813221.99     10173085.26
      3812882.68      10173943.1
#Sta/Elev= 30
  4137.1  287.25  4434.1  267.69  4596.7  261.63  4716.1  260.52  4830.1   257.3
  4900.9  258.62    4915  254.16  4922.3  249.54  4934.7  246.81  4938.2  246.81
  4943.3  249.44  4950.6  256.24  4957.5  257.61  4964.7  258.26  4971.6  255.51
  4978.9  255.72  4985.8  250.61    4993  248.09    5017  252.39    5029  258.12
  5124.5  258.02  5156.1  256.48  5167.6   258.4  5431.8  269.03  5545.4  275.07
  5569.7  274.83  5720.9   280.7  5737.5  282.31  5901.9  286.41  5922.5  286.49
#Mann= 6 ,-1 , 0
  4137.1     .11       0  4716.1     .15       0  4900.9     .06       0
    5029     .15       0  5720.9     .17       0  5901.9     .11       0
Bank Sta=4900.9,5029
XS Rating Curve= 0 ,0
Exp/Cntr=0.3,0.1

Type RM Length L Ch R = 1 ,10000   ,527,527,527
BEGIN DESCRIPTION:
SHEPARD BRANCH 16.0
END DESCRIPTION:
XS GIS Cut Line= 3
      3813796.24     10172403.79      3813061.93     10172790.03
      3812805.67     10173912.35
#Sta/Elev= 30
  4170.3  288.38  4202.4   285.7  4240.8  284.26  4270.2  280.65  4439.7  268.65
    4516  264.44  4664.6  259.68  4781.4   257.6  4895.2  255.73  4973.2  256.45
    4982   254.1  4989.6   247.4  4995.2  246.64  4997.7  244.47  5011.3  246.23
  5038.9   255.7  5075.3  255.61    5221  254.62  5339.6  256.65  5494.3  263.66
  5537.3  265.14  5565.2  264.67  5616.5  268.28  5848.3  276.32  5939.4  278.47
  5965.3  281.07  6006.3  281.82  6042.7  283.79    6107  285.21  6151.2  284.42
#Mann= 8 ,-1 , 0
  4170.3     .11       0  4781.4     .17       0  4895.2     .15       0
  4973.2     .09       0  5038.9     .15       0  5075.3     .11       0
  6042.7     .17       0    6107     .11       0
Bank Sta=4973.2,5038.9
XS Rating Curve= 0 ,0
Exp/Cntr=0.3,0.1

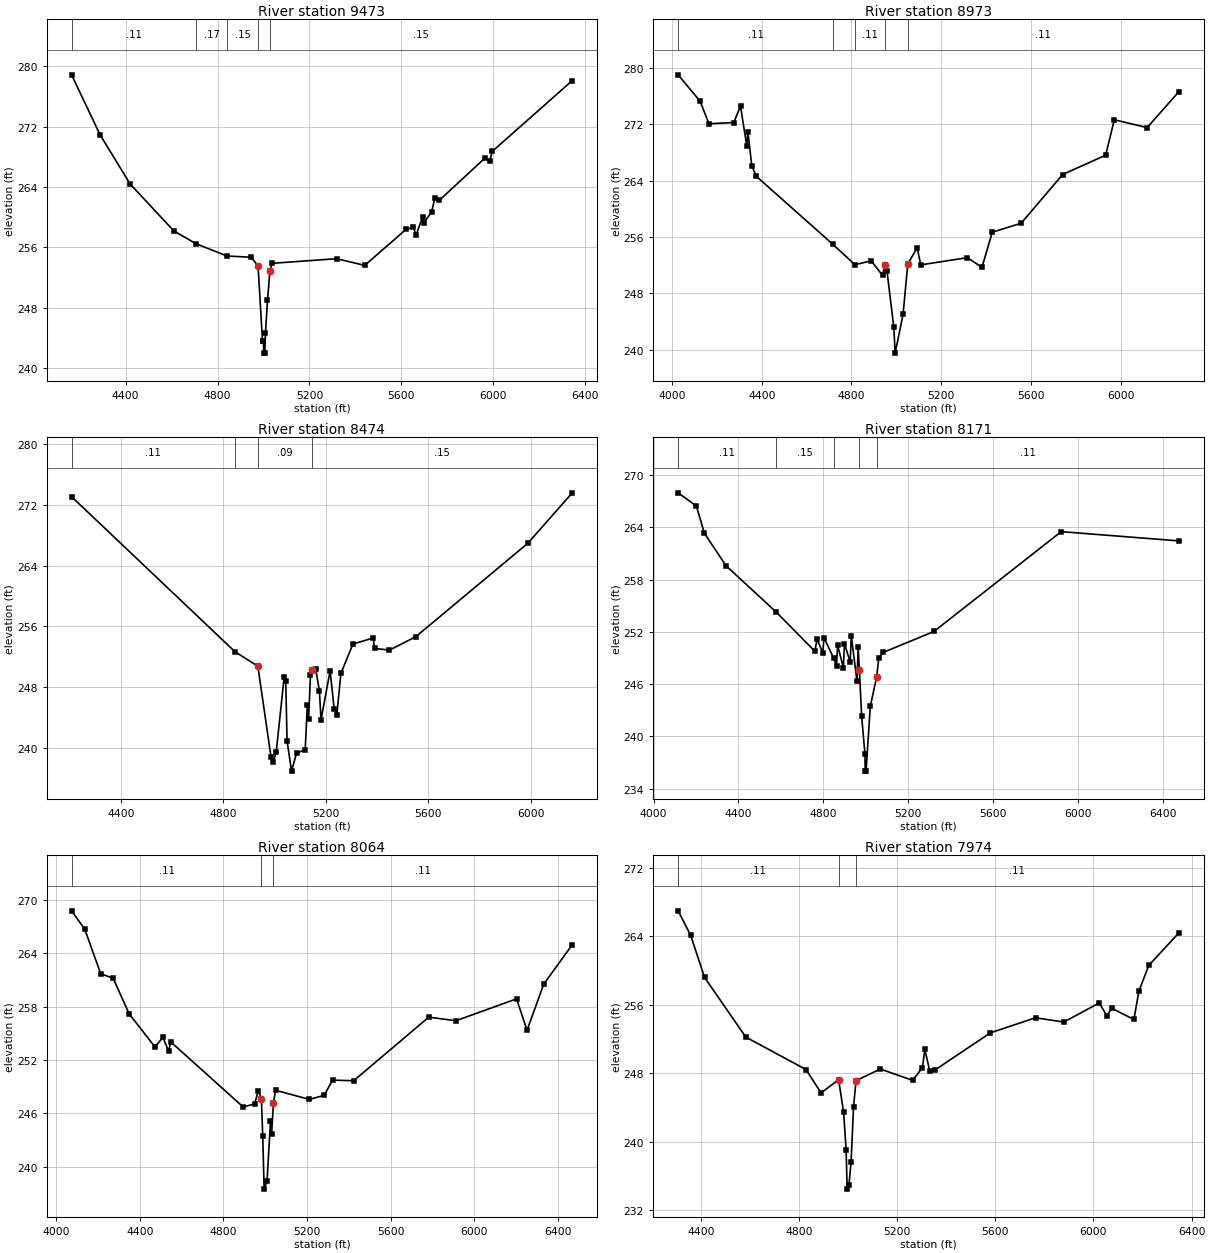
Type RM Length L Ch R = 1 ,9473    ,500,500,500
BEGIN DESCRIPTION:
SHEPARD BRANCH 15.0
END DESCRIPTION:
XS GIS Cut Line= 3
      3813659.93     10172358.35      3812834.64     10172484.63
      3811542.68     10172853.58
#Sta/Elev= 30
  4165.1  278.89  4288.6  270.96  4420.1  264.39    4610  258.18  4706.3  256.48
  4841.1  254.85  4947.3  254.68  4976.5  253.49  4995.8  243.55    5000  243.55
  5001.5  241.96  5005.5  241.96  5008.7  244.65  5017.5  248.95  5027.9  252.86
  5037.4  253.88    5319  254.49  5440.4   253.6  5619.9  258.37  5651.8  258.67
  5664.1  257.63  5692.7  260.06  5697.9  259.26  5731.7  260.69  5745.4  262.53
  5765.5  262.25  5963.8  267.85    5984  267.39    5995  268.72  6343.6  278.13
#Mann= 5 ,-1 , 0
  4165.1     .11       0  4706.3     .17       0  4841.1     .15       0
  4976.5     .09       0  5027.9     .15       0
Bank Sta=4976.5,5027.9
XS Rating Curve= 0 ,0
Exp/Cntr=0.3,0.1

Type RM Length L Ch R = 1 ,8973    ,499,499,499
BEGIN DESCRIPTION:
SHEPARD BRANCH 14.0
END DESCRIPTION:
XS GIS Cut Line= 3
      3813664.47     10172244.76      3812696.49     10172154.29
      3811492.66     10172521.88
#Sta/Elev= 30
  4027.8  278.98  4125.5  275.24    4165  272.04  4275.5  272.22  4305.6  274.55
  4333.4  268.91  4338.4  270.92  4355.8  266.09  4375.9   264.6  4716.5  254.97
  4815.3  252.07  4888.1  252.61  4938.4  250.55  4948.4  252.04  4958.5  251.12
  4988.6  243.19  4994.7  239.53  5029.9  245.04  5050.9  252.17  5092.7  254.46
  5108.6  252.04  5315.9  253.06  5381.5   251.7  5427.3  256.67    5556  257.94
  5740.9  264.85  5932.5  267.59    5971  272.61  6117.3   271.5  6258.7  276.59
#Mann= 5 ,-1 , 0
  4027.8     .11       0  4716.5     .15       0  4815.3     .11       0
  4948.4     .06       0  5050.9     .11       0
#XS Ineff= 2 , 0
       0  4948.4  252.04  5050.9       0  252.17
Permanent Ineff=
       F       F
Bank Sta=4948.4,5050.9
XS Rating Curve= 0 ,0
Exp/Cntr=0.3,0.1

Type RM Length L Ch R = 1 ,8474    ,303,303,303
BEGIN DESCRIPTION:
SHEPARD BRANCH 13.0
END DESCRIPTION:
XS GIS Cut Line= 3
      3813436.44     10171984.43      3812663.94     10171805.75
      3811533.77     10172076.28
#Sta/Elev= 30
  4207.1  273.07  4844.7  252.65  4934.4  250.73  4985.7  238.78  4994.7  238.08
  5006.4  239.48  5037.1  249.31  5043.3  248.77  5048.4  240.91  5065.8   236.9
  5085.3  239.25  5119.4  239.74  5127.4  245.56  5132.5  243.79  5139.9  249.57
  5144.7  250.27  5160.5  250.33  5174.6   247.5  5181.1  243.68  5216.6  250.13
  5232.5  245.05  5242.8  244.34  5258.7   249.8  5305.8  253.65  5384.8  254.45
  5389.9  253.08  5448.4  252.85  5551.2  254.62  5988.8  266.94  6162.1  273.58
#Mann= 4 ,-1 , 0
  4207.1     .11       0  4844.7     .15       0  4934.4     .09       0
  5144.7     .15       0
#XS Ineff= 2 , 0
       0                  5144.7       0  250.27
Permanent Ineff=
       F       T
Bank Sta=4934.4,5144.7
XS Rating Curve= 0 ,0
Exp/Cntr=0.3,0.1

Type RM Length L Ch R = 1 ,8171    ,107,107,107
BEGIN DESCRIPTION:
Mapping XS e5dcdd96
END DESCRIPTION:
XS GIS Cut Line= 3
      3813302.22     10171862.89      3812459.94     10171595.18
      3810983.04     10171595.66
#Sta/Elev= 30
  4116.2  267.97  4202.1  266.45  4239.6  263.35  4341.6   259.6  4578.6  254.27
  4760.8  249.77  4771.3  251.18  4798.3  249.56  4803.5  251.34    4849     249
  4862.8  248.11    4868  250.46    4895  247.89  4900.3  250.66  4927.3  248.52
  4932.5  251.54  4959.5  246.31  4964.8  250.23  4970.7  247.61  4981.2  242.34
    4997  237.93  4997.8     236  5002.1     236  5022.1  243.44  5052.1  246.83
  5062.1  248.98  5082.1  249.63  5322.1  252.04  5922.1  263.51  6476.9  262.45
#Mann= 5 ,-1 , 0
  4116.2     .11       0  4578.6     .15       0    4849     .11       0
  4970.7     .06       0  5052.1     .11       0
Bank Sta=4970.7,5052.1
XS Rating Curve= 0 ,0
Exp/Cntr=0.3,0.1

Type RM Length L Ch R = 1 ,8064    ,90,90,90
BEGIN DESCRIPTION:
Mapping XS 0b9d6340
END DESCRIPTION:
XS GIS Cut Line= 4
      3813350.85     10171765.68      3812466.38     10171490.13
      3812208.46      10171449.7      3811001.45     10171421.95
#Sta/Elev= 30
  4073.6  268.77  4136.9  266.69  4212.9  261.69  4272.3  261.19  4349.1  257.18
  4472.6  253.46  4510.4  254.54  4537.6  252.99  4548.1  254.03  4893.7  246.72
  4948.9  247.04    4967  248.56  4981.4  247.64    4988  243.41  4994.5  237.47
  5008.6  238.42    5025  245.14  5030.1  243.62    5039  247.19  5049.1  248.59
  5211.1  247.56  5281.7  248.02  5321.7  249.73  5422.8  249.66  5781.8  256.81
  5911.9  256.41  6201.9  258.87  6251.9  255.33    6332  260.53  6468.4  264.96
#Mann= 3 , 0 , 0
  4073.6     .11       0  4981.4     .06       0    5039     .11       0
Bank Sta=4981.4,5039
XS Rating Curve= 0 ,0
Exp/Cntr=0.3,0.1

Type RM Length L Ch R = 1 ,7974    ,499,499,499
BEGIN DESCRIPTION:
SHEPARD BRANCH 12.0
END DESCRIPTION:
XS GIS Cut Line= 3
      3813117.89     10171264.01      3812440.13     10171405.16
      3811095.08     10171314.52
#Sta/Elev= 30
  4307.7  266.95  4358.8  264.08  4415.4  259.17  4583.5  252.21  4828.7  248.43
    4890   245.7  4961.5  247.24  4981.9  243.46  4992.1  239.09  4996.4  234.47
  5003.6  234.97  5012.3  237.58  5022.3  244.01  5032.4  247.12  5131.3  248.49
  5262.9  247.17    5303  248.63    5313  250.77    5333  248.24  5353.1  248.35
    5580  252.71    5764  254.47    5879  253.97  6023.6  256.19  6054.7   254.7
  6074.7  255.57  6164.9  254.27    6185  257.55  6225.1  260.57  6348.1  264.38
#Mann= 3 , 0 , 0
  4307.7     .11       0  4961.5     .06       0  5032.4     .11       0
Bank Sta=4961.5,5032.4
XS Rating Curve= 0 ,0
Exp/Cntr=0.3,0.1

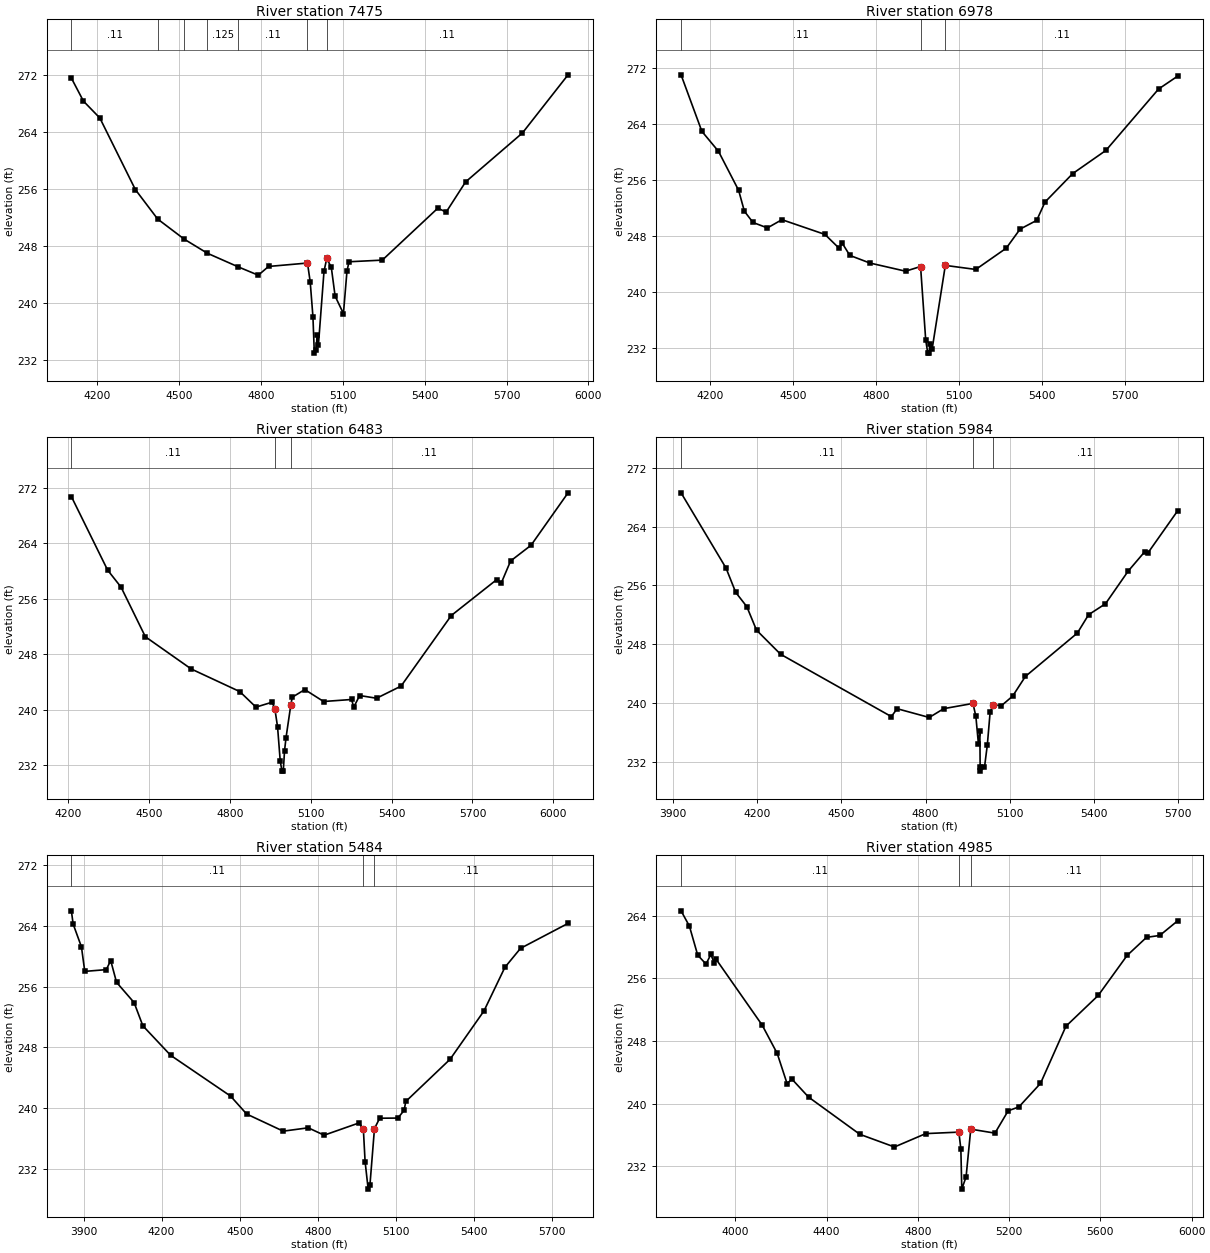
Type RM Length L Ch R = 1 ,7475    ,497,497,497
BEGIN DESCRIPTION:
SHEPARD BRANCH 11.0
END DESCRIPTION:
XS GIS Cut Line= 3
      3813142.11      10171024.6      3812248.07     10170977.03
      3811338.81     10170804.95
#Sta/Elev= 30
  4104.7   271.6    4149  268.36  4209.1  265.99  4339.3  255.93  4421.1  251.79
  4517.9  248.98    4603  246.99    4717  245.06  4789.9   243.9  4827.4  245.13
  4970.2  245.61  4980.2  242.96  4990.2  238.07  4995.3  232.95  5002.6  233.45
  5005.2  235.44  5010.4  234.14  5030.8  244.46  5040.9  246.25  5057.6  244.99
  5071.5  240.96    5102  238.51    5115  244.48  5122.4  245.79  5244.5  246.02
    5448  253.32  5478.6  252.77  5549.8  257.01  5758.2  263.89  5925.4  272.06
#Mann= 7 ,-1 , 0
  4104.7     .11       0  4421.1    .125       0  4517.9     .11       0
    4603    .125       0    4717     .11       0  4970.2     .06       0
  5040.9     .11       0
Bank Sta=4970.2,5040.9
XS Rating Curve= 0 ,0
Exp/Cntr=0.3,0.1

Type RM Length L Ch R = 1 ,6978    ,495,495,495
BEGIN DESCRIPTION:
SHEPARD BRANCH 10.0
END DESCRIPTION:
XS GIS Cut Line= 3
       3813137.8     10170305.92      3812267.64     10170557.89
      3811378.63     10170609.34
#Sta/Elev= 30
  4094.1  271.05  4169.3  262.97  4229.4  260.11  4302.3  254.53  4323.1  251.54
  4354.3  249.93  4406.4  249.15  4458.9  250.33  4614.6  248.22  4665.7  246.24
    4677  246.97  4704.5  245.22  4776.9  244.13  4906.1  242.96  4960.4  243.63
    4979  233.09  4986.5  231.24  4991.2  231.24    4994  232.57  5002.4  231.87
  5049.9  243.79  5160.1  243.21  5270.2  246.25  5320.3  248.98  5380.4  250.23
  5410.5  252.85  5510.6  256.92  5630.8  260.24  5821.2  269.02  5890.5  270.87
#Mann= 3 , 0 , 0
  4094.1     .11       0  4960.4     .06       0  5049.9     .11       0
#XS Ineff= 2 , 0
       0  4960.4  243.63  5049.9       0  243.79
Permanent Ineff=
       F       F
Bank Sta=4960.4,5049.9
XS Rating Curve= 0 ,0
Exp/Cntr=0.3,0.1

Type RM Length L Ch R = 1 ,6483    ,499,499,499
BEGIN DESCRIPTION:
SHEPARD BRANCH 9.0
END DESCRIPTION:
XS GIS Cut Line= 3
      3813112.03     10170083.19      3812325.02     10170104.51
      3811362.62     10170535.03
#Sta/Elev= 30
  4212.7  270.72  4346.9  260.13  4396.9  257.66    4487  250.51    4657  245.86
  4837.1   242.6  4897.1  240.36  4957.1  241.07  4967.2   240.1  4977.2  237.52
  4987.2  232.54  4993.7  231.13  4998.4  231.13  5003.1  234.08  5008.6  235.96
  5026.3  240.66  5031.8  241.79  5078.2  242.89  5147.8  241.17  5251.5  241.46
  5259.8  240.37  5281.7  242.03  5344.3  241.64  5435.1  243.39  5621.4  253.57
  5789.3  258.73    5807  258.28  5841.2  261.43  5917.1   263.7  6054.3  271.26
#Mann= 3 , 0 , 0
  4212.7     .11       0  4967.2     .06       0  5026.3     .11       0
Bank Sta=4967.2,5026.3
XS Rating Curve= 0 ,0
Exp/Cntr=0.3,0.1

Type RM Length L Ch R = 1 ,5984    ,500,500,500
BEGIN DESCRIPTION:
SHEPARD BRANCH 8.0
END DESCRIPTION:
XS GIS Cut Line= 3
      3813089.35     10170037.99      3812057.73     10169753.98
      3811361.03     10169718.53
#Sta/Elev= 30
    3930   268.6  4090.1  258.36  4124.5  255.06  4164.1  253.11  4198.5  249.92
  4284.2  246.64  4678.3  238.16  4699.1  239.23  4813.2  238.04    4865  239.24
  4968.8  239.95  4979.1  238.21  4988.2  234.48  4993.4  236.17  4994.4  231.24
  4994.9  230.74  5009.9  231.28  5019.9  234.28  5029.9  238.74  5039.9  239.77
    5070  239.64    5110  240.94  5155.4  243.62  5340.3  249.52  5380.4  252.02
  5440.5  253.51  5520.6  257.92  5580.6  260.61  5590.6  260.37  5697.6  266.17
#Mann= 3 , 0 , 0
    3930     .11       0  4968.8     .06       0  5039.9     .11       0
Bank Sta=4968.8,5039.9
XS Rating Curve= 0 ,0
Exp/Cntr=0.3,0.1

Type RM Length L Ch R = 1 ,5484    ,499,499,499
BEGIN DESCRIPTION:
SHEPARD BRANCH 7.0
END DESCRIPTION:
XS GIS Cut Line= 3
      3813153.92     10169824.95       3812125.3     10169318.36
      3811365.64     10169363.37
#Sta/Elev= 30
  3853.4  265.96  3860.2  264.22  3892.1  261.22  3904.8     258  3987.5  258.23
  4004.4  259.43  4026.9  256.56  4094.3   253.9  4127.9  250.85  4234.6  246.97
  4464.8  241.61  4526.6  239.25    4667     237  4763.1  237.44  4824.2  236.47
    4959  238.09  4974.9  237.22  4981.5     233  4993.3  229.38    5000  229.88
  5017.5  237.34  5037.5   238.7  5107.6  238.72  5131.5  239.75  5137.7   240.9
    5308  246.45  5438.2  252.81  5518.4  258.53  5578.5  261.03    5761  264.31
#Mann= 3 , 0 , 0
  3853.4     .11       0  4974.9     .06       0  5017.5     .11       0
Bank Sta=4974.9,5017.5
XS Rating Curve= 0 ,0
Exp/Cntr=0.3,0.1

Type RM Length L Ch R = 1 ,4985    ,498,498,498
BEGIN DESCRIPTION:
SHEPARD BRANCH 6.0
END DESCRIPTION:
XS GIS Cut Line= 3
      3813254.02     10169505.41      3812208.28      10168843.9
       3811317.3     10169140.64
#Sta/Elev= 30
  3762.6  264.65  3799.1   262.7  3835.6  258.98    3872  257.84  3893.2  259.08
  3908.5  257.95  3914.4  258.53  4117.9  250.04    4184  246.41  4227.2  242.56
  4248.4  243.13  4321.3  240.83    4546  236.07  4697.7  234.45  4834.9  236.16
    4980  236.35  4988.7  234.19  4992.8  229.06  5011.6  230.63  5032.1  236.73
  5138.1  236.22  5196.1  239.08  5242.9  239.57  5337.7  242.58  5449.2  249.89
  5590.7  253.83  5717.2  258.94  5802.4  261.26  5860.4   261.5  5939.1  263.38
#Mann= 3 , 0 , 0
  3762.6     .11       0    4980     .06       0  5032.1     .11       0
Bank Sta=4980,5032.1
XS Rating Curve= 0 ,0
Exp/Cntr=0.3,0.1