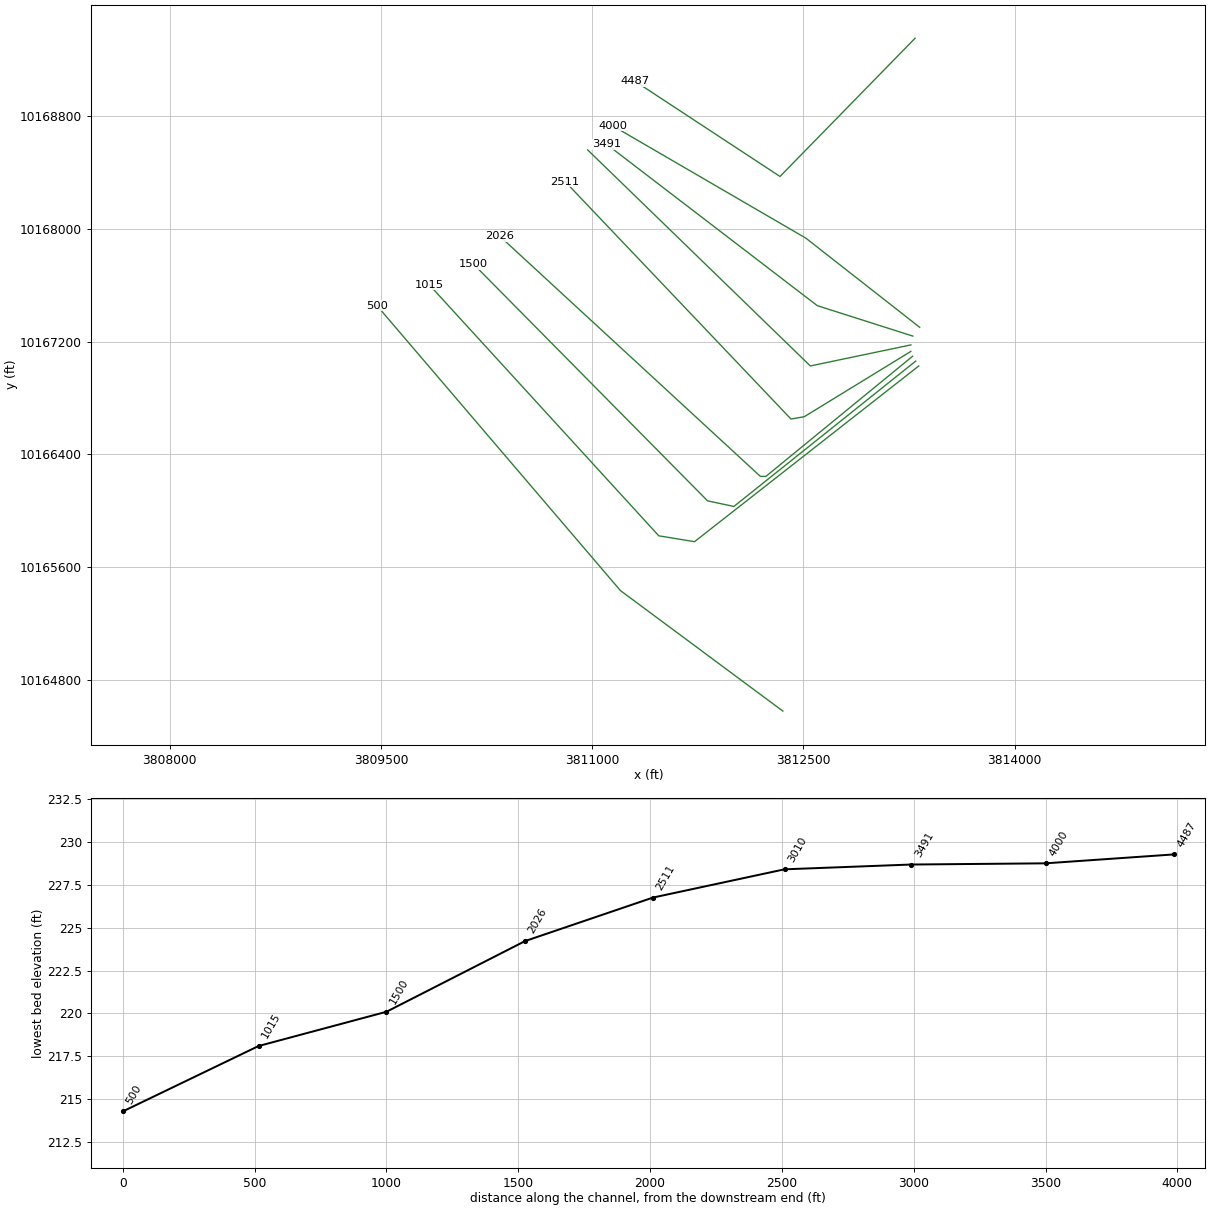
HEC-RAS study SHEPARD BRANCH.prj: SHEPARD BRANCH Base Level Engineering

--- SHEPARD BRANCH.g01 (geometry) --- (continued)

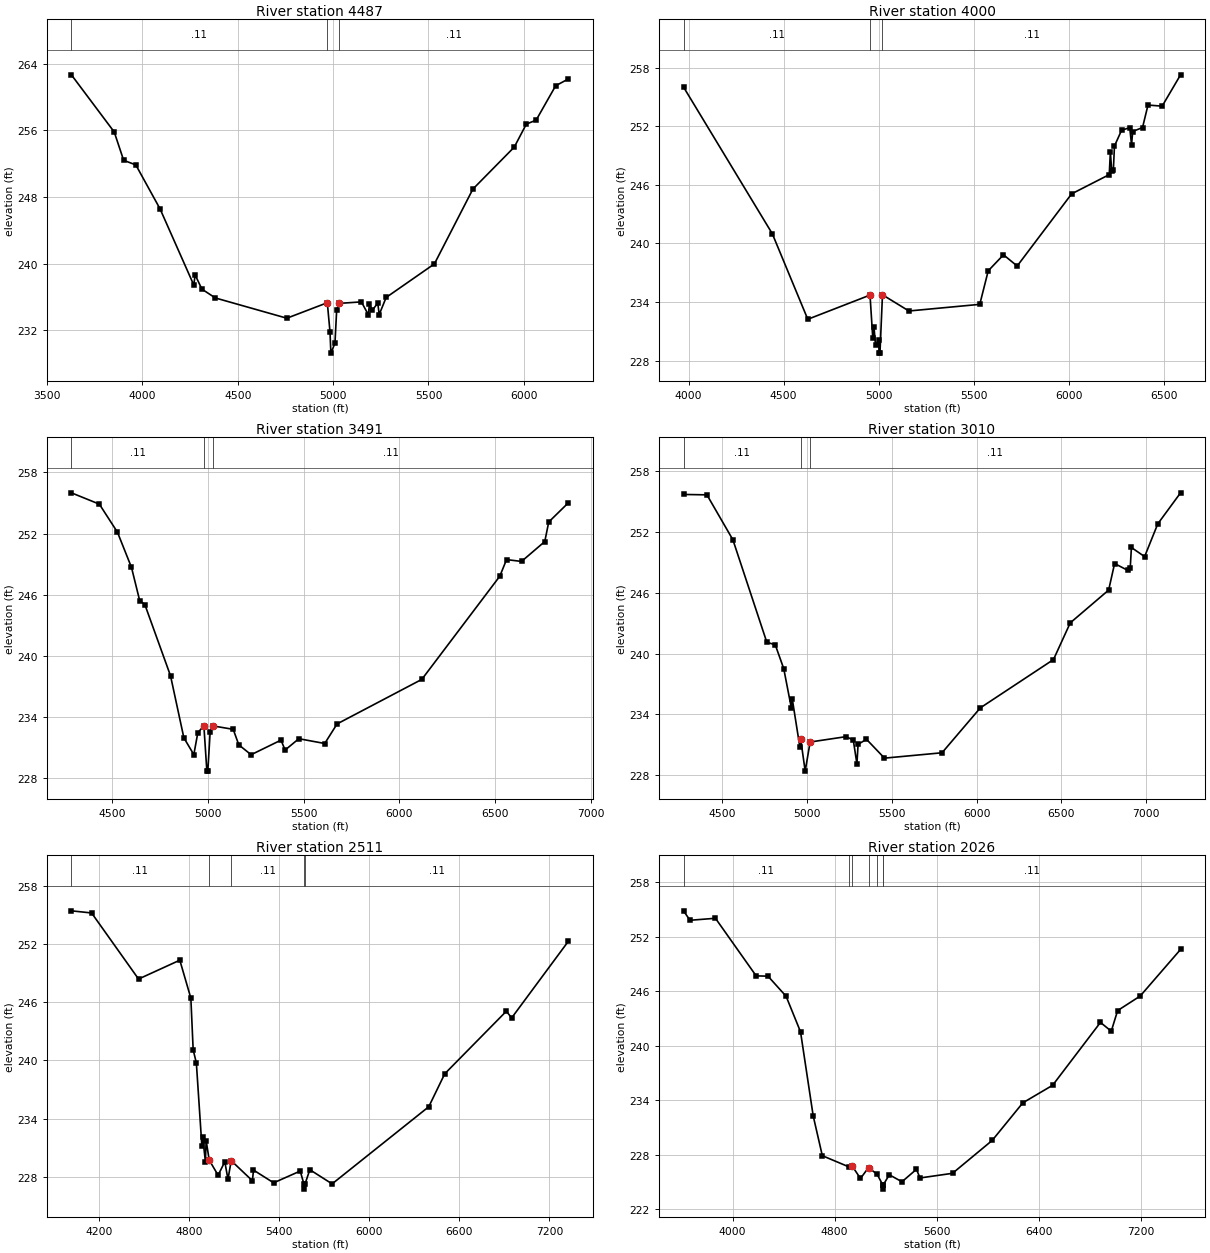
Type RM Length L Ch R = 1 ,4487    ,487,487,487
BEGIN DESCRIPTION:
SHEPARD BRANCH 5.0
END DESCRIPTION:
XS GIS Cut Line= 3
      3813292.77     10169353.72      3812333.66     10168372.38
      3811302.02     10169049.68
#Sta/Elev= 30
  3627.8  262.68  3852.4  255.82  3901.8  252.42  3965.6  251.87  4092.9  246.58
  4269.6  237.45  4276.6  238.67    4312  236.96  4382.8   235.9  4757.5  233.47
  4969.7  235.33  4983.8  231.82  4988.4  229.28  5009.8  230.47  5018.9  234.51
  5030.9  235.25  5148.5  235.43  5184.7  233.89  5190.7  235.18  5205.7  234.43
  5234.2  235.28  5241.9  233.91  5278.1  235.96  5531.2  239.99  5733.1  248.97
  5950.1  254.01  6013.3  256.77  6064.6  257.24  6167.1  261.37  6234.1  262.19
#Mann= 3 ,-1 , 0
  3627.8     .11       0  4969.7     .07       0  5030.9     .11       0
#XS Ineff= 2 ,-1
  5278.1    5306  235.96    5306  5329.3  236.23
Permanent Ineff=
       F       F
Bank Sta=4969.7,5030.9
XS Rating Curve= 0 ,0
Exp/Cntr=0.3,0.1

Type RM Length L Ch R = 1 ,4000    ,509,509,509
BEGIN DESCRIPTION:
SHEPARD BRANCH 8.5
END DESCRIPTION:
XS GIS Cut Line= 3
      3813325.53     10167301.78      3812517.11     10167934.68
        3811145.     10168732.31
#Sta/Elev= 30
  3973.3  256.04  4440.5  240.99  4626.8  232.23  4954.1  234.71  4968.6   230.3
  4974.9  231.47    4983  229.56    5000  230.11  5001.4  228.76  5006.3  228.76
  5019.6  234.74  5158.6  233.08  5531.2  233.76  5575.7   237.2    5656  238.84
  5727.9  237.69  6014.4  245.09  6212.2  247.06    6218  249.42  6225.2  247.38
  6233.7  247.51  6239.5  249.99  6276.7   251.6  6319.8  251.88  6329.3  250.13
  6335.5  251.48  6387.2  251.89  6415.8  254.19  6490.3  254.08  6587.1  257.29
#Mann= 3 ,-1 , 0
  3973.3     .11       0  4954.1     .07       0  5019.6     .11       0
Bank Sta=4954.1,5019.6
XS Rating Curve= 0 ,0
Exp/Cntr=0.3,0.1

Type RM Length L Ch R = 1 ,3491    ,481,481,481
BEGIN DESCRIPTION:
SHEPARD BRANCH 4.0
END DESCRIPTION:
XS GIS Cut Line= 3
      3813276.91     10167239.26      3812598.41     10167455.41
      3811103.36     10168600.35
#Sta/Elev= 30
  4287.9  255.99  4433.8  254.88  4528.3  252.13  4601.7  248.67  4644.4  245.42
  4671.4  245.03  4805.5  238.04  4875.1  231.96  4927.1  230.31  4948.1  232.47
  4979.6  233.13  4995.2  228.69  5000.2  228.69  5012.3  232.52  5025.9  233.13
  5132.8  232.79  5161.9  231.27  5226.2   230.3  5382.1  231.73  5403.8  230.76
  5475.5  231.87  5610.6   231.4    5675  233.32  6117.5  237.69  6524.6  247.81
  6559.9  249.44  6638.1  249.26  6759.4  251.21  6780.2  253.13  6883.1  255.02
#Mann= 3 ,-1 , 0
  4287.9     .11       0  4979.6     .07       0  5025.9     .11       0
Bank Sta=4979.6,5025.9
XS Rating Curve= 0 ,0
Exp/Cntr=0.3,0.1

Type RM Length L Ch R = 1 ,3010    ,499,499,499
BEGIN DESCRIPTION:
SHEPARD BRANCH 3.0
END DESCRIPTION:
XS GIS Cut Line= 3
       3813263.1     10167176.76      3812548.84     10167027.48
      3810967.85     10168561.08
#Sta/Elev= 30
  4270.3  255.69  4408.5  255.65  4561.7  251.22  4761.7  241.12  4811.7  240.86
  4861.7  238.51  4906.5  234.64  4911.6  235.56  4956.5  230.81  4961.6  231.57
  4988.1  228.41  5017.3  231.28  5229.5  231.81    5272  231.47  5293.3  229.12
  5300.2  231.05  5349.7  231.55  5455.9  229.69  5795.4  230.22  6021.5  234.65
  6452.9  239.41  6551.9  243.03  6778.3  246.26  6813.5  248.88  6891.5   248.2
  6905.6  248.43  6912.6  250.46  6990.5  249.56  7068.2  252.79  7202.6  255.85
#Mann= 3 ,-1 , 0
  4270.3     .11       0  4961.6     .07       0  5017.3     .11       0
Bank Sta=4961.6,5017.3
XS Rating Curve= 0 ,0
Exp/Cntr=0.3,0.1

Type RM Length L Ch R = 1 ,2511    ,485,485,485
BEGIN DESCRIPTION:
SHEPARD BRANCH 2.0
END DESCRIPTION:
XS GIS Cut Line= 4
       3813262.5     10167130.59      3812506.21     10166667.25
       3812411.6     10166650.61      3810808.13     10168335.87
#Sta/Elev= 30
    4017   255.4  4151.5  255.18  4464.1  248.38  4738.8  250.32  4812.3  246.41
  4827.7   241.1    4849  239.74  4885.7  231.19  4891.6  232.08    4909   229.6
  4914.1  231.76  4934.5  229.75  4993.7  228.19  5038.4  229.58  5059.5  227.76
  5080.9  229.69  5222.1  227.62  5229.3  228.72  5363.6  227.41  5540.4  228.62
  5565.6  227.26  5566.1  226.76  5571.9  227.26  5604.3  228.76  5752.7   227.3
  6396.3  235.24  6502.6  238.63  6912.8  245.07    6948  244.38  7326.2  252.28
#Mann= 5 ,-1 , 0
    4017     .11       0  4934.5     .07       0  5080.9     .11       0
  5565.6     .09       0  5571.9     .11       0
Bank Sta=4934.5,5080.9
XS Rating Curve= 0 ,0
Exp/Cntr=0.3,0.1

Type RM Length L Ch R = 1 ,2026    ,526,526,526
BEGIN DESCRIPTION:
SHEPARD BRANCH 4.5
END DESCRIPTION:
XS GIS Cut Line= 4
        3813275.     10167096.13      3812233.64     10166243.63
      3812194.44     10166243.22      3810345.71     10167946.85
#Sta/Elev= 30
    3615  254.85    3666  253.81  3865.5  254.03  4184.9  247.69  4277.5  247.66
  4419.6  245.45    4533  241.53  4632.3  232.28  4703.9   227.9  4910.4  226.68
  4938.6  226.75  5003.2  225.39  5066.7   226.6  5134.2  225.84    5177  224.72
  5177.5  224.22  5183.3  224.72  5229.4   225.8  5328.7  225.03  5442.1   226.4
  5470.5  225.45  5725.1  225.96  6036.4  229.58  6276.9  233.72  6510.5  235.65
  6885.6  242.57  6970.4   241.6  7020.3  243.87  7197.2  245.47    7514   250.6
#Mann= 7 ,-1 , 0
    3615     .11       0  4910.4     .15       0  4938.6     .07       0
  5066.7     .11       0  5134.2     .11       0    5177     .12       0
  5183.3     .11       0
Bank Sta=4938.6,5066.7
XS Rating Curve= 0 ,0
Exp/Cntr=0.3,0.1

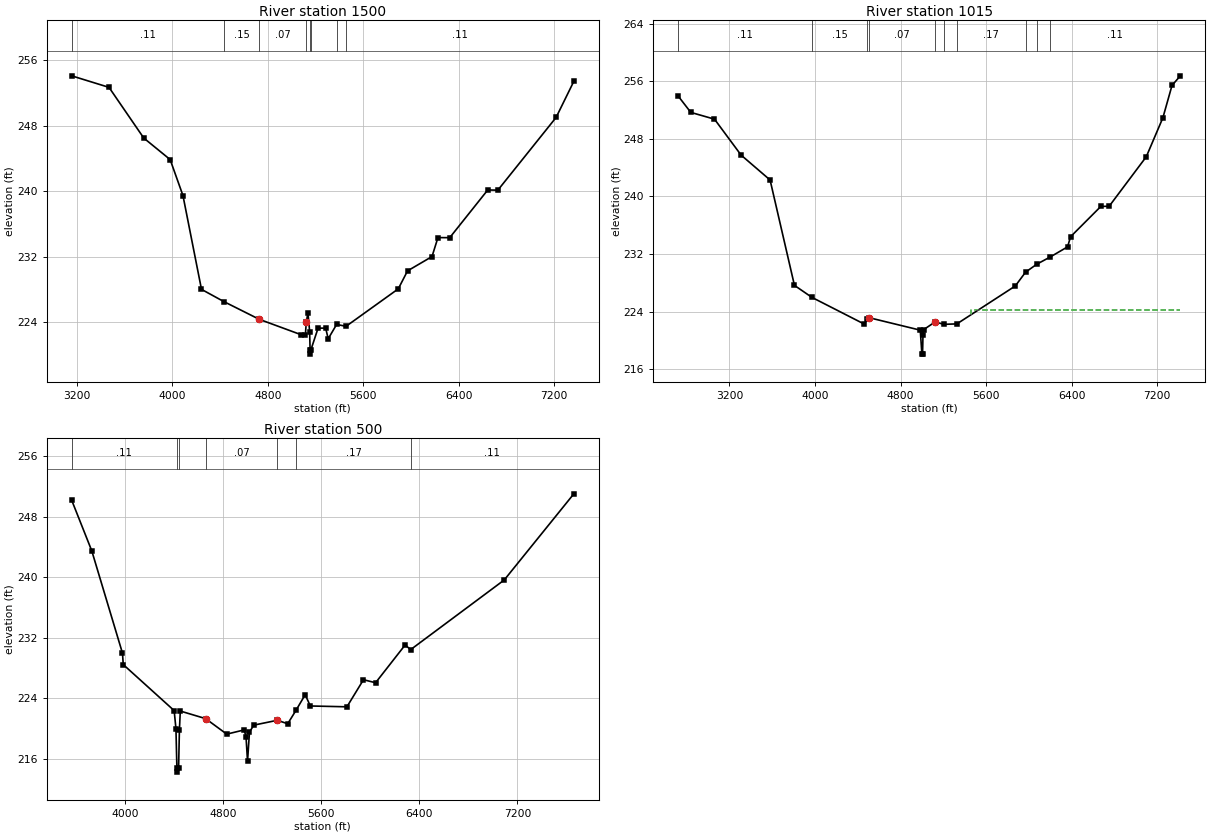
Type RM Length L Ch R = 1 ,1500    ,485,485,485
BEGIN DESCRIPTION:
SHEPARD BRANCH 3.5
END DESCRIPTION:
XS GIS Cut Line= 4
      3813296.94     10167061.72      3812006.21     10166030.09
      3811819.33     10166069.83      3810156.96     10167750.47
#Sta/Elev= 30
  3156.6  254.12  3469.5  252.71  3760.9  246.51  3981.8  243.88  4089.1  239.48
  4244.4  228.01    4431  226.52  4729.5  224.34  5079.7  222.46    5115  222.49
  5122.1  223.97  5136.3  225.16  5150.4  222.85  5154.3  220.59  5154.8  220.09
  5160.6  220.59  5221.1  223.27  5284.7  223.27    5306  221.97  5376.5  223.72
  5455.5  223.49  5892.9  228.07  5970.7  230.27  6175.7  232.02  6225.3  234.34
  6324.2  234.33  6642.4  240.16  6727.3  240.14  7215.2  249.03  7363.9  253.45
#Mann= 8 ,-1 , 0
  3156.6     .11       0    4431     .15       0  4729.5     .07       0
  5122.1     .11       0  5154.3     .12       0  5160.6     .11       0
  5376.5     .17       0  5455.5     .11       0
Bank Sta=4729.5,5122.1
XS Rating Curve= 0 ,0
Exp/Cntr=0.3,0.1

Type RM Length L Ch R = 1 ,1015    ,515,515,515
BEGIN DESCRIPTION:
SHEPARD BRANCH 1.0
END DESCRIPTION:
XS GIS Cut Line= 4
      3813318.86     10167027.28      3811726.69     10165780.09
      3811472.86     10165821.65      3809842.01     10167605.12
#Sta/Elev= 30
  2720.3  253.95    2839  251.67  3060.5  250.73  3309.2  245.74  3580.4  242.28
  3808.2  227.64    3972  225.97  4462.8  222.25  4488.3  223.01  4506.2  223.15
  4984.8  221.42  5000.1  218.09    5006  218.09  5010.4  220.79  5017.2   221.5
  5123.3  222.56    5207  222.23  5327.3  222.29  5873.8  227.56  5969.2  229.47
  6075.4  230.59  6199.5  231.58  6362.2  232.99  6390.6   234.4  6673.6  238.61
  6751.3  238.63  7098.5  245.51  7253.9  250.93    7339  255.41  7416.7  256.75
#Mann= 10 ,-1 , 0
  2720.3     .11       0    3972     .15       0  4488.3     .11       0
  4506.2     .07       0  5123.3     .11       0    5207     .15       0
  5327.3     .17       0  5969.2     .11       0  6075.4     .17       0
  6199.5     .11       0
#XS Ineff= 2 , 0
       0                  5456.3       0   224.2
Permanent Ineff=
       F       T
Bank Sta=4506.2,5123.3
XS Rating Curve= 0 ,0
Exp/Cntr=0.3,0.1

Type RM Length L Ch R = 1 ,500     ,0,0,0
BEGIN DESCRIPTION:
SHEPARD BRANCH 1.5
END DESCRIPTION:
XS GIS Cut Line= 3
      3812353.82      10164577.5      3811200.34     10165433.17
      3809472.15     10167455.28
#Sta/Elev= 30
  3563.8  250.21  3728.1   243.5  3978.5  229.98  3984.7  228.48  4399.9   222.4
  4414.5  220.02  4422.3  214.77  4422.8  214.27    4436  214.77  4442.8  219.84
    4450  222.34  4656.5  221.34  4828.8  219.29  4971.6  219.85  4986.3  218.88
  4998.4  215.71  5014.3  219.57  5049.9  220.48  5241.5  221.12  5326.1  220.66
    5395  222.47  5468.8   224.5  5510.5  223.01  5809.1   222.9  5944.1  226.48
  6042.9  226.08  6284.4  231.08  6328.6  230.45  7092.4  239.66    7660  251.04
#Mann= 7 ,-1 , 0
  3563.8     .11       0  4422.3     .09       0    4436     .11       0
  4656.5     .07       0  5241.5     .11       0    5395     .17       0
  6328.6     .11       0
Bank Sta=4656.5,5241.5
XS Rating Curve= 0 ,0
Exp/Cntr=0.3,0.1

Chan Stop Cuts=-1
Use User Specified Reach Order=0
Composite Channel Slope=5