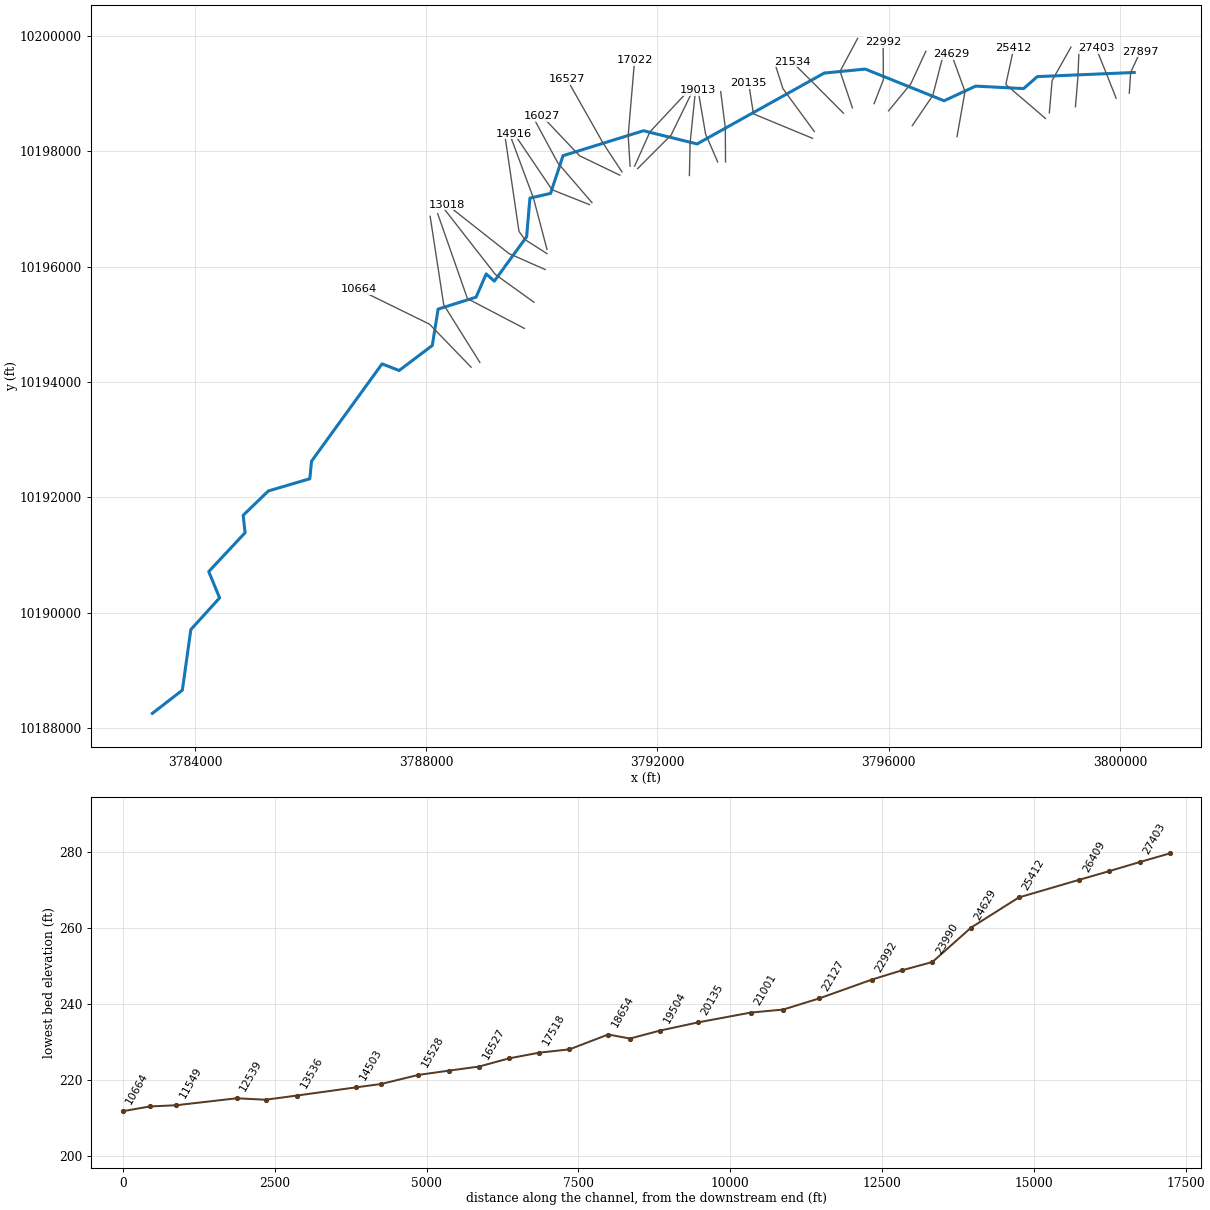
--- SMITH BRANCH.prj (project) ---

Proj Title=SMITH BRANCH Base Level Engineering
Current Plan=p01
Default Exp/Contr=0.3,0.1
English Units
Geom File=g01
Flow File=f01
Plan File=p01
Y Axis Title=Elevation
X Axis Title(PF)=Main Channel Distance
X Axis Title(XS)=Station
BEGIN DESCRIPTION:
SMITH BRANCH
END DESCRIPTION:
DSS Export Rating Curves= 0
DSS Export Rating Curve Sorted= 0
DSS Export Volume Flow Curves= 0
DXF OffsetX= 0
DXF OffsetY= 0
DXF ScaleX= 1
DXF ScaleY= 10

--- SMITH BRANCH.p01 (plan) ---

Plan Title=Multiple Run
Short Identifier=Multiple
Geom File=g01
Flow File=f01
Subcritical Flow
K Sum by GR= 0
Std Step Tol= 0.01
Critical Tol= 0.01
Num of Std Step Trials= 20
Max Error Tol= 0.3
Flow Tol Ratio= 0.001
Split Flow NTrial= 30
Split Flow Tol= 0.02
Split Flow Ratio= 0.02
Log Output Level= 0
Friction Slope Method= 1
Unsteady Friction Slope Method= 2
Unsteady Bridges Friction Slope Method= 1
Parabolic Critical Depth
Global Vel Dist=  1 , 1 , 1
Global Log Level= 0
CheckData=True
Encroach Param= -1, 0, 0, 0
BEGIN DESCRIPTION:
Multiple Run
END DESCRIPTION:

--- SMITH BRANCH.f01 (steady flow) ---

Flow Title=Multiple
Program Version=4.10
Number of Profiles= 7
Profile Names=10-year,25-year,50-year,1pct_min,100-year,1pct_plu,500-year
River Rch & RM=SMITH BRANCH,Reach-1         ,27897
     574     778    1053     471    1421    4291    2668
River Rch & RM=SMITH BRANCH,Reach-1         ,26899
    1146    1615    2243    1024    3091    9335    6078
River Rch & RM=SMITH BRANCH,Reach-1         ,22992
    1374    1948    2716    1244    3757   11346    7432
River Rch & RM=SMITH BRANCH,Reach-1         ,19504
    1727    2471    3465    1594    4814   14538    9613
River Rch & RM=SMITH BRANCH,Reach-1         ,17022
    1657    2333    3234    1469    4437   13400    8640
River Rch & RM=SMITH BRANCH,Reach-1         ,9998
    1839    2592    3596    1634    4934   14900    9611
River Rch & RM=SMITH BRANCH,Reach-1         ,6165
    1965    2774    3853    1751    5288   15970   10318
Boundary for River Rch & Prof#=SMITH BRANCH,Reach-1         , 1
Up Type= 0
Dn Type= 3
Dn Slope=0.005
Boundary for River Rch & Prof#=SMITH BRANCH,Reach-1         , 2
Up Type= 0
Dn Type= 3
Dn Slope=0.005
Boundary for River Rch & Prof#=SMITH BRANCH,Reach-1         , 3
Up Type= 0
Dn Type= 3
Dn Slope=0.005
Boundary for River Rch & Prof#=SMITH BRANCH,Reach-1         , 4
Up Type= 0
Dn Type= 3
Dn Slope=0.005
Boundary for River Rch & Prof#=SMITH BRANCH,Reach-1         , 5
Up Type= 0
Dn Type= 3
Dn Slope=0.005
Boundary for River Rch & Prof#=SMITH BRANCH,Reach-1         , 6
Up Type= 0
Dn Type= 3
Dn Slope=0.005
Boundary for River Rch & Prof#=SMITH BRANCH,Reach-1         , 7
Up Type= 0
Dn Type= 3
Dn Slope=0.005
DSS Import GetInterval= 0
DSS Import GetPeak= 0
DSS Import FillOption= 0

--- SMITH BRANCH.g01 (geometry) ---

Geom Title=Existing Conditions
Program Version=4.10

River Reach=SMITH BRANCH    ,Reach-1
Reach XY= 30
      3800248.23     10199366.84      3798570.61     10199295.18
      3798334.78     10199087.65      3797504.61     10199130.42
      3796958.78     10198876.44      3795594.83     10199425.69
      3794885.36     10199356.47      3792685.75     10198128.21
      3791758.14     10198356.87      3790367.41     10197924.27
      3790151.81      10197270.6      3789794.54     10197189.45
      3789737.25     10196519.31      3789178.38     10195749.89
      3789038.02     10195874.86      3788862.93     10195472.17
      3788206.38     10195265.06      3788105.55     10194634.25
      3787532.26     10194201.15      3787236.66     10194315.64
      3786016.76     10192628.69      3785987.25     10192324.87
      3785270.24     10192113.06      3784834.47     10191691.19
      3784867.46      10191389.1      3784238.99     10190715.49
      3784426.49      10190258.9      3783929.16     10189709.73
       3783782.4     10188659.71      3783263.44     10188257.54

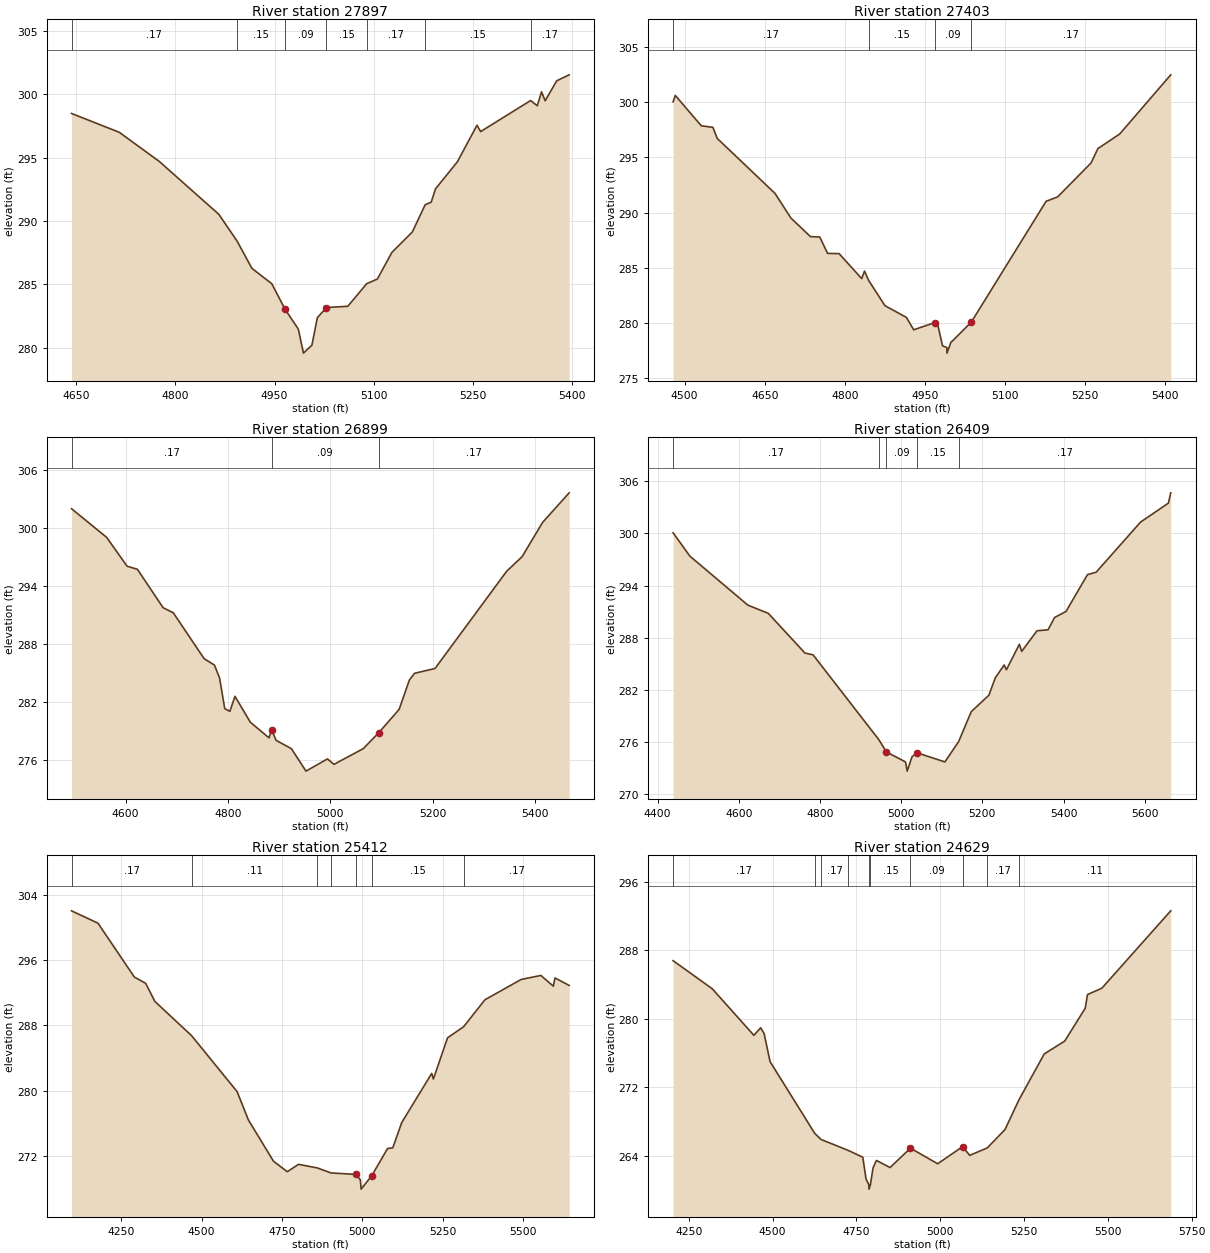
Type RM Length L Ch R = 1 ,27897   ,494,494,494
BEGIN DESCRIPTION:
SMITH BRANCH 56.0
END DESCRIPTION:
XS GIS Cut Line= 3
      3800162.47     10199008.88      3800185.65     10199365.13
      3800349.82     10199724.94
#Sta/Elev= 30
    4643  298.48  4715.3  296.99  4775.5   294.7  4865.7  290.52  4893.4   288.4
  4915.8  286.25  4945.8  285.04  4965.9  283.02  4985.9  281.46  4993.7  279.56
  5006.5  280.19  5014.7  282.36  5028.5  283.16  5060.8  283.26  5089.3  285.04
  5105.5  285.41  5127.4  287.51  5158.4  289.13  5177.7  291.27  5186.9  291.48
  5193.4  292.53  5226.4  294.66  5256.1  297.55  5261.6  297.05  5337.2   299.5
  5347.3  299.09  5353.7  300.19  5359.2  299.48  5376.7  301.06  5395.5  301.53
#Mann= 7 ,-1 , 0
    4643     .17       0  4893.4     .15       0  4965.9     .09       0
  5028.5     .15       0  5089.3     .17       0  5177.7     .15       0
  5337.2     .17       0
Bank Sta=4965.9,5028.5
XS Rating Curve= 0 ,0
Exp/Cntr=0.3,0.1

Type RM Length L Ch R = 1 ,27403   ,504,504,504
BEGIN DESCRIPTION:
SMITH BRANCH 55.0
END DESCRIPTION:
XS GIS Cut Line= 3
      3799934.04     10198921.66      3799777.48      10199319.3
      3799588.17     10199787.63
#Sta/Elev= 30
  4478.4  300.02  4482.4   300.6  4531.2  297.85    4553  297.71    4561  296.71
  4669.3  291.74  4699.1  289.51  4735.7  287.83  4753.2  287.79  4767.9  286.31
  4789.4  286.29  4831.8  284.03  4837.1  284.71  4844.9  283.86  4875.4  281.58
  4915.6  280.52  4929.2   279.4  4969.2  280.06  4974.6   279.8  4983.2  277.96
  4991.4  277.79  4991.6  277.29  4998.8  278.25  5037.1  280.09  5177.3  291.02
  5198.9  291.42  5261.6  294.49  5274.4  295.79  5315.3  297.11  5410.9  302.46
#Mann= 4 ,-1 , 0
  4478.4     .17       0  4844.9     .15       0  4969.2     .09       0
  5037.1     .17       0
Bank Sta=4969.2,5037.1
XS Rating Curve= 0 ,0
Exp/Cntr=0.3,0.1

Type RM Length L Ch R = 1 ,26899   ,490,490,490
BEGIN DESCRIPTION:
SMITH BRANCH 54.0
END DESCRIPTION:
XS GIS Cut Line= 3
      3799230.82     10198772.82      3799272.64     10199276.79
      3799292.42     10199742.97
#Sta/Elev= 30
  4494.3  301.97  4562.8  299.02  4602.9  296.04    4623  295.72  4673.2  291.76
  4693.2  291.23  4753.4   286.5  4773.5  285.84  4783.5  284.51  4793.6  281.36
  4803.6  281.06  4813.6  282.62  4843.7  279.94  4880.2  278.33  4885.3  279.18
  4893.9  278.08    4924  277.21  4952.4   274.9  4994.3  276.16  5007.1   275.6
  5064.3  277.22  5094.4  278.85  5134.4  281.27  5154.4   284.3  5164.4  284.99
  5204.5  285.49  5344.6  295.53  5374.6  297.02  5414.7  300.56  5466.6  303.61
#Mann= 3 , 0 , 0
  4494.3     .17       0  4885.3     .09       0  5094.4     .17       0
#XS Ineff= 2 , 0
       0  4813.6  282.62               0
Permanent Ineff=
       F       F
Bank Sta=4885.3,5094.4
XS Rating Curve= 0 ,0
Exp/Cntr=0.3,0.1

Type RM Length L Ch R = 1 ,26409   ,997,997,997
BEGIN DESCRIPTION:
SMITH BRANCH 53.0
END DESCRIPTION:
XS GIS Cut Line= 3
      3798779.11     10198667.56      3798827.25      10199227.2
      3799153.07     10199805.76
#Sta/Elev= 30
  4438.3  300.07  4479.5  297.39  4622.5  291.74  4672.7   290.8    4763  286.23
  4783.1  286.02  4944.9  276.27  4963.7  274.85  5010.8   273.7  5014.8  272.64
  5026.7  274.29  5038.9  274.75  5107.7   273.7  5141.6  276.04  5172.7  279.49
    5216  281.37  5231.9  283.38  5253.6  284.85  5259.3  284.31  5291.2  287.24
  5296.9  286.42  5334.5  288.79  5361.9  288.91  5377.8  290.32  5406.1  291.02
  5458.8  295.25  5480.4  295.54  5589.8  301.31  5658.2  303.48    5664  304.67
#Mann= 5 ,-1 , 0
  4438.3     .17       0  4944.9     .15       0  4963.7     .09       0
  5038.9     .15       0  5141.6     .17       0
Bank Sta=4963.7,5038.9
XS Rating Curve= 0 ,0
Exp/Cntr=0.3,0.1

Type RM Length L Ch R = 1 ,25412   ,783,783,783
BEGIN DESCRIPTION:
SMITH BRANCH 51.0
END DESCRIPTION:
XS GIS Cut Line= 3
      3798712.37     10198570.03      3798026.42     10199158.84
      3798162.66     10199786.93
#Sta/Elev= 30
    4096  302.01  4178.2   300.5  4291.3  293.91  4326.4  293.15  4354.9  290.94
  4469.1  286.75  4610.6  279.91  4645.8  276.44  4723.7   271.4  4766.5  270.12
  4801.6  271.02  4860.1  270.58  4902.4  269.97  4979.4  269.79  4993.6  269.14
  4996.1  267.99  5029.1  269.63  5078.3  272.96  5094.4  273.03  5122.3  276.13
  5215.5  282.14  5220.7  281.45  5264.7  286.49  5314.6  287.84  5380.9  291.14
  5493.4  293.62  5554.8  294.11  5593.5   292.8  5598.7  293.81  5642.7  292.89
#Mann= 7 ,-1 , 0
    4096     .17       0  4469.1     .11       0  4860.1     .15       0
  4902.4     .11       0  4979.4     .09       0  5029.1     .15       0
  5314.6     .17       0
Bank Sta=4979.4,5029.1
XS Rating Curve= 0 ,0
Exp/Cntr=0.3,0.1

Type RM Length L Ch R = 1 ,24629   ,639,639,639
BEGIN DESCRIPTION:
SMITH BRANCH 49.0
END DESCRIPTION:
XS GIS Cut Line= 3
      3797182.12     10198253.83      3797320.58     10199038.41
      3797084.89     10199684.35
#Sta/Elev= 30
  4203.3  286.76  4319.9  283.49  4444.2  278.05  4464.5  278.93  4474.7  278.26
  4492.5  274.98  4625.7  266.61  4644.3   265.9  4726.2  264.61  4769.1  263.82
  4778.6  261.31  4787.2   260.6  4787.5   260.1  4791.7   260.6  4799.6  262.58
  4809.8  263.45  4850.4  262.62  4911.3  264.88  4992.5  263.06  5066.7  265.06
    5088  264.04  5140.3  264.91  5193.4  267.06  5234.7  270.51  5310.3  275.88
  5371.4  277.38  5432.5  281.21  5439.3  282.81  5481.9  283.54  5687.6  292.58
#Mann= 10 ,-1 , 0
  4203.3     .17       0  4625.7     .11       0  4644.3     .17       0
  4726.2     .15       0  4787.2     .12       0  4791.7     .15       0
  4911.3     .09       0  5066.7     .15       0  5140.3     .17       0
  5234.7     .11       0
Bank Sta=4911.3,5066.7
XS Rating Curve= 0 ,0
Exp/Cntr=0.3,0.1

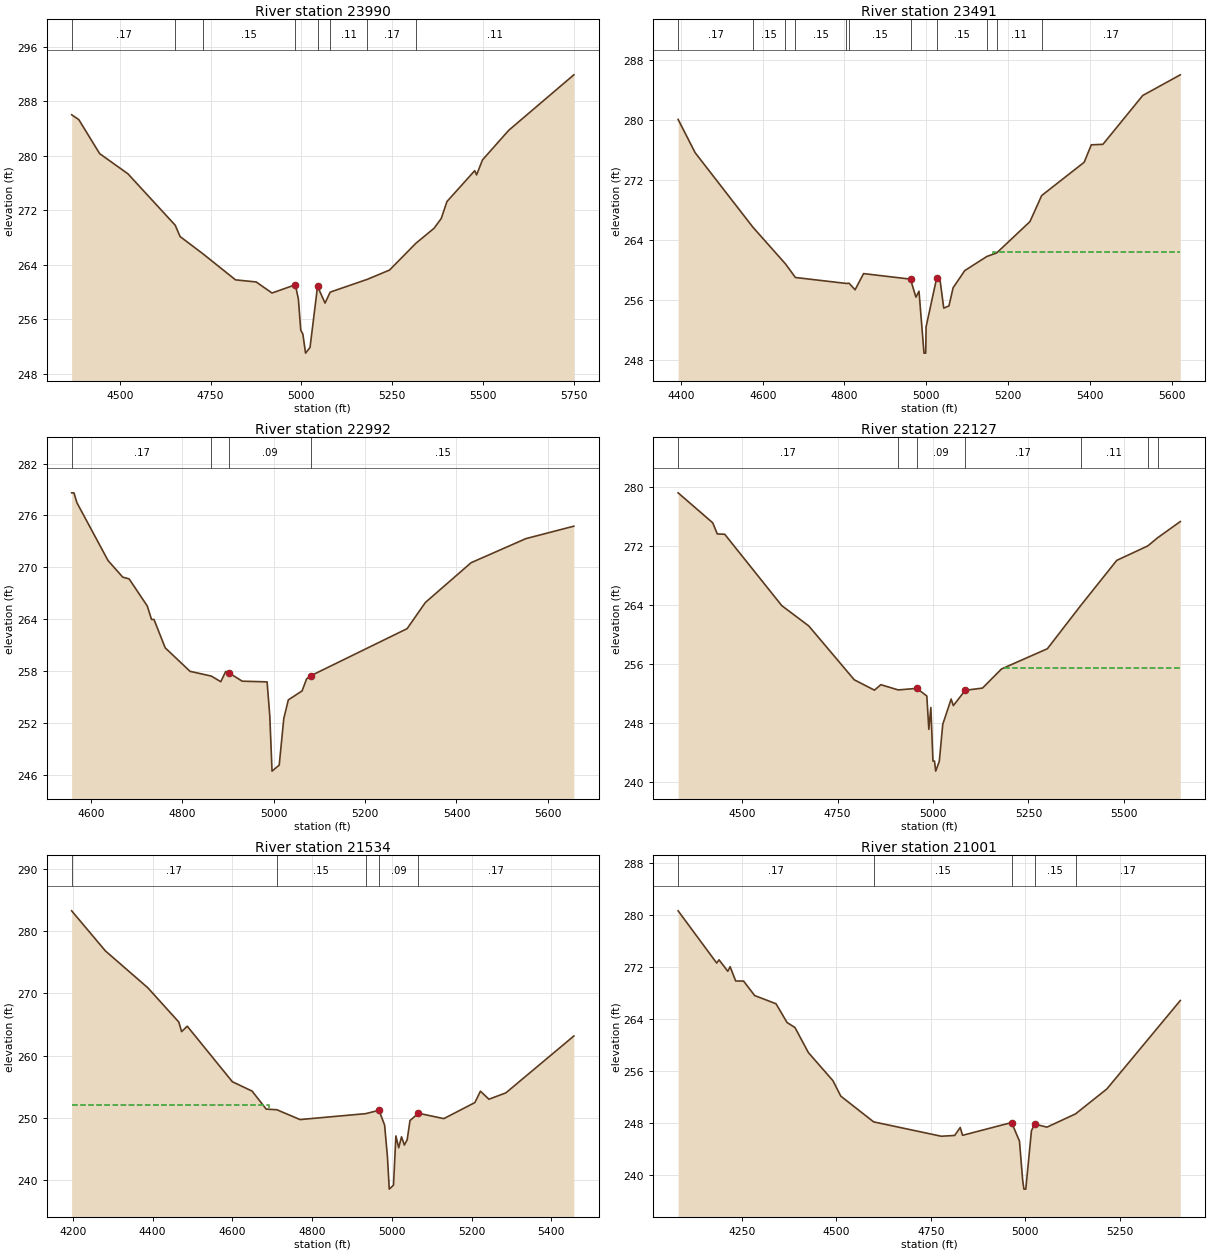
Type RM Length L Ch R = 1 ,23990   ,499,499,499
BEGIN DESCRIPTION:
SMITH BRANCH 48.0
END DESCRIPTION:
XS GIS Cut Line= 3
      3796407.81     10198444.77      3796763.33     10198967.78
      3796949.47     10199694.73
#Sta/Elev= 30
  4367.6  286.01  4387.3   285.3  4444.7  280.31  4522.6  277.35  4652.7  269.81
  4666.3  268.14  4728.7  265.63  4818.9  261.79  4875.8  261.48  4919.3  259.86
  4983.6  261.07  4991.9  258.98  4998.5   254.4  5004.3  253.83  5011.7  251.04
    5024  251.87  5044.7  260.84  5065.3  258.38  5079.5  259.99  5181.9  261.87
    5243  263.23  5315.3  267.15  5365.4  269.35  5385.3  270.79    5401  273.28
  5477.5  277.81  5482.6  277.19  5498.9  279.39  5571.1  283.73  5750.4  291.87
#Mann= 8 ,-1 , 0
  4367.6     .17       0  4652.7     .11       0  4728.7     .15       0
  4983.6     .09       0  5044.7     .15       0  5079.5     .11       0
  5181.9     .17       0  5315.3     .11       0
Bank Sta=4983.6,5044.7
XS Rating Curve= 0 ,0
Exp/Cntr=0.3,0.1

Type RM Length L Ch R = 1 ,23491   ,499,499,499
BEGIN DESCRIPTION:
SMITH BRANCH 47.0
END DESCRIPTION:
XS GIS Cut Line= 3
       3795998.1     10198701.72      3796383.38     10199170.64
      3796643.29     10199735.07
#Sta/Elev= 30
  4393.1  280.02  4434.8  275.58  4576.1  265.65  4655.6  260.77    4680  258.95
  4804.1  258.16  4811.4  258.18  4825.9  257.31  4846.7  259.47  4961.5  258.73
  4974.7  256.33  4982.3  257.12  4994.5  248.87  4998.7  248.87  4999.6  252.37
  5025.3  258.83  5033.5  258.73  5042.8  254.87  5055.5  255.16  5065.7  257.58
  5094.2  259.87  5148.5  261.76  5172.2  262.22  5253.7   266.4  5282.3  269.87
  5386.3  274.31  5403.7  276.63  5432.2   276.7  5529.6  283.21  5621.4  285.96
#Mann= 11 ,-1 , 0
  4393.1     .17       0  4576.1     .15       0  4655.6     .17       0
    4680     .15       0  4804.1     .11       0  4811.4     .15       0
  4961.5     .09       0  5025.3     .15       0  5148.5     .17       0
  5172.2     .11       0  5282.3     .17       0
#XS Ineff= 2 , 0
       0                  5163.1       0  262.31
Permanent Ineff=
       F       F
Bank Sta=4961.5,5025.3
XS Rating Curve= 0 ,0
Exp/Cntr=0.3,0.1

Type RM Length L Ch R = 1 ,22992   ,865,865,865
BEGIN DESCRIPTION:
SMITH BRANCH 46.0
END DESCRIPTION:
XS GIS Cut Line= 3
       3795748.1     10198826.75      3795908.33     10199239.22
      3795904.34      10199896.1
#Sta/Elev= 30
  4557.5  278.62  4562.5  278.62  4569.1  277.47  4637.2  270.78  4669.4  268.86
  4683.3  268.66  4723.1  265.52  4732.4  263.96  4737.7  263.97  4762.3  260.68
  4816.7  257.96  4863.3  257.41    4884  256.76  4894.7  257.94    4901  257.81
  4930.9  256.82  4985.4  256.74  4991.3  252.78  4996.2  246.41  5011.9  247.11
  5021.9  252.49  5031.9  254.66  5061.9  255.69  5071.9  257.09  5081.9  257.47
  5291.9   262.9  5331.9  265.93  5431.9  270.53  5551.9  273.32  5656.9  274.76
#Mann= 4 ,-1 , 0
  4557.5     .17       0  4863.3     .15       0    4901     .09       0
  5081.9     .15       0
Bank Sta=4901,5081.9
XS Rating Curve= 0 ,0
Exp/Cntr=0.3,0.1

Type RM Length L Ch R = 1 ,22127   ,593,593,593
BEGIN DESCRIPTION:
SMITH BRANCH 44.0
END DESCRIPTION:
XS GIS Cut Line= 3
      3795373.09     10198753.77      3795159.33     10199386.64
      3795463.37     10199958.66
#Sta/Elev= 30
    4332  279.18  4422.7  275.12  4434.7  273.61  4454.1  273.57  4603.6   263.9
  4674.3  261.15  4793.6  253.85  4846.4  252.45  4863.1  253.19  4908.7  252.48
  4957.5  252.69  4983.6  251.66  4988.9  247.14  4994.2   250.1  4999.7  242.84
  5003.8  242.84  5006.9  241.48  5016.3   242.8  5025.4  247.82  5047.4  251.25
  5053.1  250.35  5084.3  252.43  5129.6  252.73  5179.3  255.32  5299.5  258.06
  5387.3  263.94  5481.3  270.03  5562.7  271.99  5588.3  273.09  5647.8  275.29
#Mann= 7 ,-1 , 0
    4332     .17       0  4908.7     .15       0  4957.5     .09       0
  5084.3     .17       0  5387.3     .11       0  5562.7     .17       0
  5588.3     .11       0
#XS Ineff= 2 , 0
       0                  5186.2       0  255.49
Permanent Ineff=
       F       F
Bank Sta=4957.5,5084.3
XS Rating Curve= 0 ,0
Exp/Cntr=0.3,0.1

Type RM Length L Ch R = 1 ,21534   ,533,533,533
BEGIN DESCRIPTION:
SMITH BRANCH 43.0
END DESCRIPTION:
XS GIS Cut Line= 3
      3795217.86     10198661.07      3794651.32     10199230.42
      3794327.97     10199552.38
#Sta/Elev= 30
  4196.8  283.28  4281.6  276.83  4387.7  270.92  4465.5  265.41  4472.6  263.86
  4486.7  264.74  4599.9  255.81  4649.3  254.31  4684.7  251.41  4711.4  251.31
  4769.6  249.73    4934  250.68  4967.6  251.22  4981.7  248.85  4988.8  243.77
  4993.4  238.55    5004  239.19    5010   247.1  5017.1   245.2  5024.1  246.96
  5031.2  245.63  5038.3  246.48  5045.4  249.57  5066.5  250.75  5130.2  249.88
    5208  252.46  5222.1  254.29  5243.3     253  5285.8  254.02  5456.3  263.16
#Mann= 5 ,-1 , 0
  4196.8     .17       0  4711.4     .15       0    4934     .17       0
  4967.6     .09       0  5066.5     .17       0
#XS Ineff= 2 , 0
       0  4691.8  252.09               0
Permanent Ineff=
       F       F
Bank Sta=4967.6,5066.5
XS Rating Curve= 0 ,0
Exp/Cntr=0.3,0.1

Type RM Length L Ch R = 1 ,21001   ,866,866,866
BEGIN DESCRIPTION:
SMITH BRANCH 42.0
END DESCRIPTION:
XS GIS Cut Line= 3
      3794713.38     10198344.04      3794171.74     10199085.34
       3794046.7     10199476.02
#Sta/Elev= 30
  4081.9  280.59    4184  272.55  4190.2  273.05  4213.3  271.29  4219.5  271.99
  4234.2  269.79  4255.1  269.78  4284.4  267.55  4340.8  266.29  4370.1   263.4
    4391  262.63  4426.5  258.77  4491.4  254.45  4512.2  252.07  4599.1  248.11
  4777.9   245.9  4813.4  246.02  4828.1  247.25  4834.3  246.04    4964  248.01
  4984.8  245.15  4993.3  239.11  4996.6  237.76  5001.5  237.76  5016.5  246.77
  5025.5  247.76  5057.6   247.3  5133.1  249.34    5216  253.18  5410.2  266.79
#Mann= 5 ,-1 , 0
  4081.9     .17       0  4599.1     .15       0    4964     .09       0
  5025.5     .15       0  5133.1     .17       0
Bank Sta=4964,5025.5
XS Rating Curve= 0 ,0
Exp/Cntr=0.3,0.1

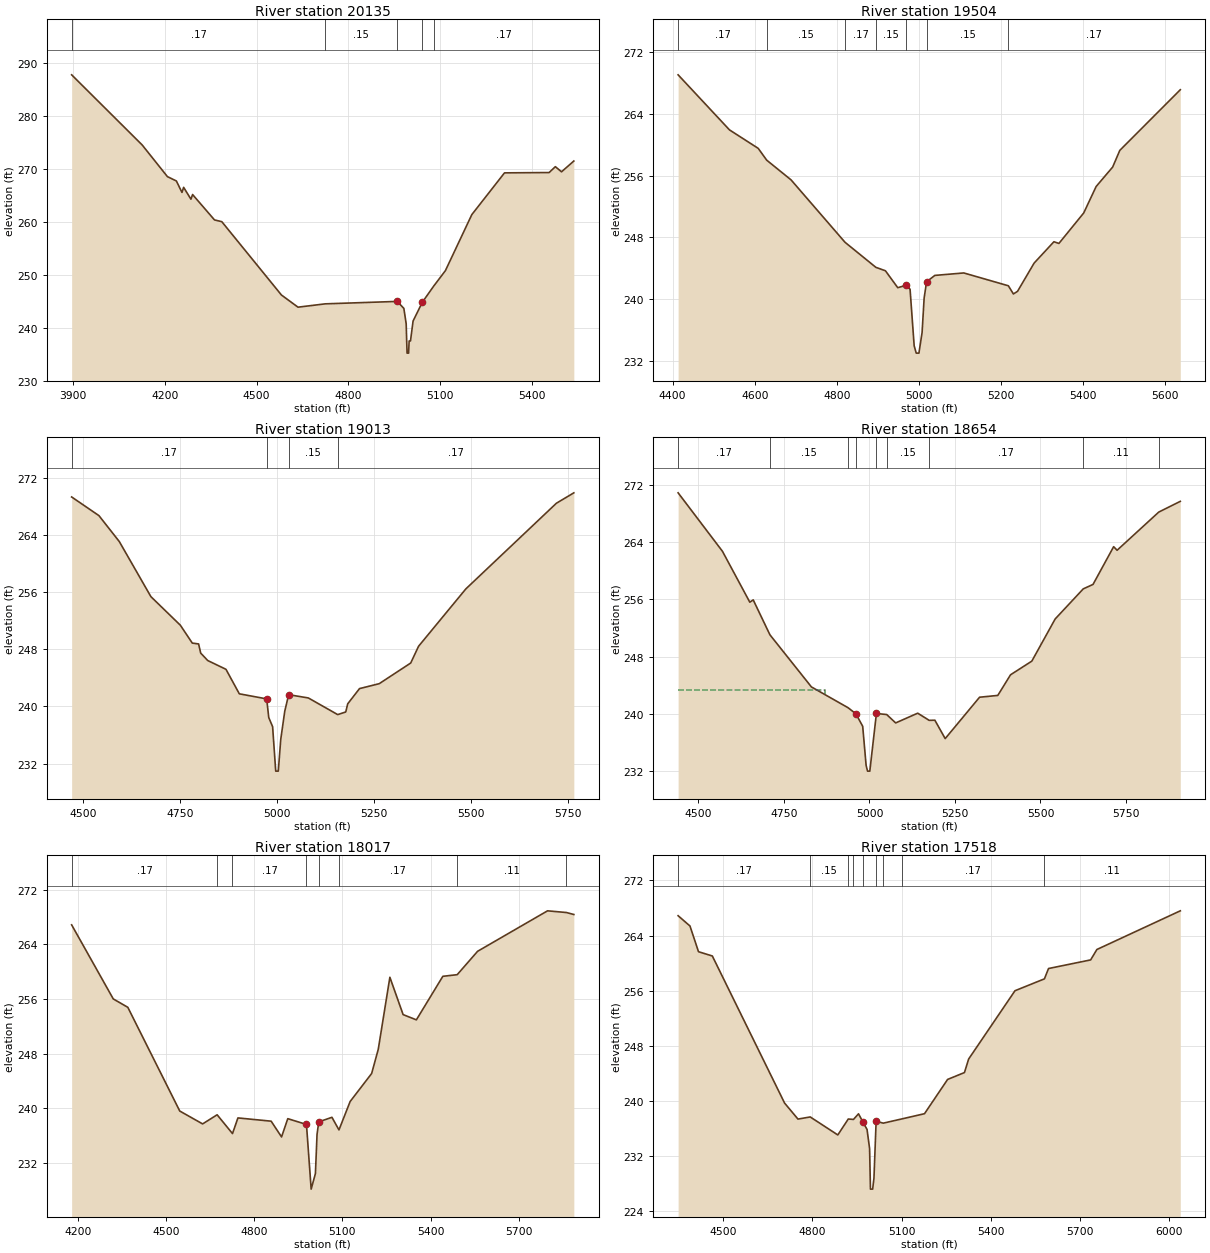
Type RM Length L Ch R = 1 ,20135   ,631,631,631
BEGIN DESCRIPTION:
SMITH BRANCH 40.0
END DESCRIPTION:
XS GIS Cut Line= 3
      3794682.16     10198225.99      3793660.93     10198649.33
      3793577.94     10199180.89
#Sta/Elev= 30
  3894.5  287.82  4125.4  274.55  4207.9  268.57  4237.2  267.75  4255.6  265.58
    4261  266.54  4284.9   264.3  4290.3  265.18    4362  260.38  4385.9  260.05
  4581.1  246.18  4635.3  243.88  4724.6  244.51    4960  244.97  4981.7  243.65
  4989.3  240.75  4992.2  235.19  4997.2  235.19    4999  237.49  5003.4  237.49
  5011.9  241.26  5042.2  244.82  5079.7  247.89  5117.7  250.79  5204.2  261.39
  5311.1  269.28  5457.2  269.34  5477.5  270.45  5497.7  269.48    5538  271.52
#Mann= 5 ,-1 , 0
  3894.5     .17       0  4724.6     .15       0    4960     .09       0
  5042.2     .15       0  5079.7     .17       0
Bank Sta=4960,5042.2
XS Rating Curve= 0 ,0
Exp/Cntr=0.3,0.1

Type RM Length L Ch R = 1 ,19504   ,491,491,491
BEGIN DESCRIPTION:
SMITH BRANCH 39.0
END DESCRIPTION:
XS GIS Cut Line= 3
      3793178.03     10197815.87      3793174.35     10198402.56
       3793094.7     10199034.56
#Sta/Elev= 30
  4413.3  269.05  4538.5  261.92  4608.5  259.53  4629.2     258  4688.5  255.45
    4820  247.37  4895.1  244.13  4918.5  243.68  4948.5  241.49  4968.5   241.8
  4978.5  241.29  4988.5  233.97  4993.5  233.02  5000.1  233.02  5007.8  235.69
  5012.8  240.15  5018.7  242.25  5038.8  243.08  5109.4   243.4    5218  241.74
  5230.3  240.68  5240.4  241.02  5280.7  244.67    5329  247.44  5341.2  247.22
  5401.7  251.17  5431.9  254.59  5472.2  257.11  5489.6  259.27    5637  267.12
#Mann= 7 ,-1 , 0
  4413.3     .17       0  4629.2     .15       0    4820     .17       0
  4895.1     .15       0  4968.5     .09       0  5018.7     .15       0
    5218     .17       0
Bank Sta=4968.5,5018.7
XS Rating Curve= 0 ,0
Exp/Cntr=0.3,0.1

Type RM Length L Ch R = 1 ,19013   ,359,359,359
BEGIN DESCRIPTION:
SMITH BRANCH 38.0
END DESCRIPTION:
XS GIS Cut Line= 3
      3793042.62     10197815.82      3792832.54     10198301.86
      3792704.08     10199055.39
#Sta/Elev= 30
  4470.5  269.31  4540.8   266.7  4593.3  263.07  4674.7  255.36  4750.6  251.36
  4781.3  248.86  4797.6  248.74    4803  247.46  4821.1  246.42  4868.1  245.19
  4902.5  241.76    4973  241.05  4978.4  238.43  4988.3  237.16  4996.3  230.94
  5002.9  230.94  5009.3   235.4  5019.5   239.3  5029.6  241.64  5080.4  241.18
    5156  238.85  5176.7  239.22  5181.8  240.36  5212.2  242.49    5263  243.18
  5344.1  246.07  5364.4  248.42  5486.1  256.44  5719.4  268.43  5764.4  269.89
#Mann= 4 ,-1 , 0
  4470.5     .17       0    4973     .09       0  5029.6     .15       0
    5156     .17       0
Bank Sta=4973,5029.6
XS Rating Curve= 0 ,0
Exp/Cntr=0.3,0.1

Type RM Length L Ch R = 1 ,18654   ,637,637,637
BEGIN DESCRIPTION:
SMITH BRANCH 37.0
END DESCRIPTION:
XS GIS Cut Line= 3
      3792553.03     10197581.48      3792564.98     10198140.85
      3792657.19     10199044.96
#Sta/Elev= 30
  4440.5  270.86  4570.1   262.7  4650.1  255.59  4660.1  255.91  4708.9  251.04
  4830.2  243.76  4937.2  240.86  4960.2  240.01  4980.2  238.26  4990.2  232.79
  4994.3     232    5001     232  5020.3  240.05  5050.4   239.9  5076.6  238.73
    5141  240.09  5174.6  239.09  5191.2  239.11  5221.4  236.54  5321.9  242.32
  5375.2  242.57  5412.4  245.45  5474.7  247.36    5543  253.25  5625.1  257.45
  5653.6  258.07  5713.9  263.34    5724  262.84  5845.8  268.17  5908.8  269.67
#Mann= 9 ,-1 , 0
  4440.5     .17       0  4708.9     .15       0  4937.2     .17       0
  4960.2     .09       0  5020.3     .17       0  5050.4     .15       0
  5174.6     .17       0  5625.1     .11       0  5845.8     .17       0
#XS Ineff= 2 , 0
       0  4870.2  243.33               0
Permanent Ineff=
       F       F
Bank Sta=4960.2,5020.3
XS Rating Curve= 0 ,0
Exp/Cntr=0.3,0.1

Type RM Length L Ch R = 1 ,18017   ,499,499,499
BEGIN DESCRIPTION:
SMITH BRANCH 36.0
END DESCRIPTION:
XS GIS Cut Line= 3
      3791657.53     10197700.96      3792236.98     10198283.43
      3792625.96     10199081.48
#Sta/Elev= 30
  4178.4  266.88  4320.1  256.01  4369.6  254.78  4546.4  239.56  4624.2  237.67
  4673.6  239.01  4725.9  236.25  4744.4  238.55  4857.5  238.07  4892.9  235.76
  4914.1  238.44  4977.7  237.59  4993.7   228.1  5008.2  230.39  5013.7  236.16
  5019.6  237.97  5064.4  238.64  5088.3  236.79  5126.4  240.96  5199.6  245.07
  5222.1  248.62  5261.6  259.19  5306.7  253.71  5351.8  252.94  5441.9  259.33
  5490.8  259.57  5560.2     263  5798.3  268.94  5862.7  268.69  5887.8   268.4
#Mann= 8 ,-1 , 0
  4178.4     .17       0  4673.6     .15       0  4725.9     .17       0
  4977.7     .09       0  5019.6     .15       0  5088.3     .17       0
  5490.8     .11       0  5862.7     .17       0
Bank Sta=4977.7,5019.6
XS Rating Curve= 0 ,0
Exp/Cntr=0.3,0.1

Type RM Length L Ch R = 1 ,17518   ,496,496,496
BEGIN DESCRIPTION:
SMITH BRANCH 35.0
END DESCRIPTION:
XS GIS Cut Line= 3
       3791605.1     10197742.89      3791870.75     10198338.09
      3792578.62      10199096.6
#Sta/Elev= 30
  4348.2  266.89  4388.1   265.4  4416.8  261.67  4463.3  261.05  4706.4  239.71
  4751.4  237.39  4792.6   237.7  4885.4  235.09  4920.6   237.4  4938.1  237.34
    4955  238.16  4970.4  236.92  4983.7  235.89  4992.3  233.13  4995.2  227.23
  5002.6  227.23    5007  228.83  5014.3  237.08  5038.3   236.8  5100.4  237.41
    5177  238.17  5254.7  243.14  5311.4  244.14  5325.5   246.1  5481.4  256.01
  5580.4  257.73  5594.2  259.23  5735.9  260.48  5756.9  261.99  6037.5   267.6
#Mann= 9 ,-1 , 0
  4348.2     .17       0  4792.6     .15       0  4920.6     .11       0
  4938.1     .15       0  4970.4     .09       0  5014.3     .15       0
  5038.3     .11       0  5100.4     .17       0  5580.4     .11       0
Bank Sta=4970.4,5014.3
XS Rating Curve= 0 ,0
Exp/Cntr=0.3,0.1

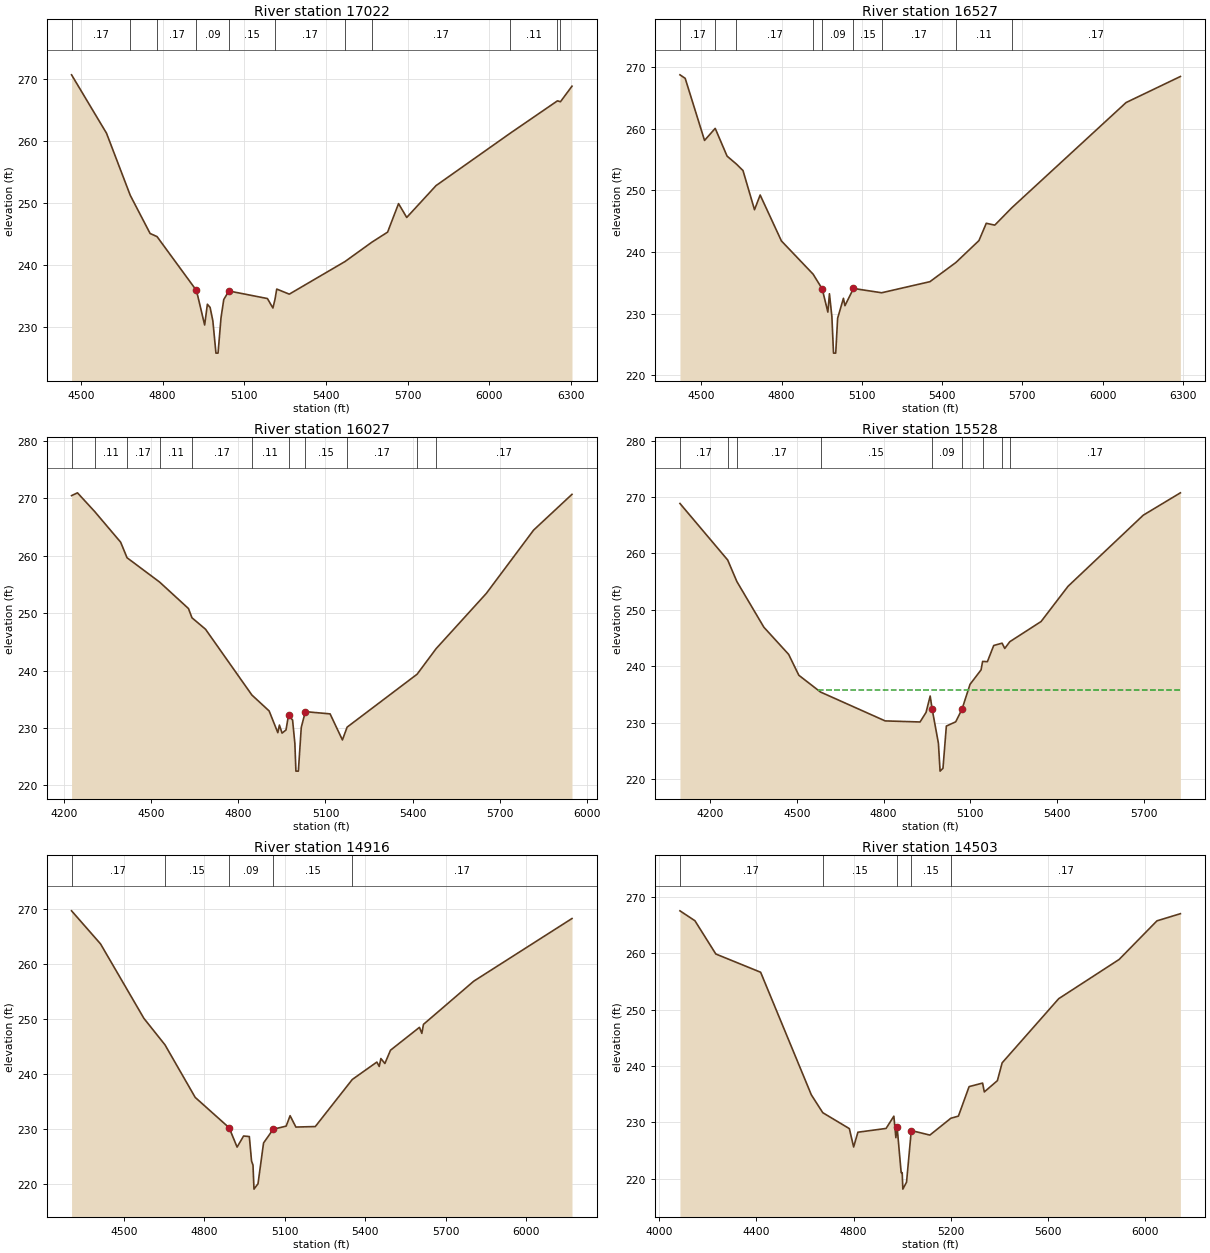
Type RM Length L Ch R = 1 ,17022   ,495,495,495
BEGIN DESCRIPTION:
SMITH BRANCH 34.0
END DESCRIPTION:
XS GIS Cut Line= 3
      3791526.99     10197742.89       3791494.3     10198276.59
      3791605.11     10199576.18
#Sta/Elev= 30
  4465.3  270.65  4593.7  261.23  4681.1  251.19    4754  245.04  4779.4  244.54
  4924.3  235.84  4954.4  230.27  4964.4  233.62  4974.4  233.11  4984.5  230.95
  4995.9  225.73  5003.6  225.73  5014.5  231.43  5024.6  234.38  5043.6  235.76
  5185.1  234.54  5205.2  233.01  5212.8   234.4  5219.3  236.07  5265.4  235.25
  5470.4  240.52  5569.3  243.65  5626.7  245.26  5666.9  249.86    5697  247.63
  5804.7  252.77  6077.5  261.23  6250.8  266.45    6262  266.31  6304.3  268.82
#Mann= 11 ,-1 , 0
  4465.3     .17       0  4681.1     .11       0  4779.4     .17       0
  4924.3     .09       0  5043.6     .15       0  5212.8     .17       0
  5470.4     .11       0  5569.3     .17       0  6077.5     .11       0
  6250.8     .17       0    6262     .11       0
Bank Sta=4924.3,5043.6
XS Rating Curve= 0 ,0
Exp/Cntr=0.3,0.1

Type RM Length L Ch R = 1 ,16527   ,500,500,500
BEGIN DESCRIPTION:
SMITH BRANCH 33.0
END DESCRIPTION:
XS GIS Cut Line= 3
      3791386.38     10197643.93       3791068.2     10198129.11
      3790433.22     10199253.38
#Sta/Elev= 30
  4419.8  268.76  4439.4  268.19  4511.7  258.11  4551.6  260.07    4596  255.56
  4630.2   254.3  4655.5  253.22  4698.6  246.86  4719.7  249.25  4799.1   241.8
  4917.9  236.39  4951.8     234  4972.9  230.24  4978.8  233.22    4988  229.48
    4994  223.58  5002.3  223.58  5009.4  229.24  5031.1  232.48  5036.8  231.28
  5068.7  234.08  5174.1  233.38  5354.6  235.18  5451.6  238.29  5537.9  241.85
  5565.3  244.66  5597.1  244.36  5660.1  247.15  6088.1  264.26  6291.2  268.49
#Mann= 9 ,-1 , 0
  4419.8     .17       0  4551.6     .11       0  4630.2     .17       0
  4917.9     .15       0  4951.8     .09       0  5068.7     .15       0
  5174.1     .17       0  5451.6     .11       0  5660.1     .17       0
#XS Ineff= 2 , 0
       0  4900.5  237.09               0
Permanent Ineff=
       F       F
Bank Sta=4951.8,5068.7
XS Rating Curve= 0 ,0
Exp/Cntr=0.3,0.1

Type RM Length L Ch R = 1 ,16027   ,499,499,499
BEGIN DESCRIPTION:
SMITH BRANCH 32.0
END DESCRIPTION:
XS GIS Cut Line= 3
      3791349.93     10197586.66      3790653.38     10197922.98
      3790001.92     10198611.68
#Sta/Elev= 30
  4226.5  270.48  4246.8  270.97  4305.7  267.73  4395.4  262.37  4417.4  259.66
  4529.1  255.44  4628.6  250.82  4640.7  249.21  4687.4  247.21  4846.9  235.75
  4906.2  232.98    4936   229.2  4941.6  230.52  4950.6  229.12  4964.2  229.67
  4972.8  232.24  4986.8   231.4  4994.7  227.32  4998.3   222.5  5006.7   222.5
  5016.7  230.12  5030.8  232.86  5115.8  232.47  5158.3  227.93  5174.4  230.16
  5415.2  239.38  5480.6  243.83  5653.4  253.46    5816  264.48    5948  270.71
#Mann= 11 ,-1 , 0
  4226.5     .17       0  4305.7     .11       0  4417.4     .17       0
  4529.1     .11       0  4640.7     .17       0  4846.9     .11       0
  4972.8     .09       0  5030.8     .15       0  5174.4     .17       0
  5415.2     .15       0  5480.6     .17       0
Bank Sta=4972.8,5030.8
XS Rating Curve= 0 ,0
Exp/Cntr=0.3,0.1

Type RM Length L Ch R = 1 ,15528   ,612,612,612
BEGIN DESCRIPTION:
SMITH BRANCH 31.0
END DESCRIPTION:
XS GIS Cut Line= 3
      3790867.86     10197111.06      3790278.51     10197797.06
      3789886.37     10198524.16
#Sta/Elev= 30
  4095.6  268.86  4260.7  258.83  4292.3  255.02  4385.9   246.9  4471.5  242.09
  4506.6  238.39  4581.7  235.41  4805.1  230.29  4925.8   230.1  4946.6   231.8
  4960.9   234.7  4967.5  232.43  4989.4  226.31  4995.1  221.38  5005.1  221.88
  5016.8  229.37  5049.2  230.13  5071.1  232.39  5098.7  236.78  5136.8  239.34
  5142.2  240.84  5158.7   240.8  5180.6  243.67  5209.6  244.08  5218.7  243.14
  5236.2  244.34  5344.4  247.92  5437.6  254.17  5697.6  266.78  5826.1  270.75
#Mann= 9 ,-1 , 0
  4095.6     .17       0  4260.7     .11       0  4292.3     .17       0
  4581.7     .15       0  4967.5     .09       0  5071.1     .15       0
  5142.2     .17       0  5209.6     .15       0  5236.2     .17       0
#XS Ineff= 2 ,-1
  4577.9  4563.6  235.69  4960.9  4592.2   234.7
Permanent Ineff=
       F       F
Bank Sta=4967.5,5071.1
XS Rating Curve= 0 ,0
Exp/Cntr=0.3,0.1

Type RM Length L Ch R = 1 ,14916   ,413,413,413
BEGIN DESCRIPTION:
SMITH BRANCH 30.0
END DESCRIPTION:
XS GIS Cut Line= 3
      3790823.87     10197076.25      3790177.87     10197333.95
      3789522.32     10198304.62
#Sta/Elev= 30
  4304.5  269.66  4412.6  263.64  4574.3  250.09  4653.1  245.26  4765.7   235.7
  4892.4  230.17    4922  226.65  4946.2  228.67  4967.7  228.57  4975.9  224.11
  4981.3  223.38    4985     219    5000  219.98  5020.7   227.4  5056.7   229.9
  5105.1  230.47  5119.7  232.37  5141.3   230.3  5213.7  230.39  5351.7  238.96
  5443.4  242.13  5452.3  241.33  5458.4  242.77  5473.3  241.87  5494.3  244.29
  5602.3  248.45  5611.2  247.35  5617.2  248.99    5805  256.86  6171.3  268.26
#Mann= 5 ,-1 , 0
  4304.5     .17       0  4653.1     .15       0  4892.4     .09       0
  5056.7     .15       0  5351.7     .17       0
Bank Sta=4892.4,5056.7
XS Rating Curve= 0 ,0
Exp/Cntr=0.3,0.1

Type RM Length L Ch R = 1 ,14503   ,967,967,967
BEGIN DESCRIPTION:
SMITH BRANCH 29.0
END DESCRIPTION:
XS GIS Cut Line= 3
       3790089.5     10196300.19      3789857.04     10197184.24
      3789459.72     10198257.35
#Sta/Elev= 30
  4085.9  267.56  4147.5   265.8  4233.4  259.89  4417.7  256.65  4626.4  234.86
  4673.3   231.7  4782.6  228.87  4800.3  225.61  4817.8  228.23  4933.7   228.9
  4965.7  231.08    4974  227.26  4979.2   229.1  4995.8  221.05    5000  221.05
  5002.7  218.12  5017.9  219.36  5037.4  228.53  5113.9  227.72  5200.1  230.71
  5231.2  231.09  5275.2  236.33  5330.7  236.96  5337.8  235.39  5391.5  237.39
  5411.2  240.56  5643.7  251.95  5892.3  258.92  6047.9  265.78  6144.3  267.05
#Mann= 5 ,-1 , 0
  4085.9     .17       0  4673.3     .15       0  4979.2     .09       0
  5037.4     .15       0  5200.1     .17       0
Bank Sta=4979.2,5037.4
XS Rating Curve= 0 ,0
Exp/Cntr=0.3,0.1

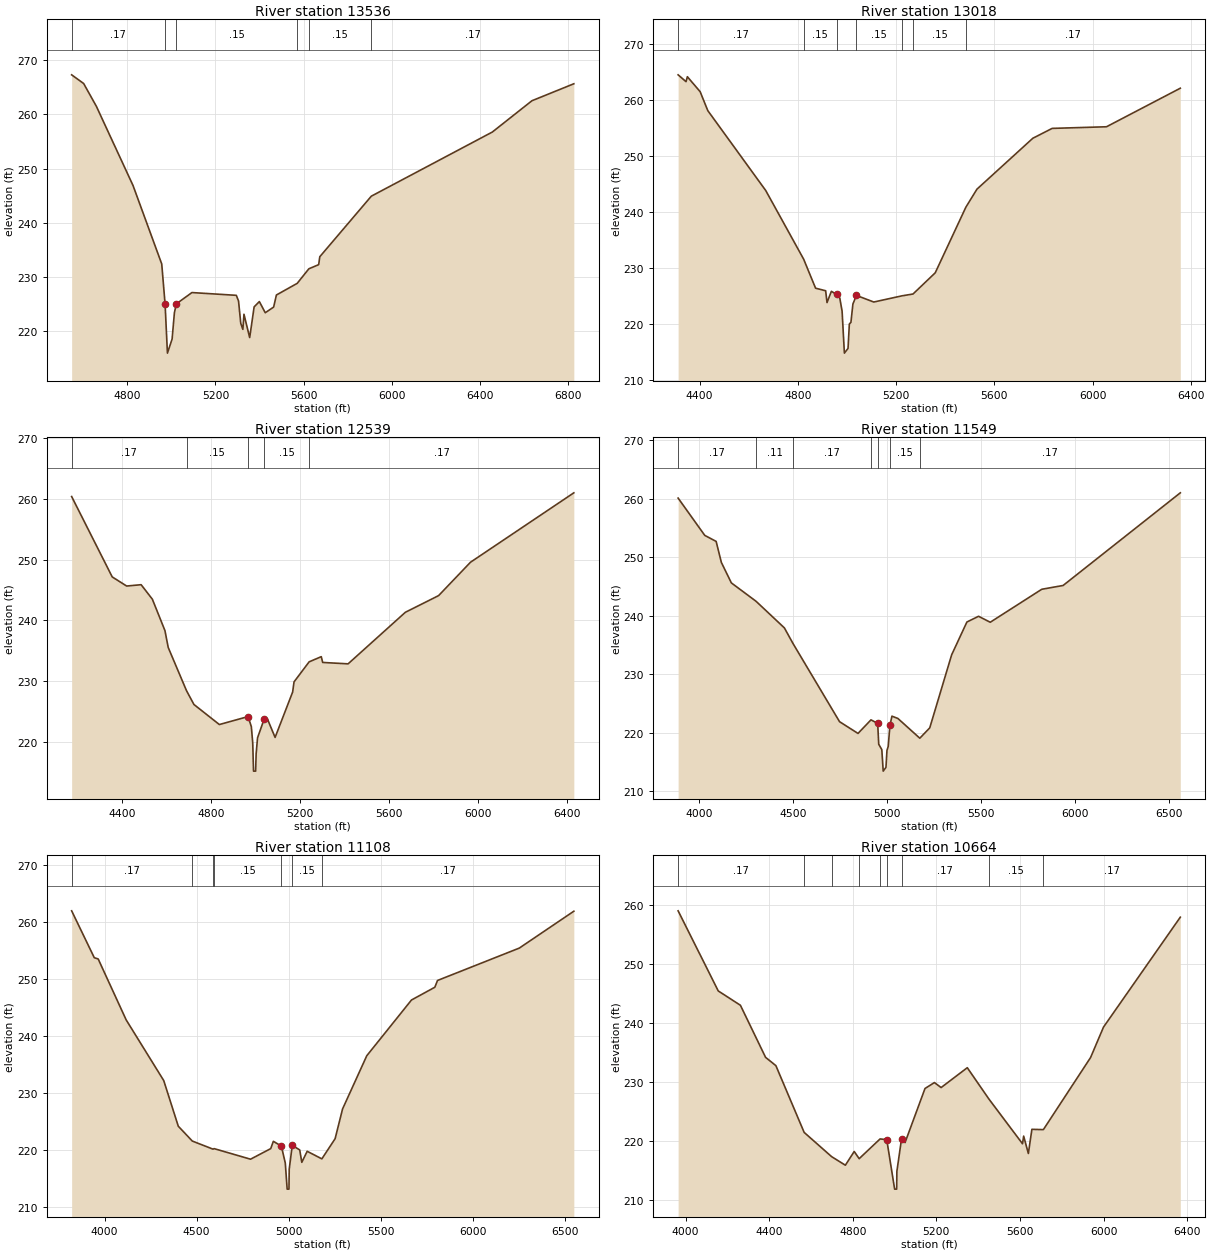
Type RM Length L Ch R = 1 ,13536   ,518,518,518
BEGIN DESCRIPTION:
SMITH BRANCH 27.0
END DESCRIPTION:
XS GIS Cut Line= 4
      3790089.45     10196227.32      3789707.74      10196470.7
      3789605.12     10196612.71      3789365.69     10198247.06
#Sta/Elev= 30
  4547.3  267.31  4601.7  265.71  4659.2  261.53  4825.9   246.9  4956.3  232.42
  4971.5  225.01  4982.1  215.98  5003.3  218.58  5013.7   223.4  5022.2  225.06
  5093.3  227.15  5294.8  226.64  5304.9  225.59    5315  221.47  5324.5  220.36
  5329.5  223.15  5355.5  218.85  5375.7  224.51  5399.4  225.49  5426.2  223.43
  5464.2  224.47  5476.8   226.7  5571.3  228.85    5624  231.53  5668.7   232.3
  5673.8  233.76  5907.7  244.93  6457.1  256.76  6636.8  262.53    6827  265.66
#Mann= 6 ,-1 , 0
  4547.3     .17       0  4971.5     .09       0  5022.2     .15       0
  5571.3     .17       0    5624     .15       0  5907.7     .17       0
Bank Sta=4971.5,5022.2
XS Rating Curve= 0 ,0
Exp/Cntr=0.3,0.1

Type RM Length L Ch R = 1 ,13018   ,479,479,479
BEGIN DESCRIPTION:
SMITH BRANCH 26.0
END DESCRIPTION:
XS GIS Cut Line= 3
      3790058.25     10195951.25      3789429.96     10196229.38
      3788365.52     10197071.06
#Sta/Elev= 30
  4312.9  264.54  4345.1  263.32  4350.6   264.2  4402.6  261.53  4433.6  258.16
  4669.7  243.88    4824  231.63  4872.4  226.46  4913.5     226    4919  223.89
  4936.7   225.9  4958.6  225.34    4971   224.7  4980.4  222.35  4989.7  214.87
  5004.5  215.71  5009.9  220.07  5016.3  220.36  5024.4  223.64  5038.8  225.17
  5109.3  223.99  5224.6   225.1    5269  225.42  5359.4   229.2  5484.1  240.91
  5529.2  244.13  5756.8  253.22  5835.4  254.98  6056.6  255.27    6357  262.15
#Mann= 7 ,-1 , 0
  4312.9     .17       0    4824     .15       0  4958.6     .09       0
  5038.8     .15       0  5224.6     .17       0    5269     .15       0
  5484.1     .17       0
Bank Sta=4958.6,5038.8
XS Rating Curve= 0 ,0
Exp/Cntr=0.3,0.1

Type RM Length L Ch R = 1 ,12539   ,990,990,990
BEGIN DESCRIPTION:
SMITH BRANCH 25.0
END DESCRIPTION:
XS GIS Cut Line= 3
      3789865.51     10195383.57      3789196.49      10195865.8
      3788318.68     10196992.89
#Sta/Elev= 30
  4175.3  260.35  4357.3  247.15  4422.1  245.65  4487.1  245.87  4537.4  243.49
  4593.9  238.33  4608.6  235.56  4690.7  228.46  4723.9   226.2  4838.1   222.9
  4966.9  224.21  4981.6  222.55  4987.8  219.88  4991.4  215.25  5000.8  215.25
  5003.1  218.12  5009.5  220.73  5038.4  223.73  5052.9  223.89  5088.2  220.79
  5166.9  228.24  5173.2  229.91  5240.9   233.2  5295.4  234.05  5301.7   233.1
  5415.7  232.87  5672.7  241.34  5821.9  244.08  5964.9  249.56  6428.6  260.96
#Mann= 5 ,-1 , 0
  4175.3     .17       0  4690.7     .15       0  4966.9     .09       0
  5038.4     .15       0  5240.9     .17       0
Bank Sta=4966.9,5038.4
XS Rating Curve= 0 ,0
Exp/Cntr=0.3,0.1

Type RM Length L Ch R = 1 ,11549   ,441,441,441
BEGIN DESCRIPTION:
SMITH BRANCH 23.0
END DESCRIPTION:
XS GIS Cut Line= 3
      3789698.86     10194930.42      3788713.47     10195447.02
      3788198.86     10196920.01
#Sta/Elev= 30
  3887.4  260.14  4029.2  253.76  4089.8  252.73  4117.5  249.14  4170.8  245.63
  4302.1  242.49  4453.1  237.93  4499.3  235.24  4746.6  221.89  4844.9  219.88
  4913.9   222.2  4949.6  221.59  4955.2  218.03  4971.6  217.11    4979  213.43
  4993.7  214.08    4999  216.98  5005.7  217.65  5014.9  221.29  5025.5  222.83
  5057.2  222.44  5173.8  219.06  5226.7  220.83  5343.3  233.33  5424.5  238.94
  5486.6  239.92  5548.7   238.9  5822.9  244.54  5936.5  245.19  6560.3  261.04
#Mann= 7 ,-1 , 0
  3887.4     .17       0  4302.1     .11       0  4499.3     .17       0
  4913.9     .15       0  4949.6     .09       0  5014.9     .15       0
  5173.8     .17       0
Bank Sta=4949.6,5014.9
XS Rating Curve= 0 ,0
Exp/Cntr=0.3,0.1

Type RM Length L Ch R = 1 ,11108   ,444,444,444
BEGIN DESCRIPTION:
SMITH BRANCH 22.0
END DESCRIPTION:
XS GIS Cut Line= 3
      3788928.05     10194341.85       3788303.1     10195341.59
      3788068.65     10196873.15
#Sta/Elev= 30
    3821  262.01    3944  253.77  3965.2  253.55  4117.3  242.84  4321.3  232.18
  4400.3  224.16  4476.4  221.55  4589.6  220.12  4594.7  220.22    4793  218.36
  4902.6  220.22  4916.8   221.5  4960.4  220.67  4981.7  217.68  4991.9   213.1
  5001.6   213.1  5003.1  216.62  5019.7   220.8  5060.2  219.98  5071.5  217.81
  5100.6  219.75  5180.4  218.42  5252.4  221.96  5292.9  227.19  5424.4  236.54
  5667.4  246.34  5794.2  248.58  5808.8  249.77  6253.1  255.46  6549.4  261.94
#Mann= 7 ,-1 , 0
    3821     .17       0  4476.4     .11       0  4589.6     .17       0
  4594.7     .15       0  4960.4     .09       0  5019.7     .15       0
  5180.4     .17       0
Bank Sta=4960.4,5019.7
XS Rating Curve= 0 ,0
Exp/Cntr=0.3,0.1

Type RM Length L Ch R = 1 ,10664   ,666,666,666
BEGIN DESCRIPTION:
SMITH BRANCH 21.0
END DESCRIPTION:
XS GIS Cut Line= 3
      3788776.98     10194258.56       3788057.9     10195003.81
      3786830.52     10195606.79
#Sta/Elev= 30
  3964.4  259.09  4156.5  245.49  4262.5  243.06  4382.9  234.22  4432.3  232.81
  4567.5  221.48  4699.1  217.36  4764.7  215.91  4807.1  218.24  4830.8  217.02
  4930.9  220.37  4962.8  220.25  5000.5  211.85  5010.2  211.85  5011.2  214.86
  5033.5  220.38  5050.3  219.75  5145.8  228.93  5190.8  229.94  5222.9  229.09
  5348.2  232.46  5451.1  227.17  5612.4  219.55  5617.9  220.85  5640.4   217.9
  5657.3     222  5712.2  221.95  5938.2  234.19  6000.1  239.36  6367.5  258.01
#Mann= 9 ,-1 , 0
  3964.4     .17       0  4567.5     .15       0  4699.1     .11       0
  4830.8     .15       0  4930.9     .17       0  4962.8     .09       0
  5033.5     .17       0  5451.1     .15       0  5712.2     .17       0
#XS Ineff= 1 ,-1
  5348.2    6000  232.46
Permanent Ineff=
       F
Bank Sta=4962.8,5033.5
XS Rating Curve= 0 ,0
Exp/Cntr=0.3,0.1