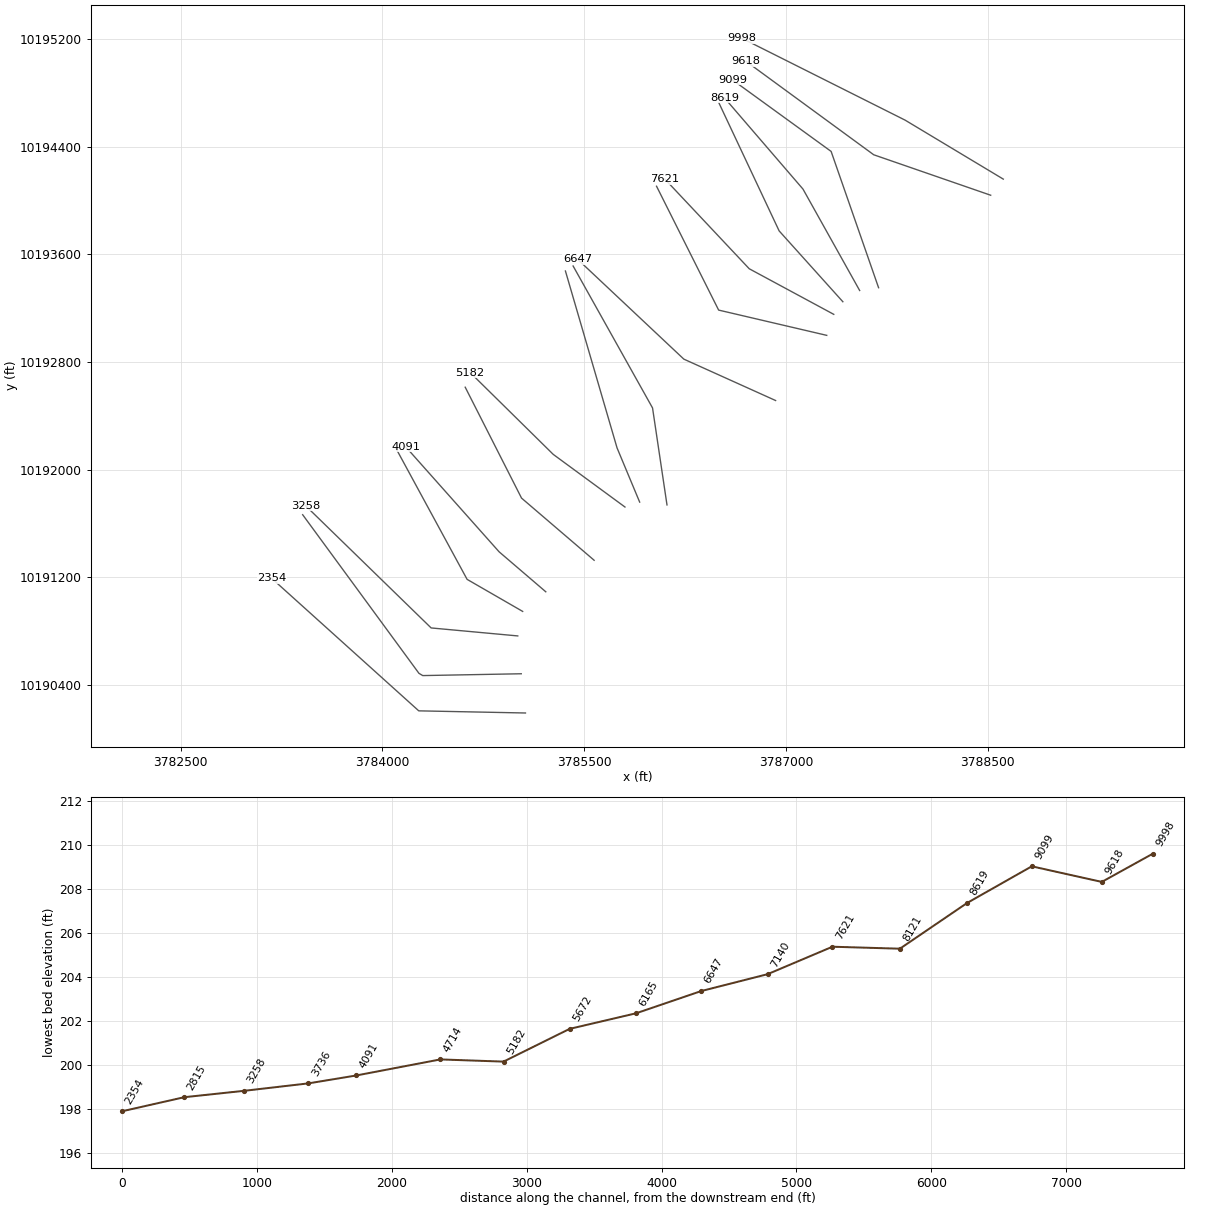
HEC-RAS study SMITH BRANCH.prj: SMITH BRANCH Base Level Engineering

--- SMITH BRANCH.g01 (geometry) --- (continued)

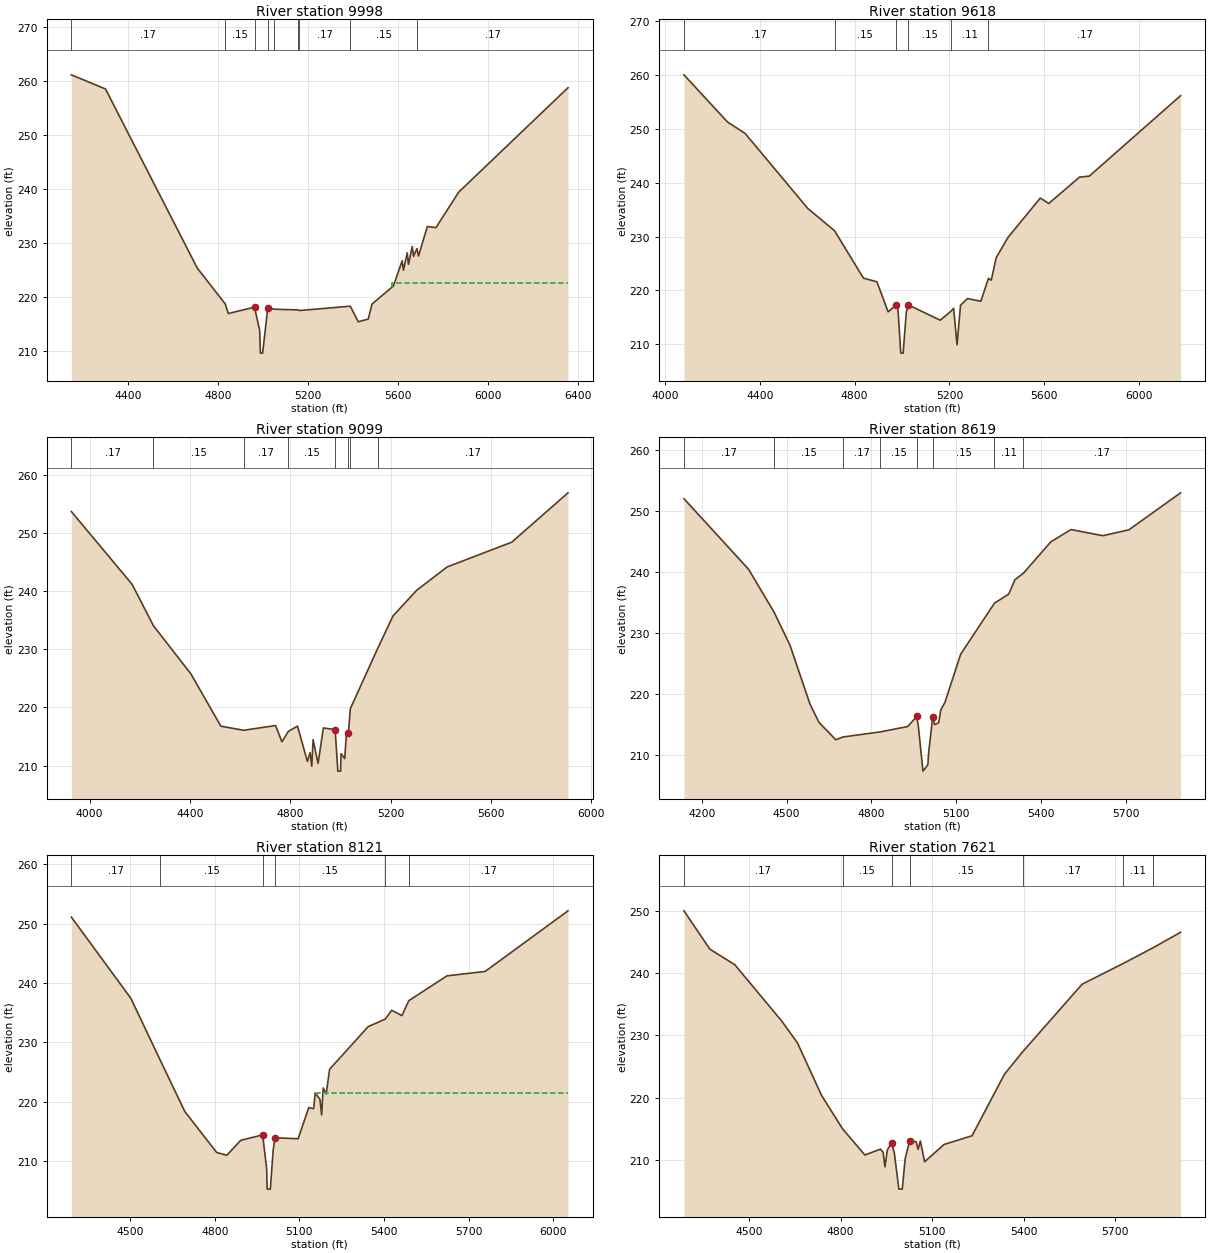
Type RM Length L Ch R = 1 ,9998    ,380,380,380
BEGIN DESCRIPTION:
SMITH BRANCH 20.0
END DESCRIPTION:
XS GIS Cut Line= 3
      3788615.54     10194159.58      3787885.79     10194597.96
      3786673.22     10195206.27
#Sta/Elev= 30
  4148.7  261.16  4300.4  258.54  4708.4  225.37  4832.9  218.73  4846.4  216.95
    4963  218.14  4985.9  213.79    4989  209.62    4999  209.62  5021.9  218.04
    5051  217.75  5158.4  217.62  5162.8  217.51  5388.8  218.31    5424  215.43
  5468.6  215.92  5485.4  218.72  5580.3  222.05  5619.4  226.73    5625  224.98
  5641.8  228.19  5647.4  226.07  5664.1  229.35  5669.7  227.55  5684.8  228.98
    5692  227.61  5731.1  233.06  5769.7  232.87  5870.7  239.44  6356.6  258.77
#Mann= 9 ,-1 , 0
  4148.7     .17       0  4832.9     .15       0    4963     .09       0
  5021.9     .15       0    5051     .11       0  5158.4     .15       0
  5162.8     .17       0  5388.8     .15       0  5684.8     .17       0
#XS Ineff= 2 , 0
       0                  5574.7       0  222.63
Permanent Ineff=
       F       F
Bank Sta=4963,5021.9
XS Rating Curve= 0 ,0
Exp/Cntr=0.3,0.1

Type RM Length L Ch R = 1 ,9618    ,519,519,519
BEGIN DESCRIPTION:
SMITH BRANCH 19.0
END DESCRIPTION:
XS GIS Cut Line= 3
      3788521.81     10194039.79      3787652.45     10194340.51
       3786704.1     10195034.57
#Sta/Elev= 30
  4080.1  260.04  4264.2  251.26  4338.2  249.15  4602.8   235.2  4715.3  231.08
  4837.2  222.27  4894.2  221.58  4941.4     216  4973.1  217.19  4982.4  216.87
  4994.8  208.33  5004.8  208.33  5018.1   215.9  5025.3  217.32  5161.2  214.45
  5206.6  216.11  5217.6  216.66  5232.2  209.88  5246.9  217.23  5276.2  218.46
  5332.6  217.97  5364.7  222.23  5376.6  221.89  5397.5  226.08  5447.6  229.86
  5583.5  237.15    5619  236.13  5748.7  241.03  5790.4  241.23  6175.2  256.17
#Mann= 6 ,-1 , 0
  4080.1     .17       0  4715.3     .15       0  4973.1     .09       0
  5025.3     .15       0  5206.6     .11       0  5364.7     .17       0
Bank Sta=4973.1,5025.3
XS Rating Curve= 0 ,0
Exp/Cntr=0.3,0.1

Type RM Length L Ch R = 1 ,9099    ,480,480,480
BEGIN DESCRIPTION:
SMITH BRANCH 18.0
END DESCRIPTION:
XS GIS Cut Line= 3
      3787688.46     10193352.27      3787335.65     10194365.51
      3786601.37     10194898.11
#Sta/Elev= 30
  3927.1  253.72  4169.4  241.18  4254.2  234.07    4404  225.76    4523  216.78
    4614  216.07  4741.2  216.89  4766.4  214.09  4792.4  215.88  4828.6  216.79
  4868.2  210.71  4878.8  212.21  4885.5  209.88  4890.8  214.47  4910.6  210.37
  4931.8  216.47  4978.8  216.18  4989.5  209.04  5000.5  209.04  5002.2  212.04
  5016.9   211.2  5023.1  215.12  5031.6  215.67  5039.4   219.8  5147.6  230.09
  5209.4  235.75  5303.7  240.16  5425.1  244.18  5682.6  248.44  5907.1  256.94
#Mann= 8 ,-1 , 0
  3927.1     .17       0  4254.2     .15       0    4614     .17       0
  4792.4     .15       0  4978.8     .09       0  5031.6     .15       0
  5039.4     .11       0  5147.6     .17       0
Bank Sta=4978.8,5031.6
XS Rating Curve= 0 ,0
Exp/Cntr=0.3,0.1

Type RM Length L Ch R = 1 ,8619    ,498,498,498
BEGIN DESCRIPTION:
SMITH BRANCH 17.0
END DESCRIPTION:
XS GIS Cut Line= 3
       3787547.8      10193331.5      3787126.56     10194085.28
      3786542.72     10194763.63
#Sta/Elev= 30
  4136.5  252.04  4365.1  240.48  4455.9  233.41    4512  228.01  4582.8  218.36
  4614.8  215.35  4674.2  212.51  4699.9  212.97  4831.2   213.8  4928.9  214.68
  4960.8  216.34  4966.6   214.7  4982.8  207.37    5000  208.39  5003.4  210.61
  5017.6   216.3  5024.2     215  5038.5   215.3  5046.1  217.44  5060.4  218.61
  5116.4  226.55    5236  234.91  5286.5   236.4  5308.4  238.74  5338.7  239.83
  5435.7  244.97    5507  246.98    5620  245.97  5712.2  246.94    5895     253
#Mann= 8 ,-1 , 0
  4136.5     .17       0  4455.9     .15       0  4699.9     .17       0
  4831.2     .15       0  4960.8     .09       0  5017.6     .15       0
    5236     .11       0  5338.7     .17       0
Bank Sta=4960.8,5017.6
XS Rating Curve= 0 ,0
Exp/Cntr=0.3,0.1

Type RM Length L Ch R = 1 ,8121    ,500,500,500
BEGIN DESCRIPTION:
SMITH BRANCH 16.0
END DESCRIPTION:
XS GIS Cut Line= 3
      3787422.85      10193248.1      3786949.21     10193774.61
      3786501.24     10194726.69
#Sta/Elev= 30
  4291.8  251.08  4502.7  237.41  4606.5  227.03    4694  218.35  4806.9  211.46
  4842.8  210.99  4892.1   213.5  4969.9  214.43  4984.1  208.65    4986  205.29
    4997  205.29  5007.1  211.87  5013.8  213.94  5095.5  213.77  5133.3  219.02
  5150.6  218.83  5156.1  221.48  5172.9  220.41  5178.9  217.78  5184.4  222.31
    5195  221.32  5207.2  225.47    5344  232.65  5404.4  233.91  5427.1   235.4
  5463.5   234.5  5487.7  237.01  5623.1  241.19  5758.6  241.94  6052.2  252.14
#Mann= 6 ,-1 , 0
  4291.8     .17       0  4606.5     .15       0  4969.9     .09       0
  5013.8     .15       0  5404.4     .11       0  5487.7     .17       0
#XS Ineff= 2 , 0
       0                  5161.9       0  221.52
Permanent Ineff=
       F       F
Bank Sta=4969.9,5013.8
XS Rating Curve= 0 ,0
Exp/Cntr=0.3,0.1

Type RM Length L Ch R = 1 ,7621    ,481,481,481
BEGIN DESCRIPTION:
SMITH BRANCH 15.0
END DESCRIPTION:
XS GIS Cut Line= 3
      3787355.16     10193154.36      3786726.83     10193493.27
       3786099.9      10194159.6
#Sta/Elev= 30
  4286.1  249.97  4371.1  243.83    4453  241.33  4606.3  232.34    4658  228.84
  4737.6  220.38  4806.1  215.06  4879.5  210.85  4930.7  211.79  4939.5  211.26
  4945.2  208.95  4953.4  211.68  4967.1  212.82  4976.1  211.18    4991  205.38
  5002.1  205.38  5011.7  210.27  5025.9  213.03  5047.3  212.99  5054.2  211.76
  5061.5  213.09  5075.6  209.77  5139.2  212.54    5231  213.93  5337.4   223.8
  5396.9  227.38  5591.9  238.21  5724.9  241.49  5825.7  244.08  5914.9  246.53
#Mann= 7 ,-1 , 0
  4286.1     .17       0  4806.1     .15       0  4967.1     .09       0
  5025.9     .15       0  5396.9     .17       0  5724.9     .11       0
  5825.7     .17       0
Bank Sta=4967.1,5025.9
XS Rating Curve= 0 ,0
Exp/Cntr=0.3,0.1

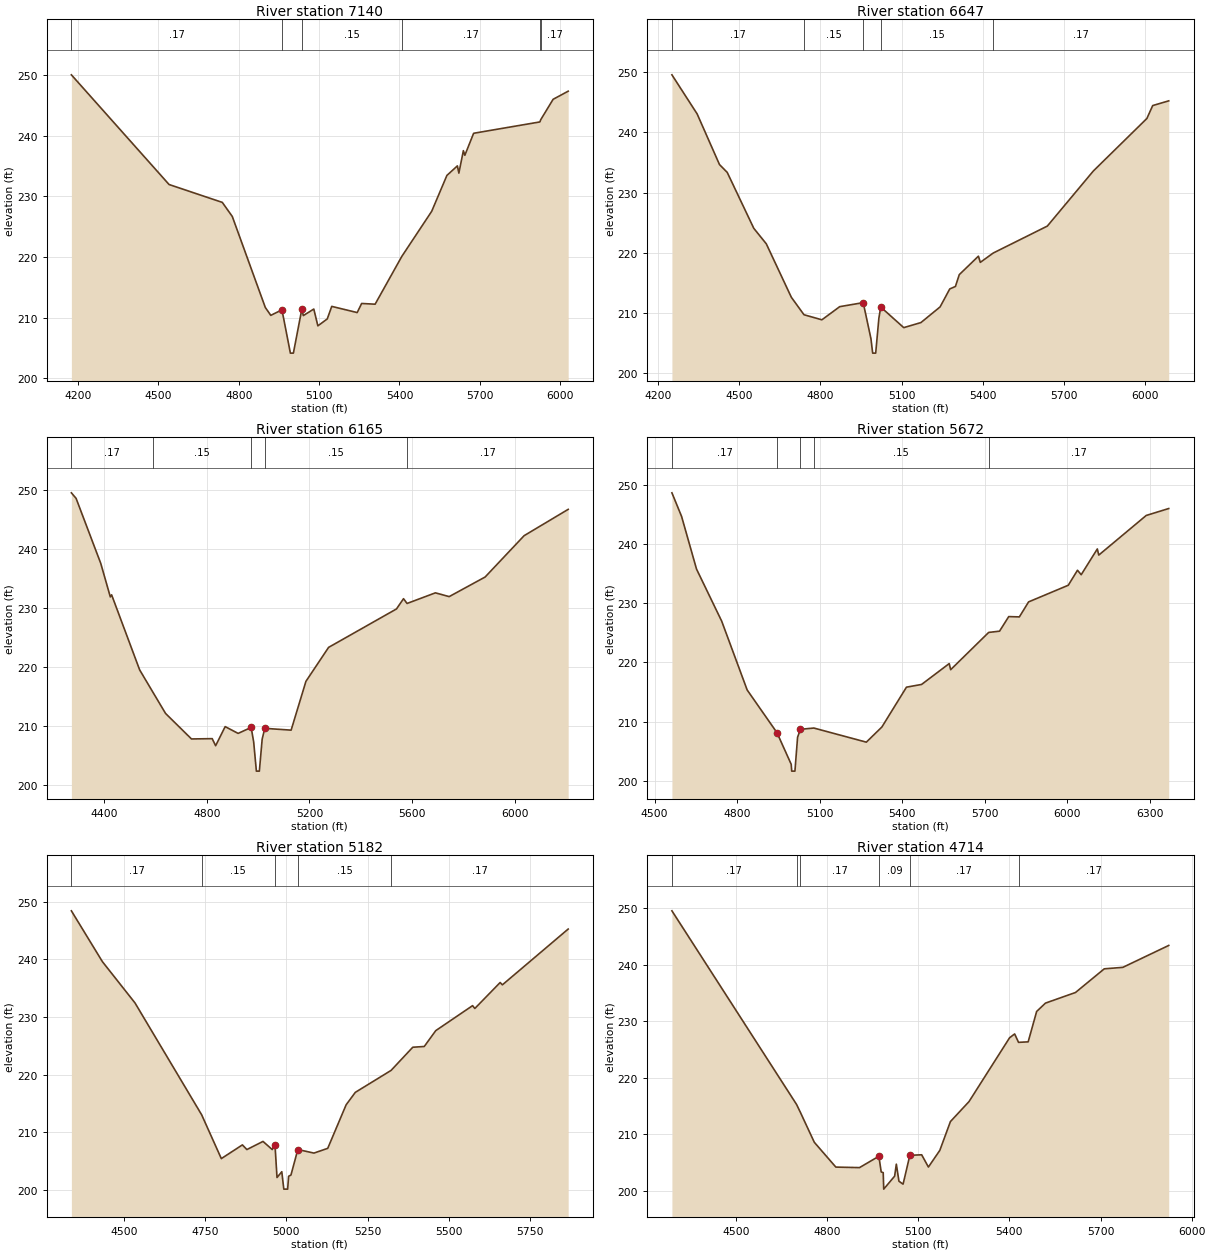
Type RM Length L Ch R = 1 ,7140    ,493,493,493
BEGIN DESCRIPTION:
SMITH BRANCH 14.0
END DESCRIPTION:
XS GIS Cut Line= 3
      3787303.04     10192998.13       3786499.4     10193185.98
      3786037.79     10194106.75
#Sta/Elev= 30
  4174.7  250.03  4539.5  231.94  4738.3  228.99  4775.6  226.67  4898.9  211.66
  4919.4  210.36  4961.1  211.27  4992.6  204.13  5003.8  204.13  5035.3  211.37
  5040.9  210.32    5080   211.4  5095.2  208.63  5130.3  209.77    5147  211.84
    5242  210.82  5258.7  212.32    5309   212.2  5408.8  220.09  5520.3  227.52
  5577.1  233.44  5616.2  235.01  5621.8  233.82  5638.6  237.52  5644.1  236.76
  5676.9  240.39  5924.3  242.26  5927.8  242.65  5973.7  245.99    6030  247.33
#Mann= 6 ,-1 , 0
  4174.7     .17       0  4961.1     .09       0  5035.3     .15       0
  5408.8     .17       0  5924.3     .11       0  5927.8     .17       0
Bank Sta=4961.1,5035.3
XS Rating Curve= 0 ,0
Exp/Cntr=0.3,0.1

Type RM Length L Ch R = 1 ,6647    ,482,482,482
BEGIN DESCRIPTION:
SMITH BRANCH 13.0
END DESCRIPTION:
XS GIS Cut Line= 3
      3786922.85     10192513.74      3786240.72      10192821.4
       3785448.9     10193565.81
#Sta/Elev= 30
  4251.7  249.54  4344.9  243.05  4427.4  234.65    4456  233.35  4554.1  224.07
  4600.3   221.5  4692.8  212.63  4739.5  209.73  4805.7  208.89  4871.5  211.07
  4958.3  211.74  4986.9  205.75  4993.2  203.36  5004.4  203.36  5016.1  209.13
    5023  211.01    5108  207.59  5171.5  208.43  5242.3  211.03  5277.9  214.01
  5298.9  214.42  5313.1  216.38  5383.9  219.45  5390.8  218.42  5438.6  219.97
  5638.4  224.44  5808.3  233.58  6006.2   242.3  6027.6  244.44  6086.8  245.22
#Mann= 5 ,-1 , 0
  4251.7     .17       0  4739.5     .15       0  4958.3     .09       0
    5023     .15       0  5438.6     .17       0
Bank Sta=4958.3,5023
XS Rating Curve= 0 ,0
Exp/Cntr=0.3,0.1

Type RM Length L Ch R = 1 ,6165    ,493,493,493
BEGIN DESCRIPTION:
SMITH BRANCH 12.0
END DESCRIPTION:
XS GIS Cut Line= 3
      3786115.53     10191737.71      3786008.08     10192458.55
      3785417.61     10193513.77
#Sta/Elev= 30
  4271.2  249.49  4289.6  248.55  4385.8  237.54  4423.1  231.86  4428.2  232.21
  4537.5   219.5  4590.2  215.65  4638.6  212.12  4739.7   207.8  4820.6  207.85
  4833.9  206.65  4871.1  209.89  4921.7  208.74  4972.5  209.75  4982.3  207.31
  4992.9  202.35  5004.5  202.35  5015.4  207.75  5025.6   209.6  5128.4  209.29
  5186.2  217.56  5274.6  223.31  5539.4  229.82  5566.9  231.56  5580.7  230.75
  5691.3  232.55    5745  231.91  5885.2  235.23  6037.3  242.23  6209.2  246.69
#Mann= 5 ,-1 , 0
  4271.2     .17       0  4590.2     .15       0  4972.5     .09       0
  5025.6     .15       0  5580.7     .17       0
Bank Sta=4972.5,5025.6
XS Rating Curve= 0 ,0
Exp/Cntr=0.3,0.1

Type RM Length L Ch R = 1 ,5672    ,490,490,490
BEGIN DESCRIPTION:
SMITH BRANCH 11.0
END DESCRIPTION:
XS GIS Cut Line= 3
       3785912.4     10191758.56      3785744.19     10192161.67
      3785360.51     10193476.64
#Sta/Elev= 30
  4563.2  248.61  4598.4  244.62  4652.6  235.75  4744.3  226.94  4836.8  215.34
  4945.2  208.13    4997  202.79  4998.8  201.64  5010.5  201.64  5020.2  207.37
  5030.6   208.7  5079.5  208.91  5270.2  206.53  5326.8  209.09  5416.1  215.81
  5471.1  216.27  5571.6  219.79  5576.8  218.76  5715.1  225.05  5754.6  225.26
    5788  227.72  5826.7  227.67  5860.2   230.2  6004.5  233.01    6038  235.54
  6051.5  234.79  6110.2  239.14  6115.4   238.1    6288  244.79  6369.8  245.96
#Mann= 5 ,-1 , 0
  4563.2     .17       0  4945.2     .09       0  5030.6     .17       0
  5079.5     .15       0  5715.1     .17       0
Bank Sta=4945.2,5030.6
XS Rating Curve= 0 ,0
Exp/Cntr=0.3,0.1

Type RM Length L Ch R = 1 ,5182    ,468,468,468
BEGIN DESCRIPTION:
SMITH BRANCH 10.0
END DESCRIPTION:
XS GIS Cut Line= 3
      3785803.07     10191722.06      3785270.24     10192113.06
      3784652.44     10192721.64
#Sta/Elev= 30
  4339.1   248.4  4434.5  239.59  4534.8  232.43  4739.8  213.04  4800.3  205.44
  4865.1  207.82  4878.9  207.01  4928.5  208.42    4957  207.01  4965.4  207.82
  4971.6  202.16  4986.3  203.17  4992.5  200.15  5004.3  200.15  5007.3  202.38
  5014.5  202.59  5035.6  207.02  5085.2   206.4  5127.6  207.22  5184.2  214.77
  5212.5  216.93  5322.4  220.73  5389.2  224.75  5424.5  224.88  5459.9  227.63
  5573.1  231.96  5580.1  231.47  5657.9  235.97  5664.9  235.57  5867.2  245.24
#Mann= 5 ,-1 , 0
  4339.1     .17       0  4739.8     .15       0  4965.4     .09       0
  5035.6     .15       0  5322.4     .17       0
Bank Sta=4965.4,5035.6
XS Rating Curve= 0 ,0
Exp/Cntr=0.3,0.1

Type RM Length L Ch R = 1 ,4714    ,623,623,623
BEGIN DESCRIPTION:
SMITH BRANCH 9.0
END DESCRIPTION:
XS GIS Cut Line= 3
      3785573.89     10191326.23      3785034.12     10191788.41
      3784615.53     10192612.71
#Sta/Elev= 30
  4289.4  249.53  4699.8  215.23  4711.1  213.97  4758.1  208.54  4828.9  204.15
  4906.8  204.06  4970.5  206.07  4978.2  203.29  4984.8  203.17  4986.5  200.25
  5022.4  202.55    5028  204.67  5036.6  201.65  5050.2  201.13  5072.5  206.24
  5111.4  206.33  5133.6  204.16  5171.2  207.12    5206  212.21  5267.2  215.75
  5400.7  227.05  5417.4  227.73  5430.2  226.24  5461.9  226.33  5489.8  231.71
  5518.9  233.19  5617.7  235.07  5712.4  239.26  5773.5  239.52  5924.5   243.4
#Mann= 6 ,-1 , 0
  4289.4     .17       0  4699.8     .15       0  4711.1     .17       0
  4970.5     .09       0  5072.5     .17       0  5430.2     .17       0
Bank Sta=4970.5,5072.5
XS Rating Curve= 0 ,0
Exp/Cntr=0.3,0.1

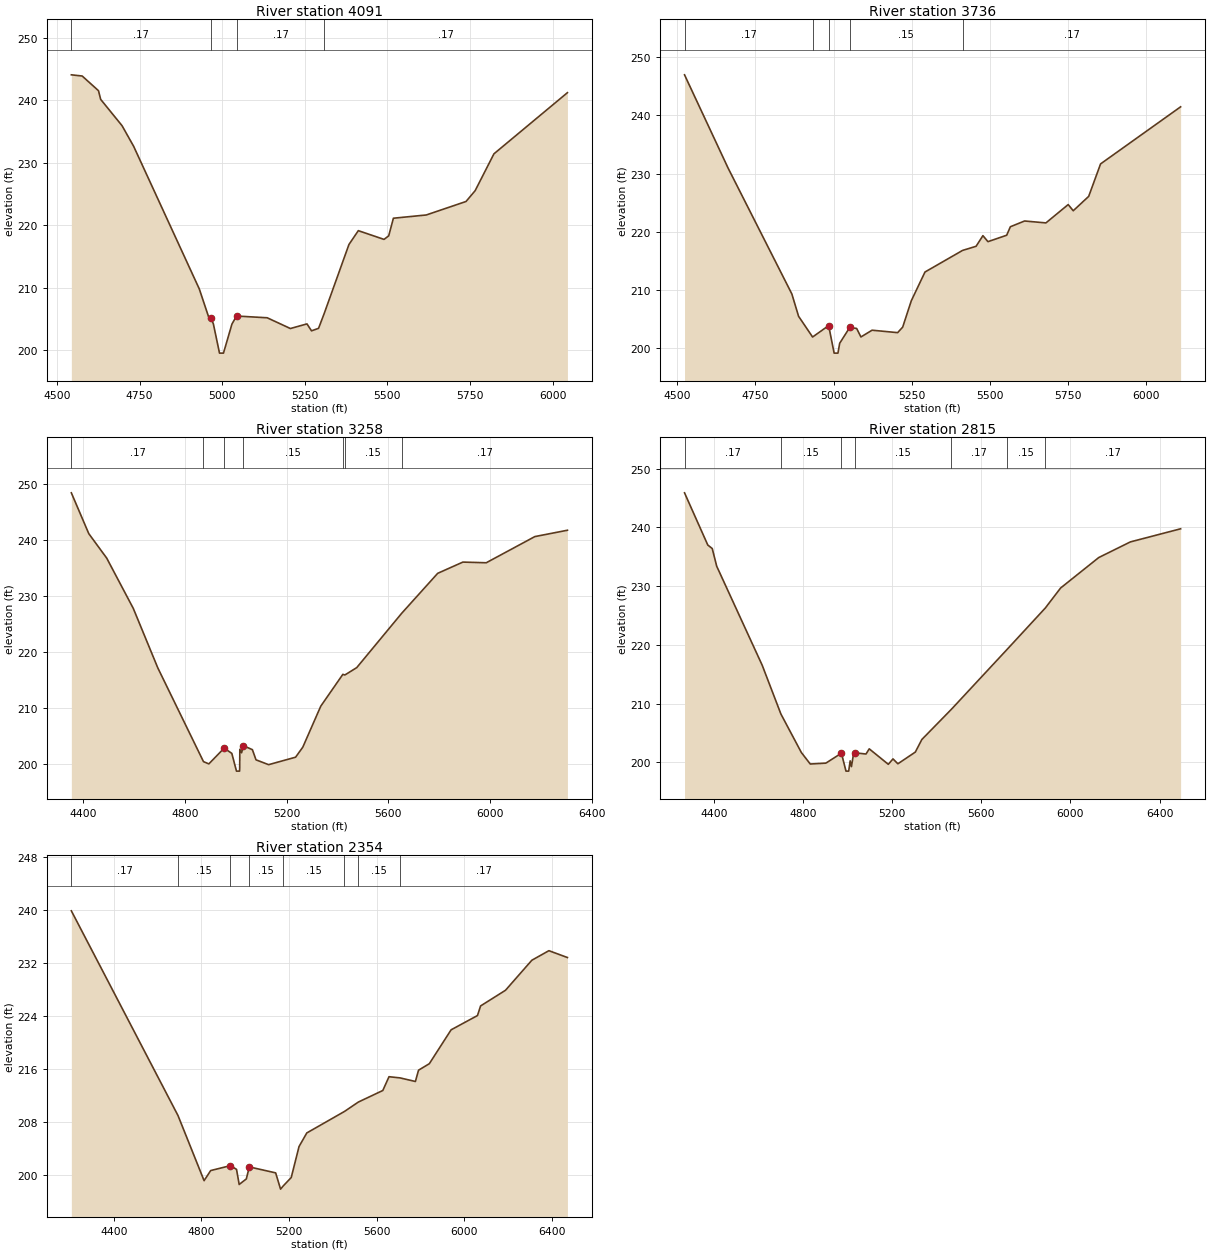
Type RM Length L Ch R = 1 ,4091    ,355,355,355
BEGIN DESCRIPTION:
SMITH BRANCH 8.0
END DESCRIPTION:
XS GIS Cut Line= 3
      3785214.48     10191091.89      3784867.46      10191389.1
      3784172.85     10192169.97
#Sta/Elev= 30
  4543.1  244.08  4575.9  243.89  4625.3  241.54  4631.9  240.15  4696.7  235.93
  4731.8  232.63  4930.5   209.8    4959  205.28  4965.6  205.14  4973.1  204.21
  4991.7  199.52  5003.7  199.52  5029.4  204.18  5043.2  205.46  5136.1  205.18
  5206.3  203.46  5256.5   204.2  5270.3  203.09  5291.6  203.49  5308.8  205.88
  5383.6  216.91    5412  219.13  5489.8  217.73    5504   218.3  5518.2  221.12
  5617.7  221.64  5738.1   223.8  5765.7  225.53  5822.6  231.43  6045.1  241.22
#Mann= 4 ,-1 , 0
  4543.1     .17       0  4965.6     .09       0  5043.2     .17       0
  5308.8     .17       0
Bank Sta=4965.6,5043.2
XS Rating Curve= 0 ,0
Exp/Cntr=0.3,0.1

Type RM Length L Ch R = 1 ,3736    ,478,478,478
BEGIN DESCRIPTION:
SMITH BRANCH 7.0
END DESCRIPTION:
XS GIS Cut Line= 3
      3785042.64     10190946.03      3784629.61     10191184.24
      3784099.91     10192159.59
#Sta/Elev= 30
  4523.2  246.99  4662.4  230.98  4866.4  209.34    4888  205.49  4932.8  201.93
  4984.2  203.89  5001.7  199.16  5013.9  199.16  5019.5  200.86  5051.8  203.59
  5073.7   203.4  5087.4  201.94  5123.1   203.1  5204.8  202.68    5221  203.63
  5248.5  208.16  5292.3   213.1  5412.4  216.81  5455.7  217.52  5477.6  219.35
  5493.7  218.32  5553.6  219.42  5565.4  220.88  5610.9  221.87  5679.1  221.54
  5750.3  224.69  5766.5  223.63  5815.9   226.1  5853.9  231.68  6109.9  241.49
#Mann= 5 ,-1 , 0
  4523.2     .17       0  4932.8     .15       0  4984.2     .09       0
  5051.8     .15       0  5412.4     .17       0
Bank Sta=4984.2,5051.8
XS Rating Curve= 0 ,0
Exp/Cntr=0.3,0.1

Type RM Length L Ch R = 1 ,3258    ,443,443,443
BEGIN DESCRIPTION:
SMITH BRANCH 6.0
END DESCRIPTION:
XS GIS Cut Line= 3
      3785006.12     10190763.76      3784362.25     10190823.13
      3783428.06     10191732.48
#Sta/Elev= 30
  4353.4  248.36    4422  241.09  4492.4  236.74    4597  227.78  4693.1  217.22
  4872.9  200.51    4894  200.11  4954.2  202.91  4984.3  201.98  5002.6  198.82
  5014.8  198.82  5015.3  199.32  5015.8   202.7  5022.8  202.09    5030  203.34
  5065.2  202.64  5079.4  200.83    5129  199.97    5235   201.3  5263.3  203.08
    5334  210.38  5420.7  216.04    5429  215.94  5475.5  217.25  5652.4  226.93
  5793.7  234.03  5892.7  236.03  5984.5  235.91  6175.6  240.57  6303.7   241.7
#Mann= 7 ,-1 , 0
  4353.4     .17       0  4872.9     .15       0  4954.2     .09       0
    5030     .15       0  5420.7     .17       0    5429     .15       0
  5652.4     .17       0
Bank Sta=4954.2,5030
XS Rating Curve= 0 ,0
Exp/Cntr=0.3,0.1

Type RM Length L Ch R = 1 ,2815    ,461,461,461
BEGIN DESCRIPTION:
SMITH BRANCH 5.0
END DESCRIPTION:
XS GIS Cut Line= 4
      3785032.22     10190482.51      3784299.75     10190468.96
      3784271.56     10190485.76      3783407.23     10191664.76
#Sta/Elev= 30
  4267.4  245.88  4371.8     237  4391.8   236.4  4411.8   233.4  4616.2  216.54
  4700.1  208.25  4791.9   201.7  4831.9  199.74  4901.9  199.89  4971.9  201.58
  4992.3  198.53  5004.5  198.53    5011  200.28  5016.8  199.29  5025.5   201.3
  5032.1  201.65  5082.1  201.44  5096.7  202.32  5182.4  199.69  5203.3  200.61
  5225.4  199.78  5303.6  201.77  5332.9  203.91  5465.1  209.03  5716.4  219.27
  5887.4  226.29  5955.8  229.68  6127.2  234.87  6269.2  237.53  6494.7  239.76
#Mann= 7 ,-1 , 0
  4267.4     .17       0  4700.1     .15       0  4971.9     .09       0
  5032.1     .15       0  5465.1     .17       0  5716.4     .15       0
  5887.4     .17       0
Bank Sta=4971.9,5032.1
XS Rating Curve= 0 ,0
Exp/Cntr=0.3,0.1

Type RM Length L Ch R = 1 ,2354    ,466,466,466
BEGIN DESCRIPTION:
SMITH BRANCH 4.0
END DESCRIPTION:
XS GIS Cut Line= 3
      3785063.48     10190190.84      3784270.24     10190206.81
      3783178.04     10191190.83
#Sta/Elev= 30
  4206.6  239.85  4693.3  208.98  4812.3  199.17  4842.4  200.69  4932.4  201.43
  4960.3  200.87  4972.4  198.59    5005  199.43  5018.6  201.24  5138.9  200.34
  5161.2  197.89    5174  198.39  5209.9  199.64  5245.5  204.31  5280.9  206.36
  5452.8   209.6  5516.3  211.02  5627.7  212.76  5656.1  214.84  5706.3  214.66
  5776.5  214.12  5790.7  215.82    5840   216.8  5939.4  221.91  6059.7  224.06
  6073.9  225.51  6187.5  227.87  6307.8   232.4  6385.6  233.84  6470.1  232.81
#Mann= 8 ,-1 , 0
  4206.6     .17       0  4693.3     .15       0  4932.4     .06       0
  5018.6     .15       0    5174     .15       0  5452.8     .17       0
  5516.3     .15       0  5706.3     .17       0
Bank Sta=4932.4,5018.6
XS Rating Curve= 0 ,0
Exp/Cntr=0.3,0.1