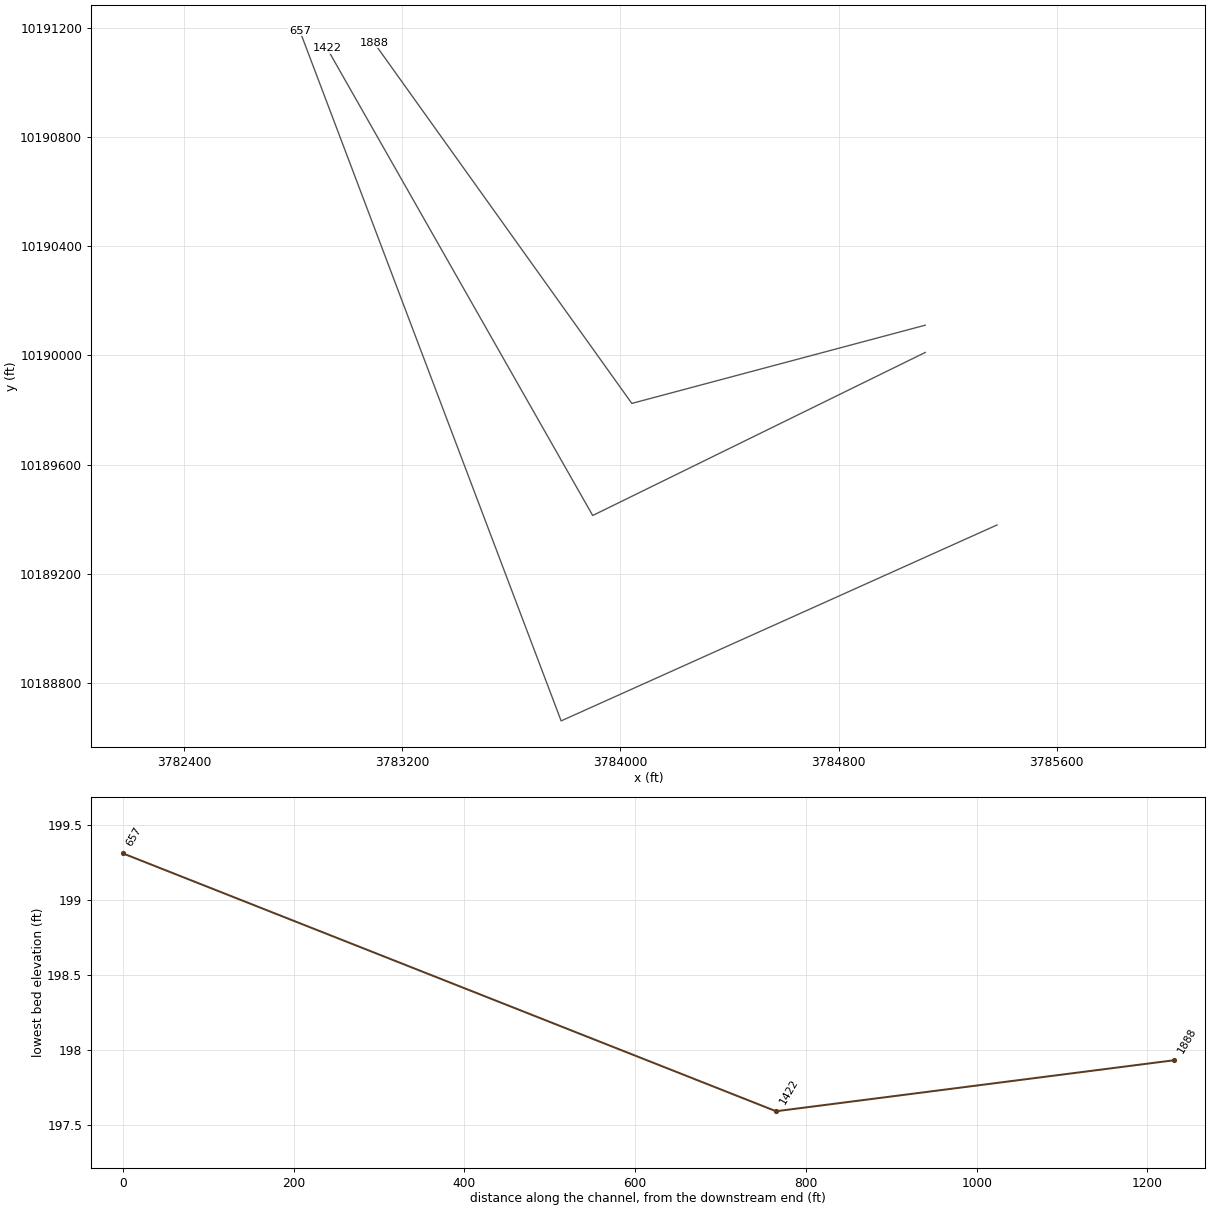
HEC-RAS study SMITH BRANCH.prj: SMITH BRANCH Base Level Engineering

--- SMITH BRANCH.g01 (geometry) --- (continued)

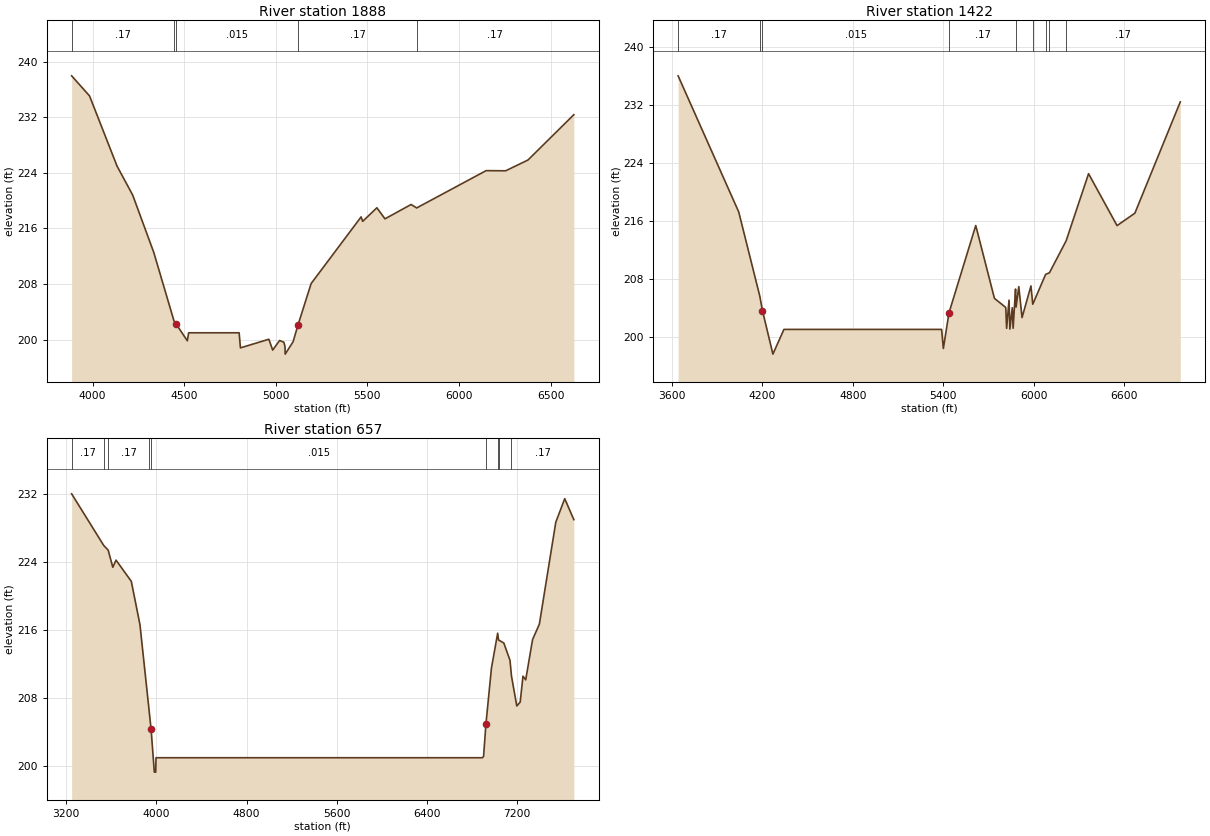
Type RM Length L Ch R = 1 ,1888    ,466,466,466
BEGIN DESCRIPTION:
SMITH BRANCH 3.0
END DESCRIPTION:
XS GIS Cut Line= 3
      3785117.83     10190111.07      3784041.63     10189824.14
      3783095.81     10191147.61
#Sta/Elev= 30
  3886.2  237.96  3983.9  235.07  4133.9  224.98  4219.3  220.81  4334.5  212.55
  4444.2  202.75  4455.4   202.3  4517.5  199.85  4524.7     201  4800.2     201
  4807.3  198.83  4962.5  200.07  4983.2  198.51    5021  199.89  5044.4  199.64
  5050.5  199.02  5051.5  197.93  5094.6  199.71  5121.8  202.15  5193.1  208.08
  5465.9  217.67  5474.5  217.03  5551.9  218.98  5596.1  217.39  5738.6  219.45
  5769.2  218.96  6147.8  224.32  6254.7   224.3  6376.4  225.85  6626.7  232.37
#Mann= 5 ,-1 , 0
  3886.2     .17       0  4444.2     .11       0  4455.4    .015       0
  5121.8     .17       0  5769.2     .17       0
Bank Sta=4455.4,5121.8
XS Rating Curve= 0 ,0
Exp/Cntr=0.3,0.1

Type RM Length L Ch R = 1 ,1422    ,765,765,765
BEGIN DESCRIPTION:
SMITH BRANCH 2.0
END DESCRIPTION:
XS GIS Cut Line= 3
      3785117.81     10190011.05      3783898.13     10189413.04
      3782923.46     10191127.22
#Sta/Elev= 30
  3641.6  235.98  4043.6   217.2  4183.1  205.61    4201  203.59  4270.2  197.59
  4343.2     201  5388.9     201  5400.6  198.37  5438.1   203.3  5615.4  215.33
  5739.4  205.28  5814.3  204.03  5820.1  201.15    5836  205.04  5841.7  201.05
  5857.6  203.99  5863.3  201.16  5879.2  206.57  5882.8  204.08  5900.8   206.9
  5922.4  202.63  5981.5     207  5993.5  204.47  6078.8  208.59  6104.1  208.81
  6214.8  213.22  6363.5  222.48  6552.4  215.32  6670.6  217.03  6971.9  232.39
#Mann= 9 ,-1 , 0
  3641.6     .17       0  4183.1     .11       0    4201    .015       0
  5438.1     .17       0  5882.8     .15       0  5993.5     .11       0
  6078.8     .15       0  6104.1     .11       0  6214.8     .17       0
#XS Ineff= 1 ,-1
  5615.4    6300  215.33
Permanent Ineff=
       F
Bank Sta=4201,5438.1
XS Rating Curve= 0 ,0
Exp/Cntr=0.3,0.1

Type RM Length L Ch R = 1 ,657     ,0,0,0
BEGIN DESCRIPTION:
SMITH BRANCH 1.0
END DESCRIPTION:
XS GIS Cut Line= 3
      3785381.12     10189378.32       3783782.4     10188659.71
      3782823.88     10191190.79
#Sta/Elev= 30
  3247.2     232  3532.3  225.93  3571.6  225.39  3612.6  223.37  3641.5  224.21
    3777  221.72  3853.8  216.63  3933.9  206.69  3952.5  204.37  3981.4  199.31
  3993.9  199.31  3996.3     201    6895     201  6904.8  201.15  6926.2  204.99
  6974.8  211.52  7030.2  215.63  7038.2  214.83  7084.7  214.48  7139.7  212.44
  7152.8  210.59    7200  207.08  7230.2  207.54    7255  210.58  7279.1  210.15
  7340.1  214.88  7400.4  216.69  7546.4  228.67  7625.7  231.43  7706.5  228.97
#Mann= 9 ,-1 , 0
  3247.2     .17       0  3532.3     .11       0  3571.6     .17       0
  3933.9     .11       0  3952.5    .015       0  6926.2     .17       0
  7030.2     .17       0  7038.2     .11       0  7152.8     .17       0
Bank Sta=3952.5,6926.2
XS Rating Curve= 0 ,0
Exp/Cntr=0.3,0.1

Chan Stop Cuts=-1
Use User Specified Reach Order=0
Composite Channel Slope=5