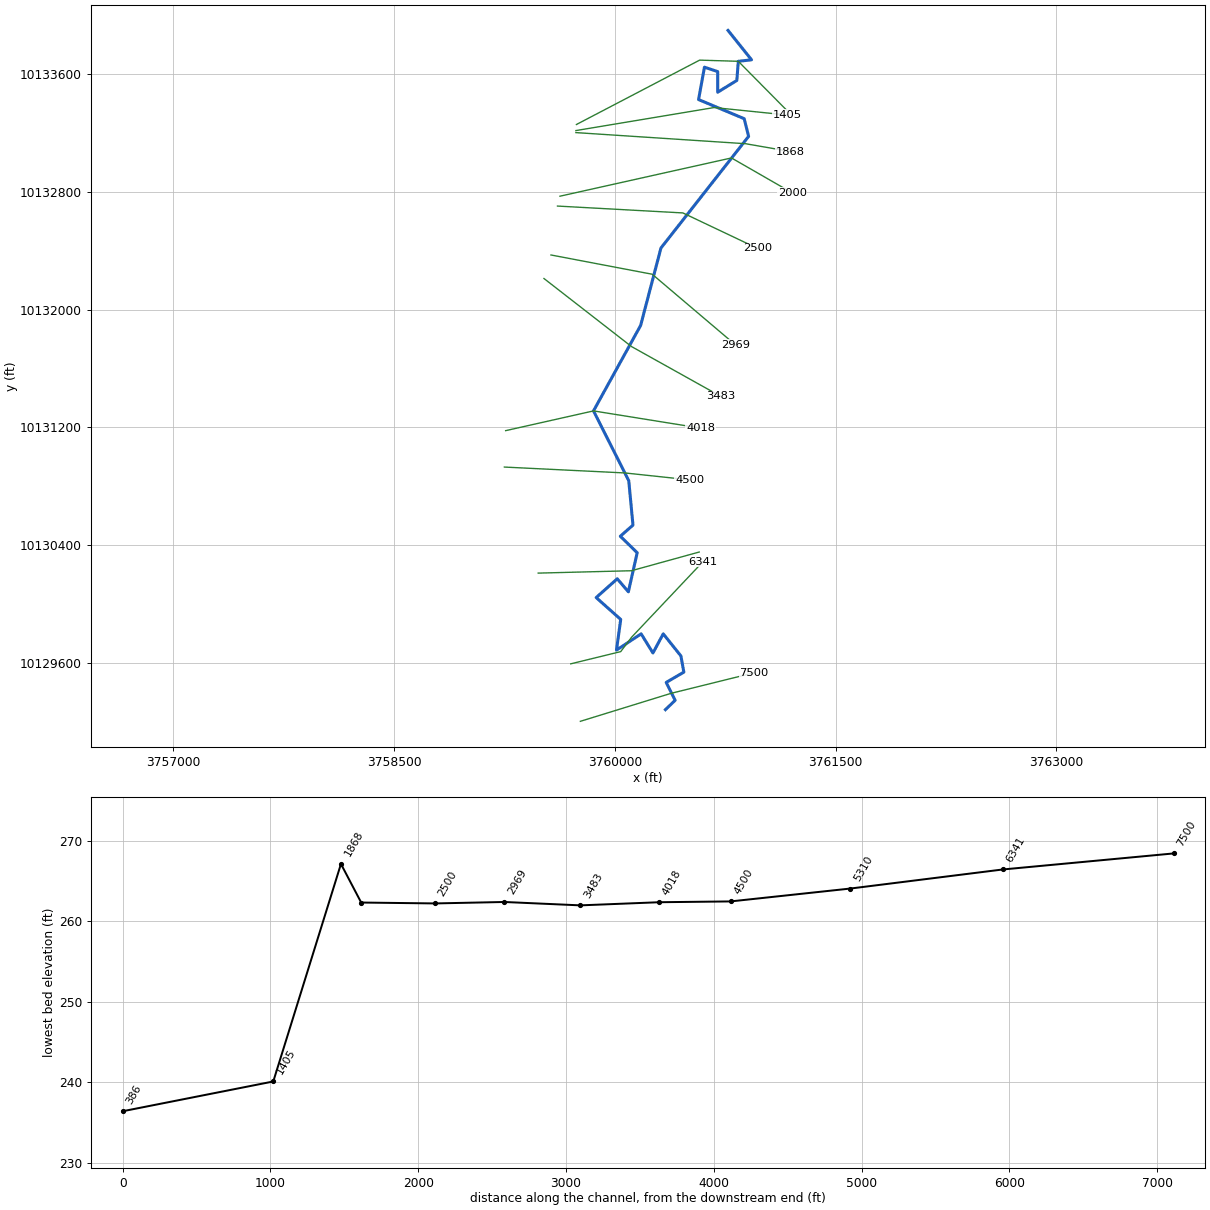
--- STEWART CREEK NORTH TRIB NO 2.prj (project) ---

Proj Title=STEWART CREEK NORTH TRIB NO 2 Base Level Engineering
Current Plan=p01
Default Exp/Contr=0.3,0.1
English Units
Geom File=g01
Flow File=f01
Plan File=p01
Y Axis Title=Elevation
X Axis Title(PF)=Main Channel Distance
X Axis Title(XS)=Station
BEGIN DESCRIPTION:
STEWART CREEK NORTH TRIB NO 2
END DESCRIPTION:
DSS Export Rating Curves= 0
DSS Export Rating Curve Sorted= 0
DSS Export Volume Flow Curves= 0
DXF OffsetX= 0
DXF OffsetY= 0
DXF ScaleX= 1
DXF ScaleY= 10

--- STEWART CREEK NORTH TRIB NO 2.p01 (plan) ---

Plan Title=Multiple Run
Short Identifier=Multiple
Geom File=g01
Flow File=f01
Subcritical Flow
K Sum by GR= 0
Std Step Tol= 0.01
Critical Tol= 0.01
Num of Std Step Trials= 20
Max Error Tol= 0.3
Flow Tol Ratio= 0.001
Split Flow NTrial= 30
Split Flow Tol= 0.02
Split Flow Ratio= 0.02
Log Output Level= 0
Friction Slope Method= 1
Unsteady Friction Slope Method= 2
Unsteady Bridges Friction Slope Method= 1
Parabolic Critical Depth
Global Vel Dist=  1 , 1 , 1
Global Log Level= 0
CheckData=True
Encroach Param= -1, 0, 0, 0
BEGIN DESCRIPTION:
Multiple Run
END DESCRIPTION:

--- STEWART CREEK NORTH TRIB NO 2.f01 (steady flow) ---

Flow Title=Multiple
Program Version=4.10
Number of Profiles= 7
Profile Names=10-year,25-year,50-year,1pct_min,100-year,1pct_plu,500-year
River Rch & RM=STEWART CREEK NO,Reach-1         ,7500
     697     959    1311     591    1785    5391    3412
River Rch & RM=STEWART CREEK NO,Reach-1         ,6341
     703     959    1302     582    1758    5309    3309
River Rch & RM=STEWART CREEK NO,Reach-1         ,2500
     652     880    1187     526    1589    4799    2945
Boundary for River Rch & Prof#=STEWART CREEK NO,Reach-1         , 1
Up Type= 0
Dn Type= 3
Dn Slope=0.005
Boundary for River Rch & Prof#=STEWART CREEK NO,Reach-1         , 2
Up Type= 0
Dn Type= 3
Dn Slope=0.005
Boundary for River Rch & Prof#=STEWART CREEK NO,Reach-1         , 3
Up Type= 0
Dn Type= 3
Dn Slope=0.005
Boundary for River Rch & Prof#=STEWART CREEK NO,Reach-1         , 4
Up Type= 0
Dn Type= 3
Dn Slope=0.005
Boundary for River Rch & Prof#=STEWART CREEK NO,Reach-1         , 5
Up Type= 0
Dn Type= 3
Dn Slope=0.005
Boundary for River Rch & Prof#=STEWART CREEK NO,Reach-1         , 6
Up Type= 0
Dn Type= 3
Dn Slope=0.005
Boundary for River Rch & Prof#=STEWART CREEK NO,Reach-1         , 7
Up Type= 0
Dn Type= 3
Dn Slope=0.005
DSS Import GetInterval= 0
DSS Import GetPeak= 0
DSS Import FillOption= 0

--- STEWART CREEK NORTH TRIB NO 2.g01 (geometry) ---

Geom Title=Existing Conditions
Program Version=4.10

River Reach=STEWART CREEK NO,Reach-1
Reach XY= 30
      3760343.23     10129281.84      3760409.03     10129345.45
      3760348.23     10129466.84      3760468.23     10129536.84
      3760448.23     10129646.84      3760328.23     10129796.84
      3760258.23     10129666.84      3760178.23     10129796.84
       3760010.6     10129686.59      3760039.24     10129894.93
      3759872.57     10130043.37       3760015.8     10130170.97
      3760091.32     10130082.43      3760151.22     10130348.05
      3760036.64     10130460.03      3760122.57     10130535.55
      3760093.93     10130837.64      3759854.35     10131311.59
      3760174.66     10131892.32      3760312.68     10132418.37
      3760908.23     10133176.84      3760878.23     10133296.84
      3760568.23     10133426.84      3760608.23     10133646.84
      3760698.23     10133616.84      3760698.23     10133476.84
      3760828.23     10133556.84      3760838.23     10133686.84
      3760928.23     10133696.84      3760768.23     10133896.84

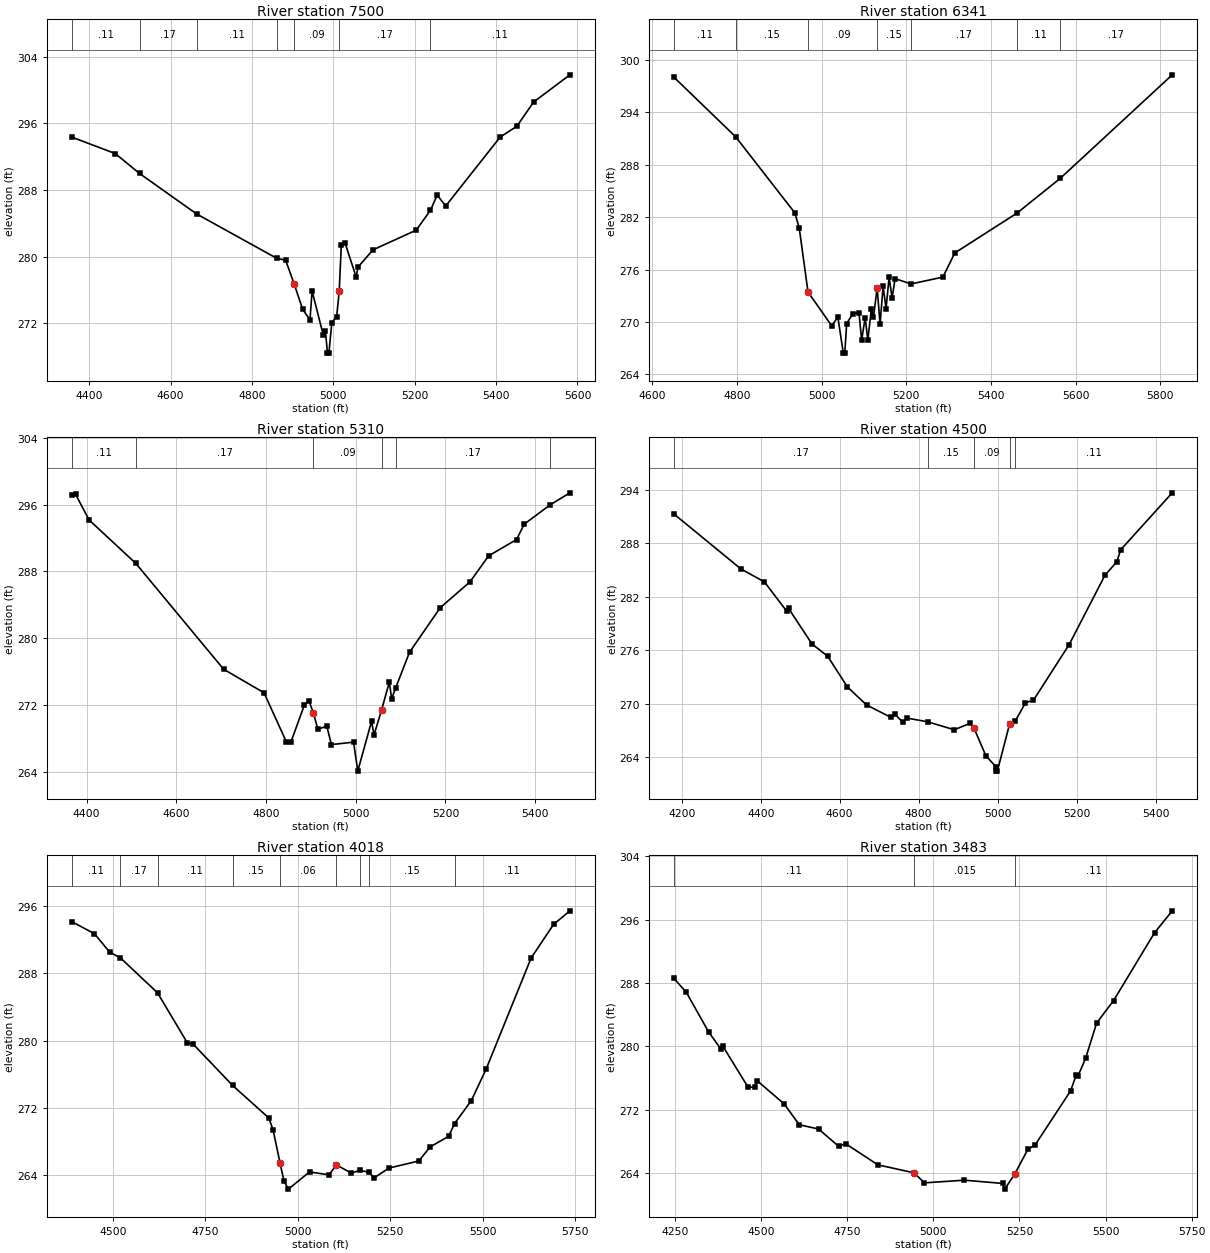
Type RM Length L Ch R = 1 ,7500    ,1159,1159,1159
BEGIN DESCRIPTION:
STEWART CREEK NORTH TRIB NO 2 13.5
END DESCRIPTION:
XS GIS Cut Line= 3
      3759765.26     10129202.59      3760379.94     10129392.32
      3760944.29     10129532.07
#Sta/Elev= 30
  4356.7  294.35  4464.1  292.37  4523.8  289.98  4663.9  285.13  4861.2   279.8
  4882.7  279.59  4903.6  276.75  4924.6  273.69  4942.6  272.43  4947.8  275.89
  4975.2  270.61  4980.5  271.14  4985.6  268.44  4989.1  268.44  4996.3   272.1
  5008.2  272.83  5014.4  275.83  5019.6  281.39  5028.8  281.64  5055.9   277.6
    5061  278.77  5097.3  280.82  5203.9  283.19  5238.7  285.57  5255.4  287.41
    5276  286.07  5409.9  294.34  5451.1  295.65  5492.3  298.55  5581.4  301.81
#Mann= 7 ,-1 , 0
  4356.7     .11       0  4523.8     .17       0  4663.9     .11       0
  4861.2     .17       0  4903.6     .09       0  5014.4     .17       0
  5238.7     .11       0
#XS Ineff= 2 , 0
       0                  5028.8       0  281.64
Permanent Ineff=
       F       F
Bank Sta=4903.6,5014.4
XS Rating Curve= 0 ,0
Exp/Cntr=0.3,0.1

Type RM Length L Ch R = 1 ,6341    ,1031,1031,1031
BEGIN DESCRIPTION:
STEWART CREEK NORTH TRIB NO 2 13.0
END DESCRIPTION:
XS GIS Cut Line= 4
      3759700.14     10129593.21      3760039.24     10129676.18
      3760113.33     10129774.08      3760597.88     10130286.89
#Sta/Elev= 30
  4650.9  298.02  4796.9  291.19  4936.8  282.48  4947.1  280.74  4967.7  273.44
  5023.8  269.56  5038.3  270.57  5051.1  266.44  5054.6  266.44  5059.1  269.82
  5073.7  270.97  5088.2  271.04  5094.5  267.94  5102.8  270.49  5109.1  267.95
  5117.4  271.47  5122.4  270.53  5131.1   273.9    5138  269.75  5145.2  274.12
  5152.1  271.52  5159.4  275.14  5166.3  272.76  5173.6  274.96  5211.3  274.36
  5286.4  275.14  5314.7  277.91  5461.7  282.47  5563.5  286.43  5828.3  298.29
#Mann= 7 ,-1 , 0
  4650.9     .11       0  4796.9     .15       0  4967.7     .09       0
  5131.1     .15       0  5211.3     .17       0  5461.7     .11       0
  5563.5     .17       0
Bank Sta=4967.7,5131.1
XS Rating Curve= 0 ,0
Exp/Cntr=0.3,0.1

Type RM Length L Ch R = 1 ,5310    ,810,810,810
BEGIN DESCRIPTION:
STEWART CREEK NORTH TRIB NO 2 11.0
END DESCRIPTION:
XS GIS Cut Line= 3
      3759478.86     10130209.54      3760112.16     10130225.66
      3760572.54     10130352.76
#Sta/Elev= 30
  4366.5  297.13  4375.5  297.23  4405.5  294.16  4509.7  288.96  4705.6  276.27
  4795.6  273.46  4845.6  267.55  4855.6  267.56  4885.7  272.01  4895.7  272.51
  4905.7  271.02  4915.7  269.09  4935.7  269.46  4945.7  267.25  4995.3  267.54
  5004.6  264.07  5035.5  270.06  5040.7  268.38  5057.8  271.41    5075  274.74
  5080.2  272.74  5088.9  274.01    5120  278.31  5188.4  283.64  5254.9  286.75
  5296.4  289.86  5358.6  291.81  5375.8  293.66  5434.2  295.99  5477.6  297.41
#Mann= 6 ,-1 , 0
  4366.5     .11       0  4509.7     .17       0  4905.7     .09       0
  5057.8     .15       0  5088.9     .17       0  5434.2     .11       0
Bank Sta=4905.7,5057.8
XS Rating Curve= 0 ,0
Exp/Cntr=0.3,0.1

Type RM Length L Ch R = 1 ,4500    ,482,482,482
BEGIN DESCRIPTION:
STEWART CREEK NORTH TRIB NO 2 8.5
END DESCRIPTION:
XS GIS Cut Line= 3
      3759248.78     10130930.02       3760067.6     10130890.08
      3760507.41     10130843.22
#Sta/Elev= 30
  4180.2   291.3  4349.5  285.15  4409.5  283.68  4465.6  280.42  4470.6  280.71
  4529.7  276.74  4569.7  275.34  4619.8   271.9  4668.3  269.88  4729.9   268.5
  4739.9  268.86    4760  267.94    4770  268.42  4823.9  267.99  4890.1  267.11
  4930.2  267.82  4940.2   267.3  4970.2   264.2  4995.6  262.97  4995.9  262.47
  4999.4  262.47  5030.4  267.75  5044.7  268.08  5070.6  270.13  5090.8  270.42
  5181.3  276.66  5271.8  284.42  5301.9  285.94    5312   287.3  5442.3  293.67
#Mann= 5 ,-1 , 0
  4180.2     .17       0  4823.9     .15       0  4940.2     .09       0
  5030.4     .15       0  5044.7     .11       0
Bank Sta=4940.2,5030.4
XS Rating Curve= 0 ,0
Exp/Cntr=0.3,0.1

Type RM Length L Ch R = 1 ,4018    ,535,535,535
BEGIN DESCRIPTION:
STEWART CREEK NORTH TRIB NO 2 8.0
END DESCRIPTION:
XS GIS Cut Line= 3
      3759257.44     10131177.41      3759854.35     10131311.59
      3760581.22     10131194.78
#Sta/Elev= 30
  4388.2  294.13  4450.1  292.68  4491.1   290.5  4520.5  289.81  4620.7  285.67
  4701.2  279.74  4716.6   279.6  4823.7  274.68  4921.6  270.82  4933.1  269.44
  4952.3  265.43  4962.6  263.36  4974.6  262.37  5031.8  264.41  5084.6  264.07
  5104.8  265.24  5145.3  264.26  5167.4  264.61  5193.1  264.37  5206.1  263.69
  5246.6  264.87  5327.7  265.71    5358  267.38  5408.3  268.64  5424.1  270.15
  5469.5  272.87    5510  276.66  5631.5  289.82  5692.3   293.8  5736.2   295.4
#Mann= 9 ,-1 , 0
  4388.2     .11       0  4520.5     .17       0  4620.7     .11       0
  4823.7     .15       0  4952.3     .06       0  5104.8     .15       0
  5167.4     .11       0  5193.1     .15       0  5424.1     .11       0
Bank Sta=4952.3,5104.8
XS Rating Curve= 0 ,0
Exp/Cntr=0.3,0.1

Type RM Length L Ch R = 1 ,3483    ,514,514,514
BEGIN DESCRIPTION:
STEWART CREEK NORTH TRIB NO 2 7.0
END DESCRIPTION:
XS GIS Cut Line= 3
      3759517.89     10132211.05      3760112.16     10131749.09
      3760717.82     10131411.09
#Sta/Elev= 30
  4247.3   288.6  4283.5  286.82  4347.7  281.86    4383  279.71  4389.3  280.04
  4461.7  274.91  4482.5  274.82  4488.9  275.67  4567.6  272.73  4611.1  270.11
  4667.2  269.57  4725.1   267.4  4745.9  267.71  4839.1  265.05    4945  264.03
  4973.9  262.77  5090.3  263.11  5201.2   262.7  5207.4  261.98  5236.6  263.89
  5274.3  266.99    5296  267.58  5398.8   274.4  5414.8  276.39  5420.6  276.32
  5442.3  278.51  5474.2  282.96  5523.4  285.79  5642.2  294.36  5693.6  297.13
#Mann= 3 , 0 , 0
  4247.3     .11       0    4945    .015       0  5236.6     .11       0
Bank Sta=4945,5236.6
XS Rating Curve= 0 ,0
Exp/Cntr=0.3,0.1

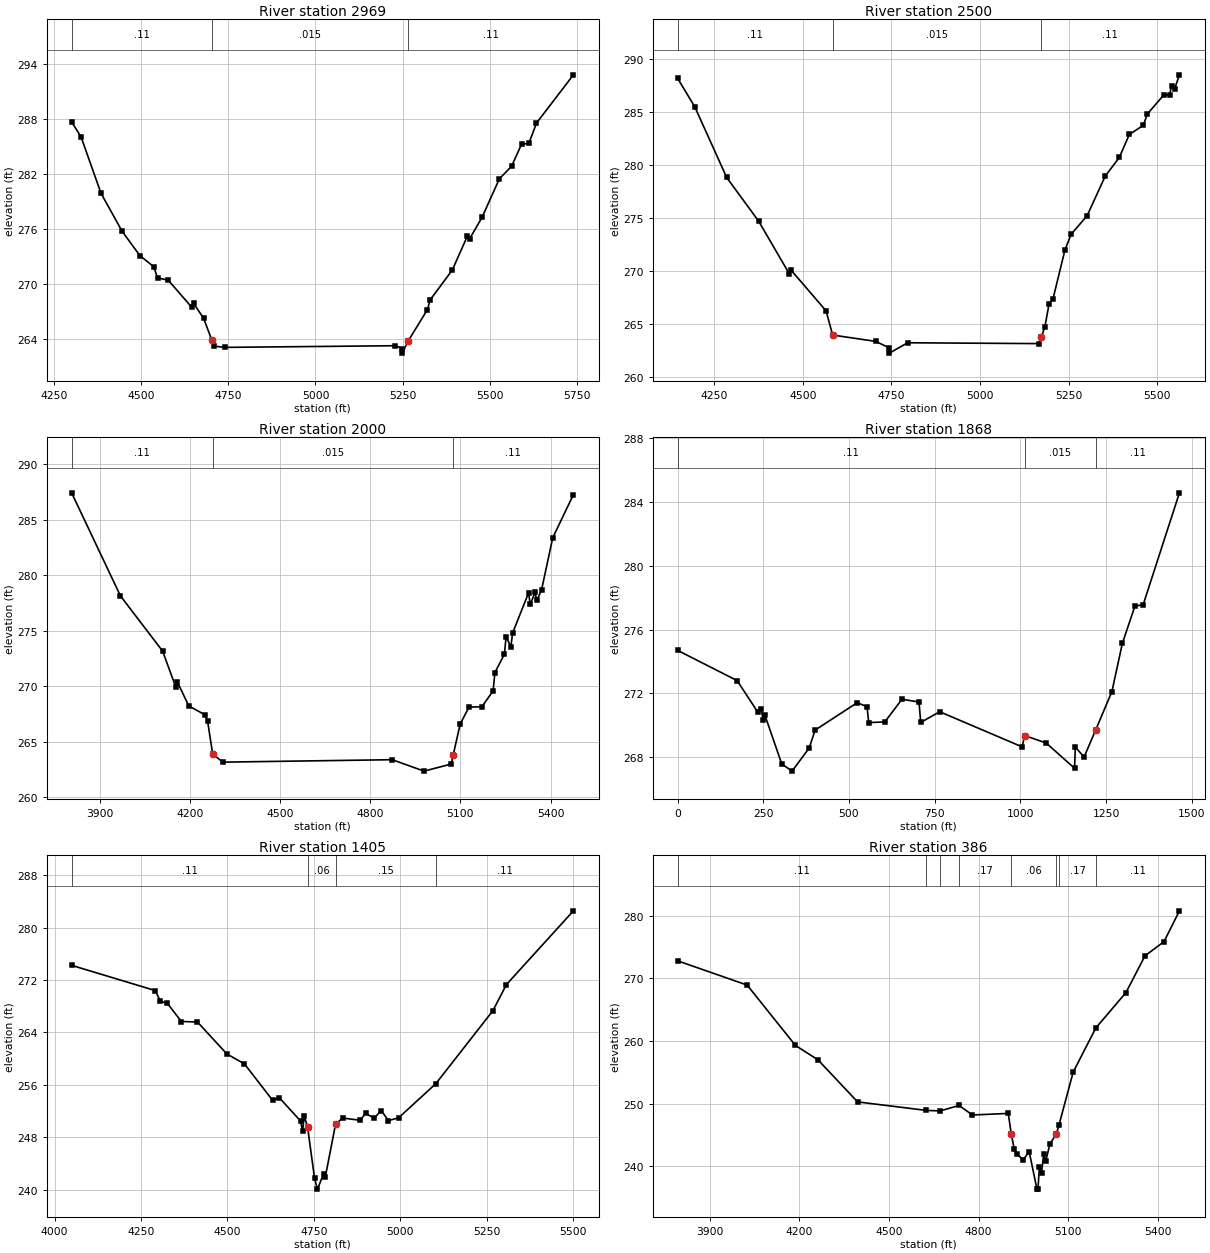
Type RM Length L Ch R = 1 ,2969    ,469,469,469
BEGIN DESCRIPTION:
STEWART CREEK NORTH TRIB NO 2 6.0
END DESCRIPTION:
XS GIS Cut Line= 3
      3759565.61       10132371.      3760253.27     10132240.16
      3760817.89     10131761.04
#Sta/Elev= 30
    4300  287.69    4327  286.07  4384.3  279.89  4444.8  275.74  4495.7  273.08
  4535.8  271.85  4546.6  270.63  4577.1  270.39  4645.3   267.4  4650.4  267.83
  4678.9  266.21  4702.6  263.81  4709.5  263.16    4740  263.03  5229.1  263.21
  5249.1   262.9  5249.4   262.4  5265.4  263.68  5321.4  267.16  5329.1  268.22
  5392.8  271.49  5435.7  275.17  5442.2  274.89  5478.1  277.25  5527.9  281.47
  5563.1  282.85  5591.6  285.26  5612.5  285.34  5634.5  287.57  5740.5  292.85
#Mann= 3 , 0 , 0
    4300     .11       0  4702.6    .015       0  5265.4     .11       0
Bank Sta=4702.6,5265.4
XS Rating Curve= 0 ,0
Exp/Cntr=0.3,0.1

Type RM Length L Ch R = 1 ,2500    ,500,500,500
BEGIN DESCRIPTION:
STEWART CREEK NORTH TRIB NO 2 4.0
END DESCRIPTION:
XS GIS Cut Line= 3
      3759609.61     10132703.31      3760461.64     10132656.67
      3760970.12     10132415.23
#Sta/Elev= 30
  4146.7   288.2    4195  285.52  4285.1  278.83  4375.3   274.7  4461.3  269.75
  4466.3  270.09  4565.6  266.22 4584.09  263.93  4705.8  263.33  4743.8  262.72
  4744.1  262.22  4795.9   263.2    5166  263.12  5172.9  263.71  5183.2  264.71
  5195.1  266.91  5205.9  267.33  5239.7  271.97  5256.9  273.44  5302.4  275.22
  5353.3  278.95  5393.3  280.73  5421.5   282.9  5460.8  283.76  5472.5  284.84
    5518  286.61  5535.2  286.65  5540.7  287.51  5549.3  287.21  5562.9  288.54
#Mann= 3 , 0 , 0
  4146.7     .11       0 4584.09    .015       0  5172.9     .11       0
Bank Sta=4584.09,5172.9
XS Rating Curve= 0 ,0
Exp/Cntr=0.3,0.1

Type RM Length L Ch R = 1 ,2000    ,137,137,137
BEGIN DESCRIPTION:
STEWART CREEK NORTH TRIB NO 2 3.0
END DESCRIPTION:
XS GIS Cut Line= 3
      3759626.37      10132770.3      3760791.63     10133030.24
      3761204.52     10132792.99
#Sta/Elev= 30
  3806.1  287.41  3968.4  278.13    4109  273.14  4152.5  269.92  4157.6  270.39
  4195.9  268.21  4249.6  267.41  4258.4  266.88 4275.58  263.86  4309.7  263.14
  4873.2  263.36  4979.1  262.33  5069.6  262.97  5076.4  263.82  5099.4  266.58
  5128.5  268.09  5171.7  268.14    5209  269.56  5214.8  271.21  5246.4  272.86
  5252.2  274.43    5268  273.54  5273.8  274.78  5326.9  278.39  5332.7  277.35
  5348.5  278.44  5354.3  277.71  5370.1  278.66  5407.4  283.36  5476.2  287.25
#Mann= 3 , 0 , 0
  3806.1     .11       0 4275.58    .015       0  5076.4     .11       0
Bank Sta=4275.58,5076.4
XS Rating Curve= 0 ,0
Exp/Cntr=0.3,0.1

Type RM Length L Ch R = 1 ,1868    ,458,458,458
XS GIS Cut Line= 3
      3759734.66     10133202.42      3760888.23     10133126.84
      3761191.99     10133073.95
#Sta/Elev= 30
       0  274.69   173.6   272.8   233.7  270.83   243.7  271.02   249.4  270.36
   254.4  270.65   303.8  267.58   333.9  267.13     384  268.58   401.1   269.7
   524.3  271.42   552.7  271.16   557.7  270.17   604.5  270.21   654.6  271.63
   704.4  271.46   709.4  270.18   764.8  270.85  1005.3  268.65  1012.6  269.36
  1075.5  268.89  1158.3  267.31  1160.6  268.64  1186.1  268.01  1220.2  269.72
  1267.3  272.11  1297.8  275.13  1334.4  277.46  1358.7  277.56  1464.4  284.56
#Mann= 3 , 0 , 0
       0     .11       0  1012.6    .015       0  1220.2     .11       0
Bank Sta=1012.6,1220.2
XS Rating Curve= 0 ,0
Exp/Cntr=0.3,0.1

Type RM Length L Ch R = 1 ,1405    ,1019,1019,1019
BEGIN DESCRIPTION:
STEWART CREEK NORTH TRIB NO 2 2.0
END DESCRIPTION:
XS GIS Cut Line= 3
      3759734.78     10133216.22      3760673.86     10133372.62
      3761170.57     10133321.97
#Sta/Elev= 30
  4049.2  274.23  4291.2  270.38  4305.8  268.74    4326  268.44  4366.6  265.66
  4412.9  265.59  4498.4   260.7  4549.1  259.19  4630.2  253.65  4650.4     254
  4711.3  250.48  4717.1  248.93  4722.2  251.19  4731.5  249.62  4751.8  241.72
  4760.2  240.08    4778   242.4    4783  241.97  4812.6  249.98  4832.9  250.93
  4883.6  250.59  4899.7  251.64  4924.2   250.9  4944.4  252.07  4965.6  250.54
  4995.1  250.97  5102.9  256.19  5267.3  267.29  5306.8   271.3  5500.5  282.55
#Mann= 4 ,-1 , 0
  4049.2     .11       0  4731.5     .06       0  4812.6     .15       0
  5102.9     .11       0
Bank Sta=4731.5,4812.6
XS Rating Curve= 0 ,0
Exp/Cntr=0.3,0.1

Type RM Length L Ch R = 1 ,386     ,0,0,0
BEGIN DESCRIPTION:
STEWART CREEK NORTH TRIB NO 2 1.0
END DESCRIPTION:
XS GIS Cut Line= 4
      3759738.33     10133257.43      3760575.45     10133694.81
      3760838.23     10133686.84      3761170.55     10133350.67
#Sta/Elev= 30
  3792.6  272.81  4025.3  268.94    4187  259.31  4262.5  257.01    4395   250.3
  4625.8  248.94  4671.7  248.86  4734.9  249.73  4779.5  248.21  4899.6  248.46
  4909.6  245.18  4919.6  242.75  4929.6  241.95  4949.6  241.06  4969.6  242.37
  4995.6  236.38  4999.1  236.38  5003.8  239.96  5010.9  238.92    5018  241.95
    5025  240.83  5039.1   243.6  5060.4  245.16  5069.6  246.65    5117  255.06
  5192.8   262.1  5293.7  267.75  5357.4  273.61    5421  275.87  5472.7  280.79
#Mann= 8 ,-1 , 0
  3792.6     .11       0  4625.8     .17       0  4671.7     .11       0
  4734.9     .17       0  4909.6     .06       0  5060.4     .15       0
  5069.6     .17       0  5192.8     .11       0
Bank Sta=4909.6,5060.4
XS Rating Curve= 0 ,0
Exp/Cntr=0.3,0.1

Chan Stop Cuts=-1
Use User Specified Reach Order=0
Composite Channel Slope=5