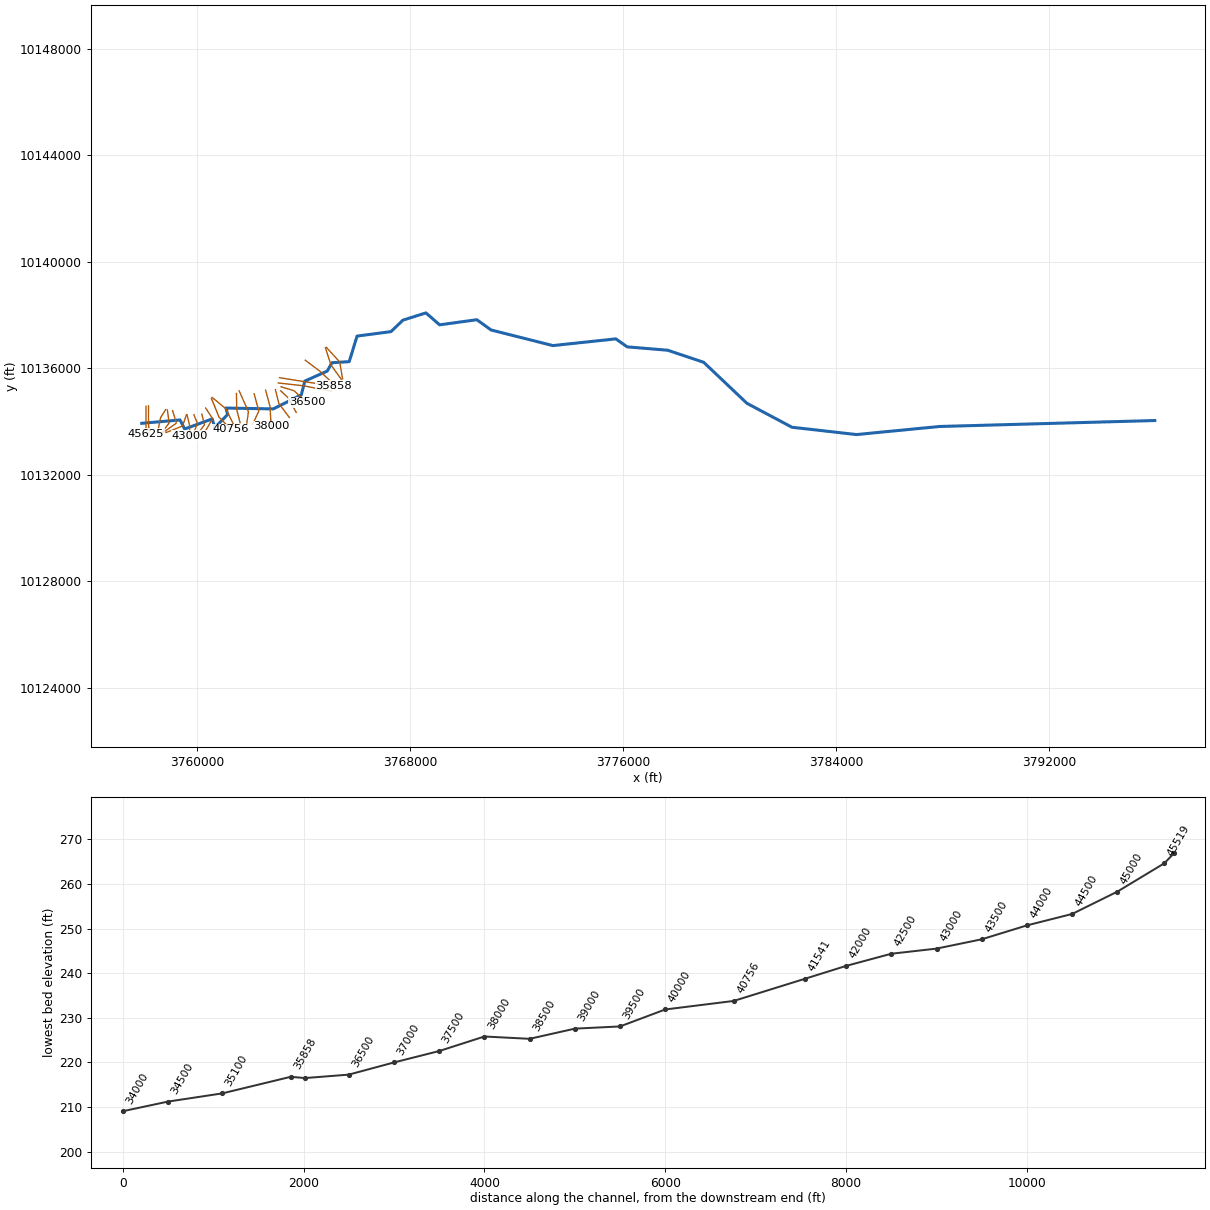
--- STEWART CREEK NORTH.prj (project) ---

Proj Title=STEWART CREEK NORTH Base Level Engineering
Current Plan=p01
Default Exp/Contr=0.3,0.1
English Units
Geom File=g01
Flow File=f01
Plan File=p01
Y Axis Title=Elevation
X Axis Title(PF)=Main Channel Distance
X Axis Title(XS)=Station
BEGIN DESCRIPTION:
STEWART CREEK NORTH
END DESCRIPTION:
DSS File=dss
DSS Export Rating Curves= 0
DSS Export Rating Curve Sorted= 0
DSS Export Volume Flow Curves= 0
DXF OffsetX= 0
DXF OffsetY= 0
DXF ScaleX= 1
DXF ScaleY= 10

--- STEWART CREEK NORTH.p01 (plan) ---

Plan Title=Multiple Run
Program Version=4.10
Short Identifier=Multiple Run
Geom File=g01
Flow File=f01
Subcritical Flow
K Sum by GR= 0
Std Step Tol= 0.01
Critical Tol= 0.01
Num of Std Step Trials= 20
Max Error Tol= 0.3
Flow Tol Ratio= 0.001
Split Flow NTrial= 30
Split Flow Tol= 0.02
Split Flow Ratio= 0.02
Log Output Level= 0
Friction Slope Method= 1
Unsteady Friction Slope Method= 2
Unsteady Bridges Friction Slope Method= 1
Parabolic Critical Depth
Global Vel Dist= 1 , 1 , 1
Global Log Level= 0
CheckData=True
Encroach Param=-1 ,0,0, 0
BEGIN DESCRIPTION:
Multiple Run
END DESCRIPTION:
Computation Interval=1HOUR
Output Interval=1HOUR
Run HTab= 0
Run UNet= 0
Run PostProcess= 0
Run WQNet= 0
UNET Theta= 1
UNET Theta Warmup= 1
UNET ZTol= 0.02
UNET ZSATol= 0.05
UNET MxIter= 20
UNET MaxInSteps= 0
UNET DtIC= 0
UNET DtMin= 0
UNET MaxCRTS= 20
UNET WFStab= 2
UNET SFStab= 1
UNET WFX= 1
UNET SFX= 1
UNET DSS MLevel= 4
UNET DZMax Abort= 100
UNET Convert EG Bridges= 0
UNET Use Existing IB Tables=-1
UNET Froude Reduction=False
UNET Froude Limit= 1
UNET Froude Power= 10
UNET Time Slicing=0,0, 5
UNET Junction Losses=0
Instantaneous Interval=1HOUR
DSS File=dss
Write IC File= 0
Write IC File at Sim End=0
Echo Input=False
Echo Parameters=False
Echo Output=False
Write Detailed= 0
WQ AD Non Conservative
WQ ULTIMATE=-1
WQ Max Comp Step=1HOUR
WQ Output Interval=15MIN
WQ Output Selected Increments= 0
WQ Output face flow=0
WQ Output face velocity=0
WQ Output face area=0
WQ Output face dispersion=0
WQ Output cell volume=0
WQ Output cell surface area=0
WQ Output cell continuity=0
WQ Output cumulative cell continuity=0
WQ Output face conc=0
WQ Output face dconc_dx=0
WQ Output face courant=0
WQ Output face peclet=0
WQ Output face adv mass=0
WQ Output face disp mass=0
WQ Output cell mass=0
WQ Output cell source sink temp=0
WQ Output cell source sink nsm=0
WQ Output MaxMinRange=-1
WQ Daily Max Min Mean=-1
WQ Daily Range=0
WQ Daily Time=0
WQ Create Restart=0
WQ Fixed Restart=0
WQ System Summary=0
WQ Use Fixed Temperature=0
Sorting and Armoring Iterations= 10
XS Update Threshold= 0.02
Hydraulics Update Threshold= 0.02
Energy Slope Method= 1
Volume Change Method= 0
XS Weighting Method= 0
Number of US Weighted Cross Sections= 1
Number of DS Weighted Cross Sections= 1
Upstream XS Weight=0.25
Main XS Weight=0.5
Downstream XS Weight=0.25
Number of DS XS's Weighted with US Boundary= 1
Upstream Boundary Weight= 1
Weight of XSs Associated with US Boundary= 0
Number of US XS's Weighted with DS Boundary= 1
Downstream Boundary Weight= 0.5
Weight of XSs Associated with DS Boundary= 0.5
Sediment Output Level= 4
Mass or Volume Output= 0
Output Increment Type= 1
Profile and TS Output Increment= 10
XS Output Flag= 0
XS Output Increment= 10
Disregard all LS=0
Disregard all Conn=0
Disregard all Breaches=0
Disregard all Pumps=0

--- STEWART CREEK NORTH.f01 (steady flow) ---

Flow Title=Multiple
Program Version=4.10
Number of Profiles= 7
Profile Names=10-year,25-year,50-year,1pct_min,100-year,1pct_plu,500-year
River Rch & RM=STEWART CREEK NO,Reach-1         ,45625
     256     329     430     186     562    1697     984
River Rch & RM=STEWART CREEK NO,Reach-1         ,45000
     662     905    1232     552    1668    5037    3160
River Rch & RM=STEWART CREEK NO,Reach-1         ,40756
    1200    1686    2336    1062    3207    9685    6257
River Rch & RM=STEWART CREEK NO,Reach-1         ,38500
    1552    2203    3073    1406    4245   12820    8385
River Rch & RM=STEWART CREEK NO,Reach-1         ,34500
    1823    2601    3639    1669    5039   15218   10002
River Rch & RM=STEWART CREEK NO,Reach-1         ,31500
    1944    2764    3858    1764    5326   16084   10507
River Rch & RM=STEWART CREEK NO,Reach-1         ,24000
    1977    2801    3899    1776    5363   16196   10511
River Rch & RM=STEWART CREEK NO,Reach-1         ,21000
    3611    5172    7251    3319   10023   30269   19830
River Rch & RM=STEWART CREEK NO,Reach-1         ,17000
    3562    5063    7060    3214    9706   29312   18987
River Rch & RM=STEWART CREEK NO,Reach-1         ,14000
    4452    6377    8940    4090   12351   37299   24400
River Rch & RM=STEWART CREEK NO,Reach-1         ,10500
    4508    6457    9053    4141   12507   37771   24704
River Rch & RM=STEWART CREEK NO,Reach-1         ,10000
    4481    6406    8967    4096   12370   37357   24357
River Rch & RM=STEWART CREEK NO,Reach-1         ,8000
    4656    6668    9348    4276   12913   38997   25497
River Rch & RM=STEWART CREEK NO,Reach-1         ,3500
    4206    5952    8272    3751   11327   34207   21973
River Rch & RM=STEWART CREEK NO,Reach-1         ,1500
    4303    6096    8480    3847   11619   35089   22575
Boundary for River Rch & Prof#=STEWART CREEK NO,Reach-1         , 1
Up Type= 0
Dn Type= 3
Dn Slope=0.005
Boundary for River Rch & Prof#=STEWART CREEK NO,Reach-1         , 2
Up Type= 0
Dn Type= 3
Dn Slope=0.005
Boundary for River Rch & Prof#=STEWART CREEK NO,Reach-1         , 3
Up Type= 0
Dn Type= 3
Dn Slope=0.005
Boundary for River Rch & Prof#=STEWART CREEK NO,Reach-1         , 4
Up Type= 0
Dn Type= 3
Dn Slope=0.005
Boundary for River Rch & Prof#=STEWART CREEK NO,Reach-1         , 5
Up Type= 0
Dn Type= 3
Dn Slope=0.005
Boundary for River Rch & Prof#=STEWART CREEK NO,Reach-1         , 6
Up Type= 0
Dn Type= 3
Dn Slope=0.005
Boundary for River Rch & Prof#=STEWART CREEK NO,Reach-1         , 7
Up Type= 0
Dn Type= 3
Dn Slope=0.005
DSS Import GetInterval= 0
DSS Import GetPeak= 0
DSS Import FillOption= 0

--- STEWART CREEK NORTH.g01 (geometry) ---

Geom Title=Existing Conditions
Program Version=4.10

River Reach=STEWART CREEK NO,Reach-1
Reach XY= 30
      3757927.96     10133938.96      3759362.35     10134065.52
      3759537.28     10133726.67      3760570.15     10134103.75
      3760671.21     10133776.89      3761150.26     10134270.34
      3761089.71     10134512.55      3762866.21     10134480.31
      3763917.69     10135006.06      3764049.07     10135524.82
      3764892.15     10135901.56      3765067.36     10136214.26
      3765716.42     10136254.36      3766011.26     10137214.56
      3767284.42     10137382.43      3767733.39     10137812.39
      3768598.68     10138085.62      3769111.02     10137637.19
      3770508.14     10137829.53      3771045.77     10137443.09
      3773362.85     10136858.39      3775728.88     10137109.84
      3776155.64     10136809.87      3777676.61     10136683.48
       3779028.6     10136229.79      3780650.62     10134691.08
      3782343.05     10133791.66       3784764.1     10133516.54
      3787880.85     10133819.76      3795967.33     10134043.51

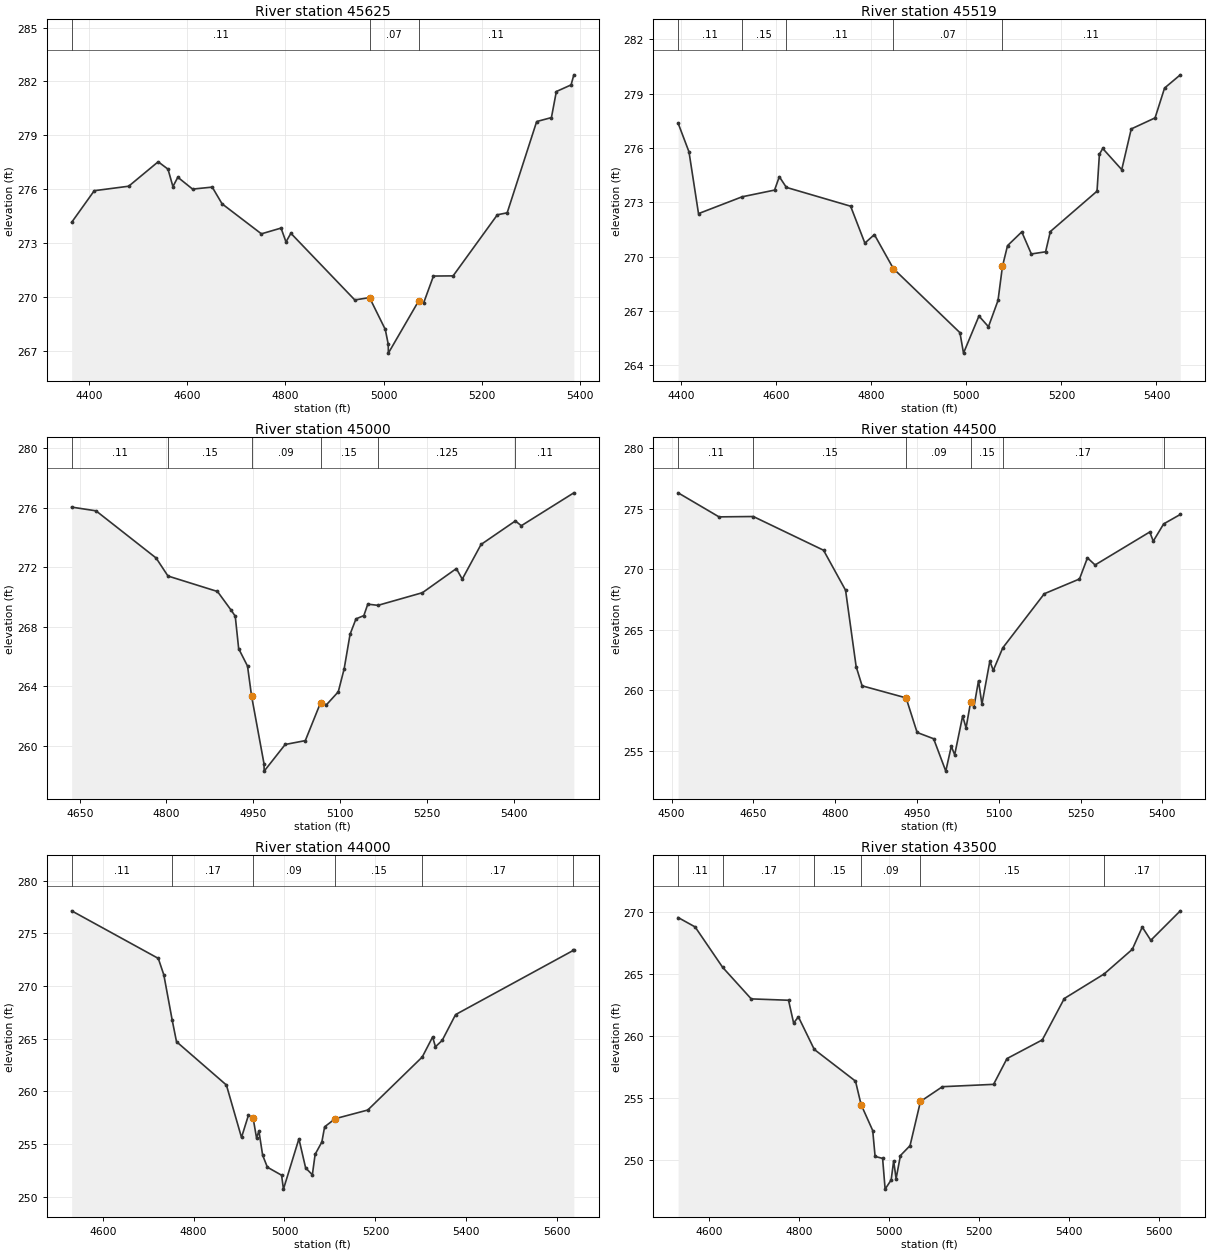
Type RM Length L Ch R = 1 ,45625   ,106,106,106
BEGIN DESCRIPTION:
STEWART CREEK NORTH 91.5
END DESCRIPTION:
XS GIS Cut Line= 3
      3758083.15     10134577.09      3758083.31     10133942.09
      3758085.56      10133555.5
#Sta/Elev= 30
    4365  274.16    4411  275.92    4481  276.17    4541  277.53    4561  277.12
    4571  276.15    4581  276.67    4611  276.01    4651  276.12    4671  275.19
    4751  273.52    4791  273.84    4801  273.07    4811  273.55    4941  269.84
    4971  269.97    5003   268.2    5009  267.38  5009.3  266.88    5071  269.79
    5081  269.67    5101  271.17    5141  271.18    5231  274.58    5251  274.69
    5311  279.77    5341  279.99    5351  281.44    5381  281.81  5386.6  282.37
#Mann= 3 , 0 , 0
    4365     .11       0    4971     .07       0    5071     .11       0
Bank Sta=4971,5071
XS Rating Curve= 0 ,0
Exp/Cntr=0.3,0.1

Type RM Length L Ch R = 1 ,45519   ,519,519,519
BEGIN DESCRIPTION:
STEWART CREEK NORTH 91.0
END DESCRIPTION:
XS GIS Cut Line= 3
       3758179.8     10134593.96       3758178.8     10133987.56
      3758201.55     10133538.03
#Sta/Elev= 30
  4393.6  277.37  4416.5  275.78  4436.5  272.37  4528.3   273.3  4596.5  273.67
  4606.5  274.41  4621.3  273.82  4756.5  272.78  4786.5  270.74  4806.5  271.21
  4846.5  269.33  4986.5  265.79    4994  264.66  5026.5  266.71  5046.5  266.12
  5066.6  267.57  5075.9  269.45  5086.6   270.6  5116.6  271.36  5136.7  270.14
  5166.7  270.26  5176.7  271.38  5274.9  273.61  5279.9  275.65  5286.9  275.97
  5326.9   274.8  5346.9  277.05    5397  277.66    5417  279.31  5450.1  280.04
#Mann= 5 ,-1 , 0
  4393.6     .11       0  4528.3     .15       0  4621.3     .11       0
  4846.5     .07       0  5075.9     .11       0
Bank Sta=4846.5,5075.9
XS Rating Curve= 0 ,0
Exp/Cntr=0.3,0.1

Type RM Length L Ch R = 1 ,45000   ,500,500,500
BEGIN DESCRIPTION:
STEWART CREEK NORTH 90.0
END DESCRIPTION:
XS GIS Cut Line= 3
      3758823.21     10134454.92      3758630.62     10134146.16
      3758530.28     10133652.04
#Sta/Elev= 30
  4636.1  276.05  4678.2   275.8  4782.1  272.63  4802.6  271.42  4888.2  270.38
  4911.7  269.13  4918.9  268.72  4924.8  266.54  4940.1  265.37  4947.1  263.36
  4968.6  258.81  4968.9  258.31  5005.2   260.1    5040  260.36  5066.4  262.91
  5076.6  262.77    5097  263.64  5107.2  265.19  5117.4  267.51  5127.6  268.54
  5141.2  268.76    5148  269.53  5165.6  269.45  5242.5   270.3  5301.1  271.92
  5311.3  271.21  5343.8  273.54  5403.1  275.12  5413.4   274.8  5504.2  277.01
#Mann= 6 ,-1 , 0
  4636.1     .11       0  4802.6     .15       0  4947.1     .09       0
  5066.4     .15       0  5165.6    .125       0  5403.1     .11       0
Bank Sta=4947.1,5066.4
XS Rating Curve= 0 ,0
Exp/Cntr=0.3,0.1

Type RM Length L Ch R = 1 ,44500   ,500,500,500
BEGIN DESCRIPTION:
STEWART CREEK NORTH 89.0
END DESCRIPTION:
XS GIS Cut Line= 3
      3758888.35     10134435.39      3758954.06     10133951.64
      3758693.02     10133606.42
#Sta/Elev= 30
  4511.8  276.33  4586.8  274.34  4649.7  274.37  4778.5  271.58  4818.9  268.27
  4838.3  261.95  4849.2  260.36  4929.9  259.36  4950.1   256.5  4980.4  255.98
  5002.7   253.3  5012.8  255.36    5019  254.65  5033.6  257.86  5039.9  256.88
  5048.2  259.01  5054.4  258.63  5062.7  260.78    5069  258.84  5083.5   262.4
  5089.8  261.64  5107.2   263.5  5183.4  267.98  5247.9   269.2  5262.5  270.95
  5276.5  270.36  5376.8  273.09  5383.2  272.33  5402.3  273.76  5432.8  274.54
#Mann= 6 ,-1 , 0
  4511.8     .11       0  4649.7     .15       0  4929.9     .09       0
  5048.2     .15       0  5107.2     .17       0  5402.3     .11       0
Bank Sta=4929.9,5048.2
XS Rating Curve= 0 ,0
Exp/Cntr=0.3,0.1

Type RM Length L Ch R = 1 ,44000   ,500,500,500
BEGIN DESCRIPTION:
STEWART CREEK NORTH 88.0
END DESCRIPTION:
XS GIS Cut Line= 4
      3759085.83     10134413.69       3759219.8     10133964.96
      3759218.09     10133939.44      3758719.04     10133586.88
#Sta/Elev= 30
  4531.7  277.13  4722.3  272.62  4734.5  271.06  4752.9  266.77  4762.4  264.72
  4872.2  260.61  4905.4  255.64  4920.6  257.74    4931  257.47  4938.5  255.59
  4943.7  256.25  4951.9  253.96  4962.3  252.82  4993.6  252.06  4997.7  250.74
  5031.7  255.51  5046.5  252.75  5061.3   252.1  5067.4  254.04  5082.2  255.21
  5088.3  256.65  5111.6  257.42  5183.2  258.24  5303.1  263.27  5325.9  265.17
  5332.1  264.24  5346.9  264.84  5376.4  267.29  5635.1  273.37  5636.6  273.37
#Mann= 6 ,-1 , 0
  4531.7     .11       0  4752.9     .17       0    4931     .09       0
  5111.6     .15       0  5303.1     .17       0  5635.1     .11       0
Bank Sta=4931,5111.6
XS Rating Curve= 0 ,0
Exp/Cntr=0.3,0.1

Type RM Length L Ch R = 1 ,43500   ,500,500,500
BEGIN DESCRIPTION:
STEWART CREEK NORTH 87.0
END DESCRIPTION:
XS GIS Cut Line= 4
      3759604.48     10134263.95      3759456.81     10133836.14
      3759441.17     10133830.21      3758838.42     10133593.41
#Sta/Elev= 30
  4530.7  269.55  4568.5  268.79  4629.7  265.53  4693.3  262.98  4776.3  262.87
  4787.6  261.03  4798.2  261.53  4833.5   258.9  4925.2  256.34  4937.6  254.45
  4963.5  252.35  4968.8  250.26  4985.5   250.1  4991.1  247.62  5004.5  248.36
  5010.1  249.91  5015.5  248.46  5025.1  250.33  5046.5  251.13  5069.7   254.7
  5118.5  255.89  5232.3  256.08  5262.1  258.16  5340.7  259.67  5389.6  263.01
  5478.1  264.99  5540.8  266.98    5563  268.78    5582  267.71  5647.6  270.09
#Mann= 6 ,-1 , 0
  4530.7     .11       0  4629.7     .17       0  4833.5     .15       0
  4937.6     .09       0  5069.7     .15       0  5478.1     .17       0
Bank Sta=4937.6,5069.7
XS Rating Curve= 0 ,0
Exp/Cntr=0.3,0.1

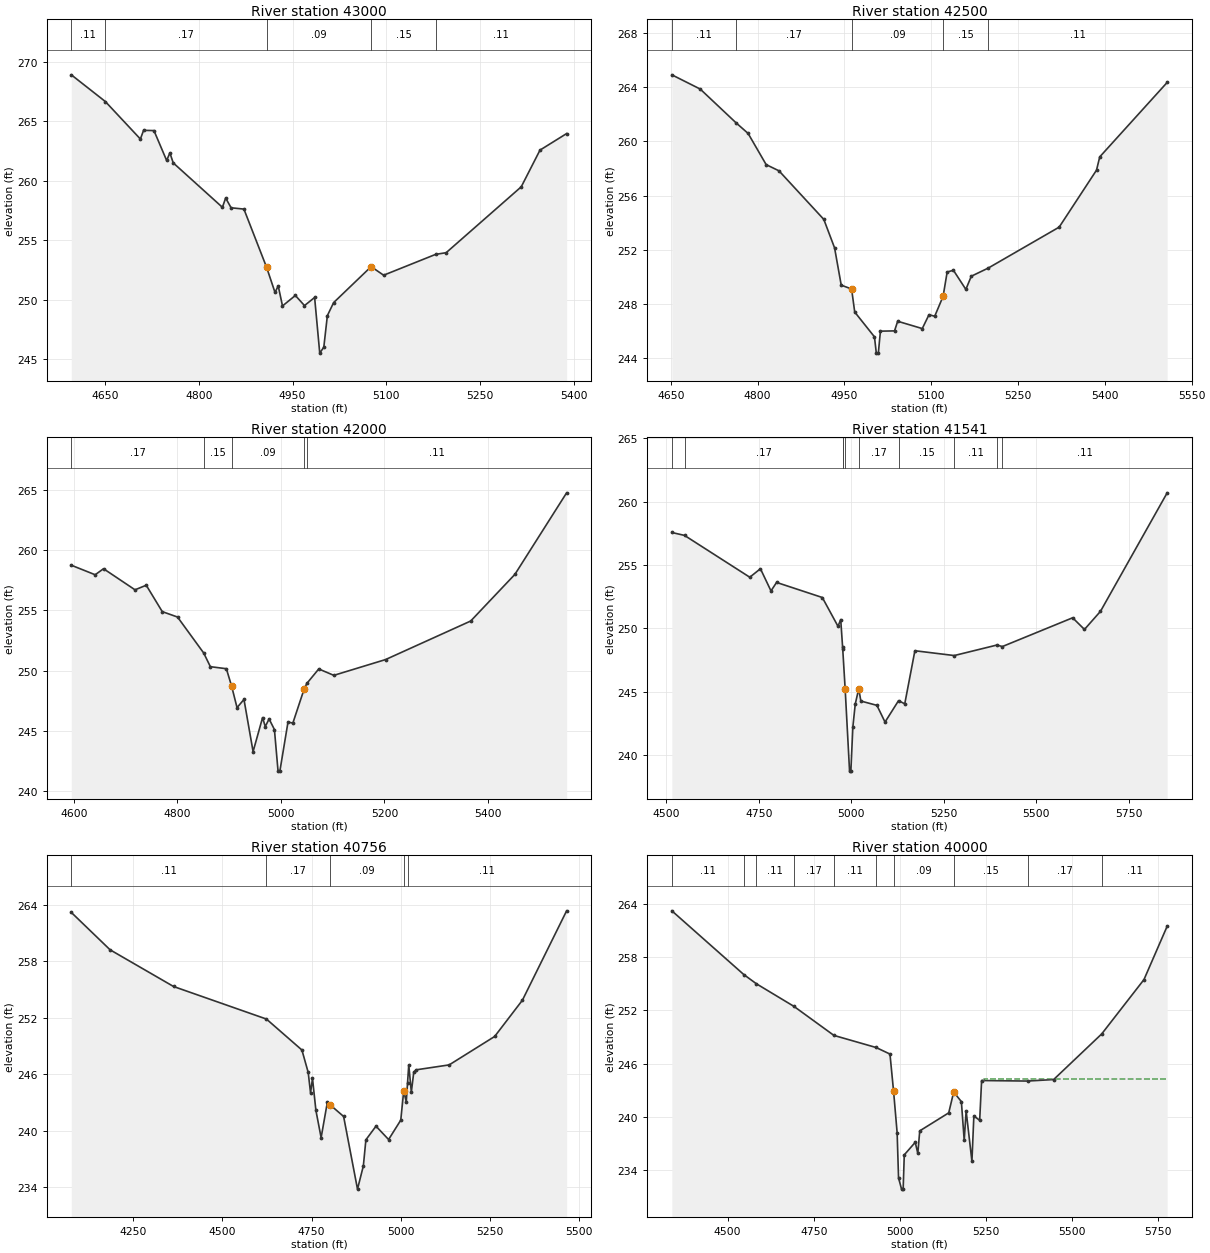
Type RM Length L Ch R = 1 ,43000   ,500,500,500
BEGIN DESCRIPTION:
STEWART CREEK NORTH 86.0
END DESCRIPTION:
XS GIS Cut Line= 3
       3759626.2      10134259.6      3759720.22      10133866.8
      3759726.01     10133478.44
#Sta/Elev= 30
  4596.1  268.89  4650.5  266.65  4706.6   263.5  4711.7  264.23  4728.3  264.21
  4748.6   261.7  4753.8  262.34  4759.1   261.5  4837.8  257.77    4843  258.55
  4851.7  257.73  4872.2  257.62  4908.5  252.73  4921.9  250.63  4927.1  251.17
  4933.9  249.49  4954.5  250.37  4969.1  249.52  4985.3   250.2  4993.5  245.53
    5000  246.03  5005.7  248.68  5015.7  249.77  5075.7  252.79  5095.7  252.07
  5178.9  253.82  5195.7  253.96  5315.8  259.49  5345.8  262.57  5388.4  263.96
#Mann= 5 ,-1 , 0
  4596.1     .11       0  4650.5     .17       0  4908.5     .09       0
  5075.7     .15       0  5178.9     .11       0
Bank Sta=4908.5,5075.7
XS Rating Curve= 0 ,0
Exp/Cntr=0.3,0.1

Type RM Length L Ch R = 1 ,42500   ,500,500,500
BEGIN DESCRIPTION:
STEWART CREEK NORTH 85.0
END DESCRIPTION:
XS GIS Cut Line= 3
      3759884.44     10134261.79      3760016.47     10133939.81
      3759830.18     10133467.53
#Sta/Elev= 30
    4652   264.9    4701  263.85  4763.2  261.35  4783.7  260.58  4814.9  258.28
  4837.1  257.82  4914.5  254.24  4933.1  252.14  4944.6  249.39  4962.5  249.11
  4967.9  247.41    5002  245.58  5005.2  244.38  5008.7  244.38  5012.3     246
  5036.7  246.02  5042.1  246.73  5084.6  246.19  5096.2  247.21  5106.1   247.1
  5120.6  248.57  5127.6  250.36  5138.4  250.49  5159.9  249.08  5169.3  250.05
  5198.5  250.65  5321.1  253.67  5385.6  257.87  5391.2  258.85  5507.7  264.34
#Mann= 5 ,-1 , 0
    4652     .11       0  4763.2     .17       0  4962.5     .09       0
  5120.6     .15       0  5198.5     .11       0
Bank Sta=4962.5,5120.6
XS Rating Curve= 0 ,0
Exp/Cntr=0.3,0.1

Type RM Length L Ch R = 1 ,42000   ,459,459,459
BEGIN DESCRIPTION:
STEWART CREEK NORTH 84.0
END DESCRIPTION:
XS GIS Cut Line= 4
      3760181.74     10134281.37      3760280.77     10133889.08
      3760276.69     10133875.64      3759952.36      10133446.7
#Sta/Elev= 30
  4595.4  258.74  4641.5  257.95  4657.6  258.45  4718.4   256.7  4740.1  257.08
    4771  254.89  4800.5  254.44  4851.1  251.45  4863.9  250.32  4894.8  250.15
  4905.1  248.68  4915.4  246.92  4928.8   247.6  4946.4  243.27  4964.7  246.09
  4969.9  245.35  4977.3  245.98  4987.6   245.1  4994.6  241.65  4998.1  241.65
  5013.8  245.72  5023.2  245.64  5044.8  248.44  5050.2  248.93  5073.2  250.13
  5102.3   249.6  5202.2  250.91  5366.6  254.11  5451.9  257.98  5551.8  264.75
#Mann= 5 ,-1 , 0
  4595.4     .17       0  4851.1     .15       0  4905.1     .09       0
  5044.8     .15       0  5050.2     .11       0
Bank Sta=4905.1,5044.8
XS Rating Curve= 0 ,0
Exp/Cntr=0.3,0.1

Type RM Length L Ch R = 1 ,41541   ,785,785,785
BEGIN DESCRIPTION:
STEWART CREEK NORTH 83.0
END DESCRIPTION:
XS GIS Cut Line= 4
      3760327.12     10134511.41      3760575.02     10134131.87
      3760574.59      10134100.6       3760155.7     10133356.85
#Sta/Elev= 30
  4515.4  257.57  4549.6  257.34  4725.9  254.04  4754.7  254.71  4783.2  252.96
  4798.3  253.63  4921.9  252.44  4964.2  250.17  4971.6   250.7  4976.7  248.52
  4977.1  248.35 4983.54  245.25  4995.5  238.74    4999  238.74  5004.4  242.23
  5010.9  244.04  5020.3  245.24    5026  244.27  5069.4  243.93  5091.3  242.61
  5127.8   244.3  5144.6  244.05    5172  248.24  5278.3  247.86  5393.7  248.69
  5408.3  248.57  5598.2  250.84  5630.1  249.92  5673.4  251.35  5853.6   260.7
#Mann= 10 ,-1 , 0
  4515.4     .11       0  4549.6     .17       0  4976.7     .15       0
  4977.1     .17       0 4983.54     .09       0  5020.3     .17       0
  5127.8     .15       0  5278.3     .11       0  5393.7     .17       0
  5408.3     .11       0
#XS Ineff= 2 , 0
       0                    5172       0  248.24
Permanent Ineff=
       F       F
Bank Sta=4983.54,5020.3
XS Rating Curve= 0 ,0
Exp/Cntr=0.3,0.1

Type RM Length L Ch R = 1 ,40756   ,756,756,756
BEGIN DESCRIPTION:
STEWART CREEK NORTH 81.0
END DESCRIPTION:
XS GIS Cut Line= 4
      3760542.31     10134876.75      3760824.81     10134174.38
       3760941.7     10134056.73      3761262.39     10133720.56
#Sta/Elev= 30
  4077.1  263.19  4185.7  259.22  4363.5  255.32  4623.7  251.86  4723.1  248.57
  4740.7  246.19  4747.3  244.01  4752.7  245.56  4762.3  242.15  4776.9  239.26
  4794.6  243.07  4801.1  242.78  4839.9  241.51  4878.8  233.79  4895.2  236.26
  4902.3  239.03  4930.6  240.48  4965.9  239.06    5000  241.12  5008.2   244.2
  5015.4  243.08  5018.9  245.04  5022.4  246.99  5029.6  244.09  5036.5  246.24
  5043.8  246.47  5135.6  246.99    5263  250.01  5340.7  253.86  5464.6  263.36
#Mann= 5 ,-1 , 0
  4077.1     .11       0  4623.7     .17       0  4801.1     .09       0
  5008.2     .15       0  5018.9     .11       0
Bank Sta=4801.1,5008.2
XS Rating Curve= 0 ,0
Exp/Cntr=0.3,0.1

Type RM Length L Ch R = 1 ,40000   ,500,500,500
BEGIN DESCRIPTION:
STEWART CREEK NORTH 80.0
END DESCRIPTION:
XS GIS Cut Line= 3
      3760567.85     10134911.07      3761079.02     10134490.89
      3761422.68     10133795.81
#Sta/Elev= 30
  4338.3  263.22  4547.1  256.04  4583.8     255  4692.5  252.46  4808.5  249.19
  4930.7  247.83  4971.1  247.09 4981.53  242.92  4991.9  238.23    4996  233.14
  5004.7  231.88  5009.4  231.88  5012.6  235.74  5044.4  237.15  5051.9  235.91
  5057.5  238.44  5141.6  240.47    5156  242.82  5178.3  241.73  5186.5  237.37
  5192.1  240.69  5208.9  235.01  5214.5  240.12  5231.4  239.63    5237  244.11
  5370.4  244.05    5446  244.22  5585.5  249.36  5708.1  255.48  5775.4  261.49
#Mann= 10 ,-1 , 0
  4338.3     .11       0  4547.1     .17       0  4583.8     .11       0
  4692.5     .17       0  4808.5     .11       0  4930.7     .17       0
 4981.53     .09       0    5156     .15       0  5370.4     .17       0
  5585.5     .11       0
#XS Ineff= 2 , 0
       0                  5245.2       0  244.24
Permanent Ineff=
       F       F
Bank Sta=4981.53,5156
XS Rating Curve= 0 ,0
Exp/Cntr=0.3,0.1

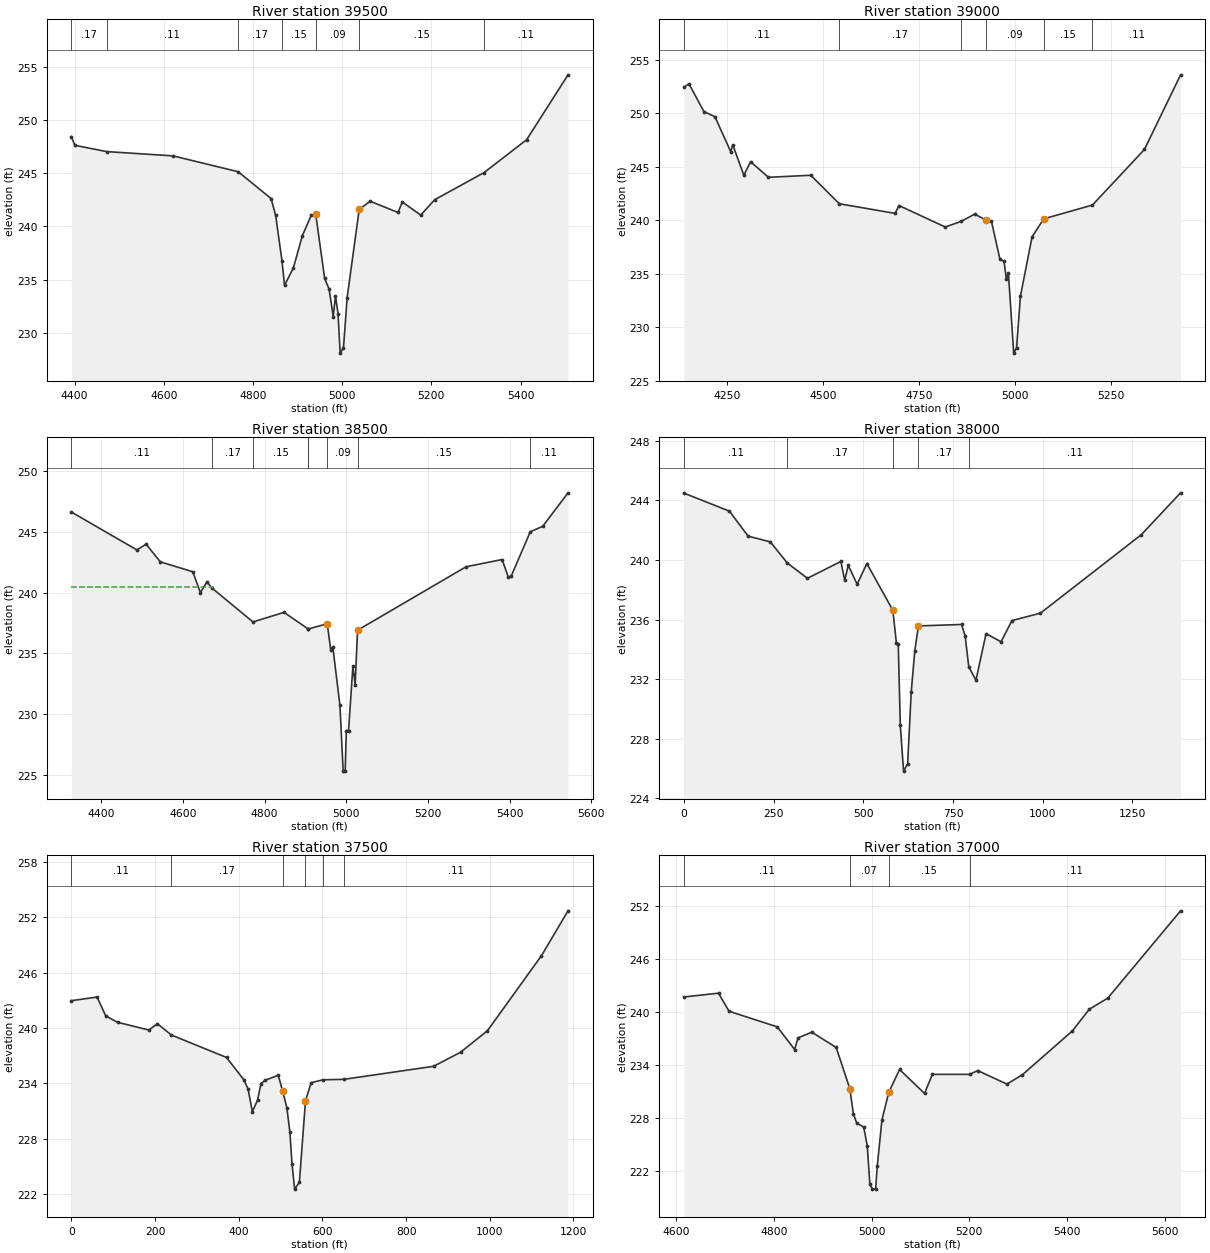
Type RM Length L Ch R = 1 ,39500   ,500,500,500
BEGIN DESCRIPTION:
STEWART CREEK NORTH 79.0
END DESCRIPTION:
XS GIS Cut Line= 3
      3761481.66     10135058.88      3761493.15     10134451.89
      3761617.85     10133961.08
#Sta/Elev= 30
  4392.9  248.44  4400.7  247.62  4472.1  247.03  4620.7  246.63  4766.8  245.14
  4840.8  242.61  4850.8  241.04  4865.1  236.77  4870.8  234.45  4890.8  236.11
  4910.8  239.13  4930.8  241.05  4940.8  241.12  4960.8   235.1  4970.8  234.09
    4980  231.51    4985  233.45  4990.8   231.8  4995.5  228.08    5003  228.58
  5011.2  233.29  5038.2  241.59  5062.7  242.36  5125.2  241.31    5135  242.29
  5176.2  241.06  5207.2   242.5  5318.3  245.06  5413.6  248.15  5506.4  254.25
#Mann= 7 ,-1 , 0
  4392.9     .17       0  4472.1     .11       0  4766.8     .17       0
  4865.1     .15       0  4940.8     .09       0  5038.2     .15       0
  5318.3     .11       0
Bank Sta=4940.8,5038.2
XS Rating Curve= 0 ,0
Exp/Cntr=0.3,0.1

Type RM Length L Ch R = 1 ,39000   ,500,500,500
BEGIN DESCRIPTION:
STEWART CREEK NORTH 78.0
END DESCRIPTION:
XS GIS Cut Line= 3
      3761581.47     10135163.04      3761931.56     10134375.67
      3761872.28     10133947.75
#Sta/Elev= 30
  4138.3  252.41  4151.4  252.73  4190.3  250.14    4219  249.66  4260.1   246.4
  4265.5  247.04  4294.3  244.19    4312  245.45  4358.5     244  4468.8  244.19
    4543  241.53  4688.2  240.63  4698.6  241.36    4819  239.36  4860.3  239.88
  4895.6  240.56  4926.1  239.99  4939.4  239.88  4961.3  236.37  4972.2  236.14
  4978.1  234.51  4983.6  235.02  4997.3  227.58  5004.8  228.08  5014.7  232.87
    5045  238.42  5075.3  240.12  5202.5  241.41  5337.8   246.6    5432  253.57
#Mann= 6 ,-1 , 0
  4138.3     .11       0    4543     .17       0  4860.3     .15       0
  4926.1     .09       0  5075.3     .15       0  5202.5     .11       0
Bank Sta=4926.1,5075.3
XS Rating Curve= 0 ,0
Exp/Cntr=0.3,0.1

Type RM Length L Ch R = 1 ,38500   ,500,500,500
BEGIN DESCRIPTION:
STEWART CREEK NORTH 77.0
END DESCRIPTION:
XS GIS Cut Line= 3
      3762145.72     10135045.83      3762321.99     10134396.01
      3762089.71     10133905.21
#Sta/Elev= 30
  4326.7  246.63  4487.1  243.51  4509.8  243.98  4544.5  242.53  4624.1  241.71
  4642.5     240  4658.8  240.88  4670.7  240.38  4771.5  237.58  4847.5  238.37
  4906.8     237  4906.9     237  4953.3  237.43  4961.8   235.3    4967  235.52
  4984.4  230.71  4992.3   225.3  4997.3   225.3    5000  228.63  5005.5  228.63
  5016.2  233.96  5021.7  232.42  5027.6   236.9  5293.1  242.12  5381.6  242.72
  5396.8  241.27  5403.8  241.35  5450.5     245  5481.2  245.46    5543  248.21
#Mann= 8 ,-1 , 0
  4326.7     .11       0  4670.7     .17       0  4771.5     .15       0
  4906.8     .17       0  4906.9     .15       0  4953.3     .09       0
  5027.6     .15       0  5450.5     .11       0
#XS Ineff= 2 , 0
       0  4673.6  240.44               0
Permanent Ineff=
       F       F
Bank Sta=4953.3,5027.6
XS Rating Curve= 0 ,0
Exp/Cntr=0.3,0.1

Type RM Length L Ch R = 1 ,38000   ,500,500,500
BEGIN DESCRIPTION:
STEWART CREEK NORTH 76.0
END DESCRIPTION:
XS GIS Cut Line= 3
      3762577.42     10135183.36      3762737.89     10134588.46
      3762788.08     10133821.87
#Sta/Elev= 30
       0  244.49   126.7  243.28     179   241.6   240.6  241.22   288.4  239.79
   344.2  238.77   437.4   239.9   448.1  238.64   458.1  239.64   482.8  238.37
   509.9  239.76   582.4  236.62   592.2  234.43   597.4  234.36   603.1   228.9
   612.2  225.82   623.6  226.32   633.6  231.15   643.6  233.92   653.6  235.57
   773.9  235.67   783.9  234.89   793.9  232.84     814  231.92   842.1  235.05
   884.1  234.51   914.2  235.93   993.8  236.43    1275   241.7  1384.4  244.51
#Mann= 5 ,-1 , 0
       0     .11       0   288.4     .17       0   582.4     .09       0
   653.6     .17       0   793.9     .11       0
Bank Sta=582.4,653.6
XS Rating Curve= 0 ,0
Exp/Cntr=0.3,0.1

Type RM Length L Ch R = 1 ,37500   ,500,500,500
BEGIN DESCRIPTION:
STEWART CREEK NORTH 75.0
END DESCRIPTION:
XS GIS Cut Line= 3
      3762945.47     10135200.72       3763075.9     10134679.97
      3763467.85     10134161.07
#Sta/Elev= 30
       0  242.97    61.5  243.36    82.1  241.32   110.3  240.63   185.2  239.79
   205.8  240.47     239  239.25   370.8  236.82     412  234.42   422.3  233.41
   432.6  230.94     445  232.21   453.2  233.99   463.5  234.36   494.5  234.89
   504.8  233.21   515.1  231.37   522.3  228.72   527.4  225.28   533.7  222.56
     545   223.3   559.6  232.12   573.1  234.09   601.3   234.4   651.2  234.45
   865.6  235.86   930.1  237.38   994.6  239.72  1123.6  247.84  1187.1   252.7
#Mann= 6 ,-1 , 0
       0     .11       0     239     .17       0   504.8     .09       0
   559.6     .15       0   601.3     .17       0   651.2     .11       0
Bank Sta=504.8,559.6
XS Rating Curve= 0 ,0
Exp/Cntr=0.3,0.1

Type RM Length L Ch R = 1 ,37000   ,500,500,500
BEGIN DESCRIPTION:
STEWART CREEK NORTH 74.0
END DESCRIPTION:
XS GIS Cut Line= 3
      3763139.63     10135163.03       3763420.9     10134901.17
       3763725.6     10134347.01
#Sta/Elev= 30
  4615.7  241.68  4686.5  242.11    4708  240.07  4806.7  238.31  4842.4  235.75
  4849.2  237.07  4877.5  237.71  4927.4  235.98  4955.2  231.35  4962.6  228.51
  4969.4  227.45  4983.6  227.01  4990.9  224.92  4996.4  220.53  5001.7     220
  5008.1     220  5011.5  222.61    5021  227.79  5034.9  230.91  5057.2   233.5
  5108.2  230.79  5124.3  232.95  5200.7  232.95  5217.1  233.38  5276.8  231.85
  5308.2  232.89  5410.9  237.85  5445.4  240.29  5483.3  241.55  5632.4   251.4
#Mann= 4 ,-1 , 0
  4615.7     .11       0  4955.2     .07       0  5034.9     .15       0
  5200.7     .11       0
Bank Sta=4955.2,5034.9
XS Rating Curve= 0 ,0
Exp/Cntr=0.3,0.1

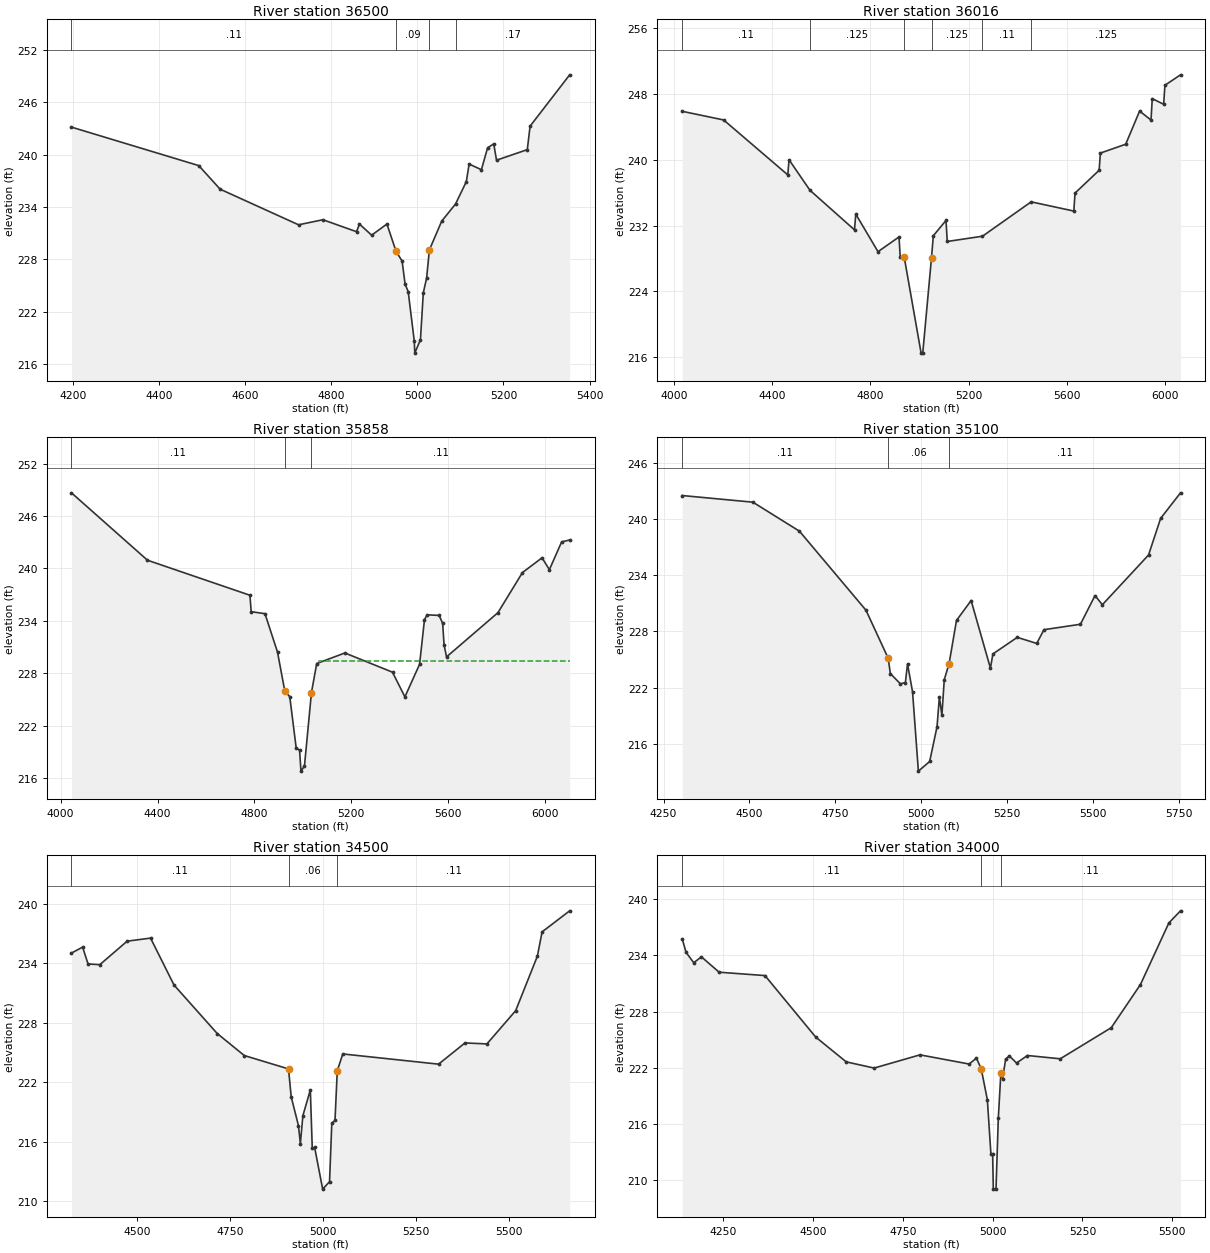
Type RM Length L Ch R = 1 ,36500   ,484,484,484
BEGIN DESCRIPTION:
STEWART CREEK NORTH 73.0
END DESCRIPTION:
XS GIS Cut Line= 4
      3763157.04     10135310.58      3763647.45     10135163.02
      3763859.31     10134962.12       3764129.2     10134733.35
#Sta/Elev= 30
  4195.9  243.16  4491.8  238.75  4541.4  236.05  4723.7  231.97  4780.3  232.55
  4858.4  231.18  4865.3  232.05  4893.6  230.78  4929.1  232.06  4950.2  228.94
  4964.4  227.81  4971.3  225.17  4978.5  224.32  4992.7  218.63  4993.8  217.27
    5007  218.81  5013.6  224.17  5021.3  225.87  5027.8   229.1  5056.4  232.39
  5088.6  234.36  5113.6  236.91  5120.1  238.93  5148.7  238.28    5163  240.79
  5177.3  241.24  5183.8  239.37  5255.3  240.58  5261.8  243.27  5353.8  249.15
#Mann= 4 ,-1 , 0
  4195.9     .11       0  4950.2     .09       0  5027.8     .15       0
  5088.6     .17       0
Bank Sta=4950.2,5027.8
XS Rating Curve= 0 ,0
Exp/Cntr=0.3,0.1

Type RM Length L Ch R = 1 ,36016   ,158,158,158
BEGIN DESCRIPTION:
STEWART CREEK NORTH 72.0
END DESCRIPTION:
XS GIS Cut Line= 3
      3763050.48     10135454.01      3764010.26     10135347.28
      3765052.29     10135143.34
#Sta/Elev= 30
  4034.3  245.91  4202.7  244.86  4463.7  238.18  4468.7  240.02  4553.9  236.31
  4735.2  231.49  4740.3  233.41  4830.8  228.84  4916.3  230.63  4921.3  228.14
  4937.2  228.22  5006.2   216.5  5012.9   216.5  5048.5  228.11    5056  230.78
  5107.5  232.64  5112.6  230.08    5256  230.72    5454   234.9  5627.6  233.78
  5632.7  235.97  5730.7  238.74  5735.7  240.83  5838.8  241.91  5895.4  245.94
  5941.8  244.85  5946.9  247.45  5993.3  246.77  5998.4  249.08  6061.8  250.35
#Mann= 6 ,-1 , 0
  4034.3     .11       0  4553.9    .125       0  4937.2     .09       0
  5048.5    .125       0    5256     .11       0    5454    .125       0
Bank Sta=4937.2,5048.5
XS Rating Curve= 0 ,0
Exp/Cntr=0.3,0.1

Type RM Length L Ch R = 1 ,35858   ,758,758,758
BEGIN DESCRIPTION:
STEWART CREEK NORTH 71.0
END DESCRIPTION:
XS GIS Cut Line= 3
      3763097.85     10135653.32      3764041.18      10135501.9
      3765130.69     10135337.84
#Sta/Elev= 30
  4044.6  248.65  4358.6  240.93  4781.6  236.92  4786.7  235.04  4843.6  234.81
  4895.4  230.41  4925.7  225.92    4946  225.31  4972.5  219.44  4986.5  219.17
  4992.3  216.78  5006.7  217.36  5035.6  225.78  5057.3   229.1  5173.5  230.31
  5370.3  228.11  5421.4  225.28    5482  229.01  5502.3  234.13  5513.3  234.68
  5562.9  234.61  5577.3   233.7  5583.2  231.24  5593.3  229.86  5805.7  234.93
  5906.8  239.52  5987.7  241.21    6018  239.85  6068.6  243.03  6101.8  243.25
#Mann= 3 , 0 , 0
  4044.6     .11       0  4925.7     .06       0  5035.6     .11       0
#XS Ineff= 2 , 0
       0                  5067.4       0  229.35
Permanent Ineff=
       F       F
Bank Sta=4925.7,5035.6
XS Rating Curve= 0 ,0
Exp/Cntr=0.3,0.1

Type RM Length L Ch R = 1 ,35100   ,600,600,600
BEGIN DESCRIPTION:
STEWART CREEK NORTH 70.0
END DESCRIPTION:
XS GIS Cut Line= 3
      3764066.28     10136307.67      3764622.29     10135890.03
       3765171.2     10135372.95
#Sta/Elev= 30
  4304.6  242.54    4510  241.83  4645.4  238.73  4839.1  230.27  4903.7  225.13
  4909.9   223.5  4939.1   222.4  4953.7  222.54  4959.9  224.53  4974.5  221.55
  4991.5  213.06  5024.3  214.09  5045.8  217.82  5052.6     221  5059.9  219.03
  5066.8  222.84  5080.9  224.57  5102.4  229.18  5144.9  231.31  5201.1  224.08
  5208.4   225.6  5279.2  227.37  5335.8  226.72  5356.9  228.19  5462.9  228.77
  5505.4  231.84  5526.8  230.86  5661.1  236.18  5696.3   240.1  5754.1  242.83
#Mann= 3 , 0 , 0
  4304.6     .11       0  4903.7     .06       0  5080.9     .11       0
#XS Ineff= 2 , 0
       0                  5144.9       0  231.31
Permanent Ineff=
       F       F
Bank Sta=4903.7,5080.9
XS Rating Curve= 0 ,0
Exp/Cntr=0.3,0.1

Type RM Length L Ch R = 1 ,34500   ,500,500,500
BEGIN DESCRIPTION:
STEWART CREEK NORTH 69.0
END DESCRIPTION:
XS GIS Cut Line= 3
      3764823.28     10136773.62      3765032.05     10136129.72
      3765419.39      10135590.4
#Sta/Elev= 30
  4323.1  235.02  4353.1  235.62  4367.8  233.92  4399.4  233.85    4473  236.22
    4536  236.53  4599.1   231.8  4715.4  226.91  4788.3  224.69  4907.3  223.34
  4914.5  220.53    4934  217.63  4939.2  215.81    4946  218.63    4966  221.22
  4971.2  215.35  4977.6  215.42  4999.2  211.22  5017.7  211.97  5023.8  217.87
  5032.4  218.14  5038.5  223.15  5053.3  224.85  5311.1  223.82  5382.3  225.96
  5441.2  225.86  5518.6  229.21    5577   234.7  5589.8  237.16    5664  239.28
#Mann= 3 , 0 , 0
  4323.1     .11       0  4907.3     .06       0  5038.5     .11       0
Bank Sta=4907.3,5038.5
XS Rating Curve= 0 ,0
Exp/Cntr=0.3,0.1

Type RM Length L Ch R = 1 ,34000   ,500,500,500
BEGIN DESCRIPTION:
STEWART CREEK NORTH 68.0
END DESCRIPTION:
XS GIS Cut Line= 4
      3764856.22     10136794.61      3765358.02     10136244.73
      3765378.61     10136126.64      3765467.85      10135611.1
#Sta/Elev= 30
  4135.7  235.74  4146.4  234.32  4167.6  233.22    4189  233.85  4238.3  232.21
    4366  231.85  4507.2  225.29  4592.3  222.64    4670  221.98  4797.7  223.39
  4934.6  222.41  4954.9  223.04  4968.3  221.89  4985.3   218.6  4995.2  212.83
    5000  212.83  5001.9  209.06  5009.4  209.06  5015.8  216.62  5022.9  221.44
  5027.9  220.86  5036.1  222.91  5046.2  223.29  5066.5  222.52    5097  223.32
  5188.3  222.97  5330.4  226.29  5411.6  230.89  5490.8  237.47  5523.2  238.76
#Mann= 3 , 0 , 0
  4135.7     .11       0  4968.3     .06       0  5022.9     .11       0
Bank Sta=4968.3,5022.9
XS Rating Curve= 0 ,0
Exp/Cntr=0.3,0.1