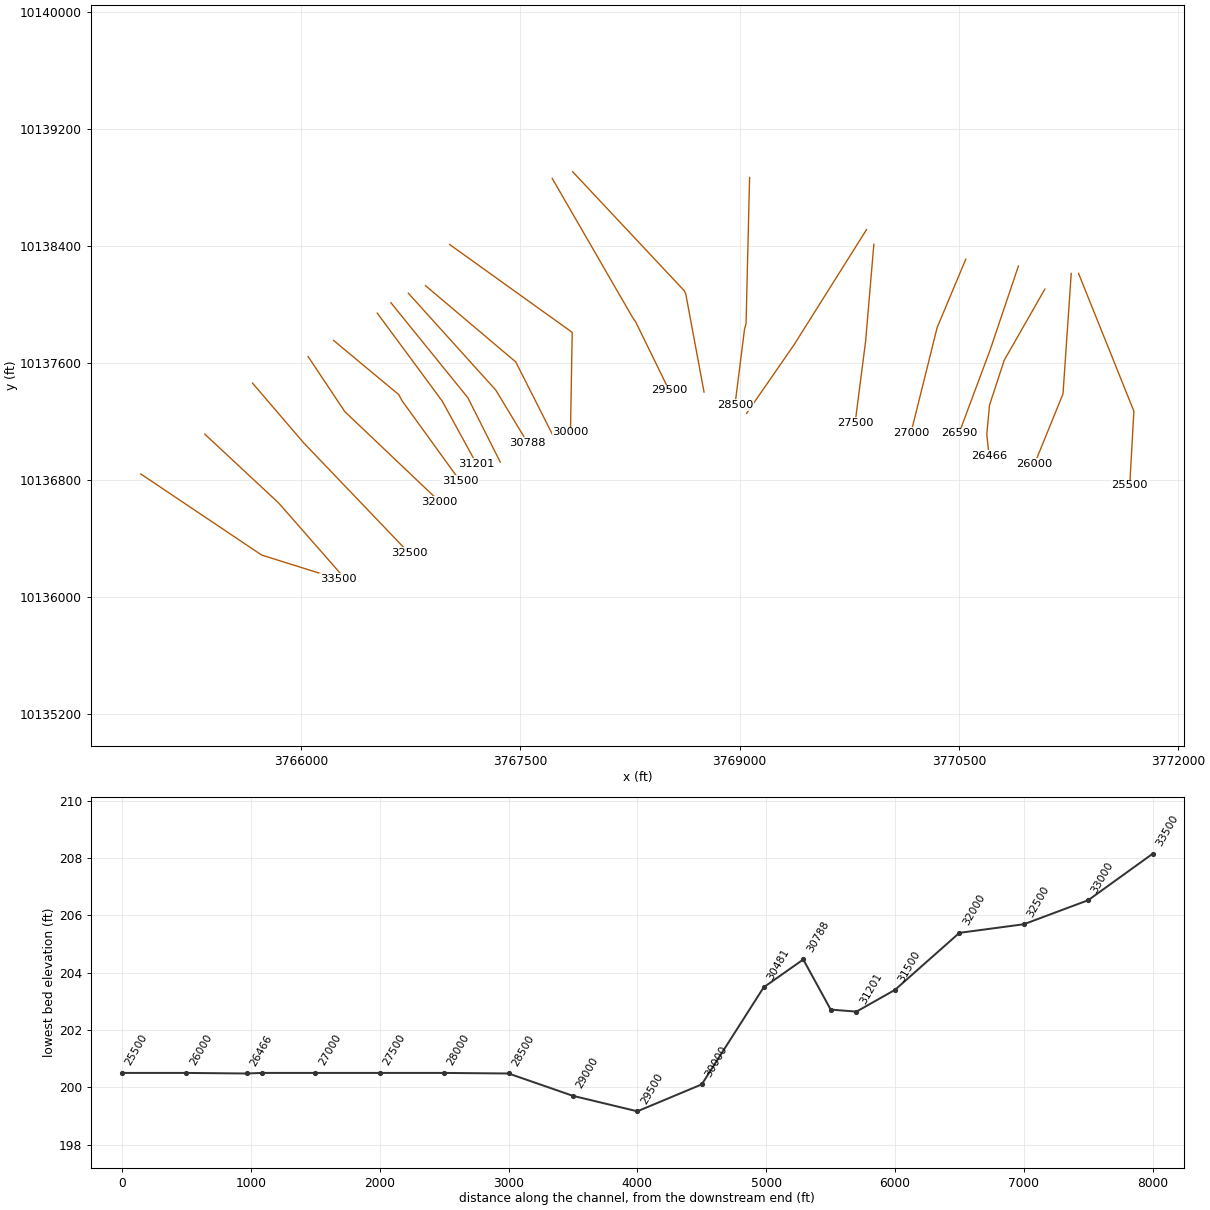
HEC-RAS study STEWART CREEK NORTH.prj: STEWART CREEK NORTH Base Level Engineering

--- STEWART CREEK NORTH.g01 (geometry) --- (continued)

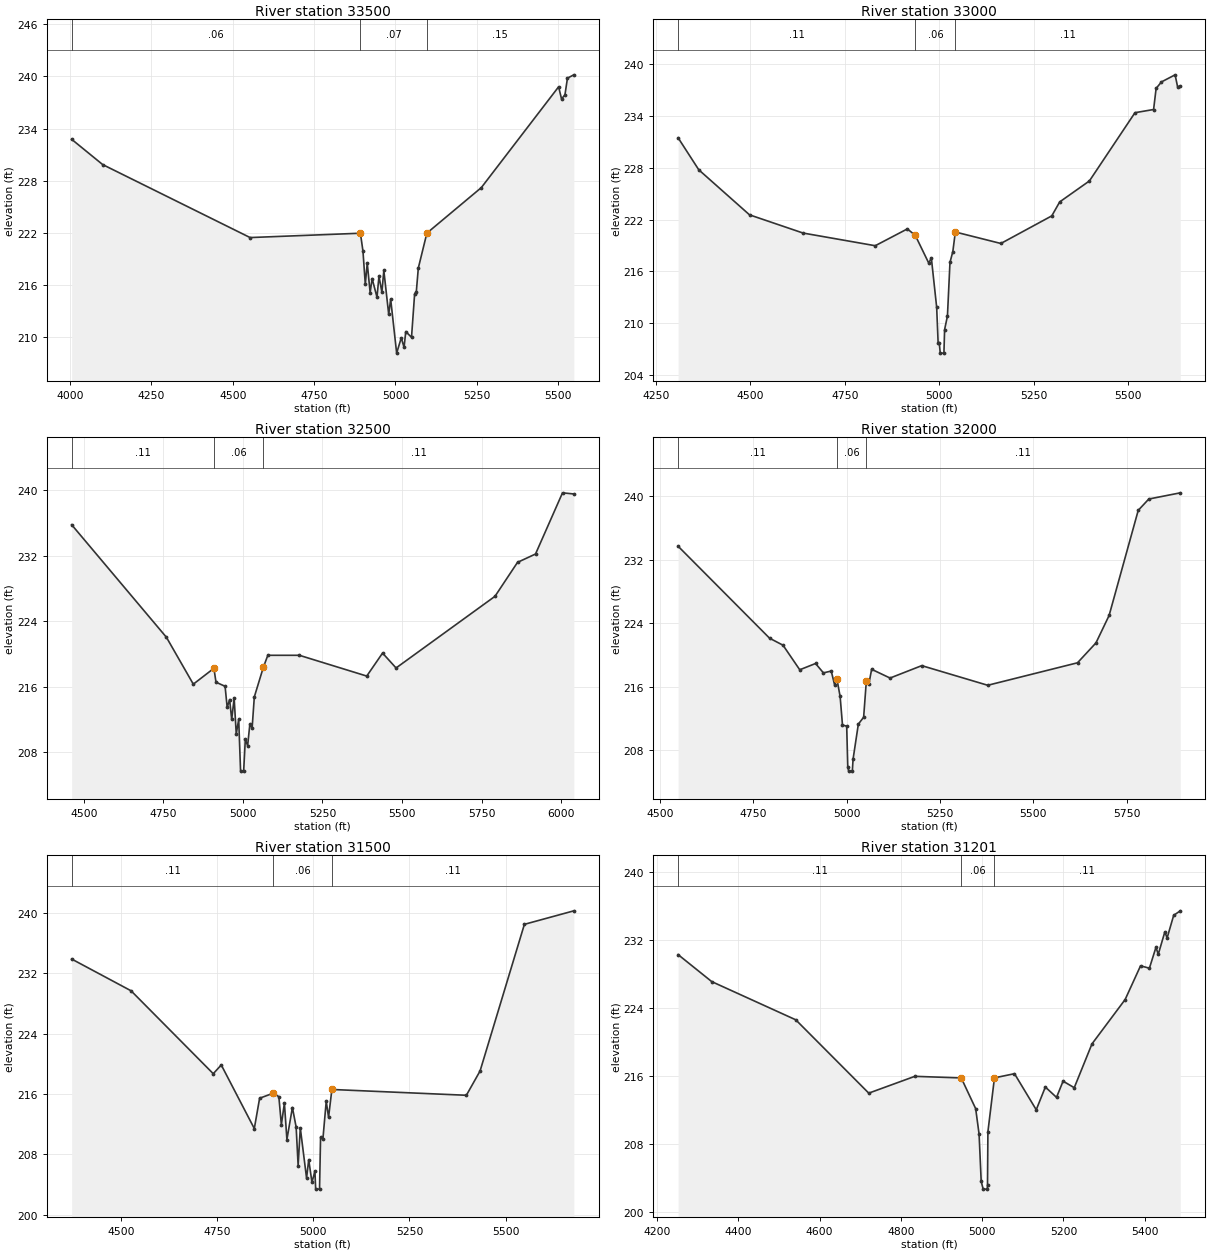
Type RM Length L Ch R = 1 ,33500   ,500,500,500
BEGIN DESCRIPTION:
STEWART CREEK NORTH 67.0
END DESCRIPTION:
XS GIS Cut Line= 3
      3764904.13     10136839.55      3765730.73     10136284.98
      3766254.03     10136120.96
#Sta/Elev= 30
  4004.6  232.76    4100  229.85  4553.2  221.45  4892.3  221.95  4900.2  219.87
  4907.3  216.07  4913.3  218.51  4922.2  215.12  4928.3  216.73  4943.3  214.58
  4949.3     217  4958.3  215.17  4964.3  217.66  4979.3   212.6  4985.3  214.37
  5003.7  208.15  5017.9  209.91  5026.5  208.82  5031.7  210.63  5049.4  209.97
  5058.9  214.94  5064.2  215.24  5070.3  217.94  5096.6  221.96    5264   227.2
  5501.6   238.8  5510.5  237.42    5521  237.86  5528.8   239.8  5548.4  240.18
#Mann= 3 , 0 , 0
  4004.6     .06       0  4892.3     .07       0  5096.6     .15       0
#XS Ineff= 2 , 0
       0                    5129       0  222.82
Permanent Ineff=
       F       F
Bank Sta=4892.3,5096.6
XS Rating Curve= 0 ,0
Exp/Cntr=0.3,0.1

Type RM Length L Ch R = 1 ,33000   ,500,500,500
BEGIN DESCRIPTION:
STEWART CREEK NORTH 66.0
END DESCRIPTION:
XS GIS Cut Line= 3
      3765341.51     10137112.11      3765847.24     10136640.81
      3766267.84     10136161.08
#Sta/Elev= 30
  4308.7  231.49  4363.4  227.78  4497.7  222.56  4639.4  220.45  4830.5  218.98
  4915.5  220.93  4936.5  220.18  4972.1  216.97    4979  217.56  4993.1  211.84
    4997  207.67    5000  207.67  5002.6  206.53  5012.3  206.53  5014.1  209.26
  5021.6  210.83  5028.3  217.04  5035.9  218.31  5042.5  220.57    5163  219.24
  5297.8  222.44  5318.8  224.06  5397.4  226.49    5518   234.4  5567.3  234.77
    5574  237.22  5588.2  237.97  5624.2  238.79  5630.9  237.39    5638  237.49
#Mann= 3 , 0 , 0
  4308.7     .11       0  4936.5     .06       0  5042.5     .11       0
Bank Sta=4936.5,5042.5
XS Rating Curve= 0 ,0
Exp/Cntr=0.3,0.1

Type RM Length L Ch R = 1 ,32500   ,500,500,500
BEGIN DESCRIPTION:
STEWART CREEK NORTH 65.0
END DESCRIPTION:
XS GIS Cut Line= 3
      3765667.86     10137461.06      3766018.33     10137052.09
      3766737.41     10136300.33
#Sta/Elev= 30
  4461.4  235.81  4759.4  222.05  4843.9  216.32  4908.7  218.26  4915.2  216.56
  4943.8  216.06  4950.4  213.47    4958  214.44  4964.6  212.02  4972.3  214.61
  4978.9  210.23  4986.6  212.02  4992.5  205.69  5002.2  205.69  5007.4  209.57
  5014.7   208.8  5021.6   211.4  5028.8  210.94  5035.7  214.76    5064  218.37
  5078.2  219.85  5177.3  219.85  5389.2  217.31  5438.9  220.12  5481.4   218.3
  5792.4  227.06  5863.2  231.21  5919.8  232.23  6004.7  239.71  6040.3  239.57
#Mann= 3 , 0 , 0
  4461.4     .11       0  4908.7     .06       0    5064     .11       0
Bank Sta=4908.7,5064
XS Rating Curve= 0 ,0
Exp/Cntr=0.3,0.1

Type RM Length L Ch R = 1 ,32000   ,500,500,500
BEGIN DESCRIPTION:
STEWART CREEK NORTH 64.0
END DESCRIPTION:
XS GIS Cut Line= 3
      3766048.46     10137642.28      3766298.97     10137266.41
       3766947.1      10136650.8
#Sta/Elev= 30
  4548.3  233.68  4793.4  222.11  4829.4  221.23  4874.2  218.14  4916.6  218.93
  4937.6  217.75  4958.6  217.98  4967.7  216.22  4973.7     217  4982.4  214.78
  4988.7   211.2    5000  211.04  5002.9   205.9  5005.3  205.39  5015.1  205.39
  5017.1   206.9  5031.2   211.3  5045.4  212.17  5052.7  216.76  5059.6   216.4
  5066.8   218.2  5116.2   217.1  5201.1  218.66  5377.9  216.19  5618.5  219.02
  5667.9  221.52  5703.1  224.97  5781.2   238.2  5809.5  239.62  5893.9   240.4
#Mann= 3 , 0 , 0
  4548.3     .11       0  4973.7     .06       0  5052.7     .11       0
Bank Sta=4973.7,5052.7
XS Rating Curve= 0 ,0
Exp/Cntr=0.3,0.1

Type RM Length L Ch R = 1 ,31500   ,299,299,299
BEGIN DESCRIPTION:
STEWART CREEK NORTH 63.0
END DESCRIPTION:
XS GIS Cut Line= 4
      3766222.15     10137753.17      3766667.98     10137382.69
      3766690.83     10137340.33      3767087.86      10136791.6
#Sta/Elev= 30
  4372.2   233.9  4526.6  229.69  4740.2   218.7    4761  219.86  4846.9  211.43
  4860.7  215.45  4896.4  216.12  4910.7  215.65  4917.2  211.93  4925.1   214.8
  4931.6  209.97  4945.9  214.22  4955.6  211.63  4960.8  206.52  4966.4  211.52
  4982.7  204.86  4988.3  207.31  4996.7   204.3  5004.4  205.78  5006.4   203.4
  5016.4   203.4  5019.1  210.25  5025.2  210.06  5033.8  215.04  5039.9  212.93
  5048.5  216.61    5398  215.84  5433.6  219.06  5548.8   238.5  5677.3  240.29
#Mann= 3 , 0 , 0
  4372.2     .11       0  4896.4     .06       0  5048.5     .11       0
Bank Sta=4896.4,5048.5
XS Rating Curve= 0 ,0
Exp/Cntr=0.3,0.1

Type RM Length L Ch R = 1 ,31201   ,200,200,200
BEGIN DESCRIPTION:
Mapping XS 4e96840b
END DESCRIPTION:
XS GIS Cut Line= 3
      3766521.52     10137939.56      3766965.74     10137337.71
      3767199.78     10136910.22
#Sta/Elev= 30
  4252.1  230.27  4334.8  227.09  4541.5  222.59  4721.1  213.95  4834.4  215.93
  4948.6  215.74  4984.1  212.12  4992.5  209.12  4997.7  203.54  5002.6  202.64
  5012.7  202.64  5013.2  203.14  5014.2   209.4  5030.3  215.75  5079.6  216.24
  5133.1  211.99  5155.5  214.67    5183  213.45  5199.1  215.36  5226.6  214.59
  5270.2  219.75  5351.8  224.98  5389.7  228.95  5411.5  228.67  5427.6  231.13
  5433.3  230.31  5449.4  232.94  5455.1  232.24  5471.2   234.9  5487.5  235.43
#Mann= 3 , 0 , 0
  4252.1     .11       0  4948.6     .06       0  5030.3     .11       0
Bank Sta=4948.6,5030.3
XS Rating Curve= 0 ,0
Exp/Cntr=0.3,0.1

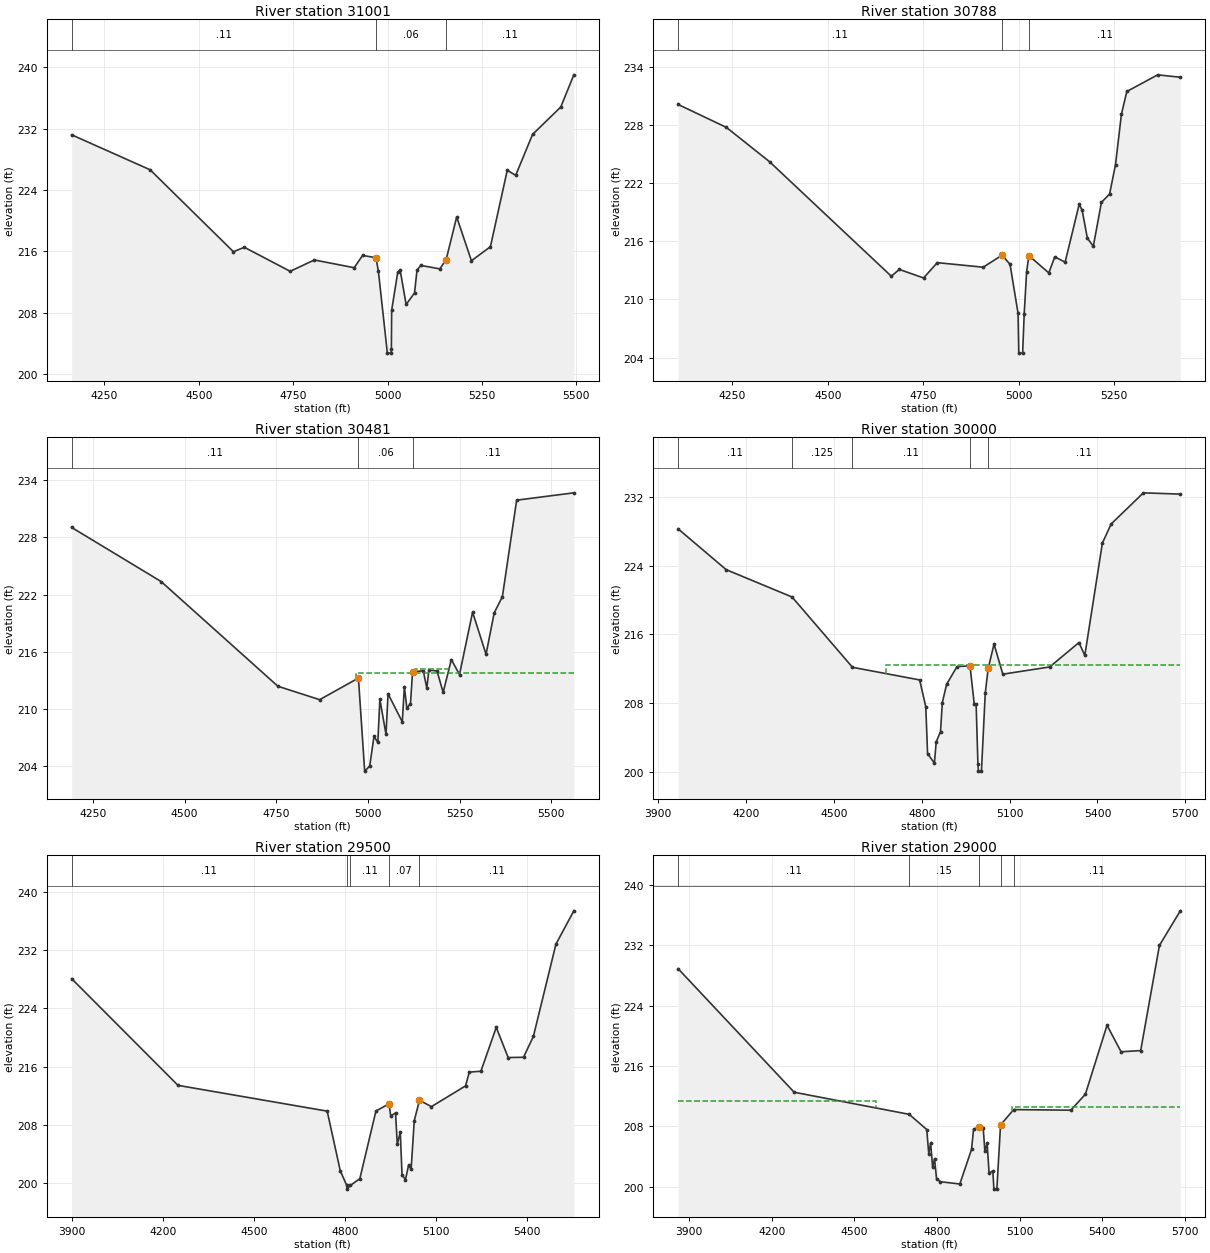
Type RM Length L Ch R = 1 ,31001   ,213,213,213
BEGIN DESCRIPTION:
STEWART CREEK NORTH 62.0
END DESCRIPTION:
XS GIS Cut Line= 3
      3766614.57     10138010.77      3767141.15     10137360.68
      3767362.88     10136920.14
#Sta/Elev= 30
  4163.4  231.21  4371.3  226.64  4591.9  215.94  4620.6  216.53  4742.1  213.39
    4806  214.87  4911.6  213.86  4933.9  215.47  4969.1  215.16  4975.6  213.43
  4999.4  202.71  5009.5  202.71    5010  203.21  5010.8  208.31  5026.8  213.24
  5033.2  213.58  5049.1  209.06  5071.4  210.57  5077.9  213.55  5088.1  214.16
  5138.4  213.71  5155.1  214.92    5183  220.49    5222  214.77  5272.3   216.6
  5316.9  226.58  5339.2  225.92  5383.9  231.26  5458.6  234.84  5493.2  239.04
#Mann= 3 , 0 , 0
  4163.4     .11       0  4969.1     .06       0  5155.1     .11       0
#XS Ineff= 2 , 0
       0  4620.6  216.53    5183       0  220.49
Permanent Ineff=
       F       F
Bank Sta=4969.1,5155.1
XS Rating Curve= 0 ,0
Exp/Cntr=0.3,0.1

Type RM Length L Ch R = 1 ,30788   ,307,307,307
BEGIN DESCRIPTION:
Mapping XS 63247e3c
END DESCRIPTION:
XS GIS Cut Line= 3
      3766734.07      10138075.7      3767331.93     10137413.31
      3767550.86     10137051.14
#Sta/Elev= 30
  4107.7  230.13  4234.3  227.76  4347.2  224.22  4666.2   212.4  4687.2   213.1
  4750.7  212.22  4786.6   213.8  4906.9  213.33  4956.2  214.57  4977.2  213.63
  4998.1  208.59  5000.1  204.46  5010.2  204.46  5014.3  208.54  5020.6  212.84
  5026.5  214.53  5078.8  212.74  5094.3   214.4  5121.5  213.85  5158.4  219.84
  5166.2  219.19  5179.7  216.33  5195.3  215.49  5216.6  220.02    5238  220.89
  5253.5  223.93    5269  229.13  5283.1  231.47    5364  233.19  5423.2  232.94
#Mann= 3 ,-1 , 0
  4107.7     .11       0  4956.2     .06       0  5026.5     .11       0
#XS Ineff= 2 , 0
       0                  5158.4       0  219.84
Permanent Ineff=
       F       F
Bank Sta=4956.2,5026.5
XS Rating Curve= 0 ,0
Exp/Cntr=0.3,0.1

Type RM Length L Ch R = 1 ,30481   ,481,481,481
BEGIN DESCRIPTION:
STEWART CREEK NORTH 61.0
END DESCRIPTION:
XS GIS Cut Line= 3
      3766851.25     10138127.57      3767468.52     10137605.73
      3767722.14     10137104.65
#Sta/Elev= 30
  4191.7  229.04  4435.7  223.37  4754.3  212.39  4868.2  210.98    4974  213.25
    4991  203.49  5004.8  204.02  5016.4  207.13  5026.9  206.51  5032.5  211.01
  5049.2  207.35  5054.8   211.6  5093.7  208.65  5099.3  212.35  5106.1  210.09
    5116  210.57  5121.6  213.91  5150.9  214.01  5160.6  212.18  5166.2  214.09
  5188.4  213.99  5205.1  211.74  5227.4  215.19  5249.7  213.62  5285.4  220.16
  5322.1  215.74  5344.4  220.09  5366.7  221.78  5405.6   231.9  5561.6  232.67
#Mann= 3 ,-1 , 0
  4191.7     .11       0    4974     .06       0  5121.6     .11       0
#XS Ineff= 3 ,-1
  4967.4  4676.2  213.81  5128.5  5227.4   214.2  5227.4  5285.4  215.19
Permanent Ineff=
       F       F       F
Bank Sta=4974,5121.6
XS Rating Curve= 0 ,0
Exp/Cntr=0.3,0.1

Type RM Length L Ch R = 1 ,30000   ,500,500,500
BEGIN DESCRIPTION:
STEWART CREEK NORTH 60.0
END DESCRIPTION:
XS GIS Cut Line= 3
      3767015.96     10138409.18      3767854.73     10137807.94
      3767842.74     10137125.04
#Sta/Elev= 30
    3968  228.29  4132.1  223.54  4357.1  220.36  4563.5  212.18  4792.9  210.71
  4813.8  207.59  4819.9  202.14  4843.2  201.03  4849.4   203.5  4864.1   204.7
  4870.3  208.08    4885  210.21  4920.6  212.27  4964.8  212.35  4979.2  207.93
  4985.7  207.91  4991.9  200.89  4993.8   200.1  5003.9   200.1  5016.9  209.18
  5026.9  212.05  5046.9  214.88  5076.9  211.38  5236.9  212.22  5336.9  215.06
  5356.9  213.56  5416.9  226.64  5446.9  228.86    5557  232.48    5683  232.33
#Mann= 5 ,-1 , 0
    3968     .11       0  4357.1    .125       0  4563.5     .11       0
  4964.8     .06       0  5026.9     .11       0
#XS Ineff= 3 ,-1
  4964.8  4677.4  212.35  4677.4  4548.6  212.45  5046.9  5376.9  214.88
Permanent Ineff=
       F       F       F
Bank Sta=4964.8,5026.9
XS Rating Curve= 0 ,0
Exp/Cntr=0.3,0.1

Type RM Length L Ch R = 1 ,29500   ,500,500,500
BEGIN DESCRIPTION:
STEWART CREEK NORTH 59.0
END DESCRIPTION:
XS GIS Cut Line= 4
      3767717.87     10138861.05      3768269.19     10137907.34
      3768287.71     10137881.88      3768517.84     10137411.09
#Sta/Elev= 30
  3898.4  228.06  4249.4  213.41  4741.6  209.87  4784.8  201.68  4806.2  199.66
  4806.7  199.16  4817.9  199.66  4849.4   200.6  4902.5  209.89  4945.5  210.87
  4951.3  209.21  4967.1  209.63  4972.9  205.32  4982.8  206.98  4988.6  201.11
    5000  200.47  5010.1  202.44  5018.6  201.89  5028.9  208.55  5046.1  211.36
  5085.6  210.49  5198.2  213.34  5210.5  215.23  5248.8  215.35  5299.5  221.37
  5338.8  217.23  5389.4  217.27    5422  220.13  5496.5  232.81  5555.5  237.38
#Mann= 5 ,-1 , 0
  3898.4     .11       0  4806.2     .09       0  4817.9     .11       0
  4945.5     .07       0  5046.1     .11       0
#XS Ineff= 2 ,-1
                          4945.5  4592.4  210.87
Permanent Ineff=
       F       F
Bank Sta=4945.5,5046.1
XS Rating Curve= 0 ,0
Exp/Cntr=0.3,0.1

Type RM Length L Ch R = 1 ,29000   ,500,500,500
BEGIN DESCRIPTION:
STEWART CREEK NORTH 58.0
END DESCRIPTION:
XS GIS Cut Line= 4
       3767857.7     10138906.42      3768621.04     10138092.82
      3768631.31     10138071.16      3768756.35      10137399.7
#Sta/Elev= 30
  3860.4  228.91  4281.6  212.54  4699.2  209.61  4762.7   207.6    4770  204.42
  4776.8   205.8  4784.1  202.58    4791  203.73  4798.3  201.08  4812.5  200.68
  4882.8  200.38  4925.3  204.96  4932.6  207.61  4953.7  207.96  4967.8  207.74
  4973.8   204.7  4981.9  205.77    4989  201.83  5002.6   202.1  5006.5   199.7
  5017.2   199.7  5030.6   208.2    5078  210.24  5285.8  210.16  5338.5  212.28
  5417.1  221.41    5468   217.9  5539.2  218.06  5607.3     232    5683  236.58
#Mann= 5 ,-1 , 0
  3860.4     .11       0  4699.2     .15       0  4953.7     .09       0
  5030.6     .15       0    5078     .11       0
#XS Ineff= 2 , 0
       0    4579  211.32  5071.3       0  210.57
Permanent Ineff=
       F       F
Bank Sta=4953.7,5030.6
XS Rating Curve= 0 ,0
Exp/Cntr=0.3,0.1

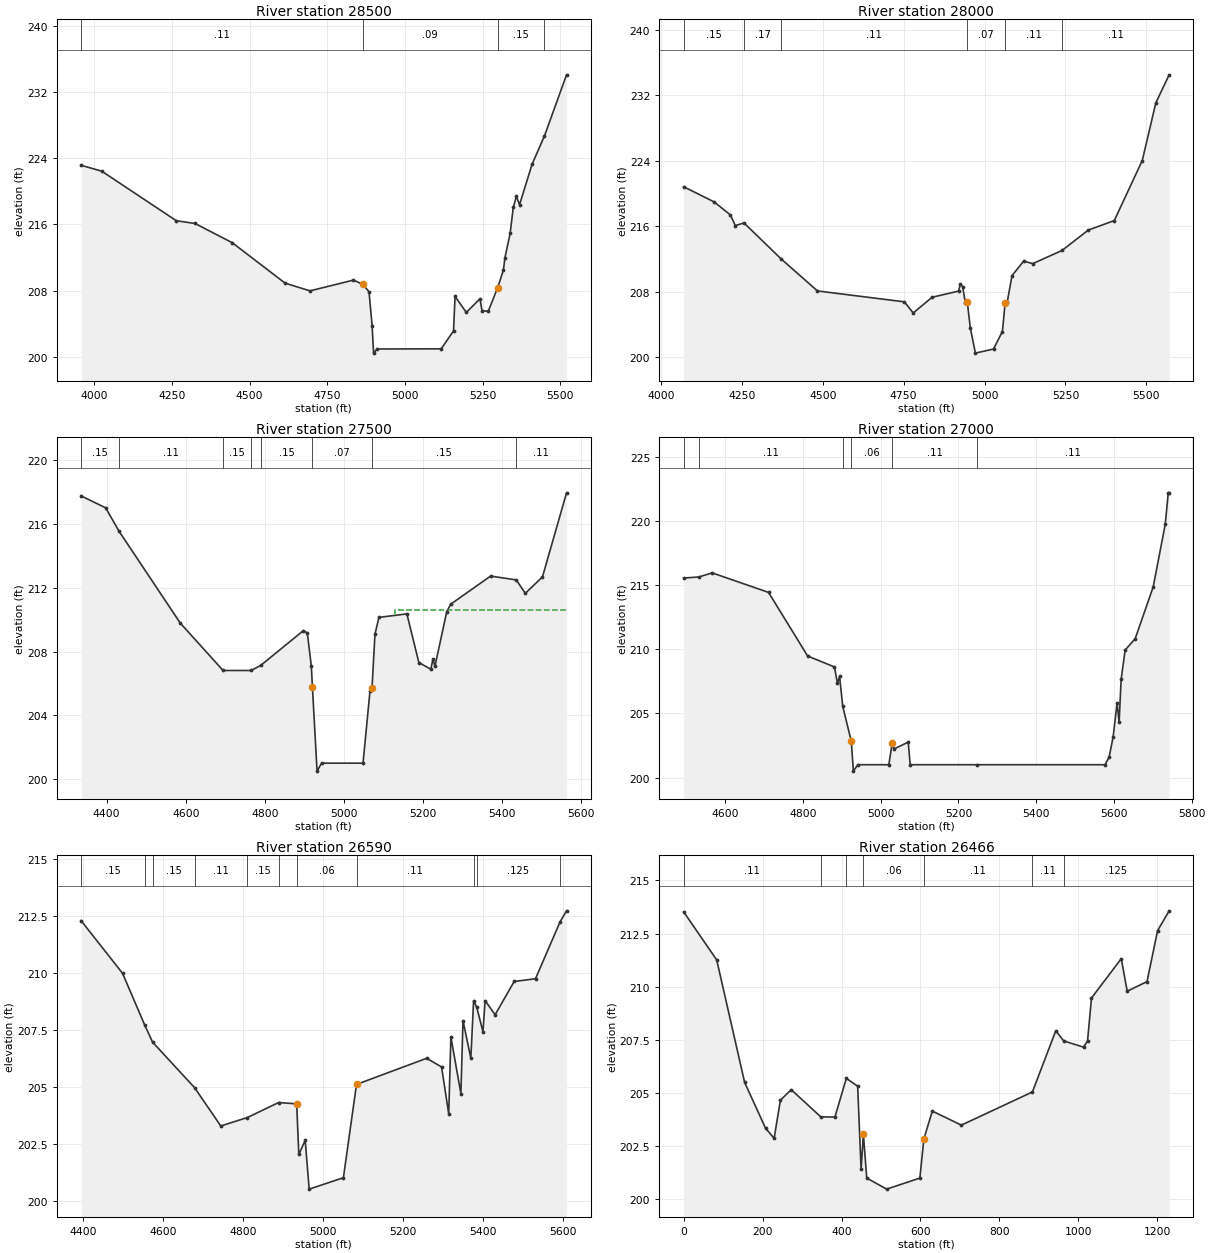
Type RM Length L Ch R = 1 ,28500   ,500,500,500
BEGIN DESCRIPTION:
STEWART CREEK NORTH 57.0
END DESCRIPTION:
XS GIS Cut Line= 4
      3769067.88     10138867.43      3769043.78     10137869.73
      3769032.95     10137827.08      3768967.85     10137311.07
#Sta/Elev= 30
    3958  223.14  4024.4  222.43  4264.5  216.45  4324.5  216.12  4444.5   213.8
  4614.6  208.92  4694.6  207.99  4834.6  209.29  4864.6  208.78  4884.6  207.88
  4894.6  203.75  4899.2  200.48  4910.5  200.98  5116.9     201  5156.4  203.16
  5161.4  207.32  5197.6  205.39  5241.7  207.04    5248  205.61  5268.1  205.52
  5298.4  208.36  5316.9  210.48    5322     212  5338.7  214.94  5348.8  218.06
  5358.8   219.4  5368.9  218.38  5409.2  223.26  5449.1  226.68  5520.1  234.05
#Mann= 4 ,-1 , 0
    3958     .11       0  4864.6     .09       0  5298.4     .15       0
  5449.1     .11       0
Bank Sta=4864.6,5298.4
XS Rating Curve= 0 ,0
Exp/Cntr=0.3,0.1

Type RM Length L Ch R = 1 ,28000   ,500,500,500
BEGIN DESCRIPTION:
STEWART CREEK NORTH 56.0
END DESCRIPTION:
XS GIS Cut Line= 3
      3769867.87     10138511.09      3769372.55     10137723.97
      3769047.72     10137254.61
#Sta/Elev= 30
    4070  220.81  4164.5  218.95  4214.3  217.37  4229.6  216.07  4256.5  216.39
  4371.5  211.99  4483.6  208.09  4752.4  206.76  4779.5   205.4    4838  207.32
  4919.6  208.07  4925.5  208.94  4932.5  208.61  4940.8  206.62  4946.7  206.76
  4956.1  203.58  4971.8   200.5  5027.8     201  5055.2  203.13    5064  206.67
  5070.1  206.69    5085  209.96  5120.8  211.72  5149.5  211.43  5239.6  213.03
  5320.8  215.52  5401.2  216.68  5487.7  224.01  5529.6  231.05  5570.8  234.47
#Mann= 6 ,-1 , 0
    4070     .15       0  4256.5     .17       0  4371.5     .11       0
  4946.7     .07       0    5064     .11       0  5239.6     .11       0
Bank Sta=4946.7,5064
XS Rating Curve= 0 ,0
Exp/Cntr=0.3,0.1

Type RM Length L Ch R = 1 ,27500   ,500,500,500
BEGIN DESCRIPTION:
STEWART CREEK NORTH 55.0
END DESCRIPTION:
XS GIS Cut Line= 3
      3769917.85     10138411.06      3769861.58     10137748.74
      3769789.82     10137190.74
#Sta/Elev= 30
  4335.3  217.76  4397.4  217.01  4431.1  215.55  4586.2  209.78  4694.3  206.81
  4765.3  206.81  4790.1  207.14  4897.3  209.31  4907.3  209.16  4917.4  207.09
 4920.23  205.75  4931.9   200.5  4943.4     201  5048.1     201  5065.8  205.55
  5070.9  205.74  5078.3  209.09  5088.4  210.14    5159  210.36  5189.2  207.31
  5219.5  206.89  5224.9  207.52  5229.9  207.07  5259.8   210.5  5269.9  210.97
  5370.7  212.73  5435.5  212.49  5458.4  211.65  5501.8  212.68  5562.6  217.95
#Mann= 8 ,-1 , 0
  4335.3     .15       0  4431.1     .11       0  4694.3     .15       0
  4765.3     .11       0  4790.1     .15       0 4920.23     .07       0
  5070.9     .15       0  5435.5     .11       0
#XS Ineff= 2 , 0
       0  4897.3  209.31  5128.7       0  210.58
Permanent Ineff=
       F       F
Bank Sta=4920.23,5070.9
XS Rating Curve= 0 ,0
Exp/Cntr=0.3,0.1

Type RM Length L Ch R = 1 ,27000   ,410,410,410
BEGIN DESCRIPTION:
STEWART CREEK NORTH 54.0
END DESCRIPTION:
XS GIS Cut Line= 3
      3770546.74     10138308.72      3770350.81     10137841.44
      3770171.76     10137121.26
#Sta/Elev= 30
  4493.3  215.55    4532  215.63  4566.7  215.95  4711.6  214.43  4812.2  209.47
  4881.1  208.62  4888.9  207.33  4894.3  207.89  4902.5  205.54  4924.5  202.82
  4929.8   200.5  4941.4     201    5021     201  5029.6  202.66  5034.7  202.23
  5070.9  202.76    5076     201  5248.5     201  5577.4     201  5587.7   201.6
    5598  203.16  5608.2  205.81  5613.4  204.31  5618.6  207.65  5628.9  209.94
  5654.7  210.82  5701.2  214.87    5732  219.73  5739.8  222.19  5742.1  222.19
#Mann= 6 ,-1 , 0
  4493.3     .17       0    4532     .11       0  4902.5     .15       0
  4924.5     .06       0  5029.6     .11       0  5248.5     .11       0
Bank Sta=4924.5,5029.6
XS Rating Curve= 0 ,0
Exp/Cntr=0.3,0.1

Type RM Length L Ch R = 1 ,26590   ,124,124,124
BEGIN DESCRIPTION:
STEWART CREEK NORTH 53.0
END DESCRIPTION:
XS GIS Cut Line= 3
      3770906.67      10138262.2      3770713.71     10137689.54
      3770500.53     10137118.32
#Sta/Elev= 30
  4395.7  212.28  4499.4  209.97  4554.6  207.71  4574.5  206.95  4679.6  204.95
  4745.1  203.27  4811.4  203.64  4889.8   204.3  4934.9  204.24  4940.2  202.02
  4956.2  202.64  4966.1   200.5  5051.7     201  5084.5 205.094  5259.9  206.24
  5297.2  205.86  5315.1   203.8  5320.5  207.18  5345.5  204.69  5350.8  207.89
  5370.4  206.24  5377.3  208.77  5385.2  208.48  5400.7   207.4  5406.1  208.77
  5431.1  208.15  5478.7  209.61  5532.1  209.73  5593.6  212.23  5609.7  212.71
#Mann= 11 ,-1 , 0
  4395.7     .15       0  4554.6     .11       0  4574.5     .15       0
  4679.6     .11       0  4811.4     .15       0  4889.8     .11       0
  4934.9     .06       0  5084.5     .11       0  5377.3     .11       0
  5385.2    .125       0  5593.6     .15       0
Bank Sta=4934.9,5084.5
XS Rating Curve= 0 ,0
Exp/Cntr=0.3,0.1

Type RM Length L Ch R = 1 ,26466   ,466,466,466
BEGIN DESCRIPTION:
Mapping XS 991fa303
END DESCRIPTION:
XS GIS Cut Line= 5
      3771087.33     10138103.78      3770809.39     10137617.39
       3770708.8     10137310.11      3770690.24      10137110.1
      3770705.89     10136964.61
#Sta/Elev= 30
       0  213.52    83.7  211.26   154.4   205.5   207.6  203.34   229.2  202.87
     245  204.66   272.4  205.16   347.3  203.88   383.2  203.87   412.1  205.69
   440.8  205.32   449.5  201.41   455.3  203.06   463.8     201   514.3  200.48
   598.4     201   608.5  202.84     630  204.15   703.6  203.49   883.5  205.05
   942.8  207.93   962.9  207.45  1013.1  207.16  1023.2  207.45  1033.2  209.47
  1108.7  211.32  1123.7  209.79  1173.9  210.24  1200.7  212.64    1230  213.57
#Mann= 7 ,-1 , 0
       0     .11       0   347.3    .125       0   412.1     .11       0
   455.3     .06       0   608.5     .11       0   883.5     .11       0
   962.9    .125       0
Bank Sta=455.3,608.5
XS Rating Curve= 0 ,0
Exp/Cntr=0.3,0.1

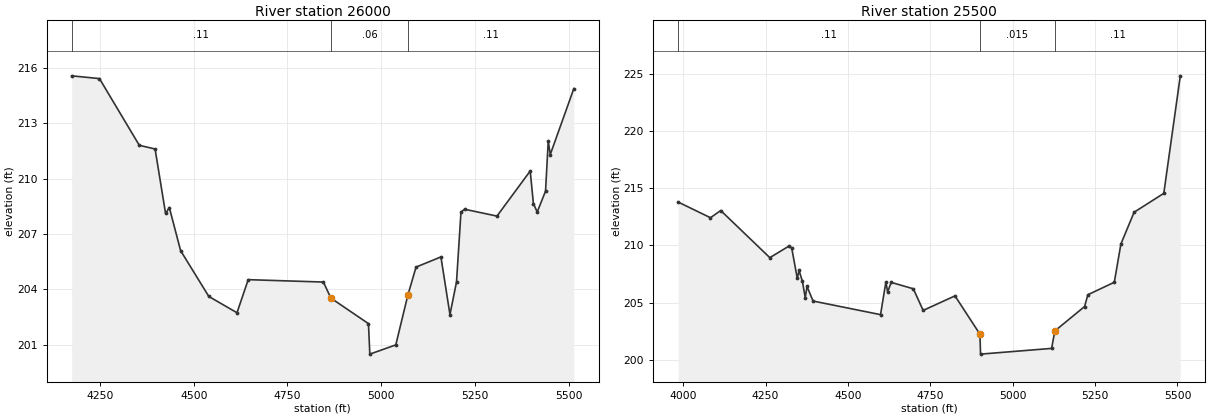
Type RM Length L Ch R = 1 ,26000   ,500,500,500
BEGIN DESCRIPTION:
STEWART CREEK NORTH 52.0
END DESCRIPTION:
XS GIS Cut Line= 3
      3771267.85     10138211.11      3771211.45     10137387.24
      3771017.86     10136911.09
#Sta/Elev= 30
  4174.2  215.56  4248.4  215.41  4354.7   211.8  4396.8   211.6  4424.8  208.11
  4434.8  208.43  4464.9   206.1  4540.2  203.62  4615.3  202.74  4645.3  204.53
  4845.8   204.4  4865.9  203.53  4966.1  202.15  4969.7   200.5    5039     201
    5071  203.68    5093  205.21  5159.4  205.76  5183.5  202.64    5201  204.41
  5212.9  208.19  5222.6  208.34  5308.9  207.97  5397.6  210.41  5406.1  208.65
  5416.3  208.19  5438.5  209.32  5445.7  212.03  5451.1   211.3    5514  214.87
#Mann= 3 , 0 , 0
  4174.2     .11       0  4865.9     .06       0    5071     .11       0
Bank Sta=4865.9,5071
XS Rating Curve= 0 ,0
Exp/Cntr=0.3,0.1

Type RM Length L Ch R = 1 ,25500   ,500,500,500
BEGIN DESCRIPTION:
STEWART CREEK NORTH 51.0
END DESCRIPTION:
XS GIS Cut Line= 3
      3771317.84     10138211.09      3771696.31     10137268.86
      3771667.85     10136761.05
#Sta/Elev= 30
  3984.6  213.79  4082.8  212.42  4113.9  213.05  4262.9  208.93    4322  209.96
  4329.5  209.75  4346.2  207.12  4351.6  207.81  4361.8  206.86  4370.4  205.43
  4375.8  206.41  4394.1  205.14  4598.9  203.95  4615.1   206.8  4620.5  205.94
  4631.2  206.77  4698.4  206.21  4728.2  204.32  4824.8  205.59  4900.6  202.24
  4902.4   200.5    5118     201    5128  202.53  5218.1  204.66  5228.1  205.69
  5308.3  206.78  5328.3  210.12  5368.4   212.9  5458.5  214.55  5508.6  224.82
#Mann= 3 , 0 , 0
  3984.6     .11       0  4900.6    .015       0    5128     .11       0
#XS Ineff= 2 , 0
       0  4631.2  206.77  5241.8       0  205.84
Permanent Ineff=
       F       F
Bank Sta=4900.6,5128
XS Rating Curve= 0 ,0
Exp/Cntr=0.3,0.1