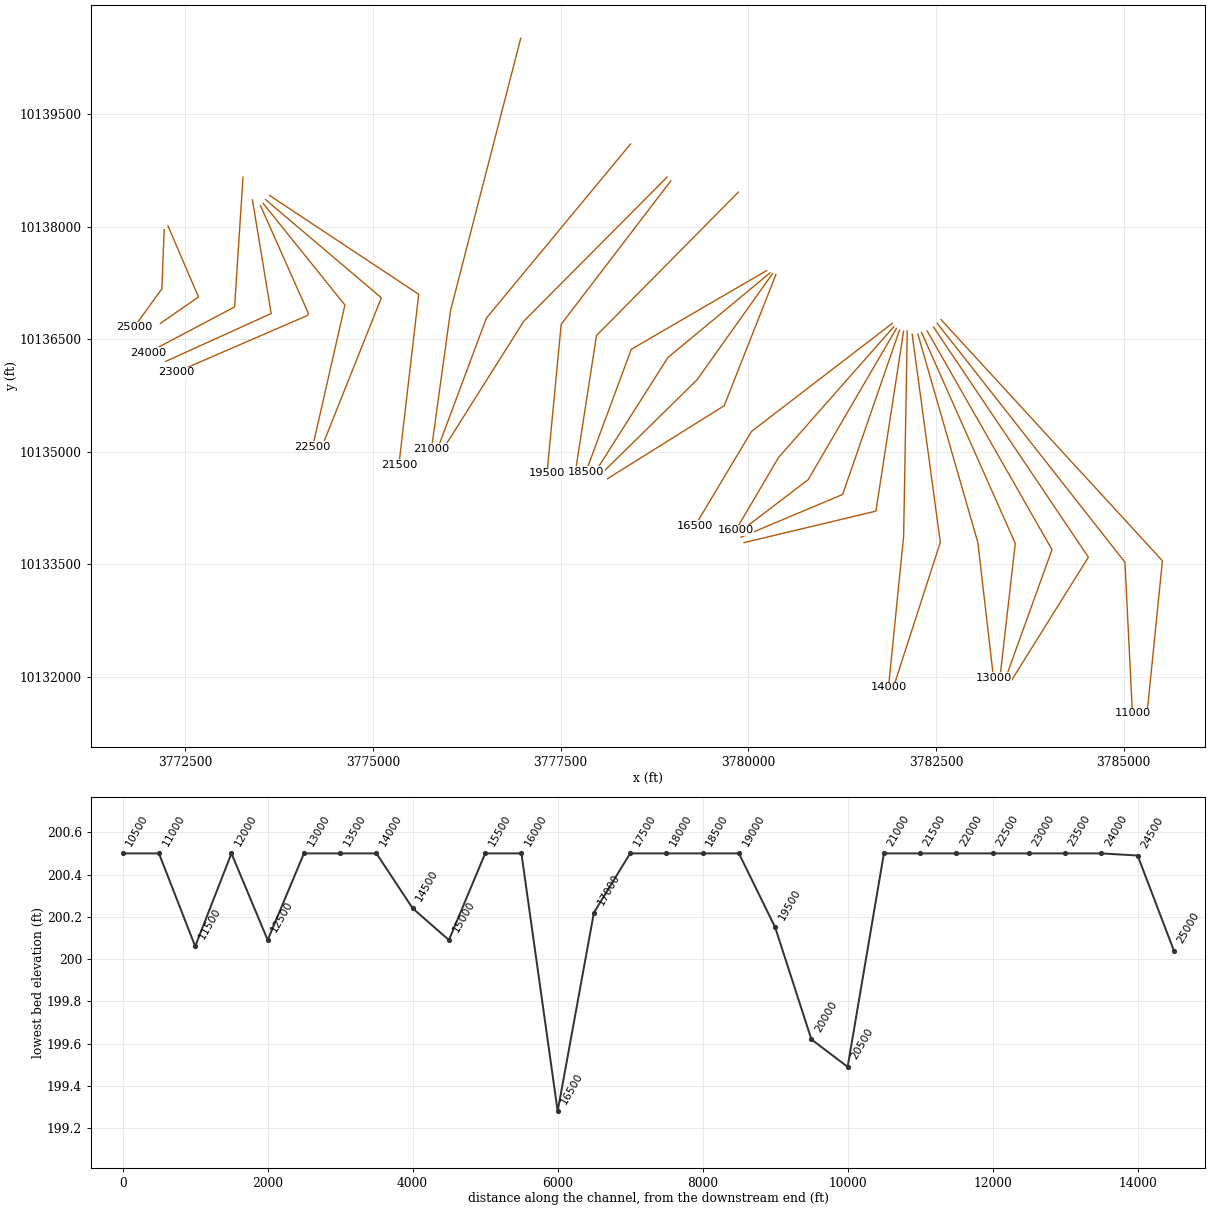
HEC-RAS study STEWART CREEK NORTH.prj: STEWART CREEK NORTH Base Level Engineering

--- STEWART CREEK NORTH.g01 (geometry) --- (continued)

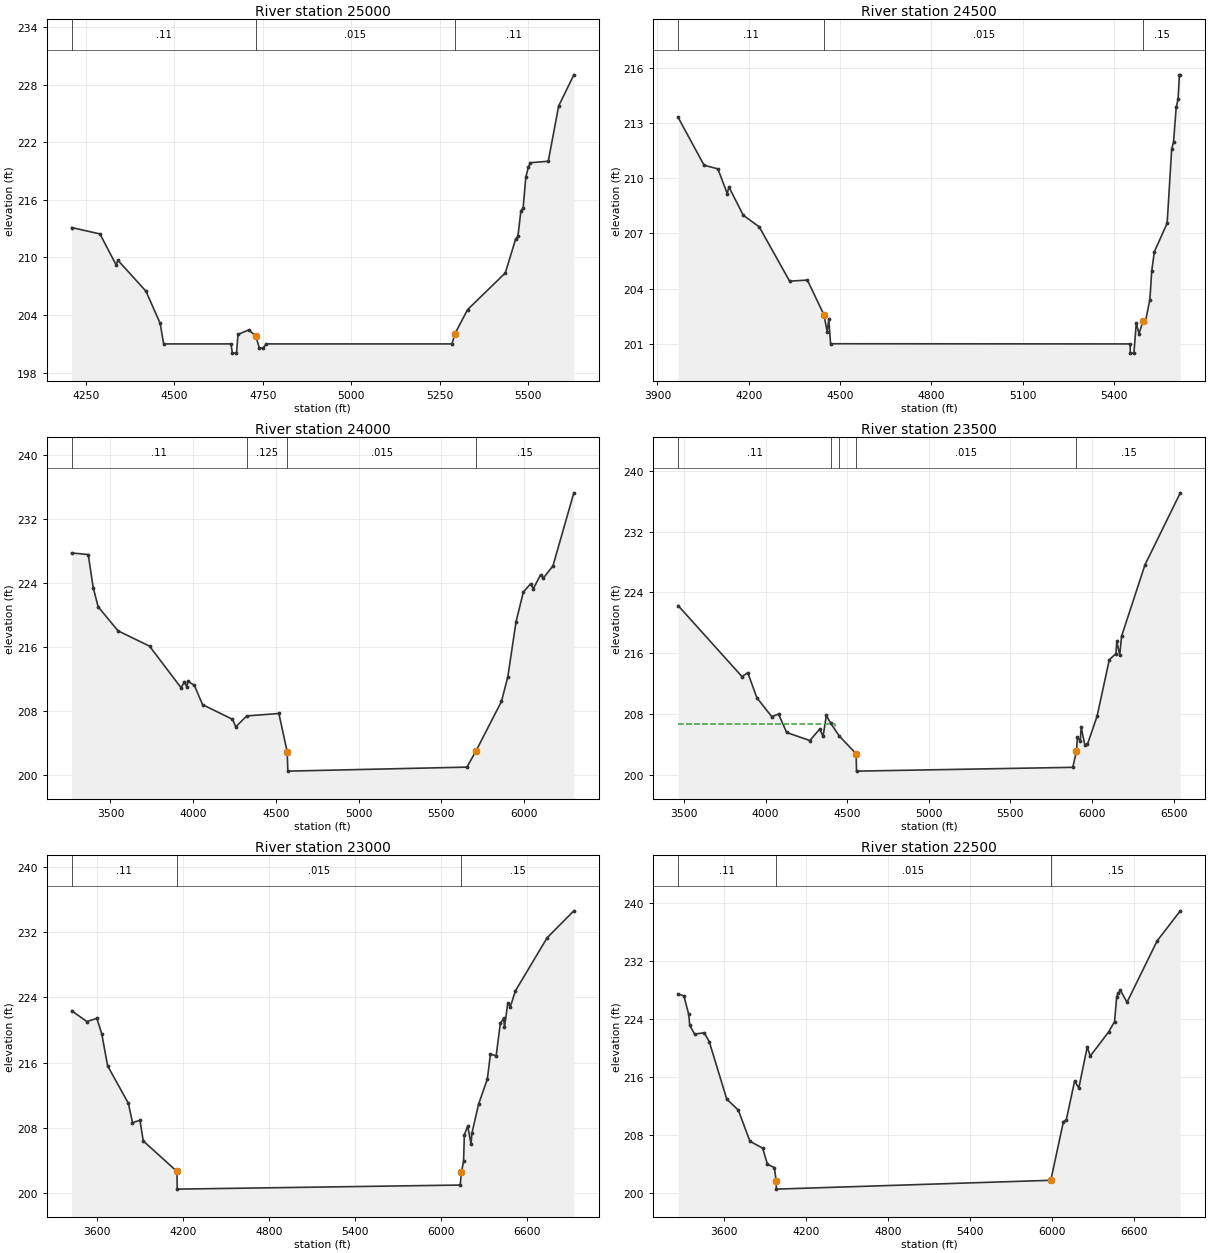
Type RM Length L Ch R = 1 ,25000   ,500,500,500
BEGIN DESCRIPTION:
STEWART CREEK NORTH 50.0
END DESCRIPTION:
XS GIS Cut Line= 3
      3772217.85     10137961.06      3772186.61     10137170.87
      3771817.85     10136661.06
#Sta/Elev= 30
  4209.2  213.12  4289.2  212.45    4335  209.23    4340  209.71  4419.3  206.49
  4459.4  203.15  4469.4     201  4659.5     201  4663.8  200.04  4675.3  200.04
  4679.6  201.99  4709.6  202.45  4729.6  201.85  4739.6   200.6  4749.6  200.54
  4759.6     201  5284.6     201  5293.1  202.07  5328.7  204.57  5435.4  208.39
  5464.8  211.94    5471  212.19  5479.5  214.85  5485.7  215.12  5493.4  218.36
  5500.4  219.38  5506.6  219.87  5556.9  220.02  5586.3  225.78  5629.2  229.02
#Mann= 3 , 0 , 0
  4209.2     .11       0  4729.6    .015       0  5293.1     .11       0
Bank Sta=4729.6,5293.1
XS Rating Curve= 0 ,0
Exp/Cntr=0.3,0.1

Type RM Length L Ch R = 1 ,24500   ,500,500,500
BEGIN DESCRIPTION:
STEWART CREEK NORTH 49.0
END DESCRIPTION:
XS GIS Cut Line= 3
      3772267.84     10138011.09      3772674.79     10137062.82
      3772167.87     10136711.09
#Sta/Elev= 30
  3968.1   213.3  4053.3   210.7  4098.7   210.5  4129.4  209.16  4134.9  209.52
    4182  207.98  4234.5  207.35  4334.2   204.4  4392.5  204.46  4446.9  202.57
  4457.5  201.66  4462.9  202.33  4468.7     201  5452.4  200.99  5452.9  200.49
  5464.6  200.49  5472.5  202.12  5481.3  201.55  5495.3  202.26  5502.2  202.18
  5517.1   203.4  5523.1  204.94  5531.8     206  5573.8  207.55  5588.7  211.58
  5594.7  211.95  5603.5  213.85  5609.6  214.28    5614  215.61    5617  215.61
#Mann= 3 ,-1 , 0
  3968.1     .11       0  4446.9    .015       0  5495.3     .15       0
Bank Sta=4446.9,5495.3
XS Rating Curve= 0 ,0
Exp/Cntr=0.3,0.1

Type RM Length L Ch R = 1 ,24000   ,500,500,500
BEGIN DESCRIPTION:
STEWART CREEK NORTH 48.0
END DESCRIPTION:
XS GIS Cut Line= 3
      3773267.85     10138661.05      3773155.94     10136930.06
      3772006.12     10136321.58
#Sta/Elev= 30
  3265.4  227.72  3365.6  227.52  3395.6   223.4  3425.7     221    3546     218
  3736.4  216.09  3926.8   210.9  3946.8  211.64  3962.4  210.96  3967.4  211.72
  4006.9  211.21    4057  208.79  4237.4  206.97  4257.4  206.03    4324  207.39
    4518  207.69  4568.1  202.92  4572.2   200.5  5654.8     201  5709.5  203.02
  5863.5   209.2  5901.9  212.28  5951.6  219.15  5995.6  222.84  6039.6  223.87
  6055.9  223.25  6099.9     225  6116.3  224.58  6174.5   226.1  6300.9  235.22
#Mann= 4 ,-1 , 0
  3265.4     .11       0    4324    .125       0  4568.1    .015       0
  5709.5     .15       0
#XS Ineff= 2 , 0
       0    4518  207.69               0
Permanent Ineff=
       F       F
Bank Sta=4568.1,5709.5
XS Rating Curve= 0 ,0
Exp/Cntr=0.3,0.1

Type RM Length L Ch R = 1 ,23500   ,500,500,500
BEGIN DESCRIPTION:
STEWART CREEK NORTH 47.0
END DESCRIPTION:
XS GIS Cut Line= 3
      3773393.46     10138357.38      3773643.31     10136841.94
      3772240.04     10136204.66
#Sta/Elev= 30
  3464.1  222.27  3855.6  212.93  3890.9  213.44  3946.8  210.14  4038.1  207.66
  4079.4     208  4129.3  205.58  4271.2  204.52    4332  206.04  4352.2  205.06
  4372.5  207.82  4399.8  206.77  4451.1  205.13  4554.9  202.78  4557.2   200.5
    5882     201  5905.1  203.09  5910.5  205.01  5928.1  204.44  5933.6  206.26
  5956.7  203.91  5972.5  204.04  6031.4  207.73  6106.1  215.15  6146.8  215.95
  6152.3  217.55  6169.9  215.76  6181.2  218.23  6324.8  227.63  6541.2  237.09
#Mann= 5 ,-1 , 0
  3464.1     .11       0  4399.8    .125       0  4451.1     .11       0
  4554.9    .015       0  5905.1     .15       0
#XS Ineff= 2 , 0
       0  4423.2  206.75  5933.6       0  206.26
Permanent Ineff=
       F       F
Bank Sta=4554.9,5905.1
XS Rating Curve= 0 ,0
Exp/Cntr=0.3,0.1

Type RM Length L Ch R = 1 ,23000   ,500,500,500
BEGIN DESCRIPTION:
STEWART CREEK NORTH 46.0
END DESCRIPTION:
XS GIS Cut Line= 4
      3773499.77     10138282.98      3774141.19     10136839.47
      3774125.38     10136815.91      3772383.55     10136061.14
#Sta/Elev= 30
  3420.4  222.35  3526.5  221.03  3596.2  221.42  3630.4  219.55  3671.5   215.6
  3816.4  211.01  3845.2  208.64  3897.2  208.93  3920.5   206.4  4155.7  202.67
  4157.7   200.5  6133.2     201 6142.07  202.59  6156.7  203.89  6162.2  207.14
  6185.6  208.23  6209.1  206.01  6214.6  207.32  6261.5   210.9  6322.6  213.97
  6344.4  217.04  6384.3  216.83  6413.3  220.79  6436.7  221.42  6442.5  220.36
  6465.7  223.31  6483.7  222.86  6518.8  224.79  6740.2  231.29  6926.7  234.59
#Mann= 3 ,-1 , 0
  3420.4     .11       0  4155.7    .015       0 6142.07     .15       0
Bank Sta=4155.7,6142.07
XS Rating Curve= 0 ,0
Exp/Cntr=0.3,0.1

Type RM Length L Ch R = 1 ,22500   ,500,500,500
BEGIN DESCRIPTION:
STEWART CREEK NORTH 45.0
END DESCRIPTION:
XS GIS Cut Line= 3
      3773536.98     10138309.55      3774625.55     10136955.45
      3774196.09     10135067.17
#Sta/Elev= 30
  3262.6  227.47  3304.7   227.2  3339.9  224.67  3347.9  223.14  3383.1  221.92
  3453.5   222.1  3490.3  220.88  3618.3  212.94  3703.1  211.42  3787.9  207.11
  3880.7  206.17  3915.9  203.94  3966.3  203.48  3979.9  201.68  3981.5   200.5
    5989  201.72  6081.3  209.82  6101.8  210.03  6163.3  215.44  6194.1  214.48
  6255.6  220.13    6278  218.89  6412.3  222.22  6455.4  223.64    6471  227.06
  6481.3  227.55  6498.4  227.96  6546.6  226.32    6767   234.8  6936.5  238.95
#Mann= 3 ,-1 , 0
  3262.6     .11       0  3979.9    .015       0    5989     .15       0
Bank Sta=3979.9,5989
XS Rating Curve= 0 ,0
Exp/Cntr=0.3,0.1

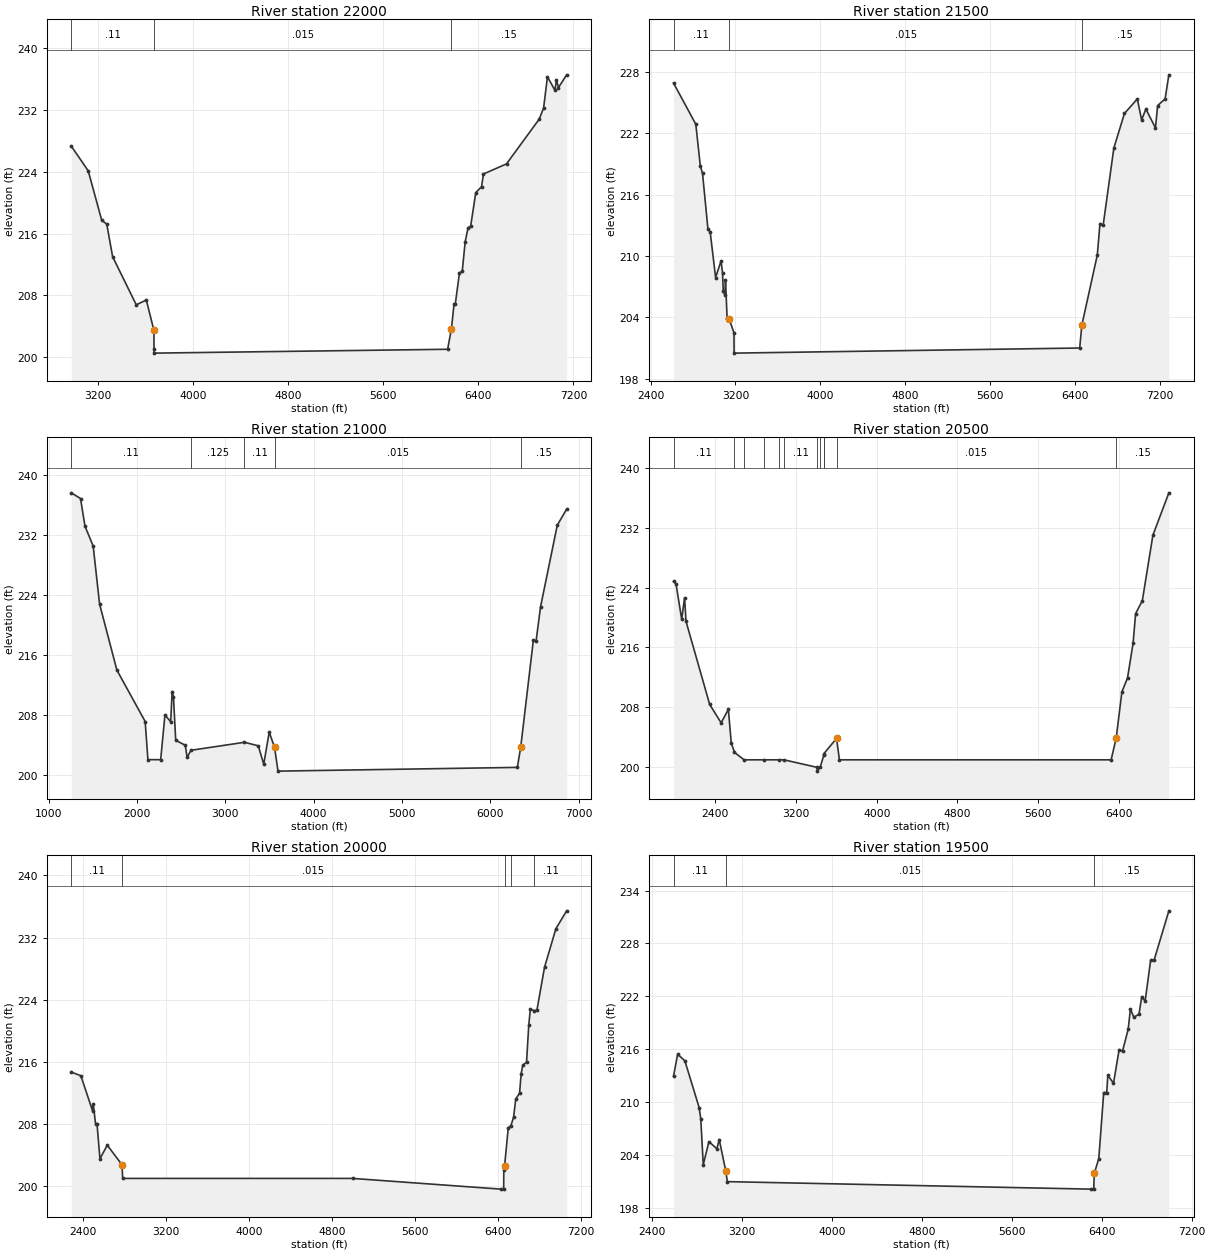
Type RM Length L Ch R = 1 ,22000   ,500,500,500
BEGIN DESCRIPTION:
STEWART CREEK NORTH 44.0
END DESCRIPTION:
XS GIS Cut Line= 3
      3773567.87     10138361.05      3775110.92     10137052.03
      3774317.85     10135061.07
#Sta/Elev= 30
  2976.5  227.32  3118.7  224.12  3231.9  217.74  3274.7  217.21  3324.1  212.99
    3523  206.76  3607.5  207.38  3671.5  203.44    3672     201  3672.5   200.5
    6142     201  6174.3  203.68  6195.9  206.86    6206  206.81  6241.1  210.85
  6265.3  211.16  6289.6  214.93  6313.9  216.74  6335.8  216.95  6378.8   221.3
  6427.1  222.06  6443.4  223.71  6637.2  225.02  6912.5  230.82  6949.3  232.26
  6981.6   236.3  7044.7  234.56    7057  235.92  7074.3  234.91  7143.1  236.56
#Mann= 3 ,-1 , 0
  2976.5     .11       0  3671.5    .015       0  6174.3     .15       0
Bank Sta=3671.5,6174.3
XS Rating Curve= 0 ,0
Exp/Cntr=0.3,0.1

Type RM Length L Ch R = 1 ,21500   ,500,500,500
BEGIN DESCRIPTION:
STEWART CREEK NORTH 43.0
END DESCRIPTION:
XS GIS Cut Line= 3
      3773622.74     10138415.76      3775608.75      10137098.6
      3775345.03     10134825.75
#Sta/Elev= 30
  2616.9  226.91    2827  222.88  2869.3  218.82  2890.4  218.07  2941.5  212.62
  2962.6  212.34  3013.7  207.89  3064.8  209.51    3079  208.35  3085.9  206.54
  3100.9  206.18  3106.9  207.69    3122  203.96    3143   203.8    3187  202.49
  3187.8   200.5  6447.2     201  6467.3  203.23  6613.1  210.08  6638.4  213.17
  6668.6  213.01  6769.3  220.55  6869.1  223.93  6990.8  225.35  7031.1   223.3
  7071.3  224.36  7161.9  222.52  7182.1   224.7  7252.5  225.36  7288.1  227.71
#Mann= 3 ,-1 , 0
  2616.9     .11       0    3143    .015       0  6467.3     .15       0
Bank Sta=3143,6467.3
XS Rating Curve= 0 ,0
Exp/Cntr=0.3,0.1

Type RM Length L Ch R = 1 ,21000   ,500,500,500
BEGIN DESCRIPTION:
STEWART CREEK NORTH 42.0
END DESCRIPTION:
XS GIS Cut Line= 3
      3776967.85     10140511.07      3776033.79     10136885.97
      3775778.76     10135038.09
#Sta/Elev= 30
  1256.5  237.65  1360.8  236.89  1411.4   233.2  1504.3  230.54  1576.6   222.8
  1772.8  213.98    2093  207.12  2123.9  202.03  2268.5  202.03  2316.8     208
  2382.1  207.09  2398.1  211.12  2413.1  210.43  2438.8  204.62  2547.3  203.95
    2568  202.32  2610.6  203.28  3217.6  204.35  3373.5  203.88  3435.4  201.43
  3497.4   205.7  3557.6  203.69  3597.3   200.5  6307.2     201 6345.67  203.73
  6488.9  218.01  6519.2  217.85  6569.6  222.41  6759.3  233.33  6865.4  235.47
#Mann= 5 ,-1 , 0
  1256.5     .11       0  2610.6    .125       0  3217.6     .11       0
  3557.6    .015       0 6345.67     .15       0
#XS Ineff= 2 ,-1
  3497.4  2413.1   205.7  2413.1  1907.1  210.43
Permanent Ineff=
       F       F
Bank Sta=3557.6,6345.67
XS Rating Curve= 0 ,0
Exp/Cntr=0.3,0.1

Type RM Length L Ch R = 1 ,20500   ,500,500,500
BEGIN DESCRIPTION:
STEWART CREEK NORTH 41.0
END DESCRIPTION:
XS GIS Cut Line= 3
      3778431.09     10139102.34      3776510.37     10136780.52
      3775848.72     10135004.78
#Sta/Elev= 30
  1986.7  224.81  2011.6  224.48  2067.5  219.77  2096.2  222.65  2110.5  219.48
    2345  208.39  2458.3  205.94    2530  207.73  2558.6  203.27  2590.1     202
  2685.7     201    2886     201  3033.9     201    3081     201  3410.6  199.99
  3411.1  199.49  3439.1  199.99  3476.4  201.64  3477.8  201.84    3602  203.86
  3630.6     201  6322.7     201 6373.37  203.92  6429.8  210.09  6485.2  211.92
  6540.5  216.57  6565.5  220.51  6632.2  222.26  6736.8  230.99    6895  236.65
#Mann= 12 ,-1 , 0
  1986.7     .11       0  2590.1    .125       0  2685.7     .11       0
    2886    .125       0  3033.9     .15       0    3081     .11       0
  3410.6     .11       0  3439.1     .11       0  3476.4    .125       0
  3477.8     .11       0    3602    .015       0 6373.37     .15       0
Bank Sta=3602,6373.37
XS Rating Curve= 0 ,0
Exp/Cntr=0.3,0.1

Type RM Length L Ch R = 1 ,20000   ,500,500,500
BEGIN DESCRIPTION:
STEWART CREEK NORTH 40.0
END DESCRIPTION:
XS GIS Cut Line= 3
      3778917.84     10138661.06       3777008.7     10136739.69
       3775909.4      10134995.4
#Sta/Elev= 30
  2291.4  214.69  2383.3  214.22  2496.5  209.68  2503.5  210.52  2524.7  208.03
  2538.9  208.03  2567.2  203.53  2637.9  205.28  2779.3  202.76  2786.3     201
    5000     201  6427.5  199.62  6455.3  199.62  6456.7  202.03  6464.1   202.6
  6499.5  207.51  6525.4   207.8  6550.8  208.89    6572  211.23  6608.5  211.97
  6623.8  214.48  6639.1  215.56  6675.6  215.97  6696.8   220.7  6712.1  222.78
  6750.7  222.59  6775.7  222.67  6848.6  228.17  6958.1  233.14  7061.8  235.45
#Mann= 5 ,-1 , 0
  2291.4     .11       0  2779.3    .015       0  6464.1     .15       0
  6525.4    .125       0  6750.7     .11       0
Bank Sta=2779.3,6464.1
XS Rating Curve= 0 ,0
Exp/Cntr=0.3,0.1

Type RM Length L Ch R = 1 ,19500   ,500,500,500
BEGIN DESCRIPTION:
STEWART CREEK NORTH 39.0
END DESCRIPTION:
XS GIS Cut Line= 3
      3778967.88      10138611.1      3777507.03     10136698.85
      3777317.85     10134711.04
#Sta/Elev= 30
  2593.6  212.95    2630  215.44  2694.3   214.7  2821.2   209.4  2835.8  208.11
  2857.9  202.92  2908.2  205.53  2979.1  204.73  2999.9  205.77    3058  202.21
  3071.8     201  6300.8  200.15  6328.6  200.15  6333.8  201.94    6374  203.62
  6417.7   211.1  6444.3  211.09  6454.3  213.05  6504.6  212.15  6554.8  215.97
  6584.9  215.79  6635.1  218.27  6655.2  220.57  6685.4  219.63  6731.7  219.99
  6755.7  221.98  6785.8  221.45  6834.7  226.09  6866.2  226.14  6996.8   231.7
#Mann= 3 ,-1 , 0
  2593.6     .11       0    3058    .015       0  6333.8     .15       0
#XS Ineff= 2 , 0
       0  2999.9  205.77               0
Permanent Ineff=
       F       F
Bank Sta=3058,6333.8
XS Rating Curve= 0 ,0
Exp/Cntr=0.3,0.1

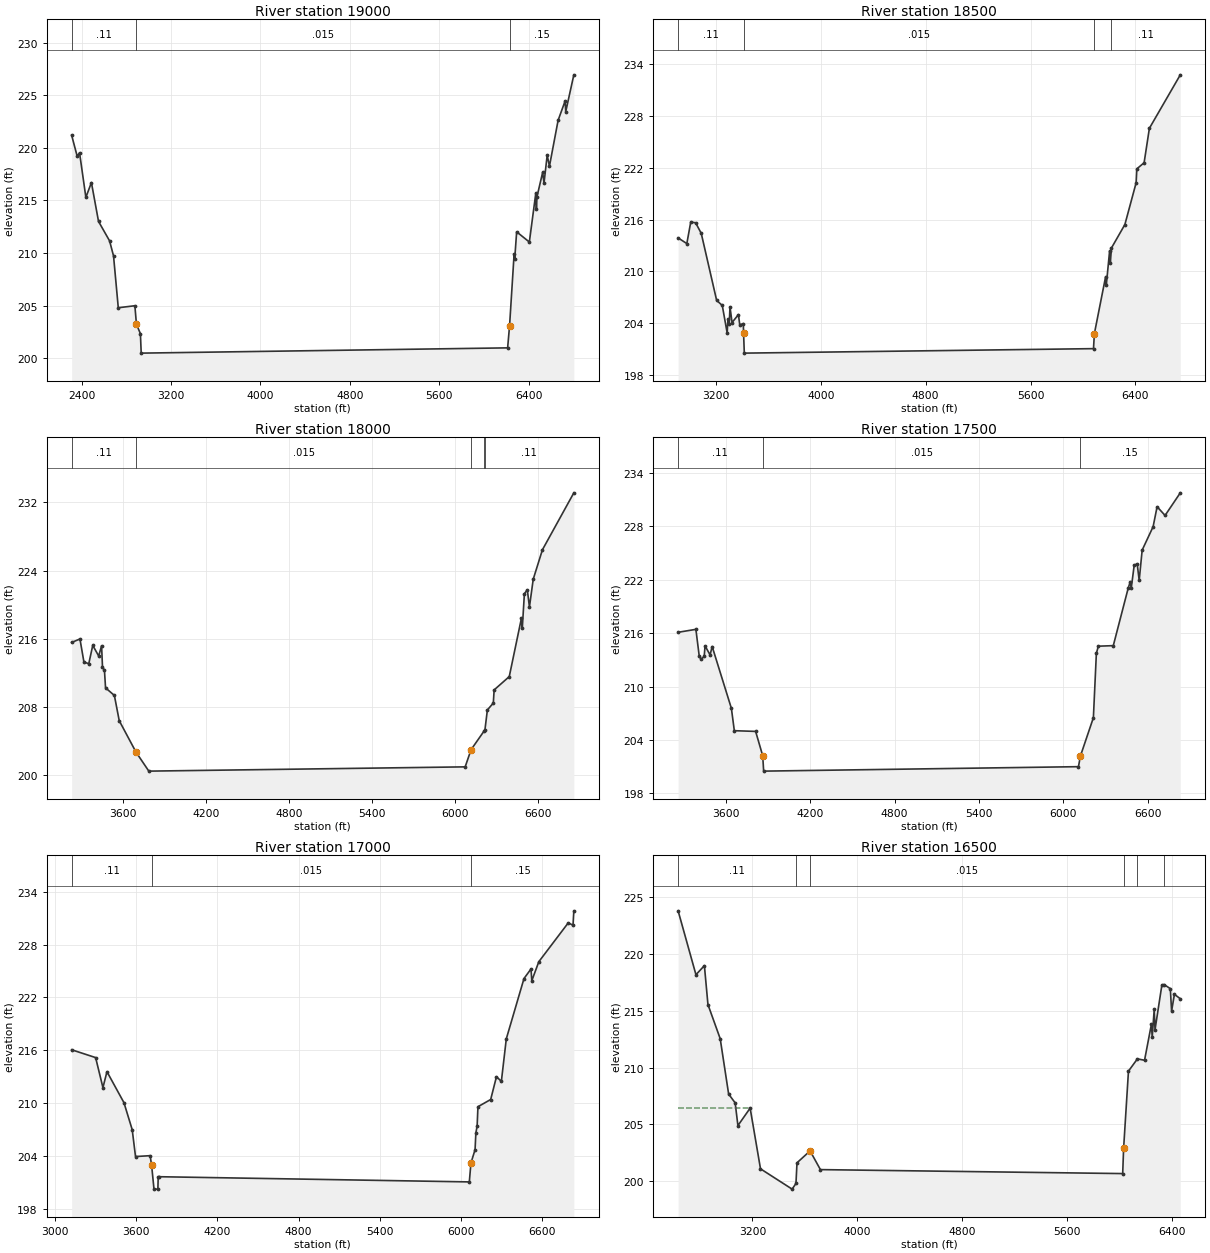
Type RM Length L Ch R = 1 ,19000   ,500,500,500
BEGIN DESCRIPTION:
STEWART CREEK NORTH 38.0
END DESCRIPTION:
XS GIS Cut Line= 3
      3779867.86     10138461.08      3777977.25     10136548.38
      3777701.61     10134765.36
#Sta/Elev= 30
  2310.6  221.19  2360.1   219.2  2381.3  219.53  2437.9  215.29  2487.4   216.7
    2551  213.01    2650  211.16  2685.4  209.73  2727.8  204.81  2876.3     205
  2890.4  203.24  2925.8  202.35    2933   200.5  6211.8     201 6229.21  203.11
  6269.8  209.91  6274.9  209.41  6292.5  212.02  6406.1  211.05  6464.1  215.71
  6469.2  214.17  6474.6  215.36  6525.2  217.67  6537.3  216.65  6565.7  219.29
  6585.9  218.25  6663.5  222.61  6726.6  224.46  6731.6  223.43  6804.2  226.93
#Mann= 3 ,-1 , 0
  2310.6     .11       0  2890.4    .015       0 6229.21     .15       0
Bank Sta=2890.4,6229.21
XS Rating Curve= 0 ,0
Exp/Cntr=0.3,0.1

Type RM Length L Ch R = 1 ,18500   ,500,500,500
BEGIN DESCRIPTION:
STEWART CREEK NORTH 37.0
END DESCRIPTION:
XS GIS Cut Line= 3
      3780245.36      10137414.8      3778440.33     10136364.42
      3777836.05     10134729.94
#Sta/Elev= 30
  2911.6  213.87  2978.1  213.21  3007.8   215.7    3045  215.63    3088   214.4
  3205.5  206.62  3248.5  206.03  3285.8  202.84  3291.6  204.42  3301.5  203.84
  3307.3  205.87    3323  204.05  3371.8  204.97  3381.8  203.77  3409.1  203.93
 3410.78  202.85  3416.6   200.5  6080.4  201.02  6087.1  202.76    6173  209.38
  6178.4  208.44  6203.4  212.38  6208.8  210.97  6217.4   212.7  6319.8  215.42
  6405.7  220.27    6411  221.88  6466.5  222.59  6506.8  226.59  6742.6  232.79
#Mann= 4 ,-1 , 0
  2911.6     .11       0 3410.78    .015       0  6087.1     .15       0
  6217.4     .11       0
Bank Sta=3410.78,6087.1
XS Rating Curve= 0 ,0
Exp/Cntr=0.3,0.1

Type RM Length L Ch R = 1 ,18000   ,500,500,500
BEGIN DESCRIPTION:
STEWART CREEK NORTH 36.0
END DESCRIPTION:
XS GIS Cut Line= 3
      3780289.42     10137384.11      3778928.14     10136254.69
      3777932.18     10134683.22
#Sta/Elev= 30
  3231.2  215.58  3291.2  215.99  3319.9  213.29    3355  213.09  3383.7  215.24
  3426.7  213.99  3447.5   215.2  3454.1  212.71  3468.3  212.31  3476.2  210.26
    3540  209.37  3575.1  206.41  3696.2  202.73  3788.9   200.5  6075.2     201
  6117.6  203.01  6210.1  205.16    6218  205.33  6235.6  207.67  6278.6  208.48
  6284.5  210.02  6393.8  211.58    6482  218.44  6487.9  217.23  6503.1  221.29
  6524.3  221.76  6539.6  219.74  6567.1     223  6633.6  226.45  6860.5  233.12
#Mann= 5 ,-1 , 0
  3231.2     .11       0  3696.2    .015       0  6117.6     .15       0
  6210.1     .17       0    6218     .11       0
Bank Sta=3696.2,6117.6
XS Rating Curve= 0 ,0
Exp/Cntr=0.3,0.1

Type RM Length L Ch R = 1 ,17500   ,500,500,500
BEGIN DESCRIPTION:
STEWART CREEK NORTH 35.0
END DESCRIPTION:
XS GIS Cut Line= 3
       3780322.8     10137373.45       3779316.4     10135957.46
      3778010.98     10134674.83
#Sta/Elev= 30
  3262.8  216.09    3389  216.42  3412.4  213.47  3425.2  213.06  3448.1  213.38
  3454.2  214.56  3489.9  213.55  3504.7  214.49  3641.2  207.55  3662.1  205.04
  3813.4  204.96  3863.8  202.22  3870.4   200.5  6106.6     201  6120.7   202.2
  6212.7   206.5  6233.9  213.73    6248  214.53  6354.1  214.59  6460.2  221.06
  6474.3  221.75  6481.4  221.02  6502.6  223.62  6523.9  223.78    6538  221.92
  6559.2  225.32    6637  227.95  6665.3  230.19  6721.9  229.21  6830.1  231.75
#Mann= 3 ,-1 , 0
  3262.8     .11       0  3863.8    .015       0  6120.7     .15       0
Bank Sta=3863.8,6120.7
XS Rating Curve= 0 ,0
Exp/Cntr=0.3,0.1

Type RM Length L Ch R = 1 ,17000   ,500,500,500
BEGIN DESCRIPTION:
STEWART CREEK NORTH 34.0
END DESCRIPTION:
XS GIS Cut Line= 3
      3780367.85     10137361.06      3779678.93     10135613.13
       3778122.7     10134638.94
#Sta/Elev= 30
  3121.2  216.05  3298.5  215.16  3352.6  211.75  3382.4  213.56  3508.1  210.04
  3569.2  206.97  3593.6  203.92  3701.6  204.02  3712.6  202.95  3730.3  200.22
    3759  200.22  3761.4  201.58  3766.8  201.63  6062.9  201.04  6074.9  203.19
  6105.4   204.7  6111.3  206.61  6120.7  207.38  6126.6  209.58  6220.9   210.4
  6263.6  212.99  6299.9  212.46  6336.4  217.29  6467.3  224.14  6519.1  225.23
    6525  223.89  6576.9  226.05  6794.5  230.46  6829.9   230.2    6836  231.83
#Mann= 3 ,-1 , 0
  3121.2     .11       0  3712.6    .015       0  6074.9     .15       0
Bank Sta=3712.6,6074.9
XS Rating Curve= 0 ,0
Exp/Cntr=0.3,0.1

Type RM Length L Ch R = 1 ,16500   ,500,500,500
BEGIN DESCRIPTION:
STEWART CREEK NORTH 33.0
END DESCRIPTION:
XS GIS Cut Line= 3
      3781917.82     10136711.05      3780041.47     10135268.79
      3779291.84     10134014.07
#Sta/Elev= 30
  2633.4  223.81  2769.3  218.18  2833.7  218.98  2860.8  215.55  2954.2  212.54
  3018.5  207.66  3068.4  206.88  3089.2  204.88  3182.5  206.42  3261.4  201.07
  3502.5  199.28  3531.8  199.78  3539.6   201.6  3639.3  202.65  3718.1     201
  6022.4  200.65  6029.5  202.88  6066.4  209.68  6134.6  210.76    6189  210.64
  6241.5  213.82  6247.4  212.68  6262.9  215.15  6268.8  213.33  6321.3  217.28
  6338.3  217.31  6385.5  216.95  6395.2  214.97  6416.7  216.45  6461.6  216.06
#Mann= 6 ,-1 , 0
  2633.4     .11       0  3531.8     .11       0  3639.3    .015       0
  6029.5     .15       0  6134.6    .125       0  6338.3     .11       0
#XS Ineff= 2 , 0
       0  3175.7  206.45               0
Permanent Ineff=
       F       F
Bank Sta=3639.3,6029.5
XS Rating Curve= 0 ,0
Exp/Cntr=0.3,0.1

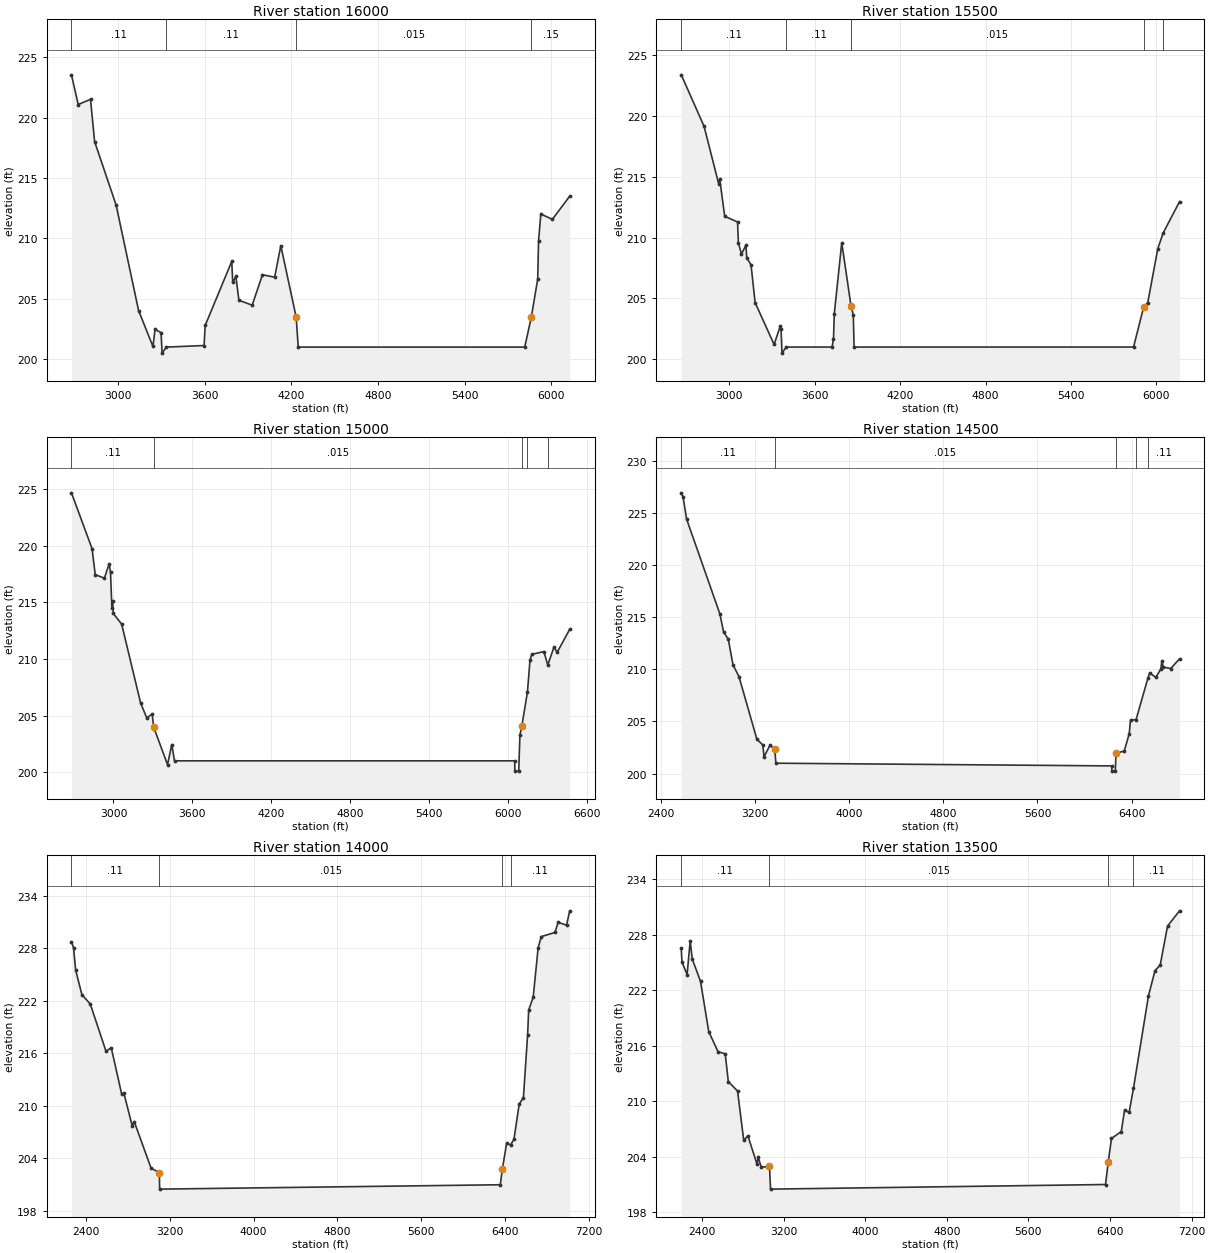
Type RM Length L Ch R = 1 ,16000   ,500,500,500
BEGIN DESCRIPTION:
STEWART CREEK NORTH 32.0
END DESCRIPTION:
XS GIS Cut Line= 3
      3781938.98     10136666.21      3780404.01     10134924.46
      3779832.61     10133951.78
#Sta/Elev= 30
  2678.4  223.55  2725.2  221.09  2810.3  221.52  2838.7  218.02  2987.7  212.76
  3143.3  204.02  3242.8  201.05  3257.1  202.47  3298.9   202.2    3306   200.5
  3335.7     201  3596.7  201.13  3604.3  202.79  3788.3   208.1    3795  206.35
  3816.8  206.86  3837.7  204.88  3929.7  204.47  4000.8  206.99  4085.3  206.79
    4128   209.4  4234.2  203.48  4248.5     201  5816.7     201  5862.2  203.47
  5906.6  206.63  5912.4  209.77  5928.1  212.02  6008.1  211.58  6128.1   213.5
#Mann= 4 ,-1 , 0
  2678.4     .11       0  3335.7     .11       0  4234.2    .015       0
  5862.2     .15       0
#XS Ineff= 2 , 0
       0    4128   209.4               0
Permanent Ineff=
       F       F
Bank Sta=4234.2,5862.2
XS Rating Curve= 0 ,0
Exp/Cntr=0.3,0.1

Type RM Length L Ch R = 1 ,15500   ,500,500,500
BEGIN DESCRIPTION:
STEWART CREEK NORTH 31.0
END DESCRIPTION:
XS GIS Cut Line= 3
      3781973.83     10136644.04      3780797.51     10134626.76
      3779874.17     10133922.11
#Sta/Elev= 30
  2664.8  223.39    2825  219.15  2926.8  214.45  2934.5  214.83  2969.8  211.75
  3059.9  211.29  3065.7  209.58  3087.2  208.64  3118.6  209.38  3124.4  208.34
  3154.4  207.77  3183.1  204.66  3316.3  201.21  3359.3  202.71  3365.1  202.52
  3371.9   200.5  3401.7     201  3723.2     201  3733.1  201.65  3738.9  203.75
  3791.1  209.58  3856.3  204.37    3872  203.65  3877.8     201  5838.9     201
  5909.6  204.27  5938.7  204.65  6009.4   209.1  6046.5  210.37  6161.5  212.96
#Mann= 5 ,-1 , 0
  2664.8     .11       0  3401.7     .11       0  3856.3    .015       0
  5909.6     .15       0  6046.5     .11       0
#XS Ineff= 2 , 0
       0  3791.1  209.58               0
Permanent Ineff=
       F       F
Bank Sta=3856.3,5909.6
XS Rating Curve= 0 ,0
Exp/Cntr=0.3,0.1

Type RM Length L Ch R = 1 ,15000   ,500,500,500
BEGIN DESCRIPTION:
STEWART CREEK NORTH 30.0
END DESCRIPTION:
XS GIS Cut Line= 3
      3782014.99     10136621.81      3781257.14     10134429.93
      3779902.42     10133859.81
#Sta/Elev= 30
  2680.8  224.68  2837.7  219.74  2861.5  217.45  2931.2  217.14  2967.7  218.42
  2977.8  217.66  2988.3  214.49  2993.5  215.11    2999  214.02  3062.5  213.08
  3206.5  206.12    3253   204.8  3294.7  205.12  3305.9  203.98  3411.7  200.66
  3443.4  202.43  3464.6     201  6051.6     201  6052.8  200.09  6082.1  200.09
  6091.2  203.28  6105.9  204.08  6148.5  207.08  6167.8   209.9  6181.8  210.41
  6273.6  210.65    6303  209.46  6350.3  211.06    6374  210.58  6469.8  212.62
#Mann= 5 ,-1 , 0
  2680.8     .11       0  3305.9    .015       0  6105.9     .15       0
  6148.5     .15       0    6303     .11       0
Bank Sta=3305.9,6105.9
XS Rating Curve= 0 ,0
Exp/Cntr=0.3,0.1

Type RM Length L Ch R = 1 ,14500   ,500,500,500
BEGIN DESCRIPTION:
STEWART CREEK NORTH 29.0
END DESCRIPTION:
XS GIS Cut Line= 3
      3782068.86       10136606.       3781700.5     10134207.62
      3779942.87      10133787.7
#Sta/Elev= 30
  2573.5  226.93  2588.6  226.56    2619  224.41  2902.2   215.3  2932.6  213.61
  2973.1  212.89  3013.5  210.42  3064.1   209.3  3215.9   203.3  3266.5  202.75
  3276.7  201.61  3327.2  202.72  3367.6  202.33  3377.7     201  6231.6  200.74
  6232.1  200.24  6261.5  200.24  6267.3  201.95  6337.4  202.17  6379.5  203.81
  6390.7  205.11  6438.3  205.19  6538.9  209.17    6553  209.65  6606.6  209.23
  6647.8  210.03    6658   210.8  6668.3  210.22  6731.6  210.08  6807.1     211
#Mann= 5 ,-1 , 0
  2573.5     .11       0  3367.6    .015       0  6267.3     .15       0
  6438.3     .15       0  6538.9     .11       0
#XS Ineff= 2 , 0
       0                  6390.7       0  205.11
Permanent Ineff=
       F       F
Bank Sta=3367.6,6267.3
XS Rating Curve= 0 ,0
Exp/Cntr=0.3,0.1

Type RM Length L Ch R = 1 ,14000   ,500,500,500
BEGIN DESCRIPTION:
STEWART CREEK NORTH 28.0
END DESCRIPTION:
XS GIS Cut Line= 3
      3782117.85     10136611.07      3782069.54      10133870.7
      3781867.85      10131861.1
#Sta/Elev= 30
  2259.2  228.72  2279.2  228.06  2299.2   225.5  2359.2  222.69  2439.2  221.62
  2589.3  216.23  2639.3  216.64  2739.3  211.33  2759.3  211.49  2839.3  207.73
  2859.3   208.2  3019.3  202.91  3099.3  202.36  3101.6   200.5  6356.4     201
  6376.5  202.79  6416.7  205.72  6454.7  205.54  6487.1  206.19  6537.3   210.2
  6577.5  210.95  6617.7  218.13  6627.8  220.94  6671.1  222.42  6718.2  228.04
  6748.4  229.32    6879  229.79  6909.2  230.95  6989.6  230.62  7019.7  232.26
#Mann= 4 ,-1 , 0
  2259.2     .11       0  3099.3    .015       0  6376.5     .15       0
  6454.7     .11       0
Bank Sta=3099.3,6376.5
XS Rating Curve= 0 ,0
Exp/Cntr=0.3,0.1

Type RM Length L Ch R = 1 ,13500   ,500,500,500
BEGIN DESCRIPTION:
STEWART CREEK NORTH 27.0
END DESCRIPTION:
XS GIS Cut Line= 3
      3782182.92     10136567.95      3782558.26      10133790.8
      3781917.86      10131811.1
#Sta/Elev= 30
  2197.6  226.55  2204.5  225.07    2255  223.72  2285.3  227.36  2305.4  225.39
  2386.2  222.99  2466.9  217.55  2557.7  215.37  2628.4  215.14  2658.6  212.14
  2749.4  211.11    2810  205.77  2850.4  206.28  2939.9   203.2  2951.3  203.98
  2981.5  202.87  3062.3  202.96  3072.5   200.5  6355.5     201    6382  203.41
    6414  205.98    6510  206.73    6542  209.03  6586.7   208.8  6629.7  211.41
  6776.6  221.42  6840.6  224.14  6891.5  224.74  6963.4  228.96  7080.7  230.61
#Mann= 4 ,-1 , 0
  2197.6     .11       0  3062.3    .015       0    6382     .15       0
  6629.7     .11       0
Bank Sta=3062.3,6382
XS Rating Curve= 0 ,0
Exp/Cntr=0.3,0.1

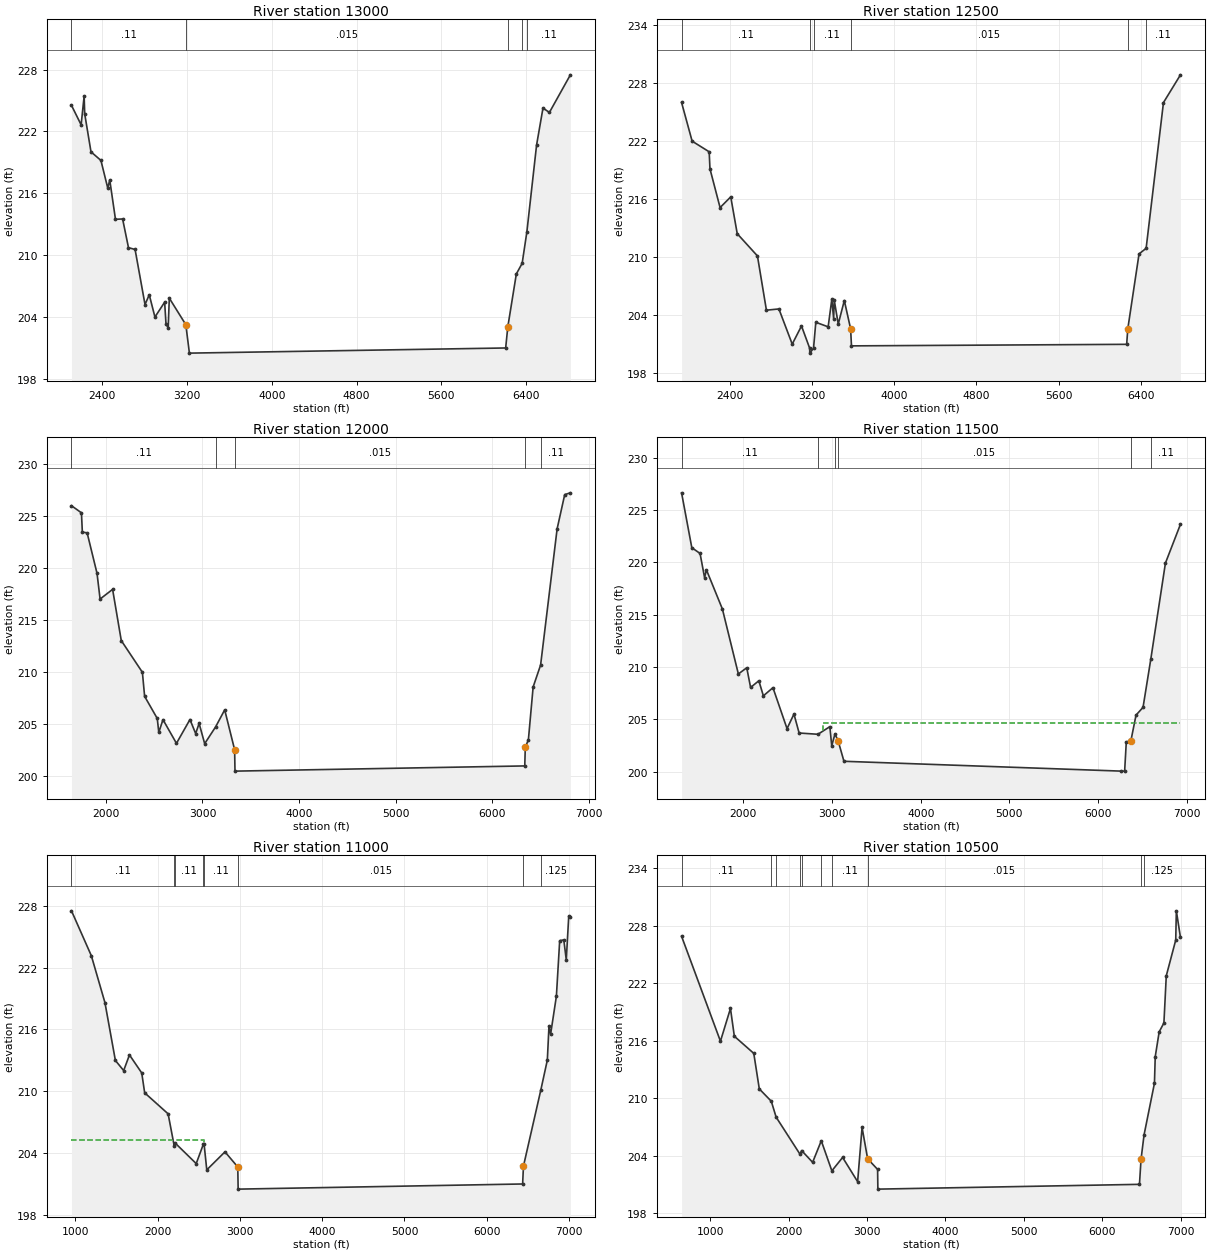
Type RM Length L Ch R = 1 ,13000   ,500,500,500
BEGIN DESCRIPTION:
STEWART CREEK NORTH 26.0
END DESCRIPTION:
XS GIS Cut Line= 3
      3782258.96     10136567.97      3783058.26     10133789.76
      3783267.18     10131984.31
#Sta/Elev= 30
  2109.1  224.53  2200.1  222.64  2228.6  225.43  2233.8  223.71  2293.2  220.02
  2386.8  219.19  2451.6   216.5  2470.1   217.3  2524.2  213.48  2591.6  213.51
    2647  210.73  2709.4  210.55  2803.1  205.21    2843  206.16  2896.7     204
  2988.2  205.44  3000.8  203.37  3021.6  202.93  3032.3  205.83  3188.1  203.26
  3221.9   200.5  6206.7     201  6226.8  203.04  6307.4  208.18  6362.4  209.21
  6406.7  212.25  6498.6  220.69    6559  224.27  6619.4  223.84  6817.5  227.49
#Mann= 5 ,-1 , 0
  2109.1     .11       0  3188.1    .015       0  6226.8     .15       0
  6362.4    .125       0  6406.7     .11       0
Bank Sta=3188.1,6226.8
XS Rating Curve= 0 ,0
Exp/Cntr=0.3,0.1

Type RM Length L Ch R = 1 ,12500   ,500,500,500
BEGIN DESCRIPTION:
STEWART CREEK NORTH 25.0
END DESCRIPTION:
XS GIS Cut Line= 3
      3782309.63     10136587.02      3783557.15     10133776.66
      3783354.19     10131999.92
#Sta/Elev= 30
  1925.2  226.01  2028.2  222.01  2194.3  220.91    2202  219.15  2300.5  215.14
  2404.5  216.25  2467.8  212.44  2664.8  210.14  2752.3  204.53  2873.9  204.66
  3003.9  201.02  3094.2   202.9  3174.1  200.59    3175  200.09  3211.5  200.59
  3233.7  203.28    3354  202.81  3389.8  205.66  3407.6  203.66  3413.1  205.59
  3452.5  203.09  3511.6  205.53  3572.9  202.61  3581.4  200.84  6263.8     201
  6275.1  202.62  6384.5  210.35  6453.6  210.93  6622.5     226  6788.3  228.87
#Mann= 6 ,-1 , 0
  1925.2     .11       0  3174.1     .11       0  3211.5     .11       0
  3572.9    .015       0  6275.1     .15       0  6453.6     .11       0
#XS Ineff= 2 , 0
       0  3511.6  205.53               0
Permanent Ineff=
       F       F
Bank Sta=3572.9,6275.1
XS Rating Curve= 0 ,0
Exp/Cntr=0.3,0.1

Type RM Length L Ch R = 1 ,12000   ,500,500,500
BEGIN DESCRIPTION:
STEWART CREEK NORTH 24.0
END DESCRIPTION:
XS GIS Cut Line= 3
      3782383.57     10136608.72      3784046.33     10133693.95
      3783432.57     10131991.93
#Sta/Elev= 30
  1644.3  226.01  1747.4  225.33  1756.7  223.48  1806.4   223.4  1908.7  219.51
  1940.4  217.04    2070  217.97  2159.7  213.05  2378.4     210  2401.4  207.69
  2532.3  205.56  2548.2  204.22  2591.4  205.45  2731.1  203.17  2870.8  205.46
  2929.9  204.11  2965.6  205.09  3023.1  203.14  3136.2  204.75  3230.4  206.39
  3333.2  202.56    3337   200.5    6337     201  6342.5  202.81  6374.4   203.5
  6423.7  208.59    6501   210.7    6672  223.79  6750.6  227.08  6809.3  227.25
#Mann= 5 ,-1 , 0
  1644.3     .11       0  3136.2    .125       0  3333.2    .015       0
  6342.5     .15       0    6501     .11       0
#XS Ineff= 1 ,-1
    2400  3230.4  206.39
Permanent Ineff=
       F
Bank Sta=3333.2,6342.5
XS Rating Curve= 0 ,0
Exp/Cntr=0.3,0.1

Type RM Length L Ch R = 1 ,11500   ,500,500,500
BEGIN DESCRIPTION:
STEWART CREEK NORTH 23.0
END DESCRIPTION:
XS GIS Cut Line= 3
      3782467.84     10136661.08      3784530.97     10133593.41
      3783510.42     10131956.48
#Sta/Elev= 30
  1303.1  226.64  1418.6   221.4  1511.6  220.85  1562.6  218.54  1583.6  219.28
  1763.6  215.54  1943.5  209.34  2038.2  209.93  2081.5  208.05  2174.5  208.69
  2225.5  207.25  2333.5  208.03  2492.4  204.12  2570.5  205.51  2628.7   203.7
  2841.3  203.58  2975.4  204.31  2996.4  202.47  3032.6  203.61  3068.4  202.96
  3134.3     201  6263.7  200.06  6299.5  200.06  6318.1  202.85  6369.7  202.95
  6427.9  205.41  6506.9  206.15  6594.2  210.74  6759.4  219.93    6929  223.64
#Mann= 6 ,-1 , 0
  1303.1     .11       0  2841.3    .125       0  3032.6     .11       0
  3068.4    .015       0  6369.7     .15       0  6594.2     .11       0
#XS Ineff= 2 ,-1
  2903.4  2570.5  204.65  2570.5  2426.5  205.51
Permanent Ineff=
       F       F
Bank Sta=3068.4,6369.7
XS Rating Curve= 0 ,0
Exp/Cntr=0.3,0.1

Type RM Length L Ch R = 1 ,11000   ,500,500,500
BEGIN DESCRIPTION:
STEWART CREEK NORTH 22.0
END DESCRIPTION:
XS GIS Cut Line= 3
      3782517.87     10136711.05      3785017.71     10133526.41
      3785117.85     10131511.09
#Sta/Elev= 30
   951.4  227.52  1192.9  223.16  1358.1  218.61  1485.3  212.99  1585.9  212.01
  1656.4  213.53  1805.6  211.78  1841.3  209.85  2126.4  207.81  2200.7  204.69
  2211.1  204.98  2468.1  202.98  2555.8  204.88  2563.4  204.91  2596.4  202.37
  2817.9  204.12  2973.4  202.65    2978   200.5  6437.1     201  6447.1  202.73
  6658.2  210.12  6737.5  213.03  6757.5  216.33  6777.5  215.55  6847.6  219.23
  6887.7  224.62  6937.7   224.7  6967.8  222.76  6997.8     227  7017.8  226.91
#Mann= 8 ,-1 , 0
   951.4     .11       0  2200.7    .125       0  2211.1     .11       0
  2555.8    .125       0  2563.4     .11       0  2973.4    .015       0
  6447.1     .15       0  6658.2    .125       0
#XS Ineff= 2 , 0
       0  2561.2  205.24               0
Permanent Ineff=
       F       F
Bank Sta=2973.4,6447.1
XS Rating Curve= 0 ,0
Exp/Cntr=0.3,0.1

Type RM Length L Ch R = 1 ,10500   ,500,500,500
BEGIN DESCRIPTION:
STEWART CREEK NORTH 21.0
END DESCRIPTION:
XS GIS Cut Line= 3
      3782567.82      10136761.1      3785517.35     10133545.59
      3785317.85     10131561.09
#Sta/Elev= 30
   636.6  226.91  1132.1  215.95  1259.7  219.37  1309.1  216.47  1556.9  214.68
  1627.2  210.97    1780  209.68  1841.6  208.02  2146.3  204.14  2166.6  204.53
  2306.7   203.3  2417.1  205.55  2551.9  202.41    2689  203.81  2880.2  201.28
  2936.9  206.94  3007.8  203.67  3134.8  202.56  3138.2   200.5  6471.9     201
    6492  203.62  6530.6  206.17  6662.9  211.56  6672.9  214.33  6723.2  216.93
  6783.5  217.86  6813.6  222.78  6934.2  226.52  6941.9  229.57  6994.5  226.79
#Mann= 10 ,-1 , 0
   636.6     .11       0    1780    .125       0  1841.6     .11       0
  2146.3    .125       0  2166.6     .11       0  2417.1    .125       0
  2551.9     .11       0  3007.8    .015       0    6492     .15       0
  6530.6    .125       0
#XS Ineff= 1 ,-1
    1800  2936.9  206.94
Permanent Ineff=
       F
Bank Sta=3007.8,6492
XS Rating Curve= 0 ,0
Exp/Cntr=0.3,0.1