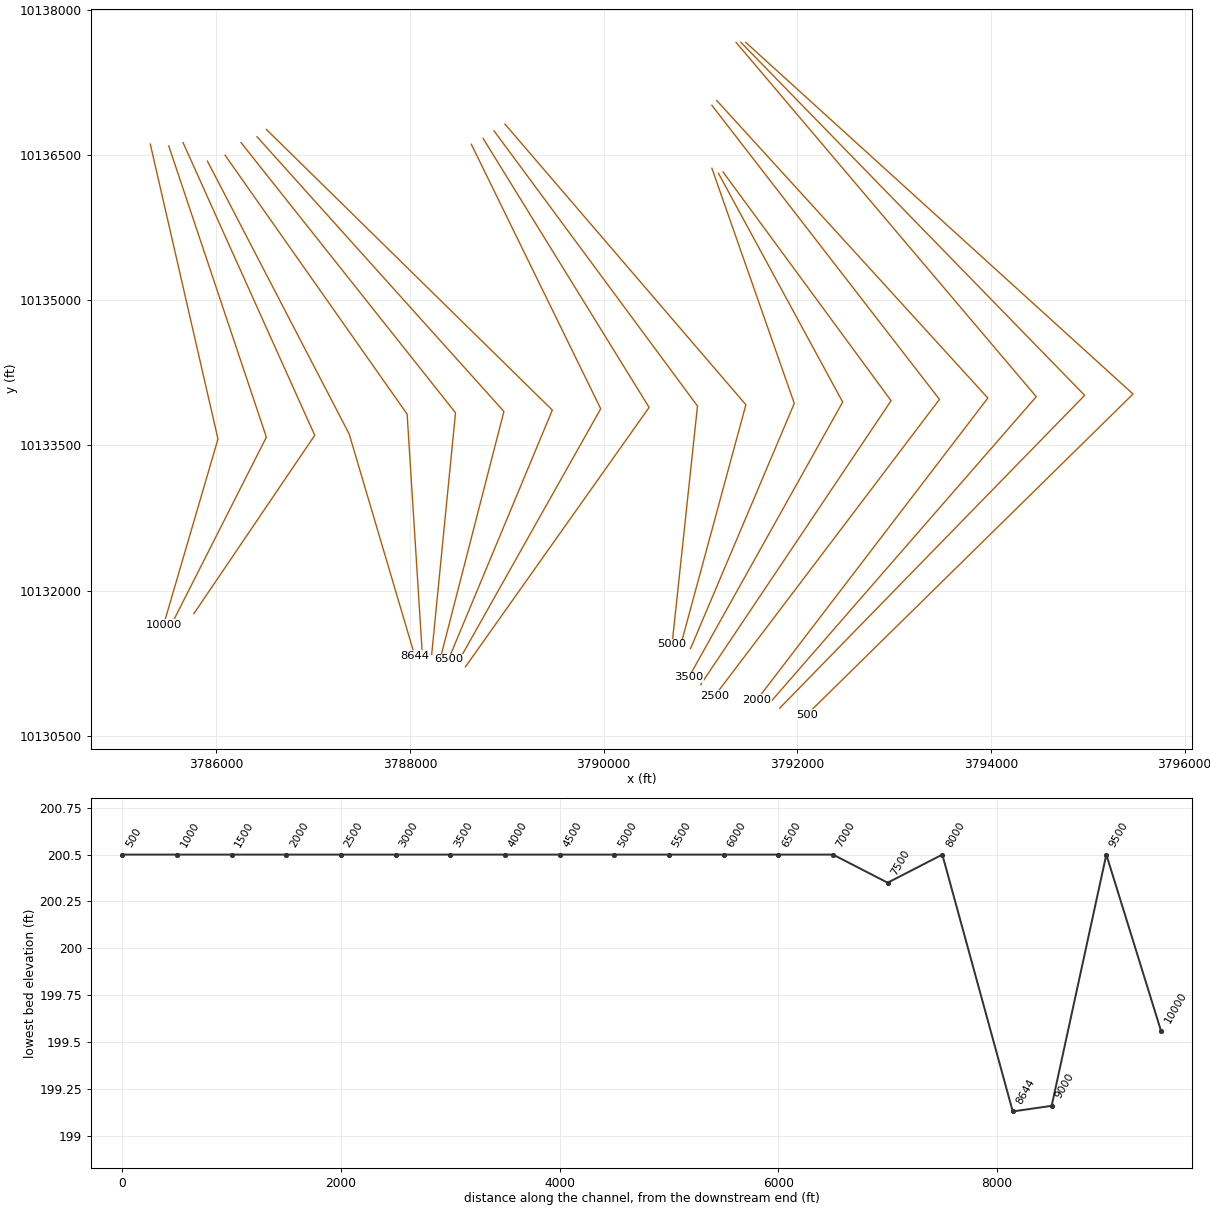
HEC-RAS study STEWART CREEK NORTH.prj: STEWART CREEK NORTH Base Level Engineering

--- STEWART CREEK NORTH.g01 (geometry) --- (continued)

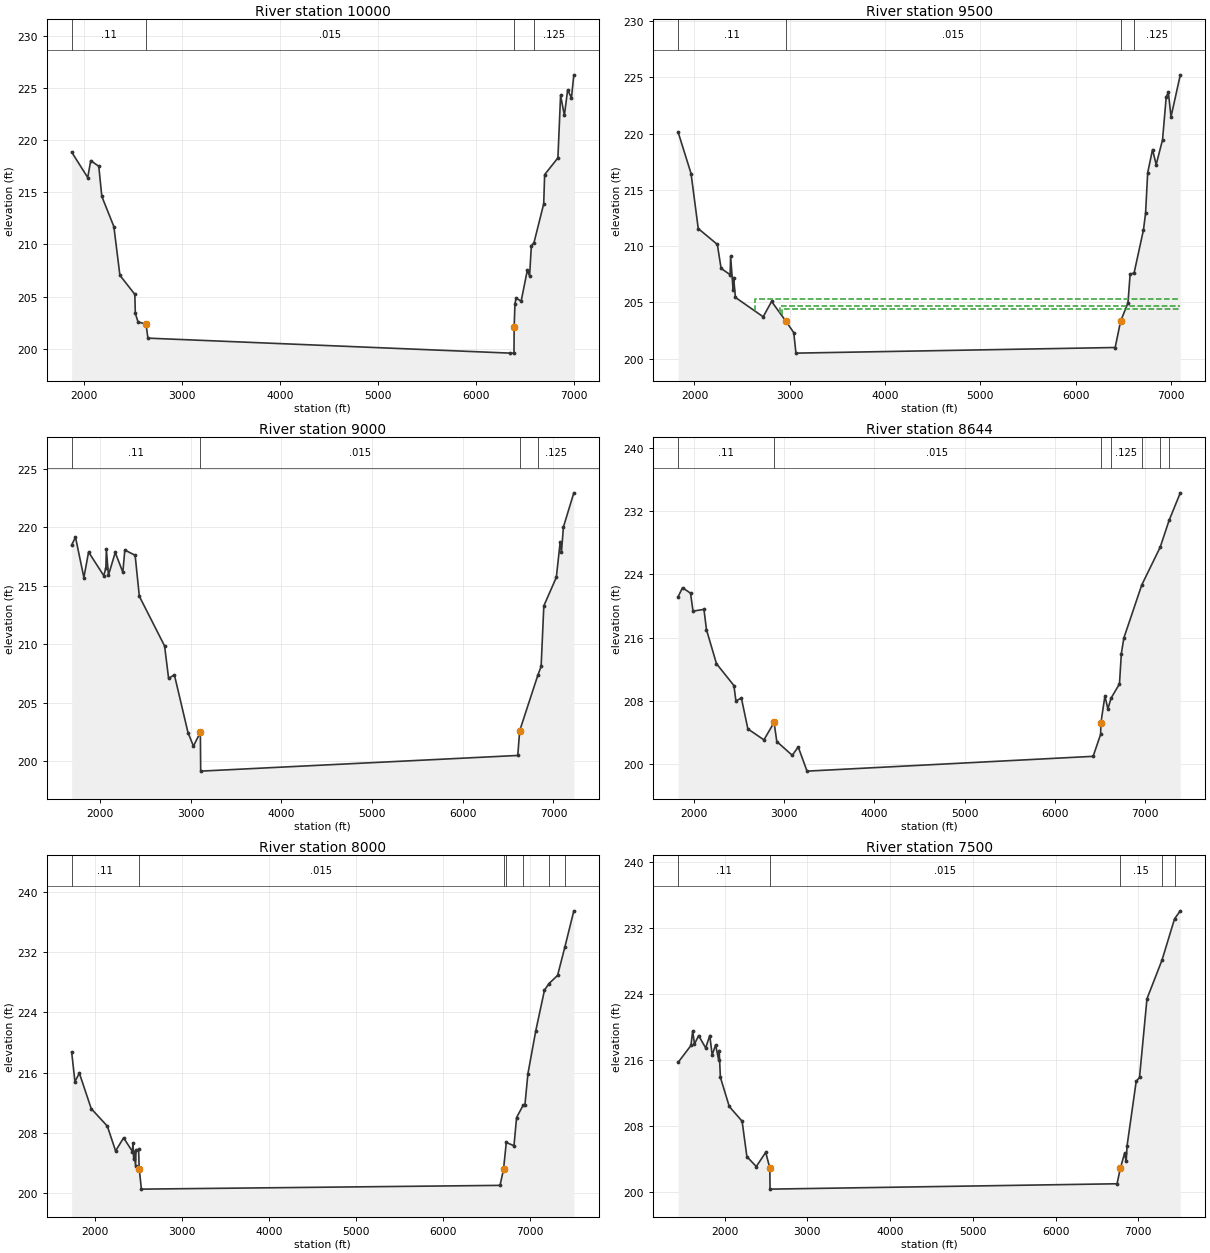
Type RM Length L Ch R = 1 ,10000   ,500,500,500
BEGIN DESCRIPTION:
STEWART CREEK NORTH 20.0
END DESCRIPTION:
XS GIS Cut Line= 3
      3785317.85     10136611.07      3786016.98     10133564.77
       3785455.2     10131645.08
#Sta/Elev= 30
  1874.5  218.88  2038.7  216.43  2069.4  218.06  2151.5  217.51  2182.3  214.62
  2305.4  211.72    2367  207.04  2519.2  205.21  2524.4  203.38  2551.7  202.57
  2633.7  202.33    2653     201  6352.3  199.56  6389.3  199.56 6391.08  202.05
  6399.1  204.27  6410.5  204.84  6462.6  204.56  6525.1  207.51  6548.4  206.98
  6566.8  209.89  6593.3  210.17  6692.6   213.9  6702.2  216.71  6837.7  218.32
  6864.9  224.34  6903.6   222.4    6937  224.86  6975.6  224.08  7000.2   226.3
#Mann= 4 ,-1 , 0
  1874.5     .11       0  2633.7    .015       0 6391.08     .15       0
  6593.3    .125       0
Bank Sta=2633.7,6391.08
XS Rating Curve= 0 ,0
Exp/Cntr=0.3,0.1

Type RM Length L Ch R = 1 ,9500    ,500,500,500
BEGIN DESCRIPTION:
STEWART CREEK NORTH 19.0
END DESCRIPTION:
XS GIS Cut Line= 3
      3785508.59     10136591.31      3786516.61     10133583.95
      3785567.84     10131711.05
#Sta/Elev= 30
  1828.2  220.14  1963.9  216.46  2039.4  211.57  2239.8  210.16  2279.4  208.03
  2374.1  207.47  2379.3  209.12  2405.6  206.07  2410.9  207.22  2429.6  205.45
  2721.1  203.73  2809.3  205.09    2957  203.37    3042  202.32    3065   200.5
  6415.7     201  6473.1  203.35  6550.2  204.96  6572.6  207.51  6614.6  207.63
  6712.5  211.44  6734.8  212.92    6757  216.52    6808  218.59  6846.1  217.25
  6912.9  219.45  6951.9  223.29  6974.2  223.67    7002   221.5  7099.5  225.23
#Mann= 4 ,-1 , 0
  1828.2     .11       0    2957    .015       0  6473.1     .15       0
  6614.6    .125       0
#XS Ineff= 4 ,-1
  2915.7  2893.7  204.42  2893.7  2830.4  204.66  2809.3  2631.8  205.09
  2631.8  2429.6  205.27
Permanent Ineff=
       F       F       F       F
Bank Sta=2957,6473.1
XS Rating Curve= 0 ,0
Exp/Cntr=0.3,0.1

Type RM Length L Ch R = 1 ,9000    ,356,356,356
BEGIN DESCRIPTION:
STEWART CREEK NORTH 18.0
END DESCRIPTION:
XS GIS Cut Line= 3
      3785656.16     10136626.05      3787016.24     10133603.13
      3785767.87      10131761.1
#Sta/Elev= 30
  1685.2  218.49  1727.5  219.16  1820.1  215.71  1871.9  217.89  2039.4  215.87
  2062.6  216.52    2068  218.11  2091.2  215.91  2166.1  217.85  2249.9  216.16
  2271.8  218.06  2385.5  217.61  2431.8  214.11  2710.5  209.86  2754.7  207.09
  2818.6  207.39  2968.5  202.46  3028.5   201.3  3105.2  202.48  3108.6  199.16
  6606.7   200.5  6627.7  202.61    6829  207.38  6864.3  208.11  6894.2  213.29
  7031.9  215.72    7074  218.71  7088.9  217.89  7109.9  220.02  7225.2  222.95
#Mann= 4 ,-1 , 0
  1685.2     .11       0  3105.2    .015       0  6627.7     .15       0
    6829    .125       0
Bank Sta=3105.2,6627.7
XS Rating Curve= 0 ,0
Exp/Cntr=0.3,0.1

Type RM Length L Ch R = 1 ,8644    ,644,644,644
BEGIN DESCRIPTION:
STEWART CREEK NORTH 2.0
END DESCRIPTION:
XS GIS Cut Line= 3
      3785907.87     10136435.13      3787371.84     10133616.78
      3788049.89     10131324.45
#Sta/Elev= 30
  1824.1  221.16  1873.2   222.3  1961.7   221.6  1989.4  219.34  2110.4  219.56
  2138.6  216.99  2249.2   212.7  2442.6  209.94  2464.7     208  2525.4  208.36
  2597.4  204.46  2775.2  203.08  2887.9  205.28  2917.8  202.87  3089.1  201.13
  3155.5  202.18  3253.1  199.13  6424.2     201  6507.6  203.79  6509.9  205.18
  6554.7  208.61  6587.9  206.99  6623.2  208.35  6716.2  210.15    6737  213.98
  6764.7  215.94  6963.1  222.64  7167.4  227.41  7266.2   230.8  7390.5  234.28
#Mann= 7 ,-1 , 0
  1824.1     .11       0  2887.9    .015       0  6509.9     .15       0
  6623.2    .125       0  6963.1     .11       0  7167.4    .125       0
  7266.2     .11       0
Bank Sta=2887.9,6509.9
XS Rating Curve= 0 ,0
Exp/Cntr=0.3,0.1

Type RM Length L Ch R = 1 ,8000    ,500,500,500
BEGIN DESCRIPTION:
STEWART CREEK NORTH 16.0
END DESCRIPTION:
XS GIS Cut Line= 3
      3786090.15     10136495.89       3787970.4       10133822.
      3788128.39     10131324.49
#Sta/Elev= 30
  1731.2  218.74  1769.2  214.79  1819.7  215.92  1956.5  211.19  2141.2  208.88
  2236.1  205.58  2328.5  207.32  2429.5   205.5  2435.7  206.67  2444.4  204.44
  2450.5  205.43  2465.3  203.62  2471.4  205.71    2501  205.77  2507.3  203.24
  2532.8   200.5  6654.2     201  6694.3  203.12  6726.1   206.7  6814.5  206.27
  6844.6  210.02  6922.9  211.72  6939.7  211.63  6974.9  215.85    7065  221.55
  7165.2  226.96    7217  227.83  7315.5  228.91  7400.3  232.73  7502.5   237.5
#Mann= 7 ,-1 , 0
  1731.2     .11       0  2507.3    .015       0  6694.3     .15       0
  6726.1    .125       0  6922.9     .11       0    7217    .125       0
  7400.3     .11       0
Bank Sta=2507.3,6694.3
XS Rating Curve= 0 ,0
Exp/Cntr=0.3,0.1

Type RM Length L Ch R = 1 ,7500    ,500,500,500
BEGIN DESCRIPTION:
STEWART CREEK NORTH 15.0
END DESCRIPTION:
XS GIS Cut Line= 3
       3786255.1     10136626.07       3788470.2     10133835.84
      3788223.98     10131340.15
#Sta/Elev= 30
  1437.4  215.73  1592.6  217.78  1613.4  219.55  1635.3  217.96  1685.6  218.98
  1770.5  217.48  1820.1  218.99    1849  216.63  1890.7  217.85  1927.5  216.02
  1933.9  217.17  1948.3  213.92  2055.7  210.38    2211  208.59  2268.7  204.29
  2382.5  203.09  2496.2  204.82  2545.9  202.91  2548.6  200.35  6743.2     201
  6783.4   202.9  6833.6  204.68  6853.7  203.71  6863.8  205.57  6974.3  213.41
  7014.8  213.92  7104.9  223.45  7286.9  228.15  7438.6  233.16  7507.8  234.12
#Mann= 5 ,-1 , 0
  1437.4     .11       0  2545.9    .015       0  6783.4     .15       0
  7286.9    .125       0  7438.6     .11       0
Bank Sta=2545.9,6783.4
XS Rating Curve= 0 ,0
Exp/Cntr=0.3,0.1

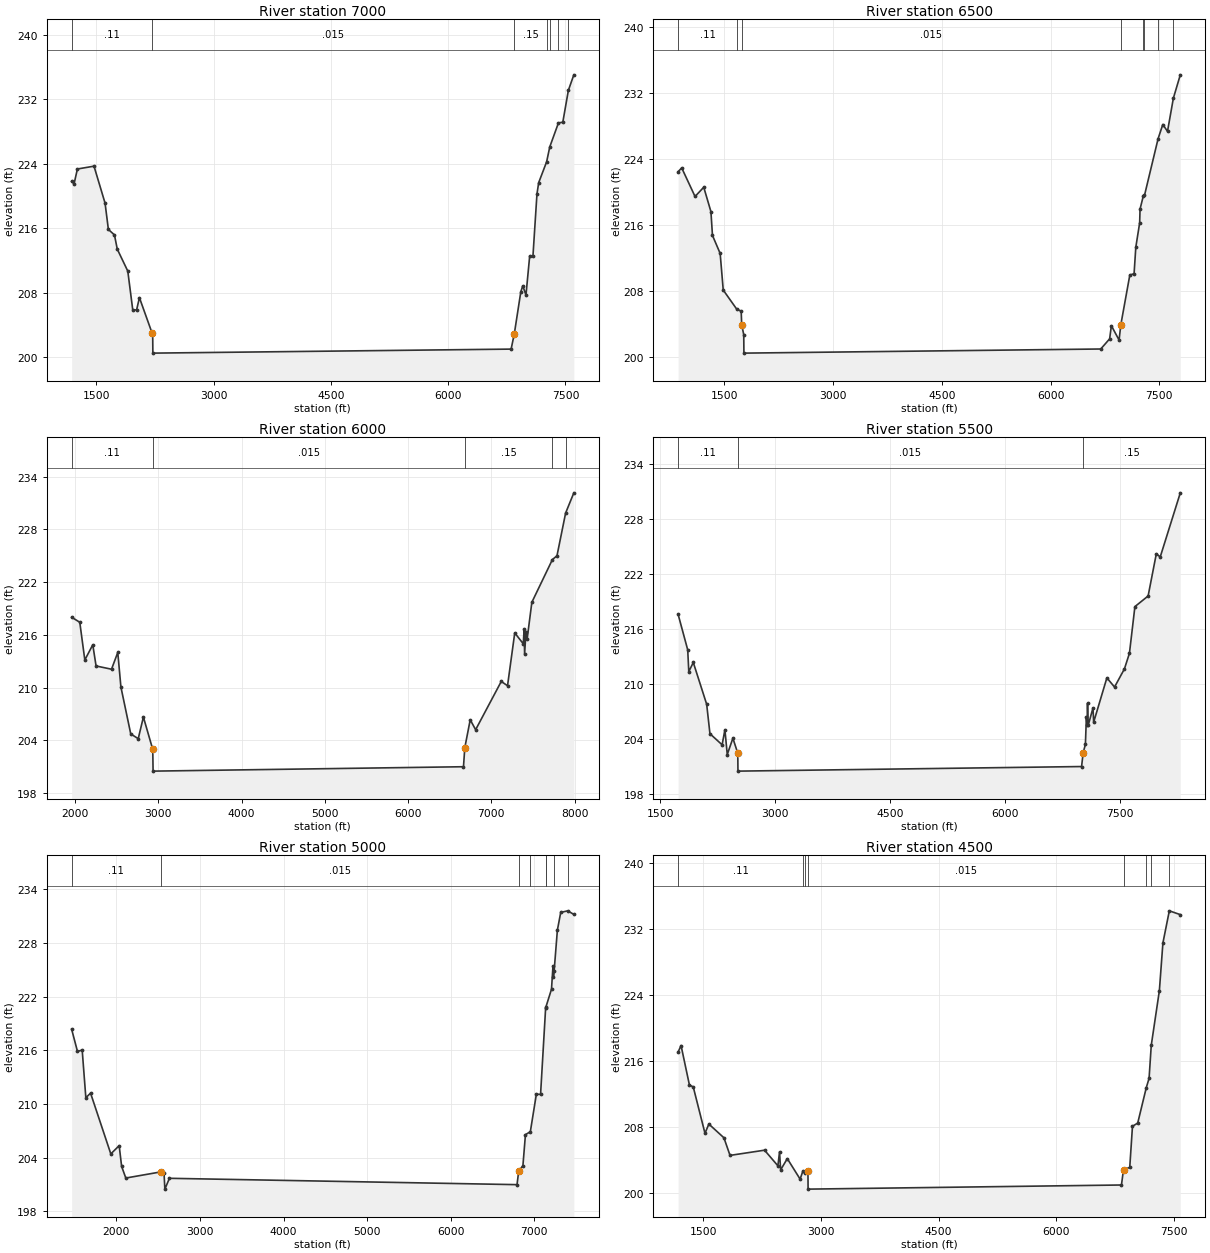
Type RM Length L Ch R = 1 ,7000    ,500,500,500
BEGIN DESCRIPTION:
STEWART CREEK NORTH 14.0
END DESCRIPTION:
XS GIS Cut Line= 3
      3786420.02     10136686.84      3788970.01     10133849.68
      3788319.88     10131324.43
#Sta/Elev= 30
  1185.3  221.81  1216.3   221.5  1258.9  223.34  1471.2  223.69  1612.5  219.11
  1655.1  215.84  1732.8  215.16  1768.7   213.4  1903.3  210.67  1966.8  205.86
  2016.1  205.86    2052  207.38  2214.9  202.96  2221.7  202.87  2223.9   200.5
  6805.6     201  6846.9  202.93  6929.5  208.11  6954.7  208.85  6995.4   207.7
  7043.1  212.56  7084.4  212.49  7136.1  220.25  7158.2  221.65  7259.6  224.23
  7299.8  226.08  7410.9  229.06  7466.5  229.14  7537.8   233.1  7607.6  235.02
#Mann= 7 ,-1 , 0
  1185.3     .11       0  2214.9    .015       0  6846.9     .15       0
  7259.6    .125       0  7299.8     .11       0  7410.9    .125       0
  7537.8     .11       0
Bank Sta=2214.9,6846.9
XS Rating Curve= 0 ,0
Exp/Cntr=0.3,0.1

Type RM Length L Ch R = 1 ,6500    ,500,500,500
BEGIN DESCRIPTION:
STEWART CREEK NORTH 13.0
END DESCRIPTION:
XS GIS Cut Line= 3
      3786517.86     10136761.07      3789469.82     10133863.53
       3788397.6     10131288.11
#Sta/Elev= 30
   863.6  222.45   913.1  222.91    1097  219.45  1217.1  220.57  1316.1  217.62
  1337.4  214.74  1443.4  212.56  1485.9  208.13  1674.5  205.79  1733.3  205.59
  1740.5  203.94  1768.7  202.73  1771.1   200.5  6692.5     201  6815.2  202.23
    6839  203.82  6945.2  202.08  6969.1  203.92  7093.2  209.94  7152.2  210.11
  7176.1  213.32  7229.1  216.26  7234.6  217.93  7278.6  219.48  7295.7  219.58
  7483.7  226.45  7548.2  228.16  7613.2  227.33    7694  231.34  7789.7  234.17
#Mann= 8 ,-1 , 0
   863.6     .11       0  1674.5    .125       0  1740.5    .015       0
  6969.1     .15       0  7278.6    .125       0  7295.7     .11       0
  7483.7    .125       0    7694     .11       0
Bank Sta=1740.5,6969.1
XS Rating Curve= 0 ,0
Exp/Cntr=0.3,0.1

Type RM Length L Ch R = 1 ,6000    ,500,500,500
BEGIN DESCRIPTION:
STEWART CREEK NORTH 12.0
END DESCRIPTION:
XS GIS Cut Line= 3
      3788633.57     10136608.71      3789969.63     10133877.37
      3788502.31     10131271.71
#Sta/Elev= 30
  1959.4     218    2057  217.43  2117.6  213.14  2213.2  214.87  2252.7  212.46
  2438.3  212.09  2513.4     214  2550.9  210.07  2669.2  204.73  2759.1  204.19
    2821  206.65  2933.6  202.96  2937.3   200.5  6665.1     201    6681  203.17
    6746  206.34    6811  205.21  7118.9   210.7    7194  210.21  7280.7  216.22
  7383.3  214.98  7393.4  216.62  7399.2  213.82  7415.1   216.3  7428.8  215.47
  7486.2   219.7    7733  224.56  7787.9  224.99  7891.6  229.85  7990.4  232.15
#Mann= 5 ,-1 , 0
  1959.4     .11       0  2933.6    .015       0    6681     .15       0
    7733    .125       0  7891.6     .11       0
Bank Sta=2933.6,6681
XS Rating Curve= 0 ,0
Exp/Cntr=0.3,0.1

Type RM Length L Ch R = 1 ,5500    ,500,500,500
BEGIN DESCRIPTION:
STEWART CREEK NORTH 11.0
END DESCRIPTION:
XS GIS Cut Line= 3
      3788755.11     10136669.47      3790469.44     10133891.22
      3788572.05     10131211.18
#Sta/Elev= 30
  1735.4   217.6  1860.7  213.72  1874.5  211.35  1933.3  212.35  2107.8  207.79
  2150.4  204.58  2309.3  203.37  2345.5  205.02  2376.2  202.31  2449.6  204.09
  2513.4  202.45  2515.7   200.5  6996.4     201  7017.3  202.52  7046.3  203.41
  7059.1  206.38  7067.8  205.54  7073.9  207.89  7082.6  205.49  7145.3   207.4
  7153.9  205.84  7326.2  210.67  7426.2  209.67  7555.1  211.65  7620.4  213.35
  7691.7  218.44    7864   219.6  7971.1  224.21  8021.6  223.85  8283.7  230.85
#Mann= 3 ,-1 , 0
  1735.4     .11       0  2513.4    .015       0  7017.3     .15       0
Bank Sta=2513.4,7017.3
XS Rating Curve= 0 ,0
Exp/Cntr=0.3,0.1

Type RM Length L Ch R = 1 ,5000    ,500,500,500
BEGIN DESCRIPTION:
STEWART CREEK NORTH 10.0
END DESCRIPTION:
XS GIS Cut Line= 3
      3788867.94     10136747.61      3790969.25     10133905.06
      3790706.72     10131445.23
#Sta/Elev= 30
  1465.1  218.37  1534.9  215.89  1591.2  216.05  1634.9  210.72  1691.4  211.23
  1933.6  204.44  2033.8  205.36    2063  203.04  2113.1  201.74  2534.8  202.43
  2570.3  202.28  2580.5   200.5    2635  201.71  6794.1     201  6814.2  202.52
  6864.5  203.12  6894.7  206.59  6953.3  206.92  7025.4  211.11  7075.7  211.09
  7136.3  220.75  7138.4  220.82  7206.5  222.85  7224.5  225.47  7229.6  224.26
  7237.7  224.85  7276.8  229.45  7316.9  231.43  7400.8  231.61  7473.8  231.21
#Mann= 8 ,-1 , 0
  1465.1     .11       0  2534.8    .015       0  6814.2     .15       0
  6953.3    .125       0  7136.3     .11       0  7138.4    .125       0
  7237.7     .17       0  7400.8     .11       0
Bank Sta=2534.8,6814.2
XS Rating Curve= 0 ,0
Exp/Cntr=0.3,0.1

Type RM Length L Ch R = 1 ,4500    ,500,500,500
BEGIN DESCRIPTION:
STEWART CREEK NORTH 9.0
END DESCRIPTION:
XS GIS Cut Line= 3
      3788980.77     10136817.07      3791469.05     10133918.91
      3790793.42     10131426.97
#Sta/Elev= 30
  1180.2  217.08  1217.6  217.87    1324  213.11  1373.4  212.85  1522.7  207.25
    1572  208.37  1764.1  206.71    1842  204.58    2282  205.21  2452.2  203.32
    2473     205  2487.3  202.83    2572  204.19  2735.3  201.71  2770.3  202.67
  2797.2  202.42  2835.2   202.7    2837   200.5  6831.7     201  6857.8  202.86
  6937.4  203.12  6972.1   208.1  7038.9  208.49  7148.5  212.78  7183.9   213.9
  7211.6  217.89    7315   224.5  7360.1  230.27  7441.9  234.16  7581.9   233.7
#Mann= 8 ,-1 , 0
  1180.2     .11       0  2770.3    .125       0  2797.2     .11       0
  2835.2    .015       0  6857.8     .15       0  7148.5    .125       0
  7211.6     .17       0  7441.9     .11       0
Bank Sta=2835.2,6857.8
XS Rating Curve= 0 ,0
Exp/Cntr=0.3,0.1

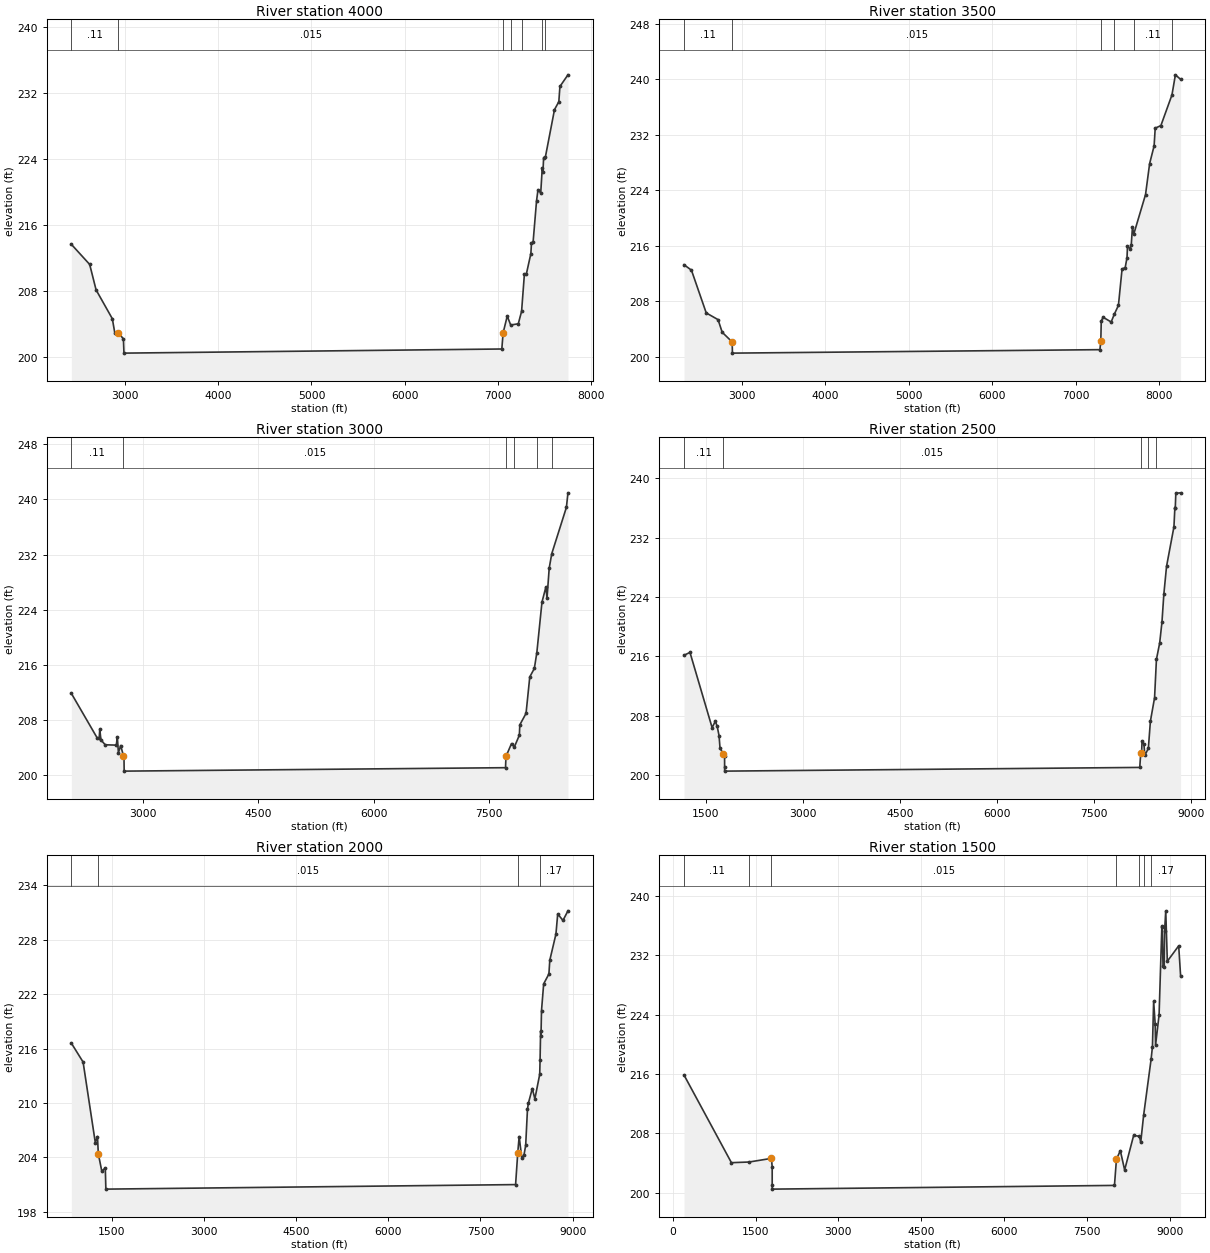
Type RM Length L Ch R = 1 ,4000    ,500,500,500
BEGIN DESCRIPTION:
STEWART CREEK NORTH 8.0
END DESCRIPTION:
XS GIS Cut Line= 3
      3791117.86     10136361.05      3791968.86     10133932.75
       3790897.6     10131400.97
#Sta/Elev= 30
  2426.9  213.66  2623.2  211.23  2691.8  208.15    2866  204.66  2891.7  202.99
    2928  202.98  2984.7  202.23  2990.6   200.5  7040.3     201  7054.1  202.94
  7098.5  204.98  7135.3   203.9  7216.9  204.05  7252.2  205.56  7282.1  210.02
  7304.3  210.12  7351.7  212.55  7358.1   213.8  7375.4  213.91  7412.4  218.92
  7428.2  220.28  7457.3  219.87  7473.5  222.86    7481  222.37  7488.4  224.16
  7506.9  224.21  7604.9  229.96  7651.3  230.92  7663.1  232.76  7749.1  234.17
#Mann= 7 ,-1 , 0
  2426.9     .11       0    2928    .015       0  7054.1     .15       0
  7135.3    .125       0  7252.2     .11       0  7473.5     .17       0
  7506.9     .11       0
Bank Sta=2928,7054.1
XS Rating Curve= 0 ,0
Exp/Cntr=0.3,0.1

Type RM Length L Ch R = 1 ,3500    ,500,500,500
BEGIN DESCRIPTION:
STEWART CREEK NORTH 7.0
END DESCRIPTION:
XS GIS Cut Line= 3
      3791185.65     10136309.31      3792468.67      10133946.6
      3790880.29     10131105.92
#Sta/Elev= 30
  2311.4  213.25  2400.4  212.47  2577.4   206.3    2719  205.33  2768.4  203.51
  2888.2  202.11  2890.8   200.5  7289.2     201 7299.82  202.28  7305.1   205.1
  7326.8  205.68  7423.8  204.99  7460.7  206.09  7510.7  207.39  7554.1  212.62
  7591.8  212.85  7613.5  214.28  7619.2  215.95  7651.2  215.51  7664.4  216.13
  7678.6  218.72  7693.8  217.65    7835  223.37  7884.2  227.85  7937.8   230.4
  7950.8  232.95  8018.9  233.33  8151.3  237.75  8192.5  240.65  8254.6     240
#Mann= 6 ,-1 , 0
  2311.4     .11       0  2888.2    .015       0 7299.82     .15       0
  7460.7    .125       0  7693.8     .11       0  8151.3     .17       0
Bank Sta=2888.2,7299.82
XS Rating Curve= 0 ,0
Exp/Cntr=0.3,0.1

Type RM Length L Ch R = 1 ,3000    ,500,500,500
BEGIN DESCRIPTION:
STEWART CREEK NORTH 6.0
END DESCRIPTION:
XS GIS Cut Line= 3
      3791233.07     10136322.83      3792968.48     10133960.44
      3791002.29     10131028.48
#Sta/Elev= 30
  2068.7   211.8  2402.9  205.36  2430.7  205.25  2438.4  206.61  2453.1  205.04
  2509.4  204.33  2653.7  204.28  2666.5   205.5  2680.7  203.17    2710  204.22
  2745.6  202.77  2753.3  202.56  2755.7   200.5  7717.8     201  7723.8  202.63
  7795.8  204.51  7833.9  204.04  7897.9  205.73  7903.9  207.23  7984.9   208.9
  8033.4   214.2  8092.9  215.43  8125.3  217.73    8192  225.06    8243  227.28
    8258  225.68  8286.3  230.02  8319.7  232.13  8510.1  238.86  8530.2  240.97
#Mann= 6 ,-1 , 0
  2068.7     .11       0  2745.6    .015       0  7723.8     .15       0
  7833.9    .125       0  8125.3     .11       0  8319.7     .17       0
Bank Sta=2745.6,7723.8
XS Rating Curve= 0 ,0
Exp/Cntr=0.3,0.1

Type RM Length L Ch R = 1 ,2500    ,500,500,500
BEGIN DESCRIPTION:
STEWART CREEK NORTH 5.0
END DESCRIPTION:
XS GIS Cut Line= 3
      3791117.87     10137011.05      3793468.29     10133974.29
       3791149.8     10130915.46
#Sta/Elev= 30
  1159.9  216.14  1252.2  216.52  1594.5  206.37  1644.3  207.23  1673.3  206.54
  1702.2  205.27  1716.3  203.64  1766.5  202.81  1787.3  202.57  1787.8     201
  1788.8   200.5  8207.1     201  8221.6  202.91  8236.2  203.07  8242.4  204.58
  8271.5  204.11  8286.1  202.62  8339.9  203.58  8371.4  207.23  8435.9   210.4
  8464.7  215.58  8514.9  217.79  8550.3  220.62  8579.4  224.39    8621  228.13
  8735.4  233.47    8750  236.07  8756.3  236.02  8764.5     238  8838.2  238.06
#Mann= 5 ,-1 , 0
  1159.9     .11       0  1766.5    .015       0  8221.6     .15       0
  8339.9     .11       0  8464.7     .17       0
Bank Sta=1766.5,8221.6
XS Rating Curve= 0 ,0
Exp/Cntr=0.3,0.1

Type RM Length L Ch R = 1 ,2000    ,500,500,500
BEGIN DESCRIPTION:
STEWART CREEK NORTH 4.0
END DESCRIPTION:
XS GIS Cut Line= 3
      3791167.88     10137061.04      3793968.09     10133988.13
      3791583.34     10130871.42
#Sta/Elev= 30
   842.6  216.59  1033.4  214.51  1232.1  205.63  1267.2   206.3  1281.4  204.38
  1338.1  202.47  1394.9  202.84  1403.9   200.5  8072.2     201  8107.5  204.51
  8130.3   206.3  8171.9  203.98  8207.3  204.21  8236.3  205.31  8265.4  209.28
  8279.9  209.96  8344.3  211.59  8385.9  210.45  8464.8  213.15  8470.8  214.78
  8479.4  217.92  8485.7  217.43  8493.9  220.17  8529.2  223.13  8614.4  224.22
    8629  225.74  8728.7  228.61  8757.8  230.84    8843  230.12  8924.4  231.18
#Mann= 4 ,-1 , 0
   842.6     .11       0  1281.4    .015       0  8107.5     .17       0
  8470.8     .17       0
Bank Sta=1281.4,8107.5
XS Rating Curve= 0 ,0
Exp/Cntr=0.3,0.1

Type RM Length L Ch R = 1 ,1500    ,500,500,500
BEGIN DESCRIPTION:
STEWART CREEK NORTH 3.0
END DESCRIPTION:
XS GIS Cut Line= 3
      3791367.82      10137661.1       3794467.9     10134001.98
      3791713.54     10130836.69
#Sta/Elev= 30
   204.2  215.86  1062.8  204.06  1383.9  204.15  1786.7  204.64    1801  203.51
  1801.2     201  1802.2   200.5  7998.6     201  8034.7  204.52  8104.9  205.68
  8182.8  203.08  8346.1  207.73  8450.6  207.61  8474.3  206.81  8527.1  210.47
  8661.9  217.97  8686.4  219.67  8707.9  225.79  8736.3  222.66    8743   219.9
  8806.6  223.96  8856.9  235.93  8863.6  235.73  8877.8  230.53  8898.7  230.42
  8906.3  235.24  8927.2  237.96  8955.7  231.17  9161.7  233.25  9195.9  229.24
#Mann= 7 ,-1 , 0
   204.2     .11       0  1383.9    .125       0  1786.7    .015       0
  8034.7     .17       0  8450.6    .125       0  8527.1     .11       0
  8661.9     .17       0
Bank Sta=1786.7,8034.7
XS Rating Curve= 0 ,0
Exp/Cntr=0.3,0.1

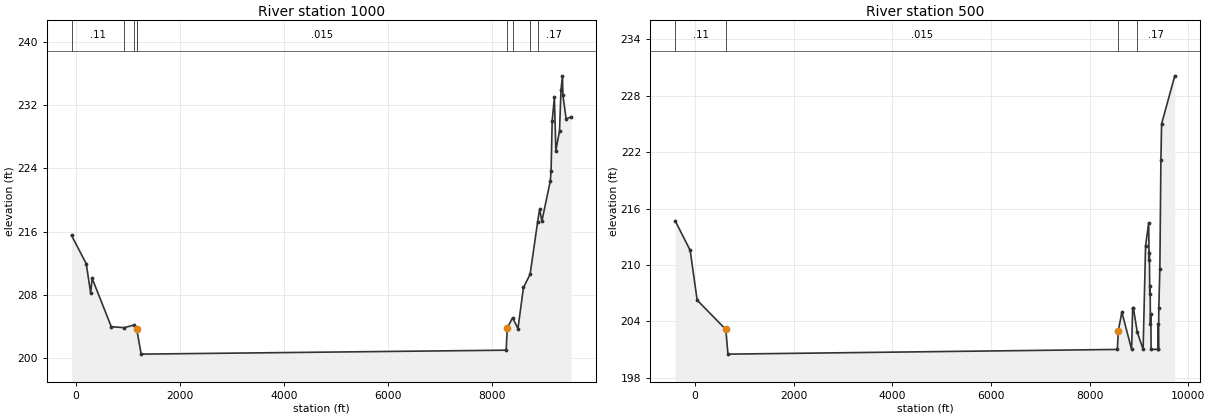
Type RM Length L Ch R = 1 ,1000    ,500,500,500
BEGIN DESCRIPTION:
STEWART CREEK NORTH 2.5
END DESCRIPTION:
XS GIS Cut Line= 3
      3791417.82      10137661.1      3794967.71     10134015.82
      3791818.45     10130785.37
#Sta/Elev= 30
   -88.2  215.52   194.7  211.94   279.5  208.23   307.8  210.09   675.6  203.97
   923.6  203.85  1110.9  204.17  1160.8  203.68  1163.6  203.71  1249.9   200.5
  8263.2     201  8284.5  203.82  8386.6   205.1  8489.6  203.74  8595.7  208.93
  8723.6  210.61  8866.3  217.18  8906.8  218.84  8949.2  217.32    9112  222.43
  9126.1  223.71  9147.2  230.01  9189.7  232.98    9218  226.24  9288.7  228.77
    9317  233.97  9345.3  235.71  9352.3  233.29    9416  230.26  9511.5  230.52
#Mann= 9 ,-1 , 0
   -88.2     .11       0   923.6    .125       0  1110.9     .11       0
  1160.8    .125       0  1163.6    .015       0  8284.5     .17       0
  8386.6    .125       0  8723.6     .11       0  8866.3     .17       0
Bank Sta=1163.6,8284.5
XS Rating Curve= 0 ,0
Exp/Cntr=0.3,0.1

Type RM Length L Ch R = 1 ,500     ,0,0,0
BEGIN DESCRIPTION:
STEWART CREEK NORTH 1.0
END DESCRIPTION:
XS GIS Cut Line= 3
      3791467.82      10137661.1      3795467.52     10134029.67
      3792095.96     10130715.64
#Sta/Elev= 30
  -402.3   214.7   -97.8  211.55    43.5  206.25   624.3  203.13   668.4   200.5
  8562.7     201    8584     203  8654.7  204.98  8852.7     201  8873.8  205.41
    8888  205.42  8967.9  202.83    9086     201  9135.6  212.03  9199.1  214.48
  9206.2  210.57  9213.3  211.32  9220.3   206.9  9227.4   207.8  9234.4  203.74
  9241.6  204.75  9248.6     201    9383  201.01    9390  203.74  9397.2  201.01
  9404.2  205.41  9425.4  209.61  9446.6  221.13  9460.7  225.02  9727.6  230.13
#Mann= 4 ,-1 , 0
  -402.3     .11       0   624.3    .015       0    8584     .17       0
  8967.9     .17       0
#XS Ineff= 2 , 0
       0                  8654.7       0  204.98
Permanent Ineff=
       F       F
Bank Sta=624.3,8584
XS Rating Curve= 0 ,0
Exp/Cntr=0.3,0.1

Chan Stop Cuts=-1
Use User Specified Reach Order=0
Composite Channel Slope=5