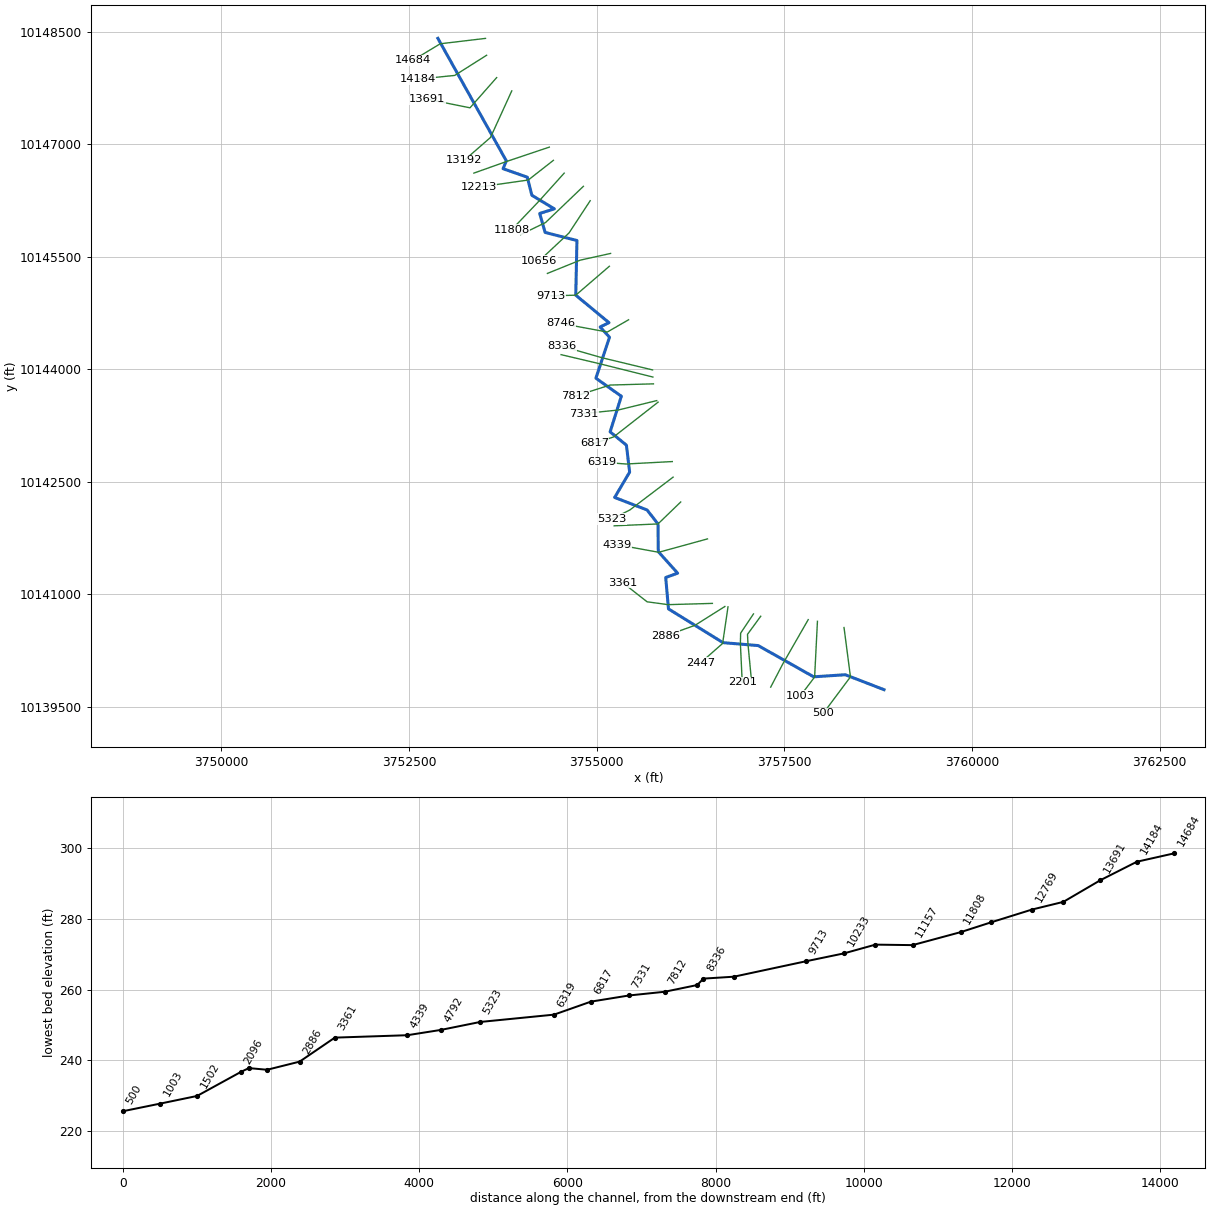
--- TOWN CREEK TRIBUTARY NO 1.prj (project) ---

Proj Title=TOWN CREEK TRIBUTARY NO 1 Base Level Engineering
Current Plan=p01
Default Exp/Contr=0.3,0.1
English Units
Geom File=g01
Flow File=f01
Plan File=p01
Y Axis Title=Elevation
X Axis Title(PF)=Main Channel Distance
X Axis Title(XS)=Station
BEGIN DESCRIPTION:
TOWN CREEK TRIBUTARY NO 1
END DESCRIPTION:
DSS Export Rating Curves= 0
DSS Export Rating Curve Sorted= 0
DSS Export Volume Flow Curves= 0
DXF OffsetX= 0
DXF OffsetY= 0
DXF ScaleX= 1
DXF ScaleY= 10

--- TOWN CREEK TRIBUTARY NO 1.p01 (plan) ---

Plan Title=Multiple Run
Short Identifier=Multiple
Geom File=g01
Flow File=f01
Subcritical Flow
K Sum by GR= 0
Std Step Tol= 0.01
Critical Tol= 0.01
Num of Std Step Trials= 20
Max Error Tol= 0.3
Flow Tol Ratio= 0.001
Split Flow NTrial= 30
Split Flow Tol= 0.02
Split Flow Ratio= 0.02
Log Output Level= 0
Friction Slope Method= 1
Unsteady Friction Slope Method= 2
Unsteady Bridges Friction Slope Method= 1
Parabolic Critical Depth
Global Vel Dist=  1 , 1 , 1
Global Log Level= 0
CheckData=True
Encroach Param= -1, 0, 0, 0
BEGIN DESCRIPTION:
Multiple Run
END DESCRIPTION:

--- TOWN CREEK TRIBUTARY NO 1.f01 (steady flow) ---

Flow Title=Multiple
Program Version=4.10
Number of Profiles= 7
Profile Names=10-year,25-year,50-year,1pct_min,100-year,1pct_plu,500-year
River Rch & RM=TOWN CREEK TRIBU,Reach-1         ,14684
     177     220     281     119     359    1084     600
River Rch & RM=TOWN CREEK TRIBU,Reach-1         ,13691
     478     631     841     368    1110    3352    2006
River Rch & RM=TOWN CREEK TRIBU,Reach-1         ,6319
     655     883    1191     528    1594    4814    2950
Boundary for River Rch & Prof#=TOWN CREEK TRIBU,Reach-1         , 1
Up Type= 0
Dn Type= 3
Dn Slope=0.005
Boundary for River Rch & Prof#=TOWN CREEK TRIBU,Reach-1         , 2
Up Type= 0
Dn Type= 3
Dn Slope=0.005
Boundary for River Rch & Prof#=TOWN CREEK TRIBU,Reach-1         , 3
Up Type= 0
Dn Type= 3
Dn Slope=0.005
Boundary for River Rch & Prof#=TOWN CREEK TRIBU,Reach-1         , 4
Up Type= 0
Dn Type= 3
Dn Slope=0.005
Boundary for River Rch & Prof#=TOWN CREEK TRIBU,Reach-1         , 5
Up Type= 0
Dn Type= 3
Dn Slope=0.005
Boundary for River Rch & Prof#=TOWN CREEK TRIBU,Reach-1         , 6
Up Type= 0
Dn Type= 3
Dn Slope=0.005
Boundary for River Rch & Prof#=TOWN CREEK TRIBU,Reach-1         , 7
Up Type= 0
Dn Type= 3
Dn Slope=0.005
DSS Import GetInterval= 0
DSS Import GetPeak= 0
DSS Import FillOption= 0

--- TOWN CREEK TRIBUTARY NO 1.g01 (geometry) ---

Geom Title=Existing Conditions
Program Version=4.10

River Reach=TOWN CREEK TRIBU,Reach-1
Reach XY= 30
      3752883.23     10148411.84      3753795.65      10146777.6
      3753751.98     10146673.69      3754074.62     10146560.79
      3754136.03     10146318.96      3754435.33     10146138.25
      3754240.18     10146076.91      3754312.33     10145823.68
      3754736.31     10145716.05      3754720.69     10144987.07
       3755163.4     10144620.75      3755045.35     10144563.46
      3755170.35     10144426.31      3754988.91     10143880.06
      3755328.02     10143639.79      3755178.42     10143164.74
      3755395.49     10142987.64      3755438.44     10142628.08
      3755238.96     10142290.11       3755670.5     10142123.11
       3755816.2     10141936.94      3755820.14     10141567.62
      3756078.06     10141280.65      3755918.98     10141222.83
      3755956.04     10140804.07      3756682.44     10140354.05
      3757151.35     10140315.08      3757889.86     10139898.62
      3758312.05     10139926.15      3758828.23     10139726.84

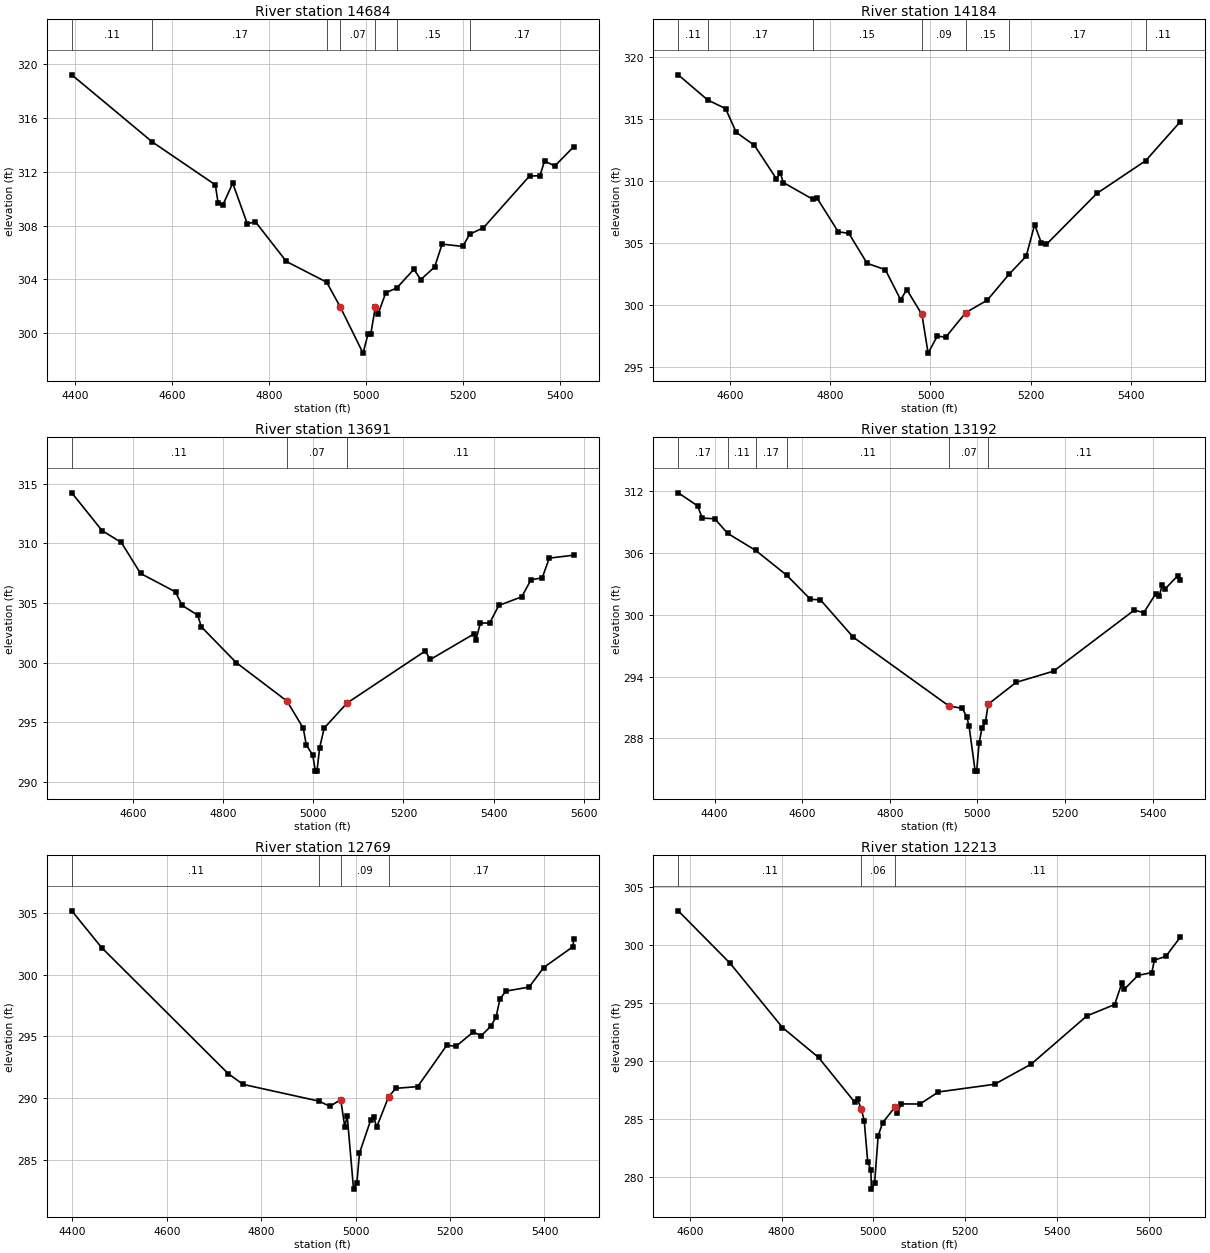
Type RM Length L Ch R = 1 ,14684   ,500,500,500
BEGIN DESCRIPTION:
TOWN CREEK TRIBUTARY NO 1 26.0
END DESCRIPTION:
XS GIS Cut Line= 3
      3753517.84     10148411.07        3752915.     10148339.28
      3752547.33     10148117.07
#Sta/Elev= 30
  4392.9  319.22  4559.4  314.22  4689.4  311.03    4695  309.69  4705.1  309.55
  4725.2  311.16  4755.4  308.13    4772  308.29    4836  305.33  4919.2  303.79
  4947.2  301.95  4994.3  298.51  5004.4   299.9  5010.2  299.91  5019.9  301.97
  5025.7  301.45  5041.2     303    5064  303.36  5099.4  304.75  5113.5  303.98
  5142.1  304.92  5157.6  306.62  5200.3  306.45  5214.5  307.36    5243  307.84
  5338.1  311.69  5359.5  311.71  5369.1   312.8  5390.5  312.44  5429.6  313.88
#Mann= 7 ,-1 , 0
  4392.9     .11       0  4559.4     .17       0  4919.2     .11       0
  4947.2     .07       0  5019.9     .11       0    5064     .15       0
  5214.5     .17       0
Bank Sta=4947.2,5019.9
XS Rating Curve= 0 ,0
Exp/Cntr=0.3,0.1

Type RM Length L Ch R = 1 ,14184   ,493,493,493
BEGIN DESCRIPTION:
TOWN CREEK TRIBUTARY NO 1 25.0
END DESCRIPTION:
XS GIS Cut Line= 3
      3753533.04     10148186.36      3753107.91     10147917.34
      3752612.08     10147866.75
#Sta/Elev= 30
  4496.9  318.55  4555.5  316.53  4591.4  315.83  4612.6  313.92    4649  312.87
  4692.4   310.2  4700.7  310.61  4706.6  309.88    4765  308.54  4773.6  308.64
    4816  305.92  4837.2  305.79  4873.6  303.38  4910.1  302.86  4940.6  300.44
  4952.7  301.27    4983  299.26  4995.3  296.15  5013.8  297.53  5030.2  297.42
  5070.4  299.41  5113.3  300.41  5156.8   302.5    5191  303.95  5207.8  306.49
  5221.2  305.02  5231.2   304.9  5331.8     309  5429.4  311.64  5498.4  314.78
#Mann= 7 ,-1 , 0
  4496.9     .11       0  4555.5     .17       0    4765     .15       0
    4983     .09       0  5070.4     .15       0  5156.8     .17       0
  5429.4     .11       0
Bank Sta=4983,5070.4
XS Rating Curve= 0 ,0
Exp/Cntr=0.3,0.1

Type RM Length L Ch R = 1 ,13691   ,499,499,499
BEGIN DESCRIPTION:
TOWN CREEK TRIBUTARY NO 1 24.0
END DESCRIPTION:
XS GIS Cut Line= 3
       3753666.2     10147887.98      3753311.34     10147485.34
      3752744.45     10147600.14
#Sta/Elev= 30
  4463.3  314.23  4530.7  311.06  4573.4  310.07    4616  307.48  4693.8  305.93
  4708.1  304.81  4743.2  303.98  4750.7  303.02  4828.5  300.01  4941.5  296.78
  4977.5  294.51  4984.1  293.12  4998.4  292.27  5004.4  290.92  5007.9  290.92
  5013.8  292.88    5024  294.53    5075  296.63  5248.4  300.98  5259.7  300.27
    5356   302.4  5361.1  301.94  5370.9  303.33  5391.3  303.32  5411.8   304.8
  5462.7  305.52  5483.1  306.94  5508.1  307.11  5523.9  308.76  5578.4  309.01
#Mann= 3 , 0 , 0
  4463.3     .11       0  4941.5     .07       0    5075     .11       0
Bank Sta=4941.5,5075
XS Rating Curve= 0 ,0
Exp/Cntr=0.3,0.1

Type RM Length L Ch R = 1 ,13192   ,423,423,423
BEGIN DESCRIPTION:
TOWN CREEK TRIBUTARY NO 1 23.0
END DESCRIPTION:
XS GIS Cut Line= 3
      3753867.86     10147711.08       3753584.4      10147089.9
      3753235.19     10146785.58
#Sta/Elev= 30
  4317.2  311.86  4361.2   310.6  4372.1   309.4  4400.6  309.34  4429.9  307.92
    4494  306.26    4565  303.84  4618.9  301.51  4641.9  301.45  4716.5  297.83
  4934.9  291.14  4965.7   290.9  4975.4  290.11  4980.9  289.22  4994.9   284.8
  4998.4   284.8  5003.9  287.52  5010.6  289.01  5018.2  289.53  5024.8  291.31
  5088.4  293.43  5173.9  294.52    5358  300.45  5379.9  300.21  5407.4  302.07
    5415  301.84  5421.7  302.85  5429.3  302.55  5457.7  303.82  5463.2  303.36
#Mann= 6 ,-1 , 0
  4317.2     .17       0  4429.9     .11       0    4494     .17       0
    4565     .11       0  4934.9     .07       0  5024.8     .11       0
Bank Sta=4934.9,5024.8
XS Rating Curve= 0 ,0
Exp/Cntr=0.3,0.1

Type RM Length L Ch R = 1 ,12769   ,556,556,556
BEGIN DESCRIPTION:
TOWN CREEK TRIBUTARY NO 1 22.0
END DESCRIPTION:
XS GIS Cut Line= 3
      3754367.82     10146961.06      3753798.09     10146769.73
      3753362.68     10146614.67
#Sta/Elev= 30
    4399  305.16  4462.3  302.18    4730  291.99  4761.6  291.11    4923  289.75
  4945.5  289.33  4968.6  289.87    4977  287.69  4982.3  288.54  4995.7  282.63
  5002.8  283.13  5008.2  285.54  5032.1  288.23  5039.1  288.46  5044.4  287.63
  5069.9   290.1  5085.2  290.79  5131.5  290.93  5193.2  294.28  5212.6  294.19
  5249.5  295.36  5265.6  295.03  5286.9  295.84  5297.5  296.57  5305.9  298.05
  5318.7  298.66  5367.5  298.99  5398.4  300.57    5460  302.25  5462.2  302.88
#Mann= 4 ,-1 , 0
    4399     .11       0    4923     .17       0  4968.6     .09       0
  5069.9     .17       0
Bank Sta=4968.6,5069.9
XS Rating Curve= 0 ,0
Exp/Cntr=0.3,0.1

Type RM Length L Ch R = 1 ,12213   ,405,405,405
BEGIN DESCRIPTION:
TOWN CREEK TRIBUTARY NO 1 21.0
END DESCRIPTION:
XS GIS Cut Line= 3
      3754422.74     10146785.08      3754088.08     10146522.95
      3753426.44     10146428.13
#Sta/Elev= 30
  4574.9  302.96  4687.9  298.44  4801.9  292.91  4880.5  290.33  4959.2  286.48
  4965.5  286.71  4973.6  285.89    4980  284.88  4987.6  281.32  4994.4  280.67
  4995.7  278.99  5002.6  279.49  5010.3  283.59  5020.4  284.72  5047.1  286.07
  5052.1  285.56  5060.8  286.33  5101.3  286.32  5141.7  287.36  5263.9  288.02
  5343.7  289.76  5464.9  293.91  5525.5  294.89  5541.3  296.77  5546.4   296.2
  5576.1   297.4  5606.4  297.64  5611.9  298.72  5636.7  299.03  5668.4  300.69
#Mann= 3 , 0 , 0
  4574.9     .11       0  4973.6     .06       0  5047.1     .11       0
Bank Sta=4973.6,5047.1
XS Rating Curve= 0 ,0
Exp/Cntr=0.3,0.1

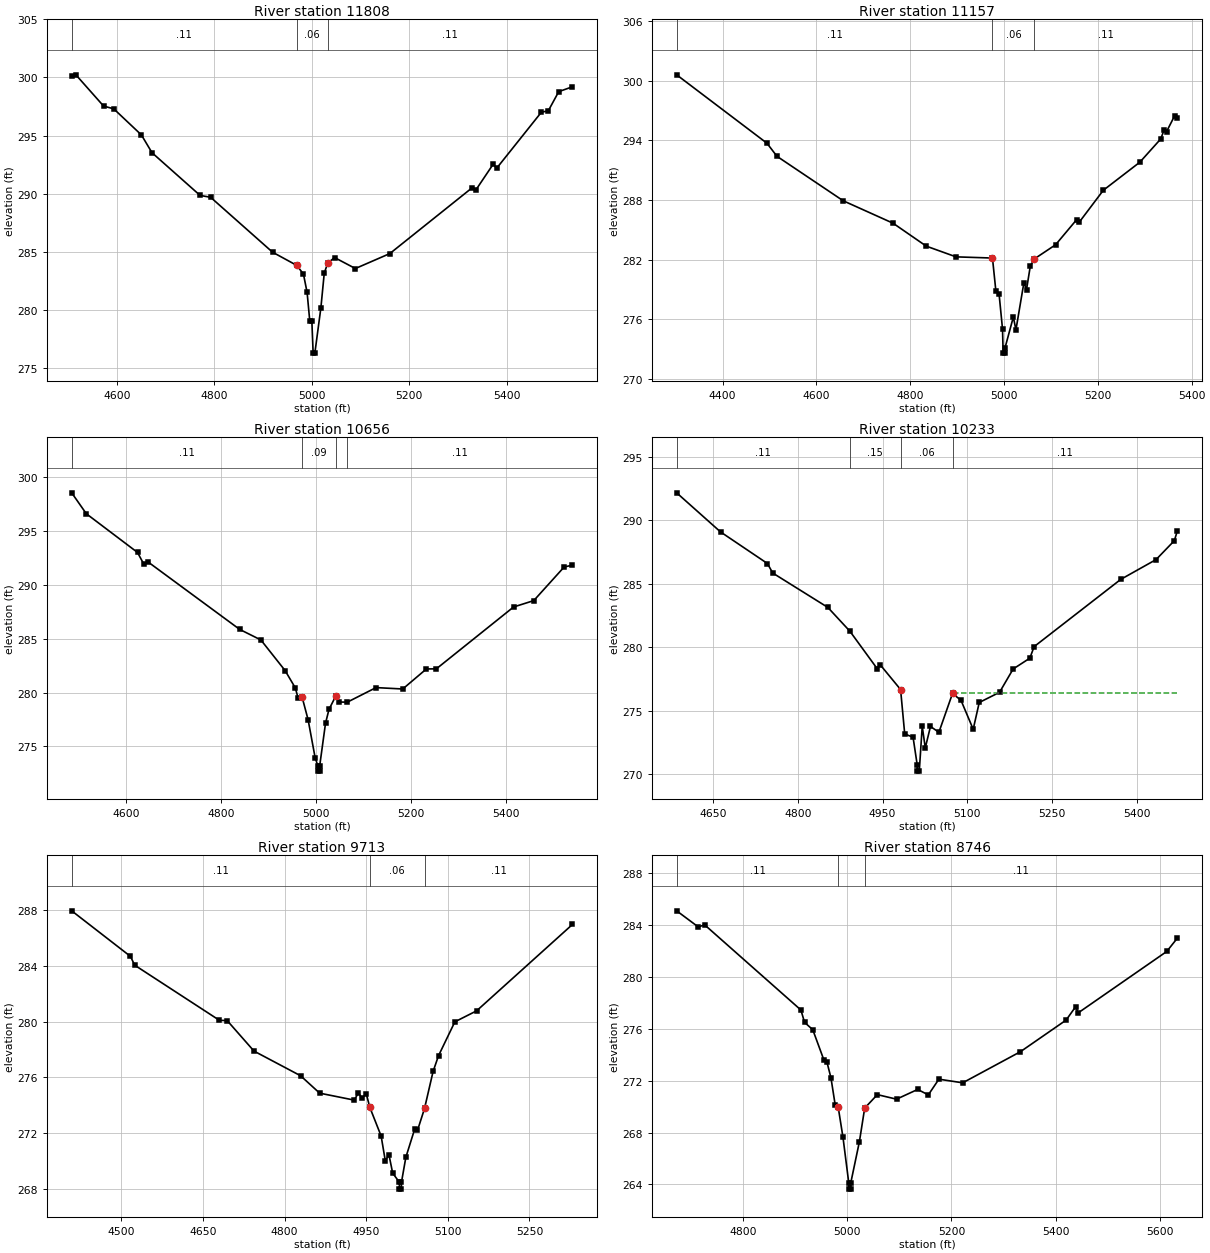
Type RM Length L Ch R = 1 ,11808   ,651,651,651
BEGIN DESCRIPTION:
TOWN CREEK TRIBUTARY NO 1 20.0
END DESCRIPTION:
XS GIS Cut Line= 3
      3754566.64     10146614.63      3754237.05     10146248.13
      3753867.85     10145861.07
#Sta/Elev= 30
  4507.1  300.09  4515.7  300.23  4572.5  297.54  4593.4   297.3  4650.2  295.05
  4671.9  293.52  4770.6  289.84  4792.2  289.68  4919.3  284.95  4969.1  283.81
  4982.8  283.06  4990.3  281.48  4995.7  279.05    5000  279.05  5002.7  276.25
  5006.2  276.25  5018.6  280.16  5025.5  283.14  5032.8  284.03  5046.9  284.48
  5089.4  283.54  5160.2  284.83  5329.7  290.52  5336.9  290.32  5372.1  292.52
  5379.4  292.18  5471.2  297.01  5485.4  297.13  5506.8  298.78  5534.9   299.2
#Mann= 3 , 0 , 0
  4507.1     .11       0  4969.1     .06       0  5032.8     .11       0
Bank Sta=4969.1,5032.8
XS Rating Curve= 0 ,0
Exp/Cntr=0.3,0.1

Type RM Length L Ch R = 1 ,11157   ,501,501,501
BEGIN DESCRIPTION:
TOWN CREEK TRIBUTARY NO 1 19.0
END DESCRIPTION:
XS GIS Cut Line= 3
      3754822.35     10146438.78      3754318.22     10145955.88
       3753985.9     10145794.12
#Sta/Elev= 30
  4301.9  300.61  4494.4  293.72  4515.8   292.4    4657  287.92  4763.3  285.66
  4834.1  283.35  4897.6  282.27  4975.3  282.15  4982.5  278.85  4989.4  278.52
  4996.7  275.01  4998.1  272.57  5001.6  272.57  5001.9  273.07  5019.8  276.21
  5025.3  274.91  5042.3  279.67  5047.9  278.97    5056  281.35  5064.8  282.07
  5109.9  283.49    5155  286.03  5160.6  285.78  5211.7  288.98  5289.6  291.81
  5334.1  294.15    5341  295.02  5346.5  294.89  5363.5  296.46  5369.6  296.22
#Mann= 3 , 0 , 0
  4301.9     .11       0  4975.3     .06       0  5064.8     .11       0
Bank Sta=4975.3,5064.8
XS Rating Curve= 0 ,0
Exp/Cntr=0.3,0.1

Type RM Length L Ch R = 1 ,10656   ,423,423,423
BEGIN DESCRIPTION:
TOWN CREEK TRIBUTARY NO 1 18.0
END DESCRIPTION:
XS GIS Cut Line= 3
      3754912.93     10146246.98      3754630.86     10145816.69
      3754236.26     10145447.77
#Sta/Elev= 30
  4485.5  298.53  4516.3  296.59  4624.1     293  4636.8  291.96  4645.9  292.13
  4839.3  285.86    4884  284.88    4935  282.04  4956.4  280.44  4962.4  279.49
  4970.8  279.58  4983.5  277.47  4998.2  273.97  5003.9  273.21  5004.2  272.71
  5007.7  272.71  5007.9  273.21  5020.1  277.14  5027.4  278.43  5041.6  279.67
  5048.4  279.12  5066.1  279.11  5126.6  280.46  5182.8  280.33  5232.6  282.19
  5253.6   282.2  5416.3  287.94  5458.8  288.53  5522.8  291.65  5540.2  291.82
#Mann= 4 ,-1 , 0
  4485.5     .11       0  4970.8     .09       0  5041.6     .15       0
  5066.1     .11       0
Bank Sta=4970.8,5041.6
XS Rating Curve= 0 ,0
Exp/Cntr=0.3,0.1

Type RM Length L Ch R = 1 ,10233   ,520,520,520
BEGIN DESCRIPTION:
TOWN CREEK TRIBUTARY NO 1 17.0
END DESCRIPTION:
XS GIS Cut Line= 3
      3755184.68      10145543.7      3754780.06     10145454.18
      3754342.88     10145277.32
#Sta/Elev= 30
  4585.6  292.17  4663.2  289.09  4746.2   286.6  4755.6  285.85  4853.1  283.14
  4892.2  281.26  4940.3  278.32  4945.4  278.64  4981.8  276.67  4989.1  273.17
  5003.9  272.91  5011.2  270.74  5011.4  270.24  5014.9  270.24  5020.1  273.77
  5025.5  272.07  5034.7  273.76  5049.6   273.3  5073.7  276.36  5088.7  275.82
  5110.3  273.54    5121  275.65  5156.9  276.45    5181  278.29  5210.5  279.14
  5218.1  280.05  5371.4  285.35  5433.9  286.91  5466.2   288.4  5471.6  289.18
#Mann= 4 ,-1 , 0
  4585.6     .11       0  4892.2     .15       0  4981.8     .06       0
  5073.7     .11       0
#XS Ineff= 2 , 0
       0                  5079.1       0   276.4
Permanent Ineff=
       F       F
Bank Sta=4981.8,5073.7
XS Rating Curve= 0 ,0
Exp/Cntr=0.3,0.1

Type RM Length L Ch R = 1 ,9713    ,967,967,967
BEGIN DESCRIPTION:
TOWN CREEK TRIBUTARY NO 1 16.0
END DESCRIPTION:
XS GIS Cut Line= 3
      3755168.66     10145373.19      3754720.69     10144987.07
      3754391.79     10144978.96
#Sta/Elev= 30
  4408.6  287.96  4516.6  284.69  4524.3  284.06  4680.1   280.1  4694.4  280.08
  4743.7  277.89  4829.3  276.12  4864.4  274.87    4928  274.37  4935.7   274.9
  4942.3  274.49    4950  274.83  4956.6  273.85  4977.4  271.79  4985.1     270
  4991.7  270.46  4998.6  269.13  5010.8  268.48  5011.1  267.98  5014.6  267.98
  5014.8  268.48  5022.8  270.26  5039.2  272.31  5044.2  272.19 5057.21  273.78
  5072.9  276.43  5082.9  277.56  5112.9  279.99  5152.9  280.78    5329  286.98
#Mann= 3 , 0 , 0
  4408.6     .11       0  4956.6     .06       0 5057.21     .11       0
Bank Sta=4956.6,5057.21
XS Rating Curve= 0 ,0
Exp/Cntr=0.3,0.1

Type RM Length L Ch R = 1 ,8746    ,410,410,410
BEGIN DESCRIPTION:
TOWN CREEK TRIBUTARY NO 1 15.0
END DESCRIPTION:
XS GIS Cut Line= 3
      3755424.38     10144659.24      3755140.83     10144495.75
      3754517.82     10144611.08
#Sta/Elev= 30
  4672.7  285.08  4714.1  283.84  4726.4     284  4911.1  277.44  4918.1  276.49
  4933.9  275.92  4955.4  273.57  4961.2  273.41  4968.8  272.21    4977   270.1
  4982.7  269.95  4991.9  267.62  5002.9  264.14  5003.2  263.64  5006.7  263.64
  5006.9  264.14  5023.4   267.3  5033.5  269.88  5057.8  270.92  5094.6  270.57
  5135.2  271.32  5155.6   270.9  5175.9  272.11  5221.6  271.83  5332.5  274.23
    5420  276.66  5438.3  277.69  5443.3  277.22  5613.2  281.95  5633.6  282.98
#Mann= 3 , 0 , 0
  4672.7     .11       0  4982.7     .06       0  5033.5     .11       0
Bank Sta=4982.7,5033.5
XS Rating Curve= 0 ,0
Exp/Cntr=0.3,0.1

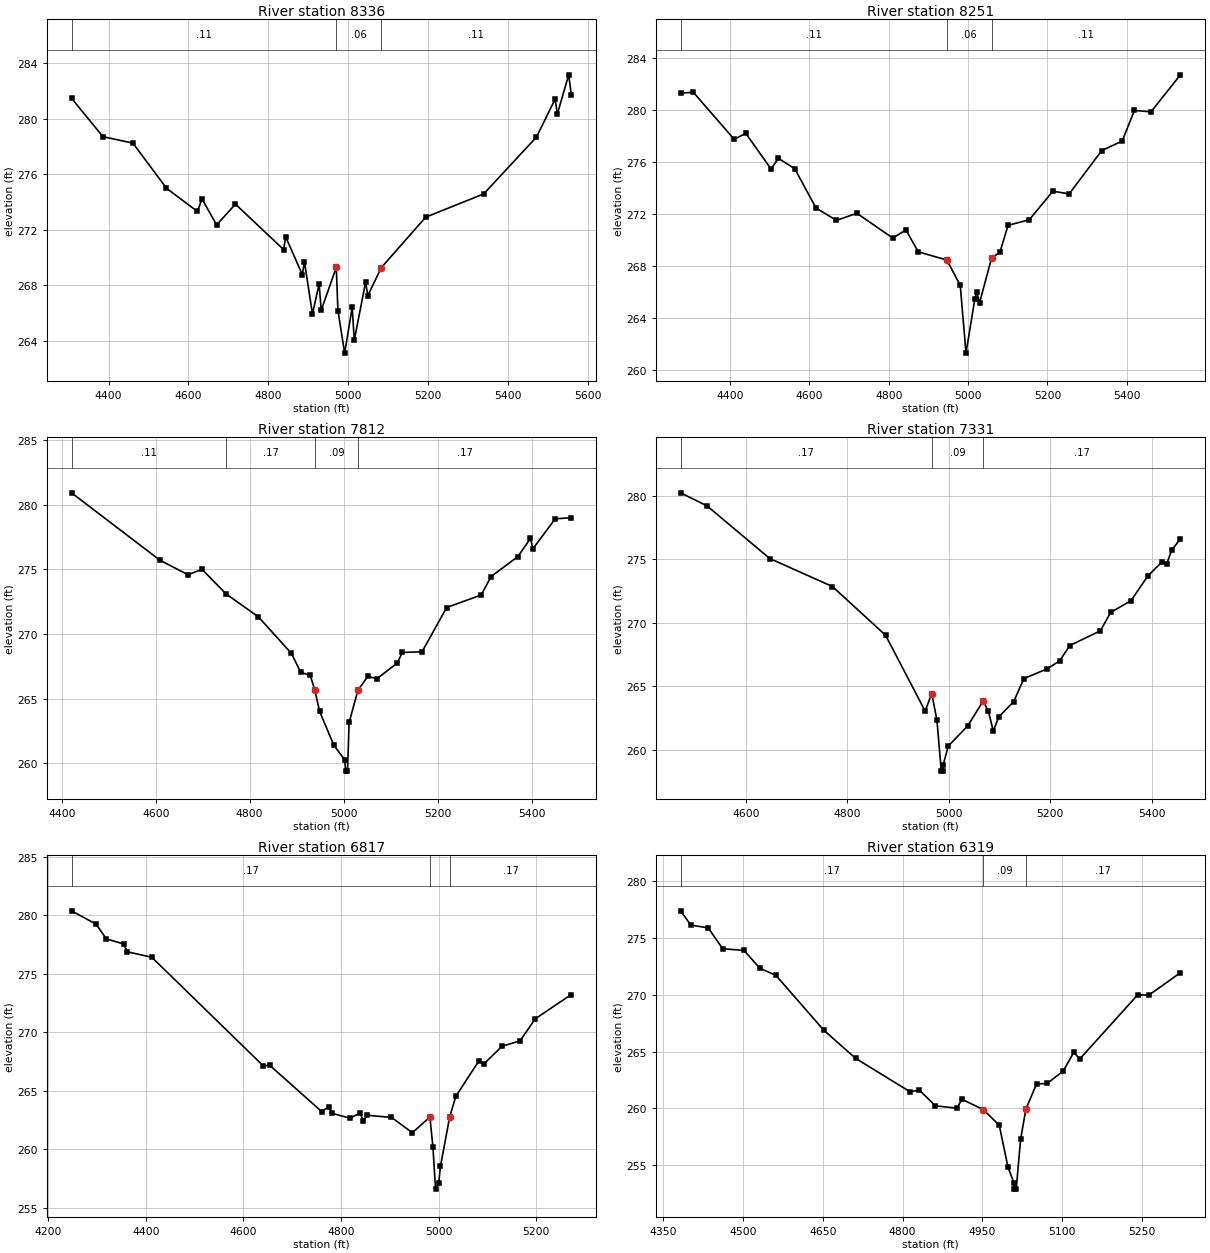
Type RM Length L Ch R = 1 ,8336    ,85,85,85
BEGIN DESCRIPTION:
Mapping XS 35c4787f
END DESCRIPTION:
XS GIS Cut Line= 3
      3755744.27     10143990.49      3755070.86     10144152.83
      3754534.01     10144307.19
#Sta/Elev= 30
  4307.3  281.49  4385.9  278.72  4461.1  278.25  4544.9     275  4622.5  273.32
  4633.9  274.23  4670.6  272.35  4717.7  273.85  4838.3  270.57  4843.4  271.49
  4885.3  268.76  4890.5   269.7  4910.5  265.92  4927.2   268.1  4932.4  266.19
 4970.16  269.29  4974.3  266.17  4991.1   263.1    5010   266.4  5015.2  264.03
  5043.7  268.24  5048.9  267.23  5082.6  269.26  5194.1  272.91  5339.4  274.59
  5471.4  278.69  5518.3  281.44  5523.5  280.33    5552  283.18  5558.6  281.74
#Mann= 3 , 0 , 0
  4307.3     .11       0 4970.16     .06       0  5082.6     .11       0
Bank Sta=4970.16,5082.6
XS Rating Curve= 0 ,0
Exp/Cntr=0.3,0.1

Type RM Length L Ch R = 1 ,8251    ,439,439,439
BEGIN DESCRIPTION:
TOWN CREEK TRIBUTARY NO 1 14.0
END DESCRIPTION:
XS GIS Cut Line= 3
      3755748.79     10143895.48      3755045.78     10144071.45
      3754524.92     10144194.09
#Sta/Elev= 30
  4275.3   281.3  4307.2  281.37  4410.3  277.74  4439.3  278.21  4503.1  275.46
  4521.7  276.28  4562.9  275.48  4616.4  272.46    4668   271.5  4719.5  272.05
  4810.1  270.14  4843.2  270.77  4874.2  269.08  4946.3  268.45  4980.1   266.5
  4994.6  261.28  5016.7  265.43  5021.9  266.01  5028.7  265.15  5059.1   268.6
  5080.1  269.05  5100.6  271.12  5154.1  271.55  5213.6  273.75  5254.7  273.54
  5336.9  276.88  5388.3  277.61  5419.1  279.97  5460.9  279.86  5535.1  282.71
#Mann= 3 ,-1 , 0
  4275.3     .11       0  4946.3     .06       0  5059.1     .11       0
Bank Sta=4946.3,5059.1
XS Rating Curve= 0 ,0
Exp/Cntr=0.3,0.1

Type RM Length L Ch R = 1 ,7812    ,481,481,481
BEGIN DESCRIPTION:
TOWN CREEK TRIBUTARY NO 1 13.0
END DESCRIPTION:
XS GIS Cut Line= 3
      3755755.56     10143804.98      3755176.69      10143788.8
      3754715.25     10143641.11
#Sta/Elev= 30
  4420.9  280.93  4608.7  275.72  4668.7  274.59  4698.7     275  4749.8   273.1
  4818.8  271.32  4888.8   268.5  4908.8  267.02  4928.8  266.81  4938.8  265.63
  4948.8  264.01  4978.8  261.41    5002  260.27  5004.7  259.38  5008.2  259.38
  5011.7  263.15  5030.3  265.63  5051.3  266.71  5070.8  266.54  5114.3  267.75
  5124.8  268.57  5166.8  268.62  5219.3  272.05  5292.8  273.02  5313.8  274.45
  5370.7  275.99  5397.6   277.4  5402.8   276.6  5450.3  278.92  5484.5     279
#Mann= 4 ,-1 , 0
  4420.9     .11       0  4749.8     .17       0  4938.8     .09       0
  5030.3     .17       0
Bank Sta=4938.8,5030.3
XS Rating Curve= 0 ,0
Exp/Cntr=0.3,0.1

Type RM Length L Ch R = 1 ,7331    ,514,514,514
BEGIN DESCRIPTION:
TOWN CREEK TRIBUTARY NO 1 12.0
END DESCRIPTION:
XS GIS Cut Line= 3
      3755798.49     10143581.19      3755285.14     10143455.58
      3754830.98     10143409.39
#Sta/Elev= 30
  4471.5  280.22  4523.6  279.19  4647.2  275.05  4770.7  272.85  4875.3  269.02
  4953.4  263.05  4966.3  264.43  4976.6  262.35  4985.2  258.33  4988.7  258.33
  4988.9  258.83    4999   260.3  5037.5   261.9  5067.6  263.84  5077.7  263.09
  5087.7  261.48  5098.4  262.59  5127.9   263.8    5148  265.61    5193  266.36
  5218.4     267  5238.5  268.21  5298.8  269.37  5318.9  270.81  5359.1  271.74
  5392.4  273.69  5419.4  274.75  5429.5  274.64  5439.5  275.73  5456.5   276.6
#Mann= 3 , 0 , 0
  4471.5     .17       0  4966.3     .09       0  5067.6     .17       0
Bank Sta=4966.3,5067.6
XS Rating Curve= 0 ,0
Exp/Cntr=0.3,0.1

Type RM Length L Ch R = 1 ,6817    ,498,498,498
BEGIN DESCRIPTION:
TOWN CREEK TRIBUTARY NO 1 11.0
END DESCRIPTION:
XS GIS Cut Line= 3
      3755817.82     10143561.04      3755225.43     10143097.49
      3754967.84     10143011.07
#Sta/Elev= 30
  4247.8  280.37  4298.4  279.22  4319.2  277.97  4354.5  277.54    4362  276.87
  4412.3   276.4  4640.2  267.14  4654.1  267.16  4760.5  263.21  4774.9  263.65
  4781.3  263.07  4818.3  262.65  4839.1  263.09  4845.5  262.42  4853.6   262.9
  4903.3  262.72  4946.1  261.41    4982  262.75  4988.3  260.15  4993.5  256.59
    5000  257.09  5003.6  258.53 5022.51  262.75  5035.1  264.52  5081.8  267.51
  5092.4  267.28  5129.8   268.8  5166.6  269.26  5198.1  271.15  5271.7  273.22
#Mann= 3 , 0 , 0
  4247.8     .17       0    4982     .09       0 5022.51     .17       0
Bank Sta=4982,5022.51
XS Rating Curve= 0 ,0
Exp/Cntr=0.3,0.1

Type RM Length L Ch R = 1 ,6319    ,996,996,996
BEGIN DESCRIPTION:
TOWN CREEK TRIBUTARY NO 1 10.0
END DESCRIPTION:
XS GIS Cut Line= 3
      3756006.86      10142768.7      3755390.02     10142736.06
      3755067.89     10142761.07
#Sta/Elev= 30
  4382.3  277.37  4401.3  276.12  4434.2  275.87  4461.4  274.04  4501.5  273.89
  4531.5  272.32  4561.6   271.7  4651.7  266.88  4711.8   264.4  4813.7  261.48
  4831.9   261.6    4862  260.23    4902  260.03    4912   260.8  4952.1   259.9
  4982.1  258.52  4998.5  254.83  5010.2  253.41  5010.5  252.91    5014  252.91
  5022.2  257.28  5032.3  259.96  5052.3  262.15  5072.4   262.2  5102.5  263.29
  5122.5  264.94  5133.5  264.34  5242.9     270  5263.3  269.95  5323.1  271.93
#Mann= 3 , 0 , 0
  4382.3     .17       0  4952.1     .09       0  5032.3     .17       0
Bank Sta=4952.1,5032.3
XS Rating Curve= 0 ,0
Exp/Cntr=0.3,0.1

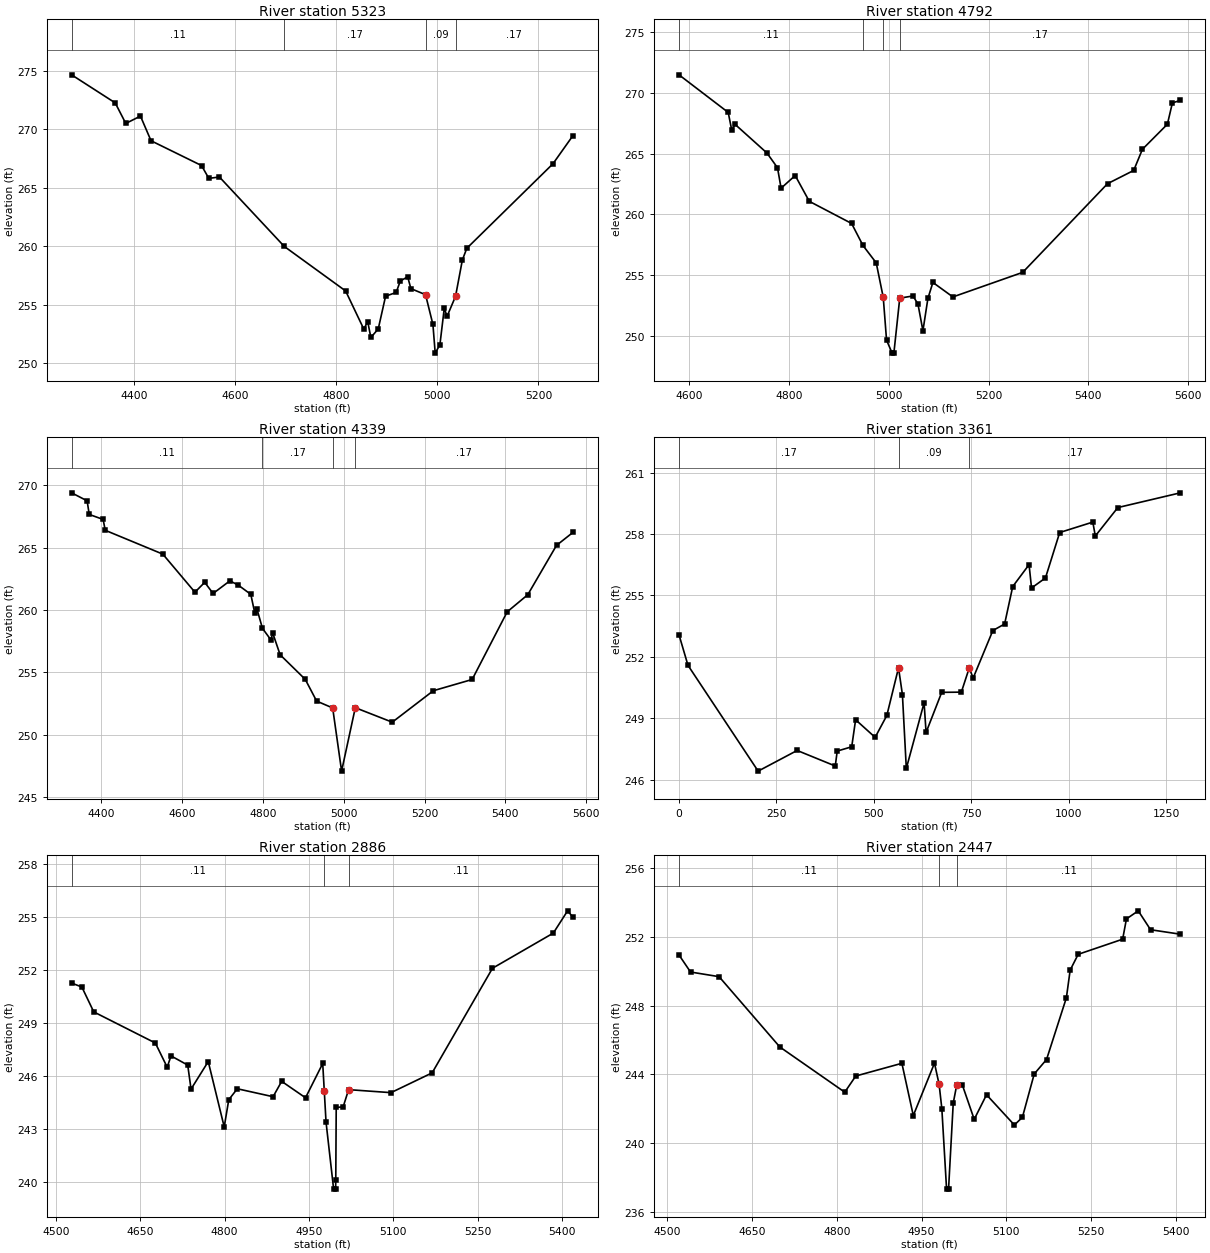
Type RM Length L Ch R = 1 ,5323    ,531,531,531
BEGIN DESCRIPTION:
TOWN CREEK TRIBUTARY NO 1 9.0
END DESCRIPTION:
XS GIS Cut Line= 3
      3756017.82     10142561.04      3755442.24     10142123.83
      3755202.56     10142003.27
#Sta/Elev= 30
  4277.2  274.65  4363.4  272.25  4384.3  270.49  4413.3  271.12  4434.2  269.01
    4534  266.89  4548.5  265.79  4569.4  265.91  4697.6  259.97  4818.9  256.16
  4854.8   252.9  4862.6  253.53  4868.8  252.18  4883.4  252.91  4897.9  255.71
  4918.8  256.03    4927  257.01  4941.6  257.37  4947.9  256.36  4976.9  255.84
  4991.5  253.29    4996  250.84  5005.3  251.56  5013.9  254.67  5019.5  253.99
  5036.2   255.7  5049.7  258.81  5058.5  259.81  5228.8  267.04  5268.3  269.45
#Mann= 4 ,-1 , 0
  4277.2     .11       0  4697.6     .17       0  4976.9     .09       0
  5036.2     .17       0
Bank Sta=4976.9,5036.2
XS Rating Curve= 0 ,0
Exp/Cntr=0.3,0.1

Type RM Length L Ch R = 1 ,4792    ,453,453,453
BEGIN DESCRIPTION:
TOWN CREEK TRIBUTARY NO 1 8.0
END DESCRIPTION:
XS GIS Cut Line= 3
      3756118.83     10142229.62       3755816.2     10141936.94
      3755231.84     10141911.97
#Sta/Elev= 30
    4579  271.47  4677.7  268.38  4684.7  266.94  4691.7  267.39  4755.5  265.04
  4776.6  263.83  4783.8  262.15  4812.1  263.19  4840.4  261.07  4925.3  259.25
  4948.1  257.44  4974.7  256.01  4988.8  253.17  4995.4  249.66  5006.6  248.59
  5010.1  248.59  5021.9  253.11  5048.4  253.29  5058.4  252.63  5068.4  250.43
  5078.4  253.09  5088.4   254.4  5128.5  253.21  5268.6  255.23  5438.8  262.52
  5491.3  263.61  5508.8  265.35  5558.9  267.41  5568.9  269.16  5584.9  269.37
#Mann= 4 ,-1 , 0
    4579     .11       0  4948.1     .17       0  4988.8     .09       0
  5021.9     .17       0
#XS Ineff= 2 , 0
       0                  5308.6       0  256.89
Permanent Ineff=
       F       F
Bank Sta=4988.8,5021.9
XS Rating Curve= 0 ,0
Exp/Cntr=0.3,0.1

Type RM Length L Ch R = 1 ,4339    ,978,978,978
BEGIN DESCRIPTION:
TOWN CREEK TRIBUTARY NO 1 7.0
END DESCRIPTION:
XS GIS Cut Line= 3
       3756475.6     10141737.45      3755825.98     10141558.91
      3755267.86     10141661.07
#Sta/Elev= 30
  4326.3  269.38  4364.7  268.74  4369.9  267.65  4404.3  267.25  4409.5  266.38
  4552.1  264.47  4631.6  261.42  4655.8  262.21  4676.6  261.32  4718.1  262.33
  4738.8  261.99  4769.9  261.25  4779.7  259.76  4784.9   260.1  4798.8  258.52
  4819.3  257.62  4824.5  258.12  4842.5  256.41  4904.7  254.44  4932.9   252.7
  4972.6  252.15  4994.7  247.09  5028.6  252.17  5120.1  251.01  5221.8  253.53
  5317.9  254.43  5404.7  259.85  5455.6  261.22  5526.7  265.17  5567.4  266.21
#Mann= 4 ,-1 , 0
  4326.3     .11       0  4798.8     .17       0  4972.6     .09       0
  5028.6     .17       0
Bank Sta=4972.6,5028.6
XS Rating Curve= 0 ,0
Exp/Cntr=0.3,0.1

Type RM Length L Ch R = 1 ,3361    ,475,475,475
XS GIS Cut Line= 4
      3756540.81     10140877.59      3755951.31     10140860.76
      3755670.93     10140898.91      3755345.41     10141154.12
#Sta/Elev= 30
       0  253.07      23  251.58     203  246.41   303.1  247.42   400.9  246.66
   405.9  247.39   443.1   247.6   453.1  248.92   503.2  248.06   533.2  249.13
   563.2  251.46   573.2  250.15   583.2  246.54   628.8  249.75   633.9   248.3
     674  250.26   724.4  250.27   744.6  251.45   754.7  250.96   805.2  253.28
   835.4   253.6   856.2  255.43   898.1   256.5   904.5  255.36   940.2  255.85
   976.7  258.07  1061.7  258.58  1068.1   257.9  1125.9  259.29  1286.3  260.01
#Mann= 3 , 0 , 0
       0     .17       0   563.2     .09       0   744.6     .17       0
Bank Sta=563.2,744.6
XS Rating Curve= 0 ,0
Exp/Cntr=0.3,0.1

Type RM Length L Ch R = 1 ,2886    ,439,439,439
BEGIN DESCRIPTION:
TOWN CREEK TRIBUTARY NO 1 5.0
END DESCRIPTION:
XS GIS Cut Line= 3
      3756707.35     10140836.38      3756308.02     10140584.38
       3755913.1     10140443.17
#Sta/Elev= 30
  4527.8  251.28    4546  251.06  4567.2  249.65  4676.7  247.89  4697.8  246.52
  4704.6  247.16  4734.3  246.64  4740.2  245.28  4770.8  246.84  4799.2  243.14
  4807.3  244.68  4822.5   245.3  4886.1  244.85  4901.4  245.72  4943.8  244.79
  4974.4  246.73 4977.13  245.19  4980.3  243.41  4993.8  239.62  4997.3  239.62
  4997.6  240.12  4998.4  244.24  5010.8  244.28  5020.4  245.25  5095.8  245.08
    5169   246.2  5276.3  252.12  5384.5  254.11  5409.9  255.37  5419.4  255.01
#Mann= 3 , 0 , 0
  4527.8     .11       0 4977.13     .06       0  5020.4     .11       0
#XS Ineff= 2 , 0
       0  4974.4  246.73               0
Permanent Ineff=
       T       F
Bank Sta=4977.13,5020.4
XS Rating Curve= 0 ,0
Exp/Cntr=0.3,0.1

Type RM Length L Ch R = 1 ,2447    ,246,246,246
BEGIN DESCRIPTION:
TOWN CREEK TRIBUTARY NO 1 4.0
END DESCRIPTION:
XS GIS Cut Line= 3
      3756749.06     10140831.23      3756677.23     10140343.64
      3756381.46     10140082.81
#Sta/Elev= 30
  4520.8  250.94  4541.2  249.95  4591.7  249.68  4699.2  245.59  4814.1  242.96
  4833.6   243.9  4915.2  244.64  4935.4   241.6  4972.9  244.65 4981.11  243.41
  4985.9  242.01  4994.3  237.32  4997.8  237.32  5006.1  242.33  5012.4   243.4
  5022.3  243.37  5043.2  241.38    5065  242.81  5114.3  241.05  5128.5   241.5
  5149.4  244.02  5171.2  244.86  5206.3  248.45    5213  250.06  5227.2  250.98
  5305.9  251.86  5312.6  253.04  5333.5  253.51  5355.3  252.41    5408  252.15
#Mann= 3 , 0 , 0
  4520.8     .11       0 4981.11     .06       0  5012.4     .11       0
Bank Sta=4981.11,5012.4
XS Rating Curve= 0 ,0
Exp/Cntr=0.3,0.1

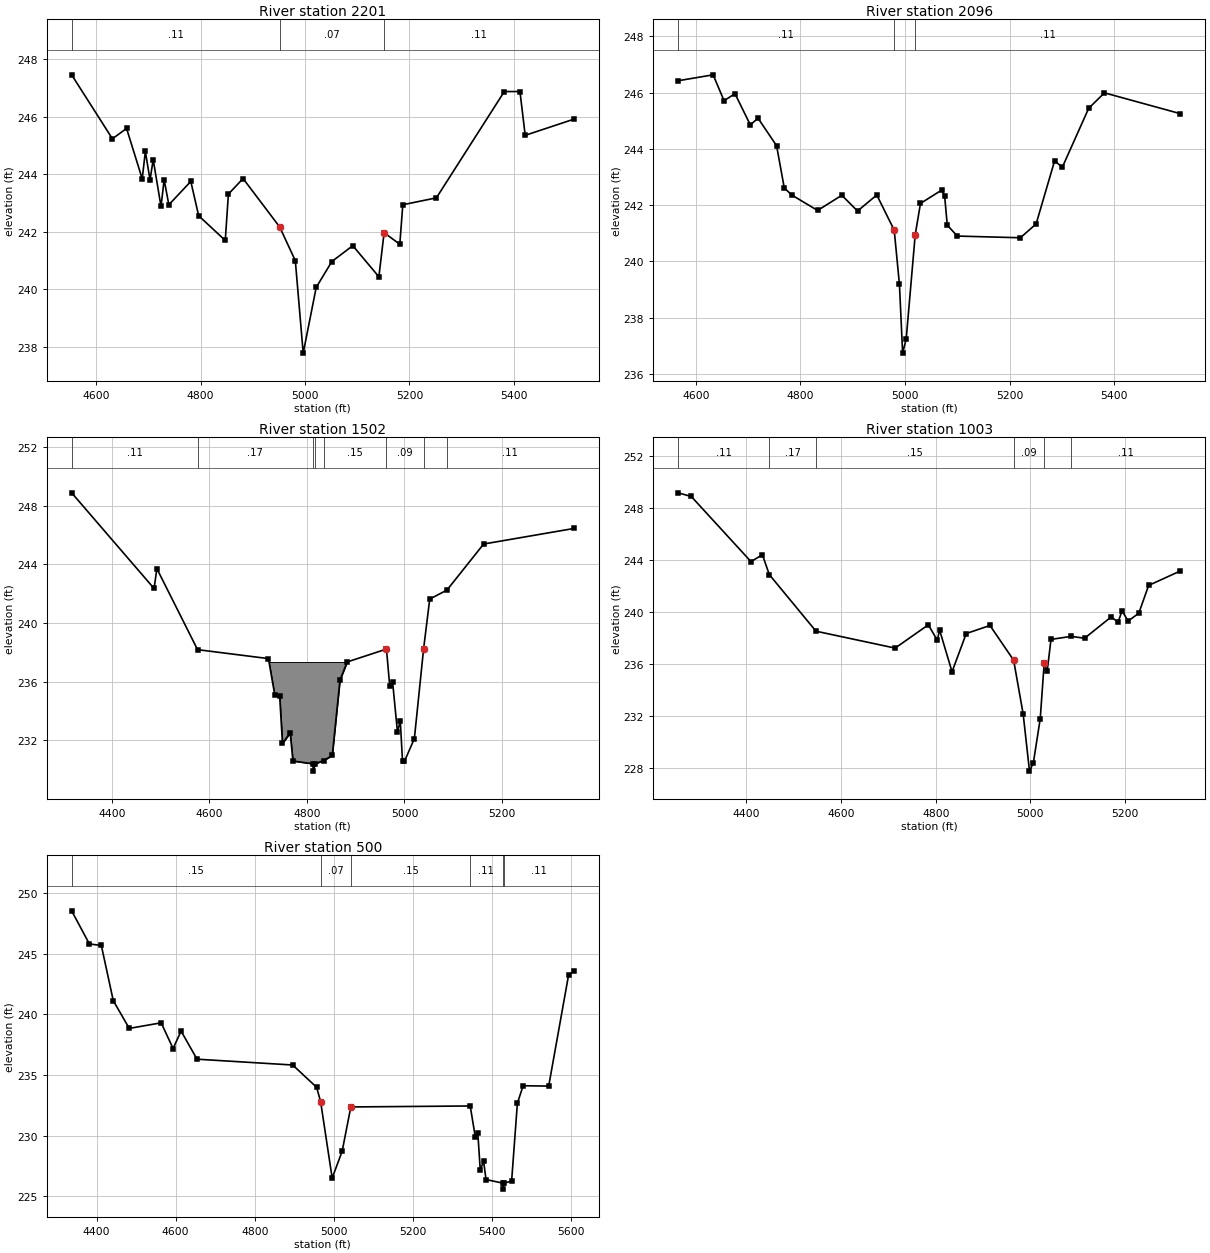
Type RM Length L Ch R = 1 ,2201    ,105,105,105
BEGIN DESCRIPTION:
Mapping XS 9ca6fe87
END DESCRIPTION:
XS GIS Cut Line= 4
      3757088.65     10140737.46      3756917.21     10140481.11
      3756913.89     10140342.34      3756938.44     10139828.03
#Sta/Elev= 30
  4552.8  247.45  4630.9  245.23    4658  245.59    4688  243.84    4694  244.79
    4703   243.8    4709  244.51    4724  242.88    4730  243.81    4739  242.94
  4781.1  243.75  4796.1  242.56  4847.1   241.7  4853.1  243.31  4881.2  243.85
  4951.3  242.17  4981.3     241  4996.4  237.79  5021.3  240.07  5051.3  240.97
  5091.4  241.52  5141.4  240.44  5151.4  241.97  5181.5  241.57  5187.2  242.94
  5251.6  243.18  5381.7  246.87  5411.7  246.87  5421.7  245.35  5514.9  245.91
#Mann= 3 , 0 , 0
  4552.8     .11       0  4951.3     .07       0  5151.4     .11       0
Bank Sta=4951.3,5151.4
XS Rating Curve= 0 ,0
Exp/Cntr=0.3,0.1

Type RM Length L Ch R = 1 ,2096    ,594,594,594
BEGIN DESCRIPTION:
TOWN CREEK TRIBUTARY NO 1 3.0
END DESCRIPTION:
XS GIS Cut Line= 4
        3757185.     10140706.45      3757008.65     10140464.78
      3757015.52     10140330.43       3757065.8     10139806.74
#Sta/Elev= 30
  4566.3  246.42  4633.2  246.63  4654.1  245.71    4675  245.96  4704.3  244.85
    4719  245.09  4754.5  244.11  4769.2  242.61  4783.4  242.36  4832.9  241.81
  4879.2  242.35  4909.2  241.79    4946  242.36  4979.3  241.11  4989.3  239.18
  4995.4  236.74  5002.2  237.24  5019.4  240.94  5029.5  242.06  5069.7  242.53
  5075.7  242.32  5080.7  241.29  5099.8   240.9  5220.4  240.84  5250.5  241.33
  5285.8  243.57  5300.7  243.35    5351  245.44  5381.1  245.99  5526.1  245.25
#Mann= 3 , 0 , 0
  4566.3     .11       0  4979.3     .07       0  5019.4     .11       0
#XS Ineff= 2 , 0
       0    4946  242.36  5069.7       0  242.53
Permanent Ineff=
       F       T
Bank Sta=4979.3,5019.4
XS Rating Curve= 0 ,0
Exp/Cntr=0.3,0.1

Type RM Length L Ch R = 1 ,1502    ,499,499,499
BEGIN DESCRIPTION:
TOWN CREEK TRIBUTARY NO 1 2.0
END DESCRIPTION:
XS GIS Cut Line= 3
      3757817.87     10140661.11      3757478.32     10140069.07
      3757317.85     10139761.07
#Sta/Elev= 30
  4317.5  248.88  4486.5  242.36  4492.3  243.71  4575.7  238.19    4721  237.58
    4734   235.1    4744  235.06  4749.8   231.8  4765.6  232.52  4771.3   230.6
  4812.5  230.41  4812.8  229.91  4816.5  230.41  4834.2  230.63  4851.9  230.98
  4867.7  236.11  4882.4  237.35  4963.1  238.23  4969.8  235.68  4975.6  236.01
  4985.6  232.58  4991.4  233.34    4996  230.58    5000  230.58  5020.3  232.13
 5039.26  238.26  5051.8  241.64  5087.1  242.25  5162.3  245.39  5347.3  246.45
#Mann= 8 ,-1 , 0
  4317.5     .11       0  4575.7     .17       0  4812.5     .12       0
  4816.5     .17       0  4834.2     .15       0  4963.1     .09       0
 5039.26     .15       0  5087.1     .11       0
#Block Obstruct= 1 ,-1
    4722  4882.4  237.35
Bank Sta=4963.1,5039.26
XS Rating Curve= 0 ,0
Exp/Cntr=0.3,0.1

Type RM Length L Ch R = 1 ,1003    ,503,503,503
BEGIN DESCRIPTION:
TOWN CREEK TRIBUTARY NO 1 1.0
END DESCRIPTION:
XS GIS Cut Line= 3
      3757940.67      10140638.8      3757903.12     10139895.75
      3757712.18     10139643.21
#Sta/Elev= 30
    4256  249.14  4283.8  248.86  4409.9  243.85    4434  244.38  4448.6  242.85
  4547.2   238.5  4714.3   237.2  4784.4  238.99  4803.3  237.81  4808.3  238.58
  4834.5  235.38  4864.5  238.32  4914.6  238.94  4964.6  236.27  4984.7  232.14
  4998.1  227.74  5006.3  228.39  5020.8  231.78  5029.1  236.04  5035.4  235.41
  5043.5  237.87    5086   238.1  5114.5  237.96  5170.7   239.6  5185.2  239.19
  5193.5  240.07  5206.4  239.28  5228.9  239.88  5249.7  242.02  5316.6  243.13
#Mann= 6 ,-1 , 0
    4256     .11       0  4448.6     .17       0  4547.2     .15       0
  4964.6     .09       0  5029.1     .15       0    5086     .11       0
Bank Sta=4964.6,5029.1
XS Rating Curve= 0 ,0
Exp/Cntr=0.3,0.1

Type RM Length L Ch R = 1 ,500     ,0,0,0
BEGIN DESCRIPTION:
TOWN CREEK TRIBUTARY NO 1 1.5
END DESCRIPTION:
XS GIS Cut Line= 3
      3758294.83     10140555.53      3758380.64     10139898.11
      3758017.86     10139411.08
#Sta/Elev= 30
    4337  248.55  4381.8  245.82  4412.1  245.69  4442.3  241.14  4482.7  238.85
  4563.4  239.31  4593.6  237.19  4613.8  238.63  4654.1  236.31  4896.2  235.83
  4956.7  233.99  4966.8   232.8    4996   226.5  5021.2  228.71  5043.2  232.37
  5345.2  232.45  5357.9  229.92  5364.4  230.21  5370.6  227.17    5379  227.89
  5385.2  226.38    5427  226.09  5427.3  225.59  5431.1  226.09  5449.9  226.25
  5464.5  232.68  5479.1  234.12  5543.7  234.09  5593.8  243.22  5607.3  243.62
#Mann= 6 ,-1 , 0
    4337     .15       0  4966.8     .07       0  5043.2     .15       0
  5345.2     .11       0    5427     .12       0  5431.1     .11       0
Bank Sta=4966.8,5043.2
XS Rating Curve= 0 ,0
Exp/Cntr=0.3,0.1

Chan Stop Cuts=-1
Use User Specified Reach Order=0
Composite Channel Slope=5