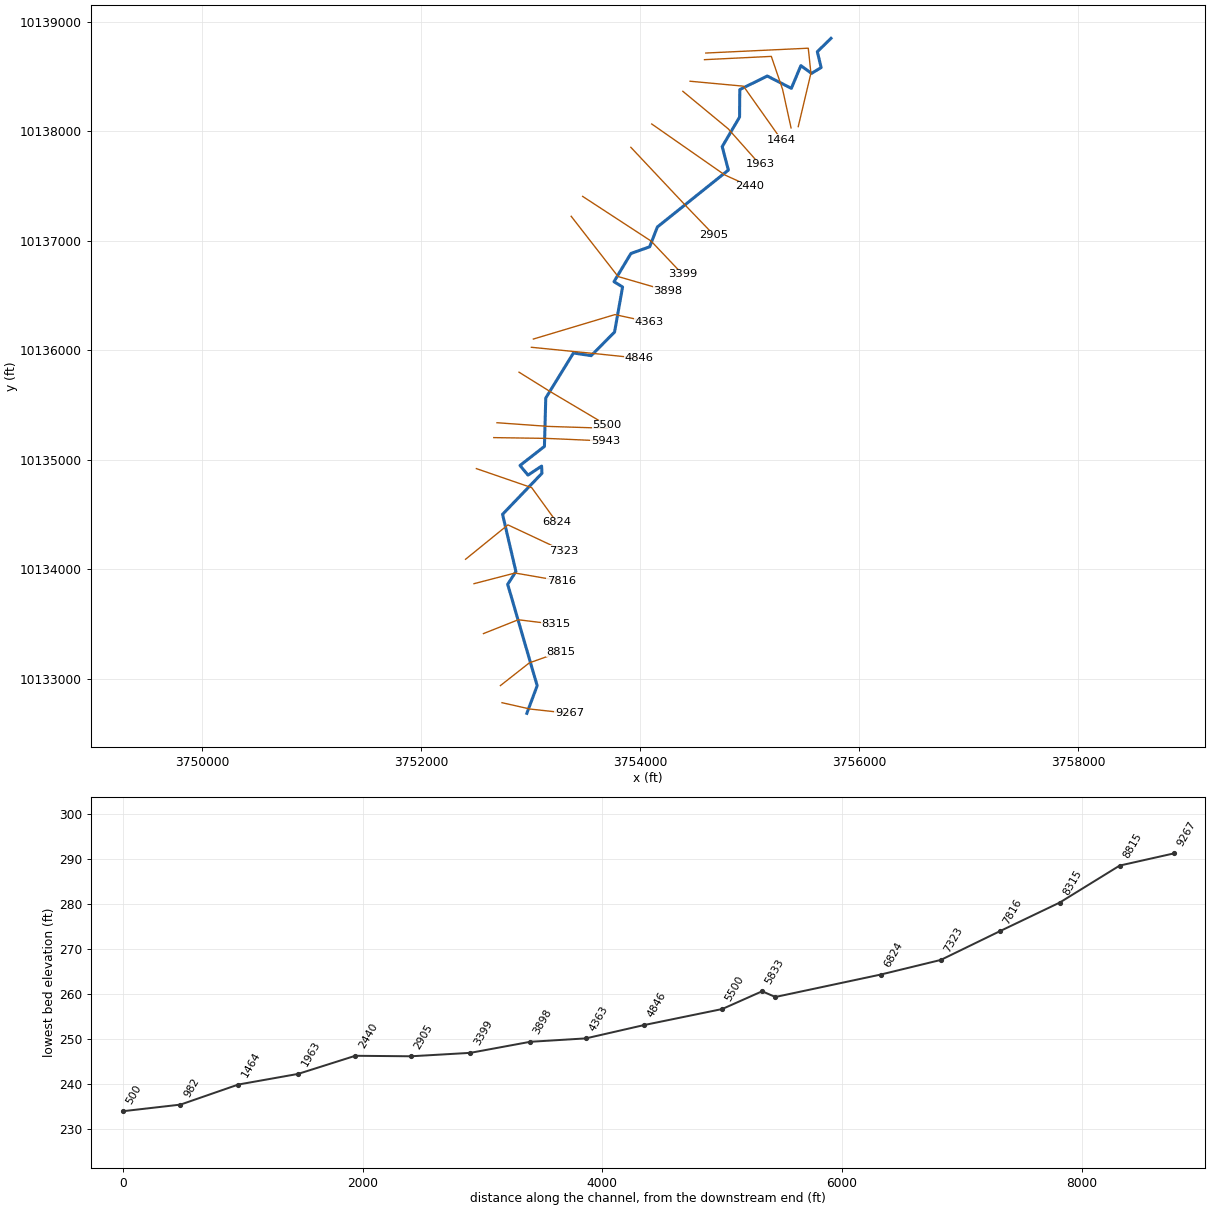
--- TOWN CREEK TRIBUTARY NO 2.prj (project) ---

Proj Title=TOWN CREEK TRIBUTARY NO 2 Base Level Engineering
Current Plan=p01
Default Exp/Contr=0.3,0.1
English Units
Geom File=g01
Flow File=f01
Plan File=p01
Y Axis Title=Elevation
X Axis Title(PF)=Main Channel Distance
X Axis Title(XS)=Station
BEGIN DESCRIPTION:
TOWN CREEK TRIBUTARY NO 2
END DESCRIPTION:
DSS Export Rating Curves= 0
DSS Export Rating Curve Sorted= 0
DSS Export Volume Flow Curves= 0
DXF OffsetX= 0
DXF OffsetY= 0
DXF ScaleX= 1
DXF ScaleY= 10

--- TOWN CREEK TRIBUTARY NO 2.p01 (plan) ---

Plan Title=Multiple Run
Short Identifier=Multiple
Geom File=g01
Flow File=f01
Subcritical Flow
K Sum by GR= 0
Std Step Tol= 0.01
Critical Tol= 0.01
Num of Std Step Trials= 20
Max Error Tol= 0.3
Flow Tol Ratio= 0.001
Split Flow NTrial= 30
Split Flow Tol= 0.02
Split Flow Ratio= 0.02
Log Output Level= 0
Friction Slope Method= 1
Unsteady Friction Slope Method= 2
Unsteady Bridges Friction Slope Method= 1
Parabolic Critical Depth
Global Vel Dist=  1 , 1 , 1
Global Log Level= 0
CheckData=True
Encroach Param= -1, 0, 0, 0
BEGIN DESCRIPTION:
Multiple Run
END DESCRIPTION:

--- TOWN CREEK TRIBUTARY NO 2.f01 (steady flow) ---

Flow Title=Multiple
Program Version=4.10
Number of Profiles= 7
Profile Names=10-year,25-year,50-year,1pct_min,100-year,1pct_plu,500-year
River Rch & RM=TOWN CREEK TRIBU,Reach-1         ,9267
     200     253     328     141     426    1286     736
River Rch & RM=TOWN CREEK TRIBU,Reach-1         ,8315
     815    1126    1543     696    2102    6348    4030
River Rch & RM=TOWN CREEK TRIBU,Reach-1         ,3399
     921    1282    1766     800    2415    7293    4675
Boundary for River Rch & Prof#=TOWN CREEK TRIBU,Reach-1         , 1
Up Type= 0
Dn Type= 3
Dn Slope=0.005
Boundary for River Rch & Prof#=TOWN CREEK TRIBU,Reach-1         , 2
Up Type= 0
Dn Type= 3
Dn Slope=0.005
Boundary for River Rch & Prof#=TOWN CREEK TRIBU,Reach-1         , 3
Up Type= 0
Dn Type= 3
Dn Slope=0.005
Boundary for River Rch & Prof#=TOWN CREEK TRIBU,Reach-1         , 4
Up Type= 0
Dn Type= 3
Dn Slope=0.005
Boundary for River Rch & Prof#=TOWN CREEK TRIBU,Reach-1         , 5
Up Type= 0
Dn Type= 3
Dn Slope=0.005
Boundary for River Rch & Prof#=TOWN CREEK TRIBU,Reach-1         , 6
Up Type= 0
Dn Type= 3
Dn Slope=0.005
Boundary for River Rch & Prof#=TOWN CREEK TRIBU,Reach-1         , 7
Up Type= 0
Dn Type= 3
Dn Slope=0.005
DSS Import GetInterval= 0
DSS Import GetPeak= 0
DSS Import FillOption= 0

--- TOWN CREEK TRIBUTARY NO 2.g01 (geometry) ---

Geom Title=Existing Conditions
Program Version=4.10

River Reach=TOWN CREEK TRIBU,Reach-1
Reach XY= 30
      3752963.71     10132682.74      3753058.27     10132935.01
      3752788.89     10133861.13      3752863.96     10133977.99
      3752741.96     10134500.47      3753101.51     10134874.73
       3753098.8     10134940.99      3752974.41     10134858.51
       3752901.4     10134946.39      3753124.49     10135120.82
      3753136.66     10135562.95       3753389.5     10135973.99
      3753551.75     10135949.65      3753764.91     10136165.33
       3753838.3     10136577.14      3753759.87     10136625.18
      3753914.54     10136883.11      3754085.33     10136943.67
      3754156.13     10137125.01      3754804.62     10137644.57
      3754748.29     10137858.79      3754906.78     10138128.61
      3754908.82     10138379.86      3755159.98      10138503.7
      3755379.89     10138391.43      3755466.69     10138598.61
      3755563.92     10138528.01      3755651.88     10138581.25
      3755617.16     10138725.92      3755742.01     10138848.07

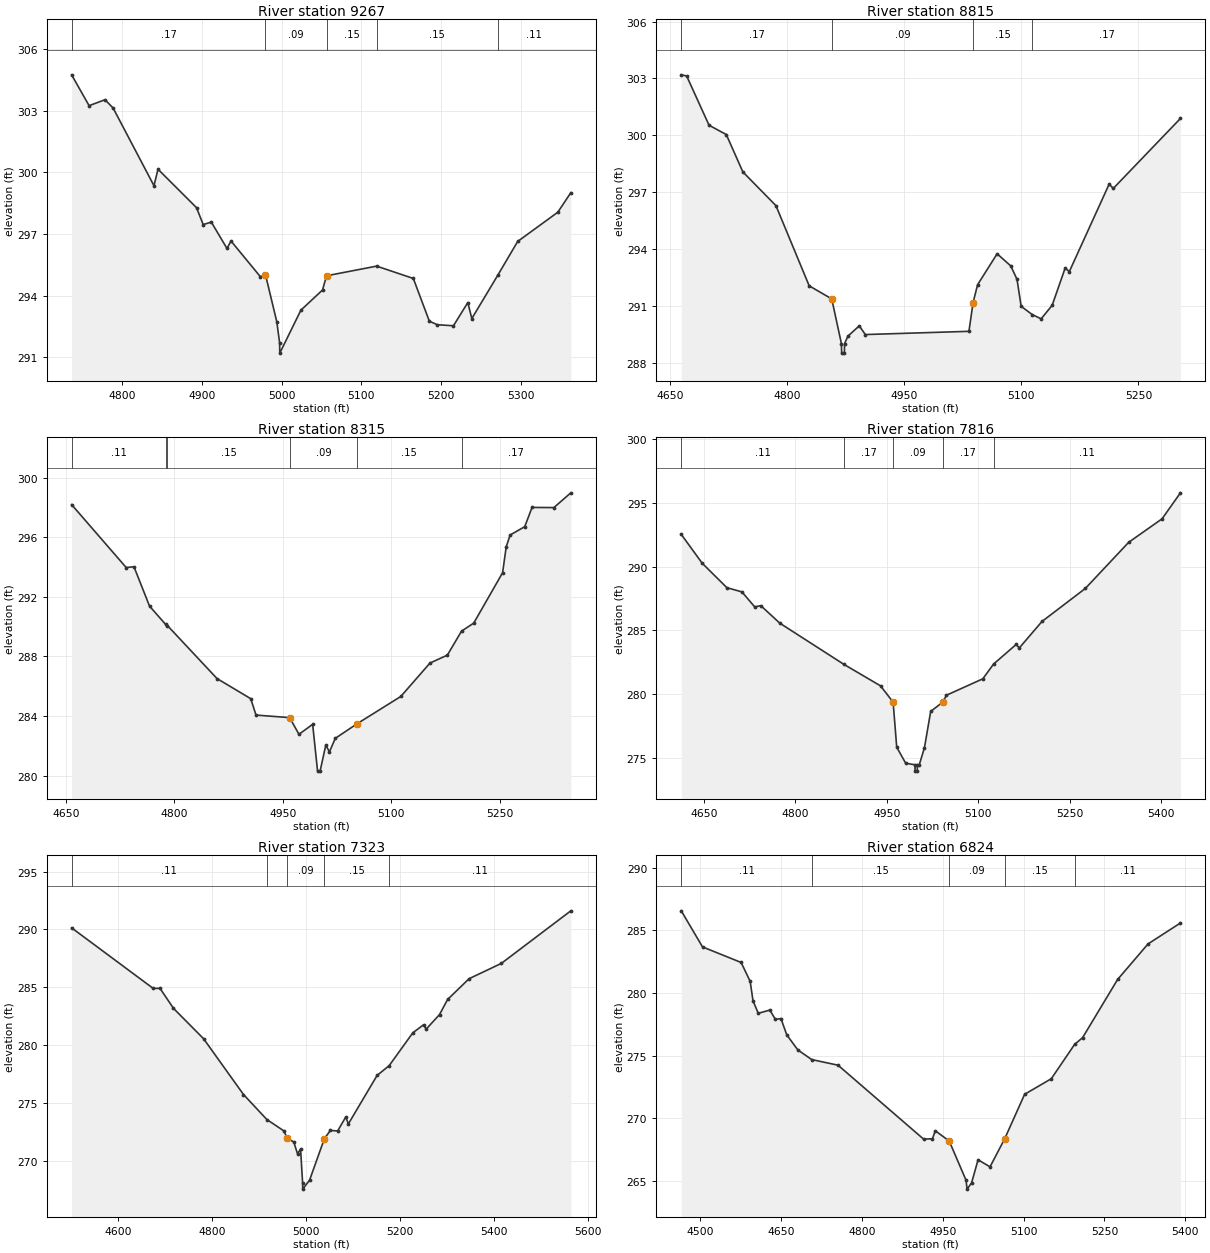
Type RM Length L Ch R = 1 ,9267    ,452,452,452
BEGIN DESCRIPTION:
TOWN CREEK TRIBUTARY NO 2 18.0
END DESCRIPTION:
XS GIS Cut Line= 3
      3752737.02     10132779.89      3752993.65     10132721.89
      3753354.08     10132682.29
#Sta/Elev= 30
  4736.9  304.74  4758.8  303.24  4778.8  303.53    4789  303.12  4840.1  299.35
  4845.2  300.15  4893.5  298.28  4901.8  297.46    4912  297.58  4931.6   296.3
  4936.7  296.66  4973.6  294.92  4979.9  295.02  4994.1  292.73  4997.6  291.71
  4997.8  291.21  5024.3   293.3  5051.4  294.28  5056.4  294.97  5119.2  295.44
  5165.2  294.84  5185.3  292.76  5195.4  292.59  5215.5  292.54  5233.5  293.67
  5238.5  292.89  5271.1     295    5296  296.64  5346.3  298.06  5362.6  299.01
#Mann= 5 ,-1 , 0
  4736.9     .17       0  4979.9     .09       0  5056.4     .15       0
  5119.2     .15       0  5271.1     .11       0
Bank Sta=4979.9,5056.4
XS Rating Curve= 0 ,0
Exp/Cntr=0.3,0.1

Type RM Length L Ch R = 1 ,8815    ,500,500,500
BEGIN DESCRIPTION:
TOWN CREEK TRIBUTARY NO 2 17.0
END DESCRIPTION:
XS GIS Cut Line= 3
      3752722.46     10132936.01       3752986.5     10133143.49
      3753272.71     10133245.35
#Sta/Elev= 30
  4664.2  303.19  4671.1  303.13  4699.8  300.53  4721.9  300.04  4743.1  298.07
  4785.5  296.29  4828.1  292.06    4857  291.37  4869.4  289.01  4869.7  288.51
  4873.2  288.51  4873.4  289.01  4877.8  289.41  4892.3  289.95    4900  289.49
  5032.8  289.66  5038.1  291.18  5043.9  292.12  5068.9  293.75  5086.4  293.11
  5094.4   292.4  5099.7  290.98    5114  290.54  5125.3  290.32  5139.4  291.03
  5156.1     293  5161.4  292.81  5212.4  297.42  5217.8   297.2  5303.8  300.89
#Mann= 4 ,-1 , 0
  4664.2     .17       0    4857     .09       0  5038.1     .15       0
    5114     .17       0
Bank Sta=4857,5038.1
XS Rating Curve= 0 ,0
Exp/Cntr=0.3,0.1

Type RM Length L Ch R = 1 ,8315    ,499,499,499
BEGIN DESCRIPTION:
TOWN CREEK TRIBUTARY NO 2 16.0
END DESCRIPTION:
XS GIS Cut Line= 3
      3752567.81     10133411.05      3752885.36     10133537.48
      3753231.09     10133495.18
#Sta/Elev= 30
  4658.2  298.19  4733.6  293.97  4744.4  294.02  4765.9  291.38  4788.2  290.15
  4790.7  290.07  4859.2  286.52  4905.8  285.17  4913.1  284.07  4959.6   283.9
  4972.5  282.78  4991.4  283.45  4998.2  280.31  5001.7  280.31  5009.6  282.06
  5014.6   281.6  5022.7  282.51  5052.9  283.49  5113.3  285.32  5153.6  287.56
  5177.6  288.09  5197.2   289.7  5214.1  290.24    5254  293.62    5259  295.36
  5264.4  296.15  5284.6  296.71  5294.7     298  5324.9  297.99  5348.3  298.98
#Mann= 6 ,-1 , 0
  4658.2     .11       0  4788.2     .17       0  4790.7     .15       0
  4959.6     .09       0  5052.9     .15       0  5197.2     .17       0
Bank Sta=4959.6,5052.9
XS Rating Curve= 0 ,0
Exp/Cntr=0.3,0.1

Type RM Length L Ch R = 1 ,7816    ,493,493,493
BEGIN DESCRIPTION:
TOWN CREEK TRIBUTARY NO 2 15.0
END DESCRIPTION:
XS GIS Cut Line= 3
      3752481.55     10133866.95      3752856.01     10133964.29
       3753281.6     10133890.76
#Sta/Elev= 30
  4613.1  292.53  4647.4  290.27  4687.9  288.35  4712.6  288.02  4733.6  286.84
  4743.6  286.94  4774.6  285.57  4879.7  282.34  4939.9  280.65  4960.6  279.37
  4966.5  275.84  4981.2  274.58  4996.4  274.46  4996.6  273.96  5000.1  273.96
  5000.4  274.46  5003.5  274.46    5012   275.8  5022.2  278.64  5042.5  279.39
  5047.9  279.91  5107.7   281.2  5125.4  282.36  5162.5   283.9  5167.5  283.62
  5204.8   285.7  5275.9  288.29    5347  291.91  5401.7  293.75  5431.9  295.79
#Mann= 5 ,-1 , 0
  4613.1     .11       0  4879.7     .17       0  4960.6     .09       0
  5042.5     .17       0  5125.4     .11       0
Bank Sta=4960.6,5042.5
XS Rating Curve= 0 ,0
Exp/Cntr=0.3,0.1

Type RM Length L Ch R = 1 ,7323    ,499,499,499
BEGIN DESCRIPTION:
TOWN CREEK TRIBUTARY NO 2 14.0
END DESCRIPTION:
XS GIS Cut Line= 3
      3752404.24     10134090.03      3752791.11     10134404.09
       3753300.6     10134165.24
#Sta/Elev= 30
  4501.7  290.14  4675.1  284.91  4689.5  284.92  4718.2  283.19  4782.1  280.57
    4867  275.75  4916.7  273.59  4953.1   272.6  4959.6  271.98  4973.9  271.65
  4981.9  270.62  4988.3  271.05  4992.7  268.08  4992.9  267.58  5007.4  268.35
  5038.8  271.92  5051.6  272.65  5067.1   272.6  5084.4  273.81  5089.9  273.21
    5151   277.4  5176.6  278.24  5226.9  281.08  5249.7  281.77  5255.2  281.39
  5283.6  282.65  5300.9  283.96  5346.5  285.75    5415  287.07  5562.7  291.61
#Mann= 5 ,-1 , 0
  4501.7     .11       0  4916.7     .15       0  4959.6     .09       0
  5038.8     .15       0  5176.6     .11       0
Bank Sta=4959.6,5038.8
XS Rating Curve= 0 ,0
Exp/Cntr=0.3,0.1

Type RM Length L Ch R = 1 ,6824    ,881,881,881
BEGIN DESCRIPTION:
TOWN CREEK TRIBUTARY NO 2 13.0
END DESCRIPTION:
XS GIS Cut Line= 3
      3752502.87       10134918.       3753008.5     10134743.78
      3753237.82     10134426.97
#Sta/Elev= 30
  4465.2  286.56  4504.6  283.68  4576.2  282.44    4593  280.93  4598.3  279.38
    4608  278.38  4629.5  278.64  4639.7   277.9  4650.1  277.96  4660.9  276.66
  4681.4  275.46  4707.1  274.69    4756  274.24  4914.7  268.34  4931.1  268.37
  4936.4  269.01  4962.3  268.18  4993.5  265.05  4995.3  264.35  5003.7  264.85
  5015.7  266.69  5037.9  266.13  5065.1  268.37  5102.1  271.92  5151.5  273.16
  5194.8   275.9  5209.6  276.44  5274.5  281.08    5331  283.92  5391.1  285.59
#Mann= 5 ,-1 , 0
  4465.2     .11       0  4707.1     .15       0  4962.3     .09       0
  5065.1     .15       0  5194.8     .11       0
Bank Sta=4962.3,5065.1
XS Rating Curve= 0 ,0
Exp/Cntr=0.3,0.1

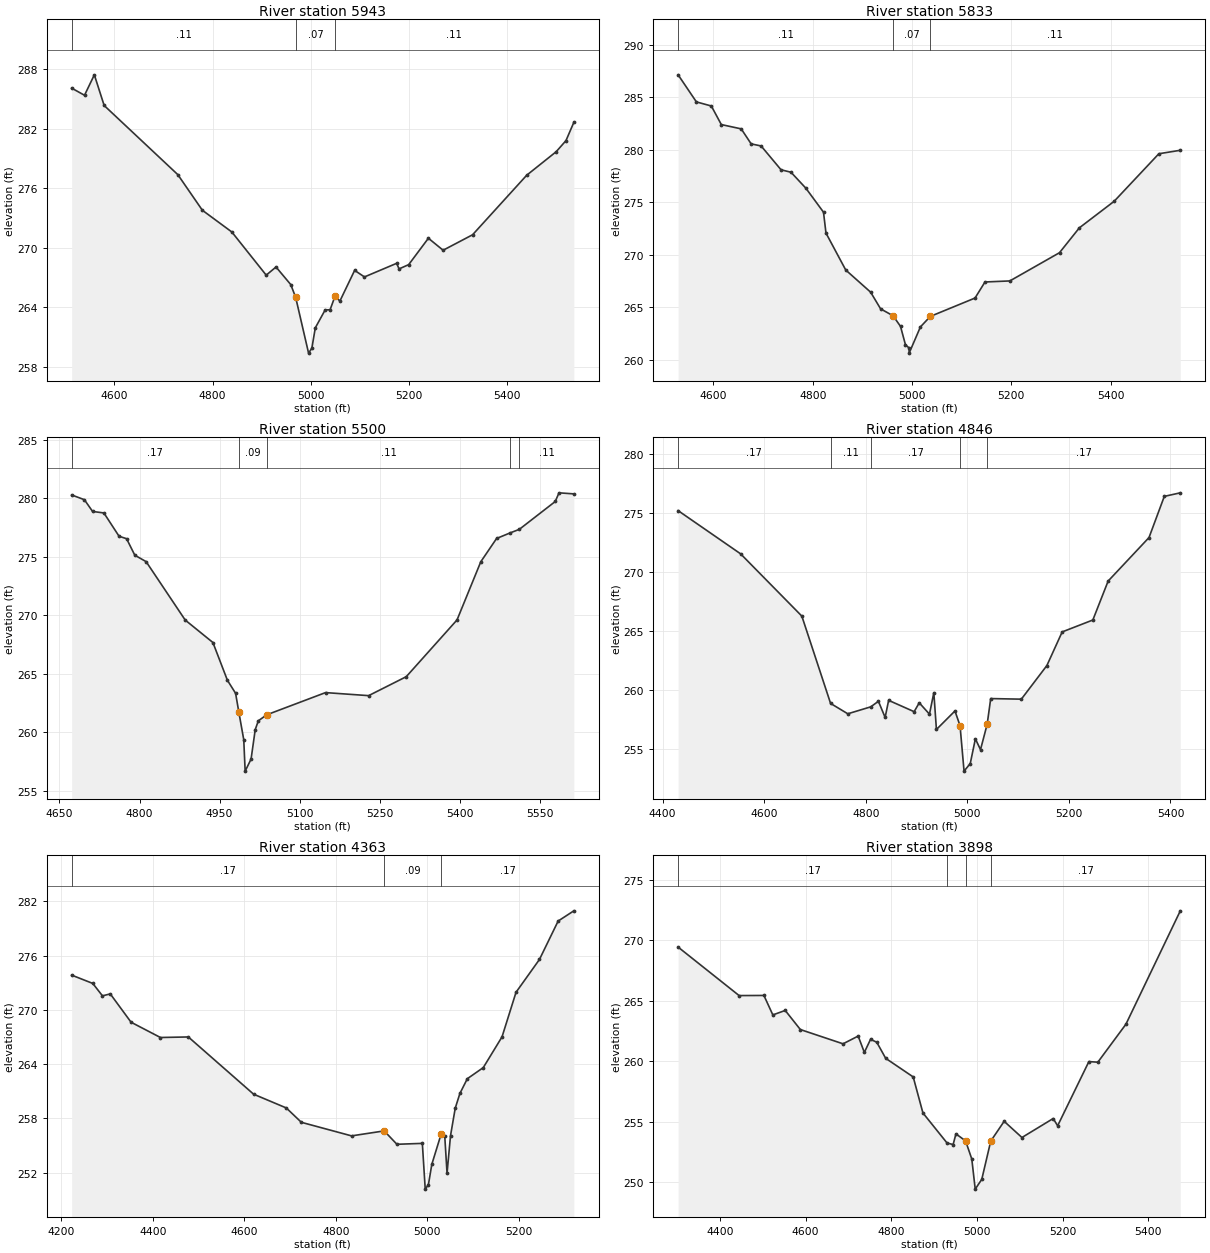
Type RM Length L Ch R = 1 ,5943    ,110,110,110
BEGIN DESCRIPTION:
TOWN CREEK TRIBUTARY NO 2 11.0
END DESCRIPTION:
XS GIS Cut Line= 3
      3752661.68     10135201.15      3753148.83     10135193.83
       3753683.8     10135170.09
#Sta/Elev= 30
  4512.8  286.07    4539  285.35    4559  287.41    4579  284.32    4729  277.35
    4779  273.76    4839  271.57    4909  267.22    4929  268.04    4959  266.27
    4969  264.98  4995.3  259.36    5002  259.86    5009  261.91  5029.1  263.72
  5039.1  263.73  5049.1  265.09  5059.1  264.61  5089.1   267.7  5109.1  267.04
  5174.6  268.41  5179.6  267.85  5199.2  268.28  5239.3  270.94  5269.3  269.73
  5329.3  271.29  5439.5  277.29  5499.5  279.66  5519.5  280.78  5535.5  282.62
#Mann= 3 , 0 , 0
  4512.8     .11       0    4969     .07       0  5049.1     .11       0
Bank Sta=4969,5049.1
XS Rating Curve= 0 ,0
Exp/Cntr=0.3,0.1

Type RM Length L Ch R = 1 ,5833    ,333,333,333
BEGIN DESCRIPTION:
TOWN CREEK TRIBUTARY NO 2 10.0
END DESCRIPTION:
XS GIS Cut Line= 3
       3752691.1     10135337.01        3753161.     10135303.35
      3753701.03     10135286.27
#Sta/Elev= 30
  4528.9  287.15  4565.7  284.57  4595.8  284.18  4615.9  282.41    4656     282
    4676  280.57  4696.1  280.37  4736.2   278.1  4756.2  277.87  4786.3  276.34
  4821.7  274.06  4826.7  272.07  4866.5  268.55  4916.6  266.44  4936.7  264.85
  4961.8  264.19  4976.8  263.18  4986.8  261.42  4993.9  261.13  4994.2  260.63
  5016.9  263.13  5036.9  264.13  5126.9  265.88  5146.9  267.41    5197  267.51
    5297   270.2    5337  272.57  5407.1   275.1  5497.1  279.63  5540.3  279.96
#Mann= 3 , 0 , 0
  4528.9     .11       0  4961.8     .07       0  5036.9     .11       0
Bank Sta=4961.8,5036.9
XS Rating Curve= 0 ,0
Exp/Cntr=0.3,0.1

Type RM Length L Ch R = 1 ,5500    ,654,654,654
BEGIN DESCRIPTION:
TOWN CREEK TRIBUTARY NO 2 10.5
END DESCRIPTION:
XS GIS Cut Line= 3
      3752892.47     10135798.61      3753170.12     10135625.68
      3753697.77     10135312.48
#Sta/Elev= 30
  4672.9  280.29  4696.8  279.88  4712.1  278.88  4733.3  278.75  4761.7  276.76
  4775.8  276.55  4791.2  275.14  4812.4  274.59  4885.6   269.6  4937.5  267.68
  4964.7  264.45    4980  263.34  4985.9  261.78  4995.3  259.37  4997.9  256.69
    5009  257.72  5016.8  260.24  5022.6  260.99  5038.2   261.5  5148.5   263.4
  5229.2  263.14  5299.7  264.76  5394.8  269.61  5439.3  274.58  5468.9  276.57
  5494.5  277.05  5511.5  277.35  5578.8  279.73  5585.8  280.47  5613.6  280.38
#Mann= 5 ,-1 , 0
  4672.9     .17       0  4985.9     .09       0  5038.2     .11       0
  5494.5     .17       0  5511.5     .11       0
Bank Sta=4985.9,5038.2
XS Rating Curve= 0 ,0
Exp/Cntr=0.3,0.1

Type RM Length L Ch R = 1 ,4846    ,483,483,483
BEGIN DESCRIPTION:
TOWN CREEK TRIBUTARY NO 2 9.0
END DESCRIPTION:
XS GIS Cut Line= 3
      3753005.41     10136026.12      3753572.04     10135969.93
      3753989.16     10135926.27
#Sta/Elev= 30
  4430.6   275.2  4553.6  271.54  4674.2  266.26  4730.8  258.86  4764.7  257.98
  4809.9  258.57    4825  259.04  4838.2  257.67  4845.1  259.12  4895.3  258.16
  4905.4  258.91  4925.5  257.95  4934.1  259.77  4939.2  256.65  4975.7  258.22
  4985.7  256.97  4993.6  253.12  5005.8  253.76  5015.9  255.86    5026  254.94
  5039.1  257.09  5046.1  259.27  5106.4  259.22  5156.7  262.07  5186.8  264.92
  5247.2  265.93  5277.3  269.23  5357.8  272.92  5387.9  276.41  5419.4  276.71
#Mann= 5 ,-1 , 0
  4430.6     .17       0  4730.8     .11       0  4809.9     .17       0
  4985.7     .09       0  5039.1     .17       0
Bank Sta=4985.7,5039.1
XS Rating Curve= 0 ,0
Exp/Cntr=0.3,0.1

Type RM Length L Ch R = 1 ,4363    ,465,465,465
BEGIN DESCRIPTION:
TOWN CREEK TRIBUTARY NO 2 8.0
END DESCRIPTION:
XS GIS Cut Line= 3
      3753023.38      10136101.4      3753768.25     10136324.63
      3754081.37     10136257.21
#Sta/Elev= 30
  4222.4  273.85  4268.6  272.93  4289.7  271.56  4306.9  271.77  4352.3  268.64
  4416.5  266.95  4477.5  267.01  4620.2  260.68  4691.6  259.16  4724.6  257.57
  4834.3  256.07  4905.7  256.62  4933.5  255.14  4989.1  255.24  4995.4  250.18
  5002.4  250.68  5009.8  252.92  5030.3  256.29    5038  256.11  5043.1  251.94
  5050.7  256.09    5061  259.13  5071.2  260.76  5087.4  262.39  5122.3  263.62
  5163.3  267.02  5193.9  271.95  5245.1  275.58    5286  279.83  5320.3  280.96
#Mann= 3 , 0 , 0
  4222.4     .17       0  4905.7     .09       0  5030.3     .17       0
Bank Sta=4905.7,5030.3
XS Rating Curve= 0 ,0
Exp/Cntr=0.3,0.1

Type RM Length L Ch R = 1 ,3898    ,499,499,499
BEGIN DESCRIPTION:
TOWN CREEK TRIBUTARY NO 2 7.0
END DESCRIPTION:
XS GIS Cut Line= 3
       3753368.8     10137222.64      3753797.07     10136672.35
      3754252.66     10136540.09
#Sta/Elev= 30
  4302.7  269.44    4445  265.43  4502.9  265.44  4523.7  263.83  4552.6   264.2
  4587.9  262.62  4687.5  261.44  4722.8  262.08  4737.2  260.73  4751.7  261.81
  4766.2  261.57    4787  260.24  4851.2   258.7  4873.9  255.72  4930.3  253.23
  4944.4  253.11  4950.9  253.99  4973.4  253.41  4987.9  251.91  4995.9  249.42
  5011.2  250.23  5032.1  253.39  5063.4  255.03  5104.9  253.69  5177.8  255.26
  5188.2  254.66  5261.1  259.97    5282  259.92  5347.5  263.06  5474.4  272.44
#Mann= 4 ,-1 , 0
  4302.7     .17       0  4930.3     .11       0  4973.4     .06       0
  5032.1     .17       0
Bank Sta=4973.4,5032.1
XS Rating Curve= 0 ,0
Exp/Cntr=0.3,0.1

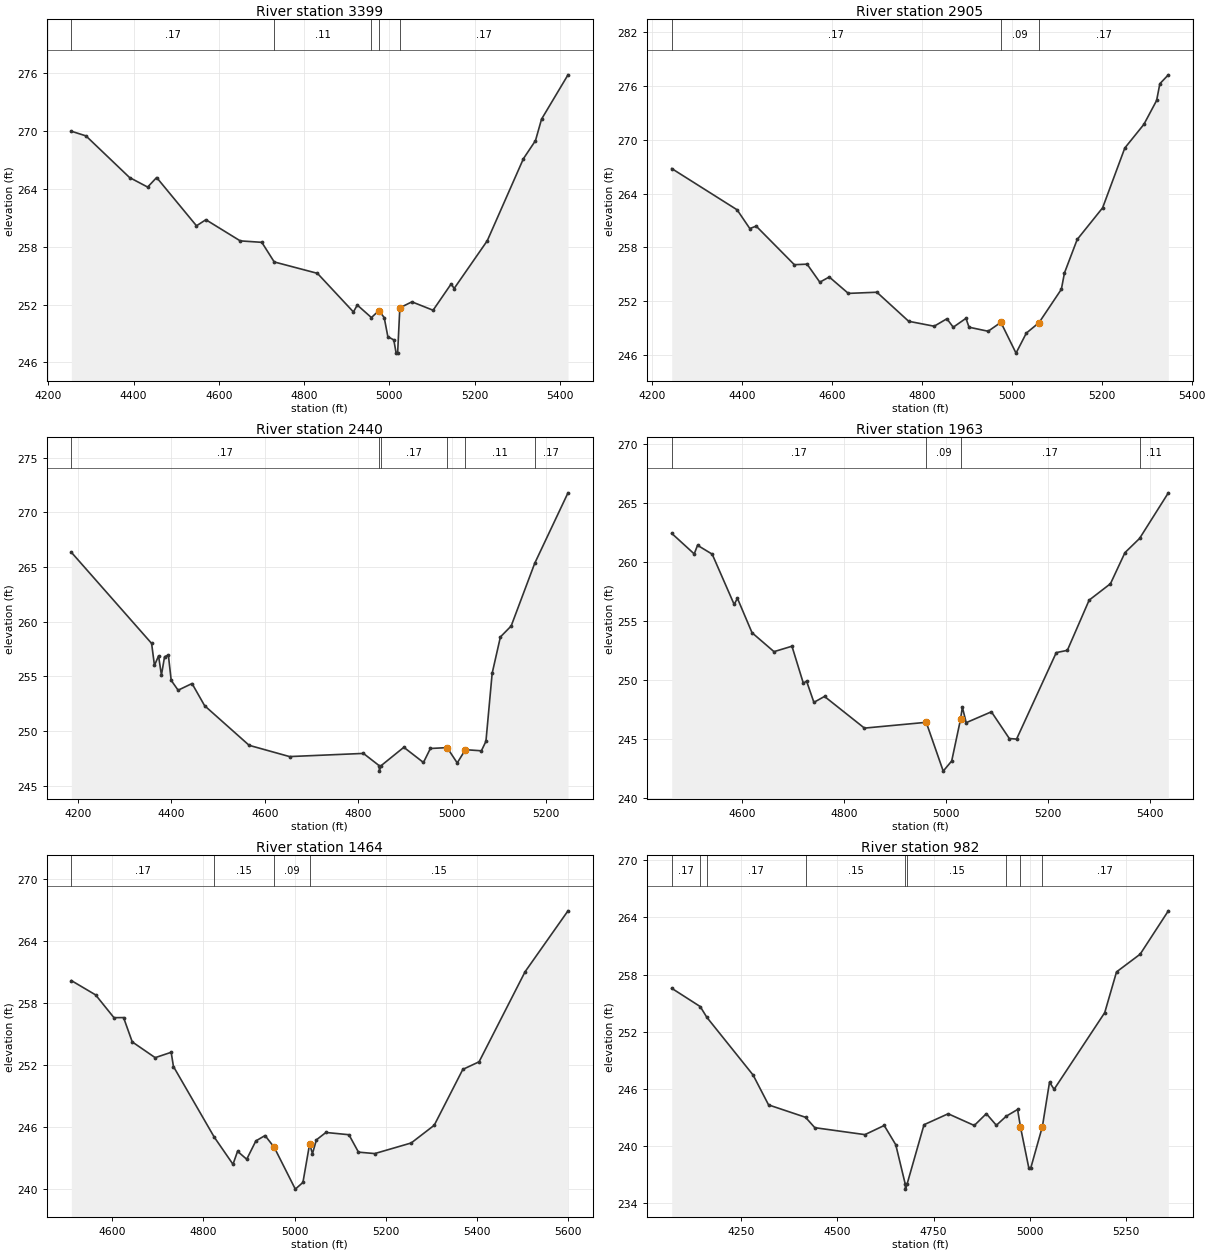
Type RM Length L Ch R = 1 ,3399    ,494,494,494
BEGIN DESCRIPTION:
TOWN CREEK TRIBUTARY NO 2 6.0
END DESCRIPTION:
XS GIS Cut Line= 3
      3753473.55     10137404.33      3754098.32     10136996.68
      3754386.88     10136692.34
#Sta/Elev= 30
    4254  269.94  4288.2  269.46  4390.5  265.15    4433  264.16  4454.1  265.15
  4547.6  260.15  4569.6  260.78  4650.3  258.59  4700.9  258.44    4730  256.41
  4831.4  255.23  4915.9  251.23  4924.9  251.95  4958.1  250.65  4975.6  251.37
  4988.1  250.65  4996.7  248.67  5010.6  248.34  5016.1  246.97  5019.6  246.97
  5024.8  251.66  5053.1  252.28  5102.8  251.41  5145.3  254.14  5152.2  253.66
  5229.9   258.6  5314.8   267.1  5343.1  268.97  5357.3  271.19  5419.4  275.78
#Mann= 5 ,-1 , 0
    4254     .17       0    4730     .11       0  4958.1     .17       0
  4975.6     .09       0  5024.8     .17       0
Bank Sta=4975.6,5024.8
XS Rating Curve= 0 ,0
Exp/Cntr=0.3,0.1

Type RM Length L Ch R = 1 ,2905    ,465,465,465
BEGIN DESCRIPTION:
TOWN CREEK TRIBUTARY NO 2 5.0
END DESCRIPTION:
XS GIS Cut Line= 3
      3753913.81     10137852.71      3754432.56     10137301.12
       3754673.9     10137050.27
#Sta/Elev= 30
  4242.8  266.79  4388.3  262.19  4416.6   260.1  4430.8  260.37  4515.7  256.07
  4544.1  256.13  4572.4  254.12  4593.4   254.7  4635.9  252.87  4699.4     253
  4770.2  249.76  4826.9  249.21  4855.2  250.04  4869.4   249.1  4897.7  250.09
  4904.5   249.1    4947  248.65  4975.4  249.64  5009.1  246.21    5032  248.44
  5060.3  249.61    5110  253.33  5116.9  255.15  5145.2  258.88  5201.8  262.41
  5251.2  269.08  5293.7  271.72    5322  274.38  5329.2  276.25  5348.1  277.24
#Mann= 3 , 0 , 0
  4242.8     .17       0  4975.4     .09       0  5060.3     .17       0
Bank Sta=4975.4,5060.3
XS Rating Curve= 0 ,0
Exp/Cntr=0.3,0.1

Type RM Length L Ch R = 1 ,2440    ,477,477,477
BEGIN DESCRIPTION:
TOWN CREEK TRIBUTARY NO 2 4.0
END DESCRIPTION:
XS GIS Cut Line= 3
      3754104.45     10138065.79      3754771.85     10137600.29
      3754997.49     10137497.61
#Sta/Elev= 30
  4186.3  266.33  4357.8     258  4363.9  255.99  4372.7  256.86  4378.8   255.1
  4385.5  256.78  4393.6  256.94  4399.7  254.62  4414.5  253.72  4444.2  254.33
  4471.2   252.3  4566.3  248.68  4652.7  247.65  4810.6  247.94  4844.3  246.82
  4844.6  246.32  4848.4  246.82    4897   248.5  4938.9  247.11  4953.7  248.39
  4989.5  248.47  5011.1  247.07  5028.6  248.28  5062.8  248.18  5072.5  249.05
  5085.8  255.27  5103.4  258.59  5126.4  259.59  5176.7  265.32  5247.9  271.77
#Mann= 6 ,-1 , 0
  4186.3     .17       0  4844.3     .12       0  4848.4     .17       0
  4989.5     .09       0  5028.6     .11       0  5176.7     .17       0
Bank Sta=4989.5,5028.6
XS Rating Curve= 0 ,0
Exp/Cntr=0.3,0.1

Type RM Length L Ch R = 1 ,1963    ,499,499,499
BEGIN DESCRIPTION:
TOWN CREEK TRIBUTARY NO 2 3.0
END DESCRIPTION:
XS GIS Cut Line= 3
      3754388.89     10138364.24      3754803.29     10138021.46
      3755092.39     10137696.02
#Sta/Elev= 30
  4462.2  262.42  4506.3  260.68  4512.8  261.41  4541.5  260.66  4584.5  256.41
    4591  256.92  4619.6  254.01  4662.6  252.41  4697.8  252.87    4720  249.75
  4726.5  249.91  4740.8  248.12  4761.6  248.62  4839.8  245.94  4960.9  246.43
  4994.2   242.3  5010.8  243.16 5028.08  246.68  5031.7  247.71  5039.2   246.4
  5088.6  247.32  5123.7  245.06  5137.9  245.01  5215.7  252.33  5237.4  252.52
  5280.1  256.77  5321.9  258.16  5350.3  260.79  5378.9  261.99  5435.3  265.85
#Mann= 4 ,-1 , 0
  4462.2     .17       0  4960.9     .09       0 5028.08     .17       0
  5378.9     .11       0
Bank Sta=4960.9,5028.08
XS Rating Curve= 0 ,0
Exp/Cntr=0.3,0.1

Type RM Length L Ch R = 1 ,1464    ,482,482,482
BEGIN DESCRIPTION:
TOWN CREEK TRIBUTARY NO 2 2.0
END DESCRIPTION:
XS GIS Cut Line= 3
      3754454.87     10138456.26      3754942.39     10138411.11
       3755288.8     10137921.58
#Sta/Elev= 30
  4510.4  260.18  4563.6  258.79  4603.8  256.58  4624.9  256.59  4643.9  254.23
  4694.2   252.7  4729.3  253.22  4734.3  251.84  4823.6     245  4864.9  242.35
  4874.9  243.61    4895  242.84  4915.1  244.62  4935.2  245.14  4955.3     244
  5001.6  239.94  5018.3  240.59    5033  244.33  5039.2  243.38  5047.8  244.72
  5068.7  245.44  5119.2  245.22  5140.1  243.53  5175.8  243.39  5255.8  244.42
  5306.3  246.14    5369  251.56  5404.7   252.3  5505.6  261.04  5599.7  266.95
#Mann= 4 ,-1 , 0
  4510.4     .17       0  4823.6     .15       0  4955.3     .09       0
    5033     .15       0
Bank Sta=4955.3,5033
XS Rating Curve= 0 ,0
Exp/Cntr=0.3,0.1

Type RM Length L Ch R = 1 ,982     ,482,482,482
BEGIN DESCRIPTION:
TOWN CREEK TRIBUTARY NO 2 1.0
END DESCRIPTION:
XS GIS Cut Line= 4
      3754586.56     10138653.23      3755196.78     10138683.21
      3755300.03     10138381.02       3755377.2     10138029.59
#Sta/Elev= 30
  4069.7  256.57  4143.8  254.65  4160.8  253.53  4281.2  247.46  4321.3  244.33
  4417.3  243.03  4441.4  241.94  4571.6  241.21  4621.7  242.17  4651.7  240.15
  4676.5  235.99  4676.8  235.49  4680.9  235.99  4725.1  242.25  4787.8   243.4
  4855.7  242.17    4887  243.41    4913  242.19  4938.9  243.15  4968.2  243.85
  4975.7  242.01  4997.3  237.72  5002.5  237.72 5032.62  242.06  5051.1  246.71
  5063.1  245.97  5194.5  254.01  5225.2  258.29  5286.6  260.15  5359.8   264.7
#Mann= 9 ,-1 , 0
  4069.7     .17       0  4143.8     .15       0  4160.8     .17       0
  4417.3     .15       0  4676.5     .12       0  4680.9     .15       0
  4938.9     .17       0  4975.7     .09       0 5032.62     .17       0
Bank Sta=4975.7,5032.62
XS Rating Curve= 0 ,0
Exp/Cntr=0.3,0.1

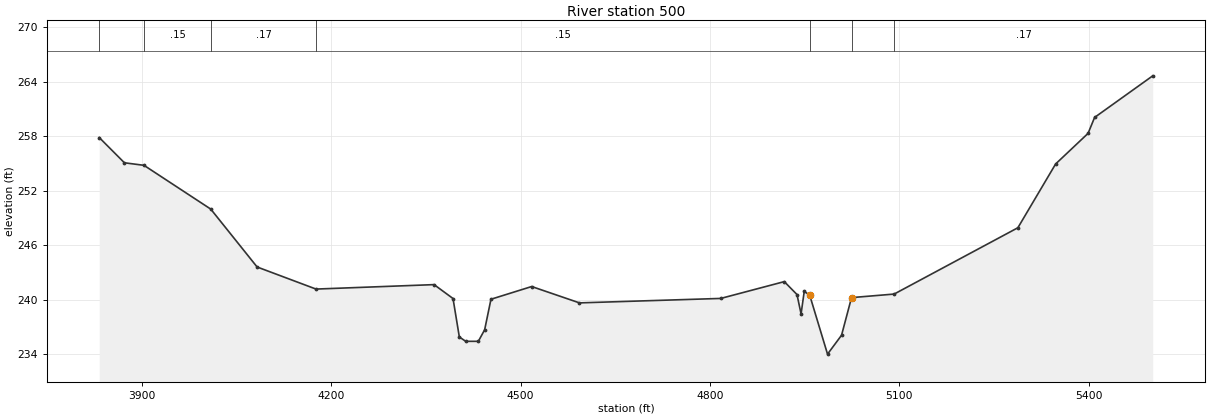
Type RM Length L Ch R = 1 ,500     ,0,0,0
BEGIN DESCRIPTION:
TOWN CREEK TRIBUTARY NO 2 1.5
END DESCRIPTION:
XS GIS Cut Line= 4
      3754598.05      10138713.8      3755534.33     10138757.99
      3755558.55      10138529.2      3755442.76     10138041.45
#Sta/Elev= 30
  3832.6  257.86  3872.5  255.08  3903.5   254.8  4009.3  249.98  4082.7  243.61
    4176  241.18    4363  241.67    4393  240.14    4403  235.91  4413.1  235.43
  4433.1  235.43  4443.1   236.7  4453.1  240.06  4517.6  241.46  4593.3  239.66
  4817.1  240.15  4917.7     242  4937.8  240.58  4944.3  238.45  4949.3  240.92
  4957.9  240.52  4986.2  234.02  5008.4   236.1  5024.2  240.24  5091.7  240.63
  5287.7  247.93  5347.5  254.95  5398.9  258.32  5409.2  260.07  5501.3  264.65
#Mann= 7 ,-1 , 0
  3832.6     .17       0  3903.5     .15       0  4009.3     .17       0
    4176     .15       0  4957.9     .09       0  5024.2     .15       0
  5091.7     .17       0
Bank Sta=4957.9,5024.2
XS Rating Curve= 0 ,0
Exp/Cntr=0.3,0.1

Chan Stop Cuts=-1
Use User Specified Reach Order=0
Composite Channel Slope=5