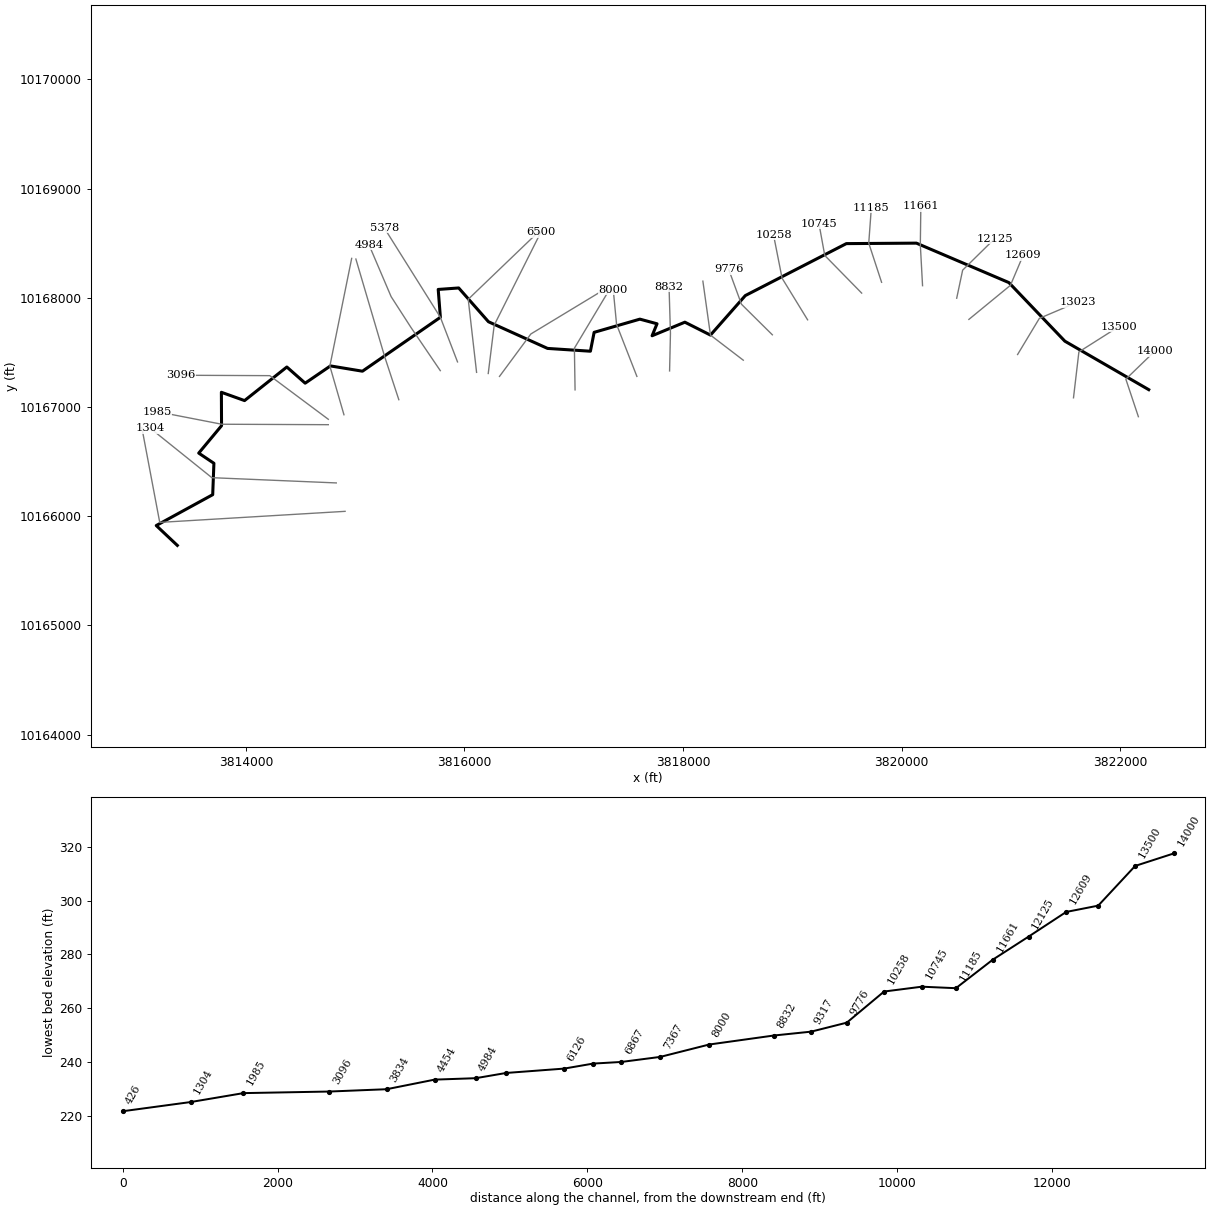
--- WEIRS CREEK TRIBUTARY NO 1.prj (project) ---

Proj Title=WEIRS CREEK TRIBUTARY NO 1 Base Level Engineering
Current Plan=p01
Default Exp/Contr=0.3,0.1
English Units
Geom File=g01
Flow File=f01
Plan File=p01
Y Axis Title=Elevation
X Axis Title(PF)=Main Channel Distance
X Axis Title(XS)=Station
BEGIN DESCRIPTION:
WEIRS CREEK TRIBUTARY NO 1
END DESCRIPTION:
DSS Export Rating Curves= 0
DSS Export Rating Curve Sorted= 0
DSS Export Volume Flow Curves= 0
DXF OffsetX= 0
DXF OffsetY= 0
DXF ScaleX= 1
DXF ScaleY= 10

--- WEIRS CREEK TRIBUTARY NO 1.p01 (plan) ---

Plan Title=Multiple Run
Short Identifier=Multiple
Geom File=g01
Flow File=f01
Subcritical Flow
K Sum by GR= 0
Std Step Tol= 0.01
Critical Tol= 0.01
Num of Std Step Trials= 20
Max Error Tol= 0.3
Flow Tol Ratio= 0.001
Split Flow NTrial= 30
Split Flow Tol= 0.02
Split Flow Ratio= 0.02
Log Output Level= 0
Friction Slope Method= 1
Unsteady Friction Slope Method= 2
Unsteady Bridges Friction Slope Method= 1
Parabolic Critical Depth
Global Vel Dist=  1 , 1 , 1
Global Log Level= 0
CheckData=True
Encroach Param= -1, 0, 0, 0
BEGIN DESCRIPTION:
Multiple Run
END DESCRIPTION:

--- WEIRS CREEK TRIBUTARY NO 1.f01 (steady flow) ---

Flow Title=Multiple
Program Version=4.10
Number of Profiles= 7
Profile Names=10-year,25-year,50-year,1pct_min,100-year,1pct_plu,500-year
River Rch & RM=WEIRS CREEK TRIB,Reach-1         ,14000
     264     339     444     192     580    1752    1022
River Rch & RM=WEIRS CREEK TRIB,Reach-1         ,12125
     729     999    1363     612    1849    5584    3517
River Rch & RM=WEIRS CREEK TRIB,Reach-1         ,6867
     748    1021    1389     622    1879    5674    3545
River Rch & RM=WEIRS CREEK TRIB,Reach-1         ,5378
    1255    1753    2421    1097    3312   10002    6416
River Rch & RM=WEIRS CREEK TRIB,Reach-1         ,4984
    1255    1753    2421    1097    3312   10002    6416
Boundary for River Rch & Prof#=WEIRS CREEK TRIB,Reach-1         , 1
Up Type= 0
Dn Type= 3
Dn Slope=0.005
Boundary for River Rch & Prof#=WEIRS CREEK TRIB,Reach-1         , 2
Up Type= 0
Dn Type= 3
Dn Slope=0.005
Boundary for River Rch & Prof#=WEIRS CREEK TRIB,Reach-1         , 3
Up Type= 0
Dn Type= 3
Dn Slope=0.005
Boundary for River Rch & Prof#=WEIRS CREEK TRIB,Reach-1         , 4
Up Type= 0
Dn Type= 3
Dn Slope=0.005
Boundary for River Rch & Prof#=WEIRS CREEK TRIB,Reach-1         , 5
Up Type= 0
Dn Type= 3
Dn Slope=0.005
Boundary for River Rch & Prof#=WEIRS CREEK TRIB,Reach-1         , 6
Up Type= 0
Dn Type= 3
Dn Slope=0.005
Boundary for River Rch & Prof#=WEIRS CREEK TRIB,Reach-1         , 7
Up Type= 0
Dn Type= 3
Dn Slope=0.005
DSS Import GetInterval= 0
DSS Import GetPeak= 0
DSS Import FillOption= 0

--- WEIRS CREEK TRIBUTARY NO 1.g01 (geometry) ---

Geom Title=Existing Conditions
Program Version=4.10

River Reach=WEIRS CREEK TRIB,Reach-1
Reach XY= 30
      3822262.54     10167158.72      3821495.09      10167602.7
      3820982.72     10168139.31      3820136.37     10168500.64
      3819495.09      10168496.3      3818570.49     10168020.43
      3818251.48     10167658.46      3818017.29     10167776.72
      3817717.29     10167652.41      3817762.43     10167762.14
      3817605.49      10167804.5      3817186.74     10167683.66
      3817152.71     10167510.75      3816760.35     10167536.44
      3816219.72     10167780.71      3815947.33     10168090.09
      3815759.83     10168076.55      3815779.62     10167821.34
      3815066.48     10167327.78      3814773.42      10167376.2
      3814542.18     10167218.13      3814374.38     10167366.25
      3813987.48     10167058.65      3813775.35     10167134.71
      3813776.86      10166828.6      3813567.98     10166577.65
      3813706.95     10166484.41      3813695.93     10166196.93
      3813179.24     10165914.28       3813372.2     10165732.28

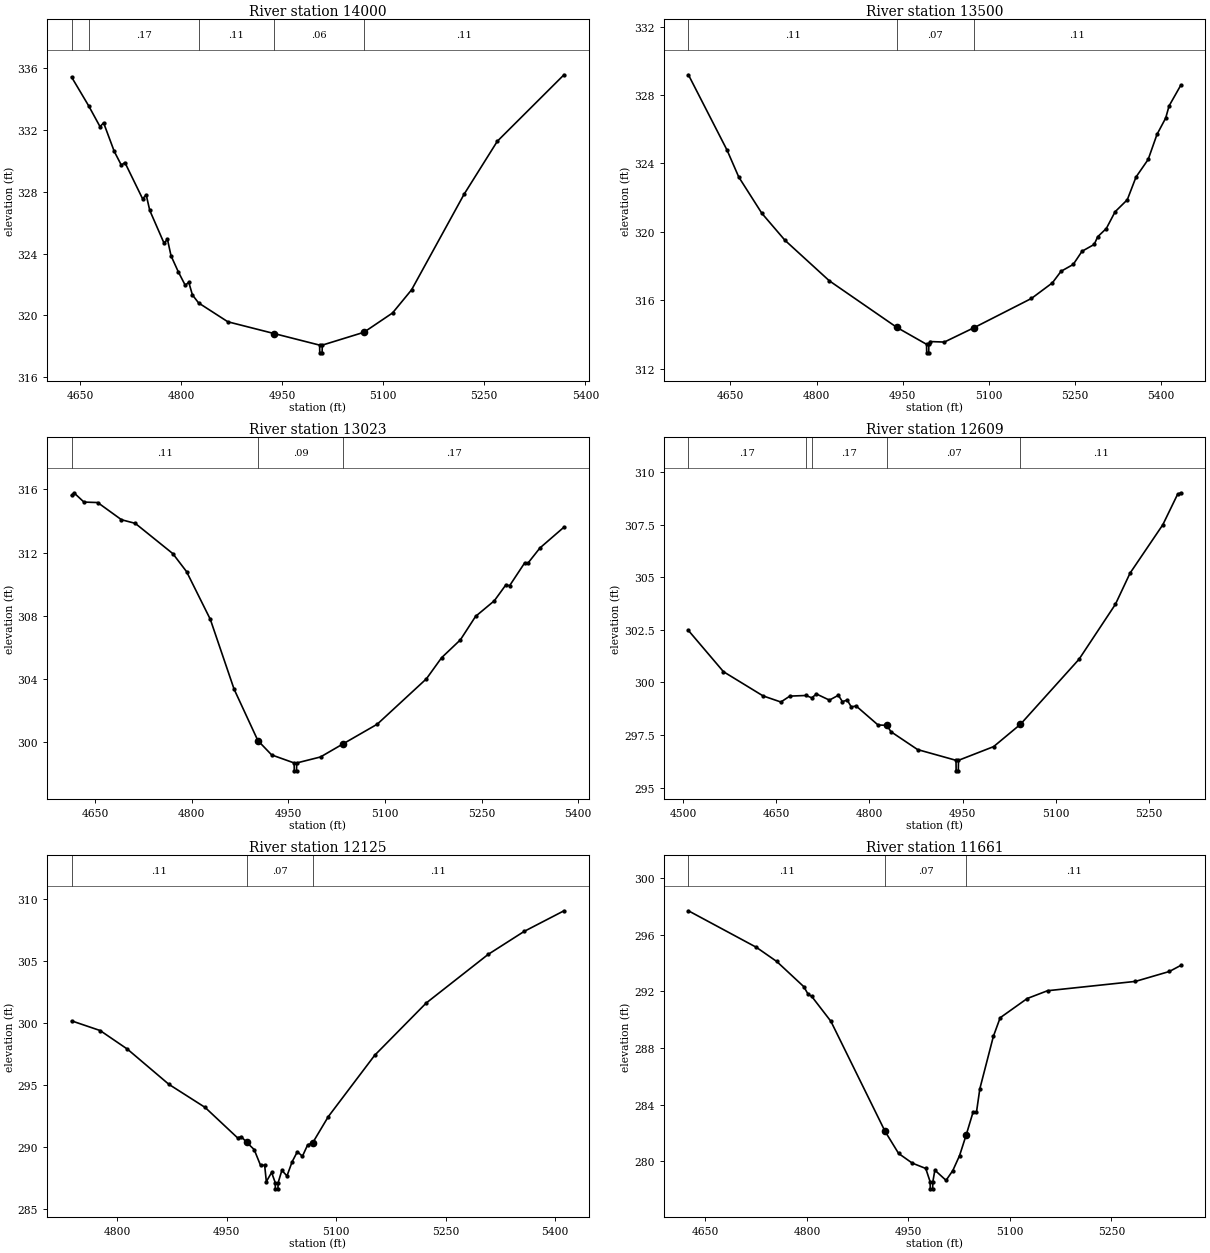
Type RM Length L Ch R = 1 ,14000   ,500,500,500
BEGIN DESCRIPTION:
WEIRS CREEK TRIBUTARY NO 1 25.0
END DESCRIPTION:
XS GIS Cut Line= 3
      3822167.87     10166911.03      3822053.19     10167254.91
      3822317.83     10167511.05
#Sta/Elev= 30
  4637.5  335.43  4662.7  333.58  4679.7  332.22    4685  332.47  4700.8  330.62
  4711.3  329.73  4716.6   329.9  4742.9  327.55  4748.2  327.81  4753.5   326.8
  4774.6  324.69  4779.8  324.92  4785.1  323.86  4795.7  322.84  4806.2  321.95
  4811.4  322.15  4816.8  321.33    4826  320.81  4869.4  319.59  4937.9  318.83
  5005.6  318.08  5005.8  317.58  5009.3  317.58  5009.6  318.08  5071.3  318.91
  5113.8  320.16  5142.1  321.66  5219.8  327.83  5269.4  331.28  5368.3  335.58
#Mann= 5 ,-1 , 0
  4637.5     .11       0  4662.7     .17       0    4826     .11       0
  4937.9     .06       0  5071.3     .11       0
Bank Sta=4937.9,5071.3
XS Rating Curve= 0 ,0
Exp/Cntr=0.3,0.1

Type RM Length L Ch R = 1 ,13500   ,477,477,477
BEGIN DESCRIPTION:
WEIRS CREEK TRIBUTARY NO 1 24.5
END DESCRIPTION:
XS GIS Cut Line= 3
        3821574.     10167084.01      3821623.41     10167504.42
      3821990.09     10167736.95
#Sta/Elev= 30
  4576.7  329.18  4644.2  324.76  4664.4   323.2  4704.6  321.08  4744.9   319.5
  4822.2  317.13 4939.57  314.41  4991.4  313.42  4991.7  312.92  4995.2  312.92
  4995.4  313.42  4997.6  313.58  5022.4  313.55  5074.1  314.39  5174.1   316.1
  5210.5  317.01  5225.7  317.69  5246.9  318.09  5262.2  318.86  5283.4  319.26
  5289.5  319.71  5304.5  320.19  5319.8  321.17    5341  321.87  5356.2   323.2
  5377.4  324.23  5392.7  325.69  5407.9  326.65  5413.8  327.36  5434.2  328.57
#Mann= 3 , 0 , 0
  4576.7     .11       0 4939.57     .07       0  5074.1     .11       0
Bank Sta=4939.57,5074.1
XS Rating Curve= 0 ,0
Exp/Cntr=0.3,0.1

Type RM Length L Ch R = 1 ,13023   ,414,414,414
BEGIN DESCRIPTION:
WEIRS CREEK TRIBUTARY NO 1 24.0
END DESCRIPTION:
XS GIS Cut Line= 3
      3821062.36     10167480.66      3821261.58     10167811.62
      3821609.22      10167959.8
#Sta/Elev= 30
  4613.7  315.62  4617.3  315.79  4632.9   315.2  4654.2  315.17  4691.1  314.08
  4712.5  313.85  4770.8  311.93  4792.1  310.79    4829  307.76  4865.9  303.33
  4902.8  300.07  4924.2  299.16  4959.1  298.65  4959.3  298.15  4962.8  298.15
  4963.1  298.65    5000  299.03  5035.4  299.87  5088.1  301.11  5164.4  303.99
    5188  305.33  5217.1  306.46  5240.7  307.95  5269.8  308.94  5287.9  309.96
  5293.4  309.89    5317  311.35  5322.4  311.35  5340.6  312.29  5377.9  313.61
#Mann= 3 ,-1 , 0
  4613.7     .11       0  4902.8     .09       0  5035.4     .17       0
Bank Sta=4902.8,5035.4
XS Rating Curve= 0 ,0
Exp/Cntr=0.3,0.1

Type RM Length L Ch R = 1 ,12609   ,484,484,484
BEGIN DESCRIPTION:
WEIRS CREEK TRIBUTARY NO 1 23.0
END DESCRIPTION:
XS GIS Cut Line= 3
      3820616.71      10167802.3      3820996.83     10168114.36
      3821114.42     10168392.08
#Sta/Elev= 30
  4508.2  302.47  4564.7  300.51  4628.5  299.36  4657.2  299.07  4671.6  299.35
  4697.6  299.38  4706.9  299.27  4714.6  299.45  4735.4  299.16  4749.8  299.39
  4756.3  299.09  4764.1  299.16  4770.6  298.84  4778.5  298.88  4813.7  297.98
    4828  297.96  4834.5  297.66  4877.5  296.81  4939.4   296.3  4939.6   295.8
  4943.1   295.8  4943.4   296.3    5000  296.95  5043.2  298.01  5137.6   301.1
  5196.2  303.71  5219.8  305.19  5272.6  307.49  5296.3  308.93  5301.6  309.01
#Mann= 5 ,-1 , 0
  4508.2     .17       0  4697.6     .11       0  4706.9     .17       0
    4828     .07       0  5043.2     .11       0
Bank Sta=4828,5043.2
XS Rating Curve= 0 ,0
Exp/Cntr=0.3,0.1

Type RM Length L Ch R = 1 ,12125   ,464,464,464
BEGIN DESCRIPTION:
WEIRS CREEK TRIBUTARY NO 1 22.0
END DESCRIPTION:
XS GIS Cut Line= 3
      3820505.05     10167996.26      3820559.54     10168253.25
      3820853.43     10168542.56
#Sta/Elev= 30
  4737.3   300.2  4776.4  299.42  4813.8  297.92  4870.7  295.08  4920.3  293.22
  4964.9  290.76    4970  290.86  4977.3   290.4  4987.6  289.82  4996.3  288.55
    5002  288.55  5004.3  287.23  5011.5  287.97  5016.5  287.15  5016.7  286.65
  5020.2  286.65  5020.5  287.15  5025.6  288.14  5032.6  287.69  5039.7  288.84
  5046.8  289.64  5053.8  289.28  5060.9  290.19  5067.9  290.37  5089.2  292.47
  5152.8  297.42  5223.5  301.64  5308.4  305.56  5357.9  307.42  5412.4  309.08
#Mann= 3 , 0 , 0
  4737.3     .11       0  4977.3     .07       0  5067.9     .11       0
Bank Sta=4977.3,5067.9
XS Rating Curve= 0 ,0
Exp/Cntr=0.3,0.1

Type RM Length L Ch R = 1 ,11661   ,476,476,476
BEGIN DESCRIPTION:
WEIRS CREEK TRIBUTARY NO 1 21.0
END DESCRIPTION:
XS GIS Cut Line= 3
      3820192.56      10168110.8      3820172.17     10168485.45
       3820176.9     10168838.02
#Sta/Elev= 30
  4624.8  297.69  4725.2  295.11  4755.3  294.11  4795.3  292.33  4801.9  291.78
  4806.9  291.65  4835.4  289.88  4915.5   282.1  4935.5  280.54  4955.6  279.86
  4975.6  279.48  4982.1  278.54  4982.3  278.04  4985.8  278.04  4986.1  278.54
  4989.1  279.36  5005.6  278.64  5015.6  279.33  5025.6  280.39  5035.6  281.88
  5045.6  283.47  5050.6  283.46  5055.6  285.12  5075.6  288.82  5085.6  290.13
  5125.6  291.49  5155.6  292.04  5285.6   292.7  5335.7   293.4  5352.6  293.83
#Mann= 3 , 0 , 0
  4624.8     .11       0  4915.5     .07       0  5035.6     .11       0
Bank Sta=4915.5,5035.6
XS Rating Curve= 0 ,0
Exp/Cntr=0.3,0.1

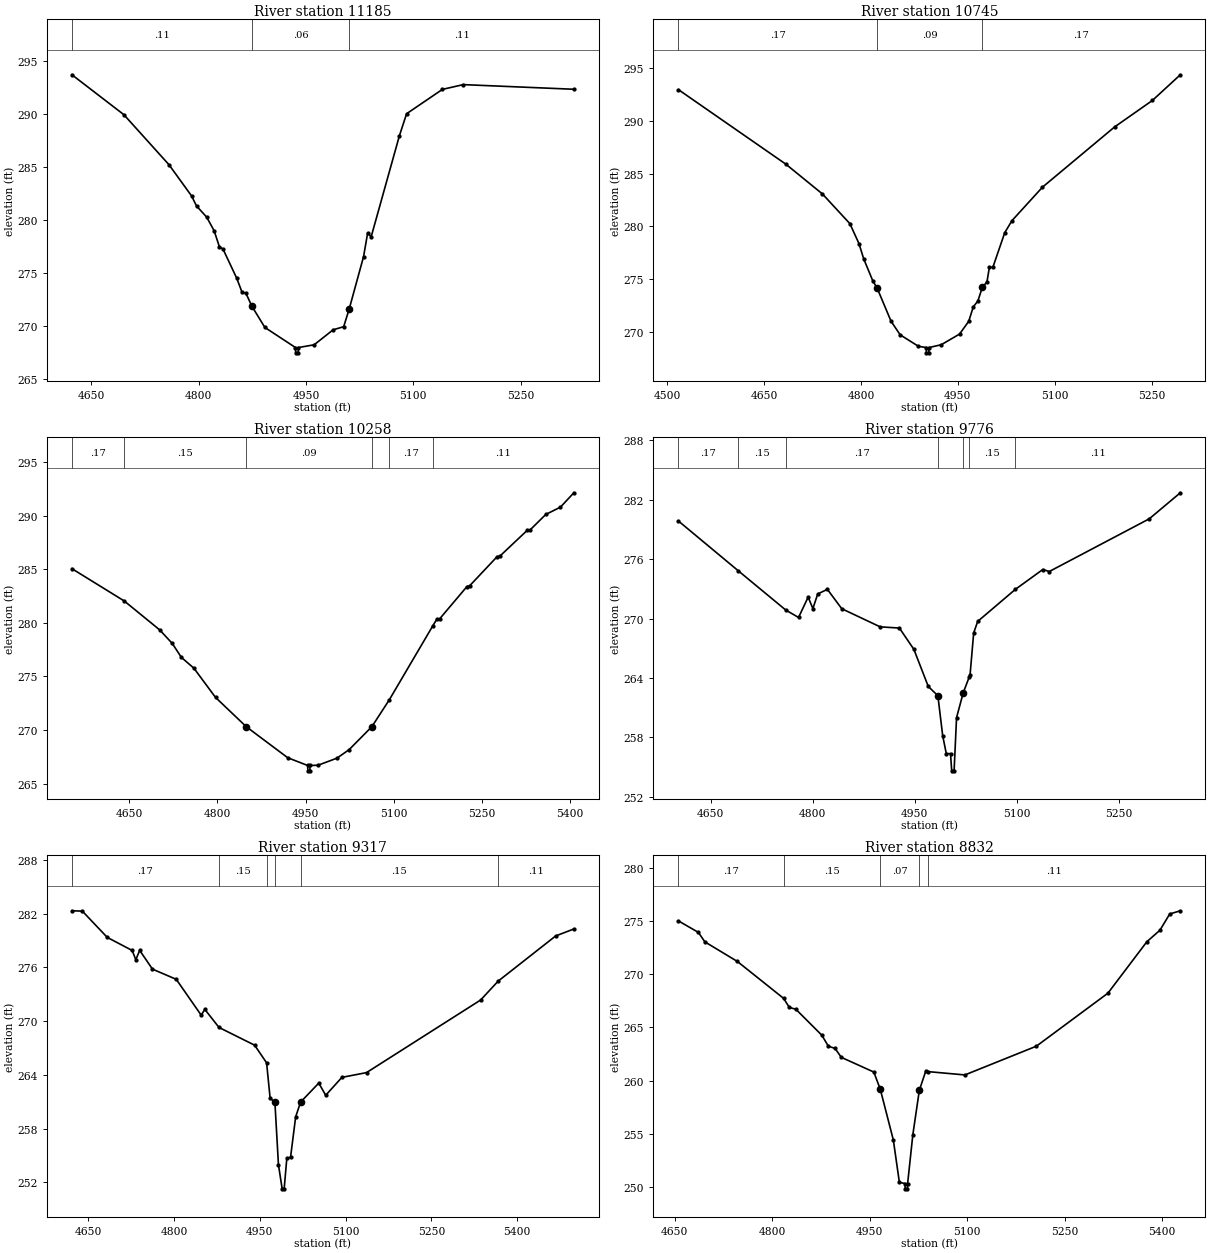
Type RM Length L Ch R = 1 ,11185   ,440,440,440
BEGIN DESCRIPTION:
WEIRS CREEK TRIBUTARY NO 1 20.0
END DESCRIPTION:
XS GIS Cut Line= 3
      3819817.56     10168142.07      3819700.17     10168500.64
       3819723.8     10168824.38
#Sta/Elev= 30
  4622.7  293.72  4695.3  289.95  4758.4  285.22    4790  282.27  4796.9  281.32
  4811.1  280.27  4821.6  278.97  4828.8  277.48    4834  277.24  4853.1   274.5
  4860.6  273.16  4865.9  273.09  4874.2  271.86  4892.5  269.84  4935.3  267.94
  4935.6  267.44  4939.1  267.44  4939.3  267.94  4961.4   268.2    4988  269.62
  5002.7  269.91  5010.5   271.6  5030.5  276.53  5036.2  278.76  5041.2  278.42
  5080.6  287.95  5090.7  290.04  5140.8  292.34    5170  292.79  5324.6  292.35
#Mann= 3 , 0 , 0
  4622.7     .11       0  4874.2     .06       0  5010.5     .11       0
Bank Sta=4874.2,5010.5
XS Rating Curve= 0 ,0
Exp/Cntr=0.3,0.1

Type RM Length L Ch R = 1 ,10745   ,487,487,487
BEGIN DESCRIPTION:
WEIRS CREEK TRIBUTARY NO 1 19.0
END DESCRIPTION:
XS GIS Cut Line= 3
      3819635.27     10168043.13      3819297.61     10168387.79
      3819244.86     10168677.33
#Sta/Elev= 30
  4517.5  292.98  4683.9   285.9  4740.4  283.08  4782.9  280.26    4797  278.36
  4804.2  276.93  4818.3  274.84  4825.3  274.11  4846.6     271  4860.7  269.71
    4889  268.62  4901.2   268.5  4901.4     268  4904.9     268  4905.2   268.5
  4924.3  268.77  4952.6  269.78  4966.8  270.99  4973.9  272.37  4980.9  272.91
    4988  274.24    4995  274.72  4998.8  276.12  5004.2  276.12  5022.6  279.41
  5033.8  280.55  5080.9  283.72  5192.6  289.44    5251  291.95  5294.3  294.39
#Mann= 3 , 0 , 0
  4517.5     .17       0  4825.3     .09       0    4988     .17       0
Bank Sta=4825.3,4988
XS Rating Curve= 0 ,0
Exp/Cntr=0.3,0.1

Type RM Length L Ch R = 1 ,10258   ,482,482,482
BEGIN DESCRIPTION:
WEIRS CREEK TRIBUTARY NO 1 18.0
END DESCRIPTION:
XS GIS Cut Line= 3
       3819140.5      10167798.3      3818906.98     10168179.46
      3818828.31     10168577.87
#Sta/Elev= 30
    4553  285.05  4641.9  282.04  4702.2  279.34  4723.5  278.08    4739  276.78
  4760.3  275.77    4797  273.05  4849.2  270.32  4919.8  267.42  4953.7   266.7
  4953.9   266.2  4957.4   266.2  4957.7   266.7  4971.1  266.72  5003.4  267.38
  5024.2  268.18  5062.8  270.32  5092.6  272.84    5166  279.69    5173  280.32
  5178.1  280.38  5224.3  283.38  5229.4  283.48  5275.6  286.17  5280.7  286.24
  5326.9  288.63    5332  288.68  5358.4  290.11  5383.3  290.79  5406.1  292.13
#Mann= 6 ,-1 , 0
    4553     .17       0  4641.9     .15       0  4849.2     .09       0
  5062.8     .15       0  5092.6     .17       0    5166     .11       0
Bank Sta=4849.2,5062.8
XS Rating Curve= 0 ,0
Exp/Cntr=0.3,0.1

Type RM Length L Ch R = 1 ,9776    ,459,459,459
BEGIN DESCRIPTION:
WEIRS CREEK TRIBUTARY NO 1 17.0
END DESCRIPTION:
XS GIS Cut Line= 3
      3818817.84     10167661.09      3818535.33     10167941.01
      3818417.87     10168261.03
#Sta/Elev= 30
  4602.3  279.85  4690.6  274.81  4760.4  270.85  4779.1  270.11  4793.2  272.16
  4800.2  271.01  4807.3  272.48  4821.5  272.95  4842.7  270.99  4899.2  269.16
  4927.5  269.04  4948.8  266.89    4970  263.14  4984.1  262.21  4991.2  258.17
  4996.5  256.36  5002.7  256.36  5004.5  254.62    5008  254.62  5011.6  259.99
  5021.4   262.5  5030.5  264.14  5031.5  264.32  5036.8  268.54  5042.7  269.71
  5098.2  272.95  5138.5  274.95  5148.1  274.75  5295.2  280.07  5340.9   282.7
#Mann= 7 ,-1 , 0
  4602.3     .17       0  4690.6     .15       0  4760.4     .17       0
  4984.1     .09       0  5021.4     .15       0  5030.5     .15       0
  5098.2     .11       0
Bank Sta=4984.1,5021.4
XS Rating Curve= 0 ,0
Exp/Cntr=0.3,0.1

Type RM Length L Ch R = 1 ,9317    ,485,485,485
BEGIN DESCRIPTION:
WEIRS CREEK TRIBUTARY NO 1 16.0
END DESCRIPTION:
XS GIS Cut Line= 3
      3818551.91     10167428.57      3818251.48     10167658.46
      3818182.14     10168152.51
#Sta/Elev= 30
  4621.7  282.31  4639.9  282.27  4683.4  279.34    4727  277.88  4733.3  276.85
  4740.1  277.89  4762.4   275.8    4804  274.66  4847.6  270.66  4853.9  271.31
  4878.7  269.29    4941  267.31  4961.9  265.34  4968.1  261.37  4976.4  260.96
  4982.6  253.98  4989.1  251.28  4992.6  251.28  4997.2  254.67  5003.8  254.82
  5012.7  259.32  5021.3  260.96  5053.1  263.08  5065.2  261.72  5093.5  263.72
  5136.5  264.25  5335.9  272.35  5366.8  274.47  5467.1   279.5  5498.9  280.28
#Mann= 6 ,-1 , 0
  4621.7     .17       0  4878.7     .15       0  4961.9     .17       0
  4976.4     .09       0  5021.3     .15       0  5366.8     .11       0
Bank Sta=4976.4,5021.3
XS Rating Curve= 0 ,0
Exp/Cntr=0.3,0.1

Type RM Length L Ch R = 1 ,8832    ,832,832,832
BEGIN DESCRIPTION:
WEIRS CREEK TRIBUTARY NO 1 15.0
END DESCRIPTION:
XS GIS Cut Line= 3
      3817877.39     10167330.43      3817885.35     10167674.64
      3817872.36     10168102.44
#Sta/Elev= 30
  4655.7     275  4686.4  273.92  4696.4  273.03  4746.4  271.19  4817.6  267.72
  4826.4  266.87  4836.4   266.7  4876.4  264.26  4886.4  263.23  4896.7  263.02
  4906.4  262.18  4956.4   260.8  4966.4  259.17  4986.4  254.42  4995.7  250.44
  5004.4  250.33  5004.7  249.83  5008.2  249.83  5008.4  250.33  5016.4  254.91
  5026.4  259.08  5036.5  260.93  5040.1  260.84  5096.5  260.53  5206.5  263.23
  5316.6  268.21  5376.6  273.05  5396.6  274.12  5411.7  275.65    5428  275.95
#Mann= 5 ,-1 , 0
  4655.7     .17       0  4817.6     .15       0  4966.4     .07       0
  5026.4     .11       0  5040.1     .11       0
Bank Sta=4966.4,5026.4
XS Rating Curve= 0 ,0
Exp/Cntr=0.3,0.1

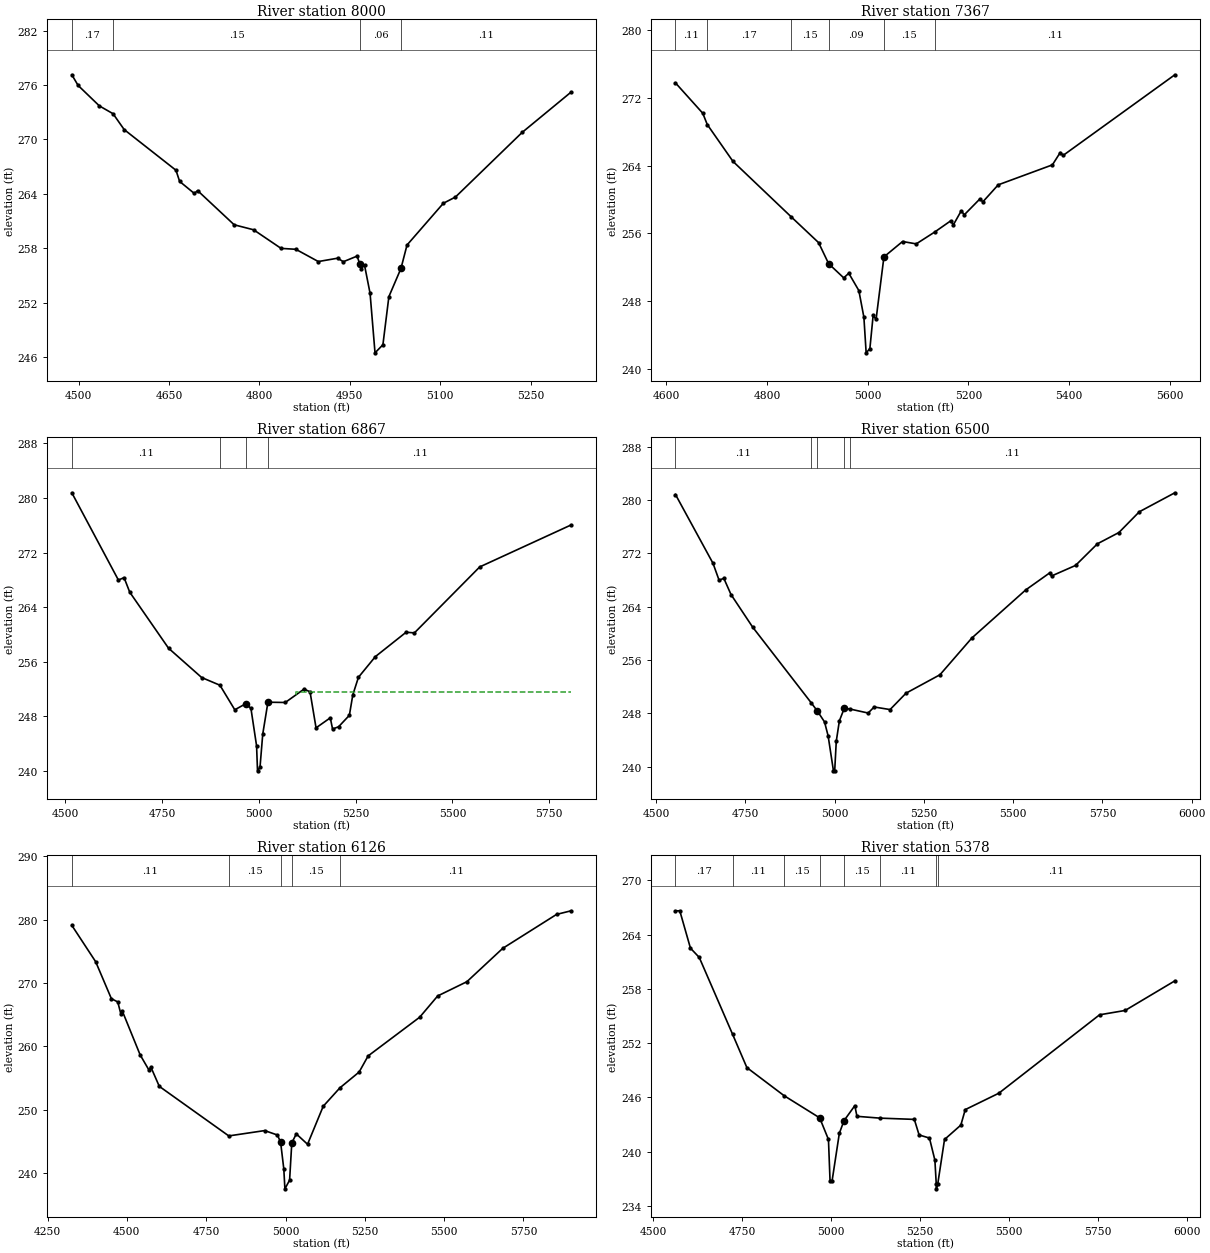
Type RM Length L Ch R = 1 ,8000    ,633,633,633
BEGIN DESCRIPTION:
WEIRS CREEK TRIBUTARY NO 1 14.0
END DESCRIPTION:
XS GIS Cut Line= 3
      3817578.15     10167280.09      3817392.17     10167756.37
      3817361.88     10168072.22
#Sta/Elev= 30
  4488.7  277.13  4499.2  275.95  4534.4   273.7  4557.1  272.84  4575.6  271.09
  4661.5  266.61  4667.6  265.38    4692  264.05  4697.4  264.37  4758.1   260.6
  4790.3  260.05  4835.9     258  4860.4   257.9  4897.7  256.55  4929.9  256.92
  4939.2  256.53  4962.1  257.15  4966.7  256.24  4969.1  255.76  4974.4  256.15
  4983.6  253.05  4991.8  246.49  5004.9  247.38  5014.8  252.68  5034.9   255.8
  5044.9  258.37  5105.2  262.97  5125.3  263.66  5235.8  270.77  5317.3  275.23
#Mann= 4 ,-1 , 0
  4488.7     .17       0  4557.1     .15       0  4966.7     .06       0
  5034.9     .11       0
#XS Ineff= 2 , 0
       0  4962.1  257.15               0
Permanent Ineff=
       F       F
Bank Sta=4966.7,5034.9
XS Rating Curve= 0 ,0
Exp/Cntr=0.3,0.1

Type RM Length L Ch R = 1 ,7367    ,500,500,500
BEGIN DESCRIPTION:
WEIRS CREEK TRIBUTARY NO 1 12.0
END DESCRIPTION:
XS GIS Cut Line= 3
      3817012.33     10167156.87      3817006.18     10167538.53
      3817319.15     10168062.24
#Sta/Elev= 30
  4618.3  273.79  4672.5   270.2  4681.4  268.87  4732.5  264.51  4847.9  257.97
  4902.5  254.91  4922.5  252.42  4952.5  250.74  4962.5  251.29  4982.5  249.24
  4992.5  246.09    4997  241.88  5004.4  242.38  5010.9  246.31  5016.7  245.83
  5032.3  253.22  5069.3  255.04  5096.5  254.76  5132.9  256.15  5164.6  257.47
  5170.4  257.03    5186  258.68  5191.8  258.19    5223  260.08  5228.8  259.73
  5259.3  261.74  5366.9   264.1  5382.5  265.56  5388.3  265.22  5610.1  274.75
#Mann= 6 ,-1 , 0
  4618.3     .11       0  4681.4     .17       0  4847.9     .15       0
  4922.5     .09       0  5032.3     .15       0  5132.9     .11       0
Bank Sta=4922.5,5032.3
XS Rating Curve= 0 ,0
Exp/Cntr=0.3,0.1

Type RM Length L Ch R = 1 ,6867    ,367,367,367
BEGIN DESCRIPTION:
WEIRS CREEK TRIBUTARY NO 1 11.0
END DESCRIPTION:
XS GIS Cut Line= 3
      3816320.77      10167280.1      3816607.74     10167668.73
      3817297.95     10168086.71
#Sta/Elev= 30
  4516.9  280.77  4637.2  267.98  4651.9  268.33  4666.5   266.2  4766.7  257.99
  4852.3  253.69  4899.5  252.56  4937.9  248.96  4966.3  249.85  4979.6  249.17
  4994.2  243.67  4996.6  240.01    5003  240.51  5010.1  245.39  5023.5  250.07
  5068.3  250.03    5117     252  5132.3  251.59  5147.8  246.31  5184.6  247.78
  5190.5  246.14    5206  246.47  5233.9  248.15  5242.8  251.15  5257.3  253.72
    5301  256.75  5380.5  260.33  5401.9  260.23  5570.6   269.9  5806.9  276.06
#Mann= 4 ,-1 , 0
  4516.9     .11       0  4899.5     .15       0  4966.3     .06       0
  5023.5     .11       0
#XS Ineff= 2 , 0
       0                  5095.4       0   251.5
Permanent Ineff=
       F       T
Bank Sta=4966.3,5023.5
XS Rating Curve= 0 ,0
Exp/Cntr=0.3,0.1

Type RM Length L Ch R = 1 ,6500    ,374,374,374
BEGIN DESCRIPTION:
WEIRS CREEK TRIBUTARY NO 1 11.5
END DESCRIPTION:
XS GIS Cut Line= 3
      3816217.69     10167306.71      3816272.27     10167749.26
      3816699.47     10168601.03
#Sta/Elev= 30
  4554.1  280.84  4659.2  270.52  4676.2  267.99  4689.5  268.27  4709.6  265.84
  4770.1  260.96  4934.1  249.61  4951.4  248.37  4971.6  246.73  4981.7  244.63
  4996.6  239.39  5000.1  239.39  5004.5  243.83  5013.2  246.89  5026.8  248.75
    5043  248.66  5093.8  248.06  5110.6  248.97  5155.2  248.58  5199.9  251.04
  5294.9   253.8  5384.2  259.31    5535  266.52    5602  269.07  5607.6  268.62
  5674.7   270.2  5736.1  273.45  5796.3  275.14  5853.4  278.25  5952.9   281.1
#Mann= 5 ,-1 , 0
  4554.1     .11       0  4934.1     .15       0  4951.4     .09       0
  5026.8     .15       0    5043     .11       0
Bank Sta=4951.4,5026.8
XS Rating Curve= 0 ,0
Exp/Cntr=0.3,0.1

Type RM Length L Ch R = 1 ,6126    ,748,748,748
BEGIN DESCRIPTION:
WEIRS CREEK TRIBUTARY NO 1 9.0
END DESCRIPTION:
XS GIS Cut Line= 3
      3816110.92     10167317.19      3816034.41     10167986.33
      3816683.76     10168610.09
#Sta/Elev= 30
  4326.5   279.1  4401.7  273.36  4451.2  267.53  4471.3  267.02    4481  265.13
    4486  265.54  4541.8  258.67  4570.3  256.21  4575.3  256.78  4602.2   253.7
  4821.2  245.88  4934.3  246.72  4974.6  246.02  4984.6  244.87  4994.7  240.65
  4998.1  237.53  5012.9   238.9  5019.8  244.78    5034   246.2  5069.5  244.56
  5118.9  250.56  5171.4  253.46  5232.1  255.96  5260.4   258.5    5423  264.61
  5479.6  267.96  5571.7  270.21  5684.6  275.47  5854.4  280.83  5900.4   281.4
#Mann= 5 ,-1 , 0
  4326.5     .11       0  4821.2     .15       0  4984.6     .09       0
  5019.8     .15       0  5171.4     .11       0
Bank Sta=4984.6,5019.8
XS Rating Curve= 0 ,0
Exp/Cntr=0.3,0.1

Type RM Length L Ch R = 1 ,5378    ,394,394,394
BEGIN DESCRIPTION:
WEIRS CREEK TRIBUTARY NO 1 8.0
END DESCRIPTION:
XS GIS Cut Line= 3
      3815936.46     10167412.92      3815779.62     10167821.34
      3815265.93     10168640.38
#Sta/Elev= 30
  4562.5  266.61  4574.6  266.62  4604.6  262.49  4629.3  261.47  4723.2  252.97
  4763.3   249.3  4867.9   246.2    4968  243.75  4992.7  241.36  4997.2  236.76
  5002.8  236.76  5023.3  242.04  5036.3  243.43  5066.9   245.1  5072.8  243.92
    5137  243.72  5234.2  243.58  5247.6  241.86  5276.7  241.52    5292  239.08
  5295.9  236.41  5296.1  235.91  5299.9  236.41  5319.1  241.36    5365  242.95
  5377.4  244.66  5471.8  246.47  5755.1  255.13    5827  255.61  5966.8  258.88
#Mann= 8 ,-1 , 0
  4562.5     .17       0  4723.2     .11       0  4867.9     .15       0
    4968     .09       0  5036.3     .15       0    5137     .11       0
  5295.9     .12       0  5299.9     .11       0
#XS Ineff= 2 , 0
       0                  5066.9       0   245.1
Permanent Ineff=
       F       T
Bank Sta=4968,5036.3
XS Rating Curve= 0 ,0
Exp/Cntr=0.3,0.1

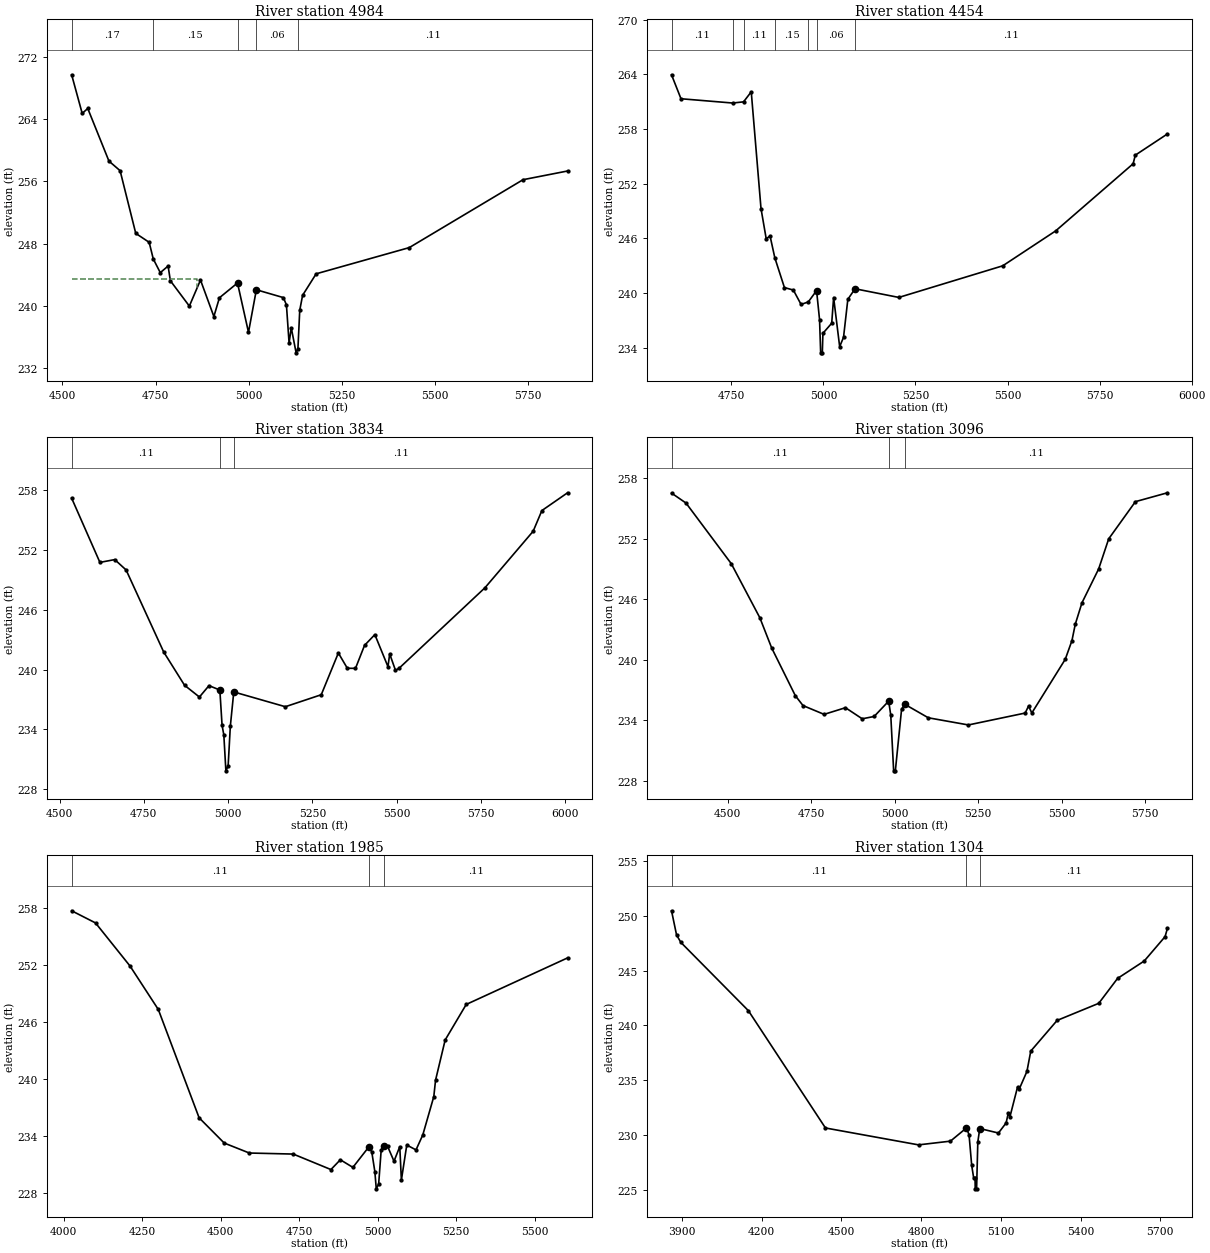
Type RM Length L Ch R = 1 ,4984    ,530,530,530
BEGIN DESCRIPTION:
WEIRS CREEK TRIBUTARY NO 1 7.0
END DESCRIPTION:
XS GIS Cut Line= 4
      3815778.84     10167332.85      3815511.95     10167726.14
      3815328.85     10168010.59      3815126.02     10168486.16
#Sta/Elev= 30
  4524.7  269.71    4553  264.74  4567.9  265.38  4624.8  258.61  4654.7  257.38
  4696.7  249.32  4732.7  248.17  4743.7  246.03  4762.5  244.27  4783.5  245.12
  4789.6  243.23  4840.5  239.97  4870.4  243.32  4906.3  238.63  4921.2  241.04
  4969.7  242.94  4999.2   236.6  5020.3  242.07  5092.9  241.06    5101  240.12
  5108.1  235.23    5114  237.17    5127  233.96  5131.8  234.46  5136.7  239.43
  5144.4  241.36  5180.7  244.12  5430.6  247.49  5735.8  256.22  5855.3  257.34
#Mann= 5 ,-1 , 0
  4524.7     .17       0  4743.7     .15       0  4969.7     .09       0
  5020.3     .06       0  5131.8     .11       0
#XS Ineff= 2 , 0
       0  4861.4   243.4               0
Permanent Ineff=
       F       F
Bank Sta=4969.7,5020.3
XS Rating Curve= 0 ,0
Exp/Cntr=0.3,0.1

Type RM Length L Ch R = 1 ,4454    ,620,620,620
BEGIN DESCRIPTION:
WEIRS CREEK TRIBUTARY NO 1 6.0
END DESCRIPTION:
XS GIS Cut Line= 3
      3815399.28     10167066.86      3815270.47     10167458.73
      3815006.38     10168354.83
#Sta/Elev= 30
  4587.5  263.94  4613.2  261.31  4753.5  260.84  4783.1  260.97    4804  262.07
  4830.5  249.26  4844.6  245.95  4855.1  246.25    4868  243.86  4894.1  240.59
  4918.3  240.32  4939.3  238.74    4959  239.02  4981.4  240.26  4989.5  237.07
  4992.5  233.43    4997  233.43  4998.6  235.57  5022.5  236.68  5027.7   239.5
  5044.1  234.11  5054.6  235.13  5066.3   239.3  5085.8  240.46  5204.8  239.51
    5487  242.98  5630.7  246.81  5841.1  254.18  5846.9  255.12  5934.2  257.45
#Mann= 7 ,-1 , 0
  4587.5     .11       0  4753.5     .17       0  4783.1     .11       0
    4868     .15       0    4959     .11       0  4981.4     .06       0
  5085.8     .11       0
Bank Sta=4981.4,5085.8
XS Rating Curve= 0 ,0
Exp/Cntr=0.3,0.1

Type RM Length L Ch R = 1 ,3834    ,738,738,738
BEGIN DESCRIPTION:
WEIRS CREEK TRIBUTARY NO 1 5.0
END DESCRIPTION:
XS GIS Cut Line= 3
      3814897.12     10166928.94      3814768.23     10167374.68
      3814967.85     10168361.08
#Sta/Elev= 30
    4536  257.16  4619.8  250.73  4663.8  251.01  4697.5  249.97  4808.9  241.76
  4870.7  238.43  4914.8  237.25  4943.2  238.39  4975.4  237.95    4982  234.42
  4987.2  233.46  4993.3  229.86    5000  230.36  5006.5  234.33  5016.7  237.76
  5169.6  236.28  5276.1  237.48  5326.8  241.66  5353.4  240.13  5377.6  240.12
  5404.4  242.42    5435   243.5  5473.9  240.29    5479  241.57  5496.2  239.92
  5506.5  240.12  5761.5  248.19  5904.4  253.85  5930.3  255.92  6006.4   257.7
#Mann= 3 , 0 , 0
    4536     .11       0  4975.4     .06       0  5016.7     .11       0
Bank Sta=4975.4,5016.7
XS Rating Curve= 0 ,0
Exp/Cntr=0.3,0.1

Type RM Length L Ch R = 1 ,3096    ,1111,1111,1111
BEGIN DESCRIPTION:
WEIRS CREEK TRIBUTARY NO 1 4.0
END DESCRIPTION:
XS GIS Cut Line= 3
      3814753.99     10166887.36      3814218.34       10167287.
      3813401.95     10167290.64
#Sta/Elev= 30
  4331.7  256.54  4375.1  255.55  4510.6  249.54  4596.1  244.18  4631.6  241.18
  4702.4  236.45  4725.4  235.47  4788.5   234.6  4852.5  235.26  4902.6  234.16
  4938.2  234.39  4981.8  235.91  4988.1  234.52  4996.7     229  5001.8     229
  5020.5  235.12  5030.5  235.59  5100.5  234.26  5220.5  233.55  5390.5  234.73
  5400.5  235.42  5410.5  234.74  5510.5  240.06  5530.5  241.91  5540.5  243.54
  5560.5  245.66  5610.5  249.02  5640.5     252  5720.5  255.69  5816.4  256.57
#Mann= 3 , 0 , 0
  4331.7     .11       0  4981.8     .06       0  5030.5     .11       0
Bank Sta=4981.8,5030.5
XS Rating Curve= 0 ,0
Exp/Cntr=0.3,0.1

Type RM Length L Ch R = 1 ,1985    ,681,681,681
BEGIN DESCRIPTION:
WEIRS CREEK TRIBUTARY NO 1 3.0
END DESCRIPTION:
XS GIS Cut Line= 3
      3814753.97     10166837.91      3813778.78     10166842.03
      3813185.02     10166957.61
#Sta/Elev= 30
  4024.8  257.68  4100.9   256.4  4210.9  251.86  4300.9  247.29  4430.9  235.89
  4510.9  233.23  4590.9  232.18  4730.9  232.07  4850.9  230.44  4880.9  231.47
  4920.9  230.67  4970.9  232.79  4980.9  232.33  4990.9  230.22  4995.4  228.41
    5003  228.91  5011.1  232.52  5018.7  232.92  5031.5  232.88  5051.9  231.32
  5070.3  232.85  5075.4  229.33  5092.6  233.02    5122  232.51  5143.6  234.08
  5178.7  238.12  5184.3  239.85  5214.9  244.08    5282  247.82  5604.9  252.72
#Mann= 3 , 0 , 0
  4024.8     .11       0  4970.9     .06       0  5018.7     .11       0
Bank Sta=4970.9,5018.7
XS Rating Curve= 0 ,0
Exp/Cntr=0.3,0.1

Type RM Length L Ch R = 1 ,1304    ,878,878,878
BEGIN DESCRIPTION:
WEIRS CREEK TRIBUTARY NO 1 2.0
END DESCRIPTION:
XS GIS Cut Line= 3
      3814826.87     10166304.52      3813688.19      10166352.6
      3813121.46     10166808.12
#Sta/Elev= 30
  3860.3  250.45  3879.3  248.24  3895.7  247.56  4149.6  241.34  4439.8  230.64
  4790.1   229.1  4910.3  229.44  4970.3  230.64  4980.3  230.02  4990.3  227.22
  4997.7  226.08  5002.8  226.08  5003.6  225.09  5008.7  225.09  5013.3  229.36
  5020.6  230.59    5091  230.18  5119.8   231.1  5127.8  231.97  5134.2  231.66
    5163  234.39  5169.4   234.2  5198.2   235.8  5212.6  237.65  5311.8  240.45
  5468.6  242.01  5539.3  244.28  5639.8  245.87  5718.2  248.09  5727.1  248.85
#Mann= 3 , 0 , 0
  3860.3     .11       0  4970.3     .06       0  5020.6     .11       0
#XS Ineff= 2 , 0
       0                  5127.8       0  231.97
Permanent Ineff=
       F       F
Bank Sta=4970.3,5020.6
XS Rating Curve= 0 ,0
Exp/Cntr=0.3,0.1

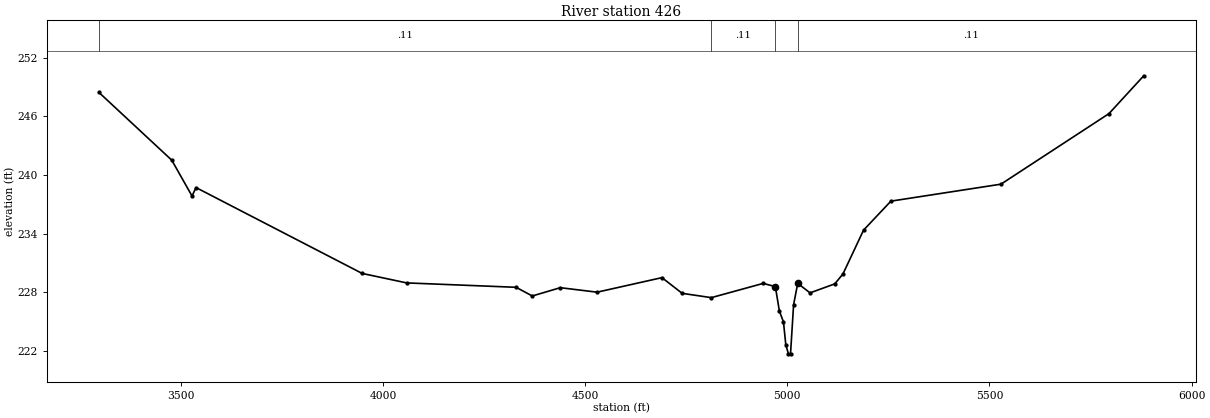
Type RM Length L Ch R = 1 ,426     ,0,0,0
BEGIN DESCRIPTION:
WEIRS CREEK TRIBUTARY NO 1 1.0
END DESCRIPTION:
XS GIS Cut Line= 4
      3814907.55     10166044.33      3813211.14     10165943.01
      3813210.65     10165945.73      3813047.14     10166811.94
#Sta/Elev= 30
  3297.8  248.46  3477.8  241.52  3527.9  237.85  3537.9  238.71  3948.7  229.91
  4058.8  228.94  4329.3  228.49  4369.4   227.6  4438.6  228.45  4529.7  227.99
    4690  229.48  4740.1  227.87  4812.2  227.43  4940.4  228.89  4970.5  228.56
  4980.5  226.04  4990.5  224.95  4996.4  222.58  5002.8  221.67    5008  221.67
  5015.6  226.71  5025.8  228.89  5056.3  227.92  5117.4  228.84  5137.7  229.86
  5188.6  234.35  5256.2  237.32  5528.4  239.06  5795.5  246.29  5881.5  250.17
#Mann= 4 ,-1 , 0
  3297.8     .11       0  4812.2     .11       0  4970.5     .06       0
  5025.8     .11       0
Bank Sta=4970.5,5025.8
XS Rating Curve= 0 ,0
Exp/Cntr=0.3,0.1

Chan Stop Cuts=-1
Use User Specified Reach Order=0
Composite Channel Slope=5