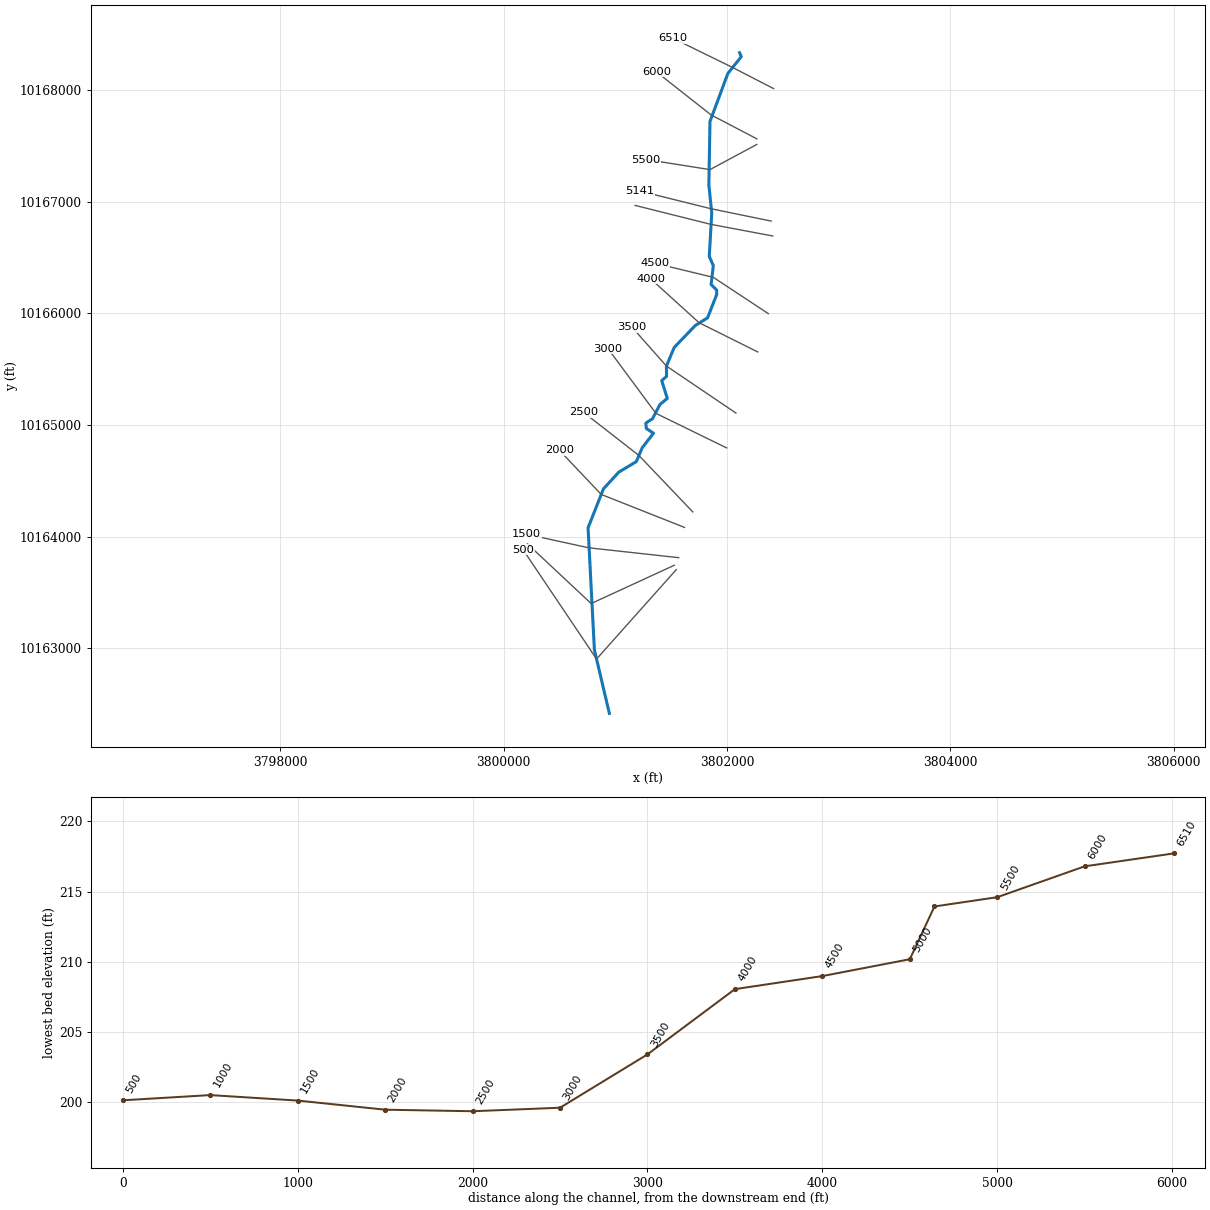
--- WEIRS CREEK TRIBUTARY NO 2.prj (project) ---

Proj Title=WEIRS CREEK TRIBUTARY NO 2 Base Level Engineering
Current Plan=p01
Default Exp/Contr=0.3,0.1
English Units
Geom File=g01
Flow File=f01
Plan File=p01
Y Axis Title=Elevation
X Axis Title(PF)=Main Channel Distance
X Axis Title(XS)=Station
BEGIN DESCRIPTION:
WEIRS CREEK TRIBUTARY NO 2
END DESCRIPTION:
DSS Export Rating Curves= 0
DSS Export Rating Curve Sorted= 0
DSS Export Volume Flow Curves= 0
DXF OffsetX= 0
DXF OffsetY= 0
DXF ScaleX= 1
DXF ScaleY= 10

--- WEIRS CREEK TRIBUTARY NO 2.p01 (plan) ---

Plan Title=Multiple Run
Short Identifier=Multiple
Geom File=g01
Flow File=f01
Subcritical Flow
K Sum by GR= 0
Std Step Tol= 0.01
Critical Tol= 0.01
Num of Std Step Trials= 20
Max Error Tol= 0.3
Flow Tol Ratio= 0.001
Split Flow NTrial= 30
Split Flow Tol= 0.02
Split Flow Ratio= 0.02
Log Output Level= 0
Friction Slope Method= 1
Unsteady Friction Slope Method= 2
Unsteady Bridges Friction Slope Method= 1
Parabolic Critical Depth
Global Vel Dist=  1 , 1 , 1
Global Log Level= 0
CheckData=True
Encroach Param= -1, 0, 0, 0
BEGIN DESCRIPTION:
Multiple Run
END DESCRIPTION:

--- WEIRS CREEK TRIBUTARY NO 2.f01 (steady flow) ---

Flow Title=Multiple
Program Version=4.10
Number of Profiles= 7
Profile Names=10-year,25-year,50-year,1pct_min,100-year,1pct_plu,500-year
River Rch & RM=WEIRS CREEK TRIB,Reach-1         ,6510
     530     712     957     425    1282    3872    2375
River Rch & RM=WEIRS CREEK TRIB,Reach-1         ,5500
     784    1074    1464     657    1983    5989    3756
River Rch & RM=WEIRS CREEK TRIB,Reach-1         ,2500
     743    1009    1365     607    1834    5539    3423
Boundary for River Rch & Prof#=WEIRS CREEK TRIB,Reach-1         , 1
Up Type= 0
Dn Type= 3
Dn Slope=0.005
Boundary for River Rch & Prof#=WEIRS CREEK TRIB,Reach-1         , 2
Up Type= 0
Dn Type= 3
Dn Slope=0.005
Boundary for River Rch & Prof#=WEIRS CREEK TRIB,Reach-1         , 3
Up Type= 0
Dn Type= 3
Dn Slope=0.005
Boundary for River Rch & Prof#=WEIRS CREEK TRIB,Reach-1         , 4
Up Type= 0
Dn Type= 3
Dn Slope=0.005
Boundary for River Rch & Prof#=WEIRS CREEK TRIB,Reach-1         , 5
Up Type= 0
Dn Type= 3
Dn Slope=0.005
Boundary for River Rch & Prof#=WEIRS CREEK TRIB,Reach-1         , 6
Up Type= 0
Dn Type= 3
Dn Slope=0.005
Boundary for River Rch & Prof#=WEIRS CREEK TRIB,Reach-1         , 7
Up Type= 0
Dn Type= 3
Dn Slope=0.005
DSS Import GetInterval= 0
DSS Import GetPeak= 0
DSS Import FillOption= 0

--- WEIRS CREEK TRIBUTARY NO 2.g01 (geometry) ---

Geom Title=Existing Conditions
Program Version=4.10

River Reach=WEIRS CREEK TRIB,Reach-1
Reach XY= 30
      3802113.23     10168331.84      3802128.23     10168296.84
      3802008.23     10168146.84      3801848.23     10167716.84
      3801838.23     10167146.84      3801864.02     10166897.58
      3801841.76     10166507.57      3801878.23     10166426.84
      3801858.23     10166256.84      3801908.23     10166206.84
      3801908.23     10166166.84      3801826.27     10165958.53
      3801717.16     10165890.15      3801528.02     10165693.81
      3801457.91     10165525.93      3801459.49      10165433.7
      3801416.16     10165396.71      3801465.98     10165237.07
      3801400.26     10165182.68      3801333.48     10165055.29
      3801273.87     10165016.07      3801278.59     10164967.03
      3801342.22     10164925.55       3801240.3     10164793.28
      3801188.61     10164670.87      3801031.78     10164576.92
      3800894.24     10164427.46      3800756.61     10164078.48
      3800813.29     10162985.52      3800947.37     10162416.96

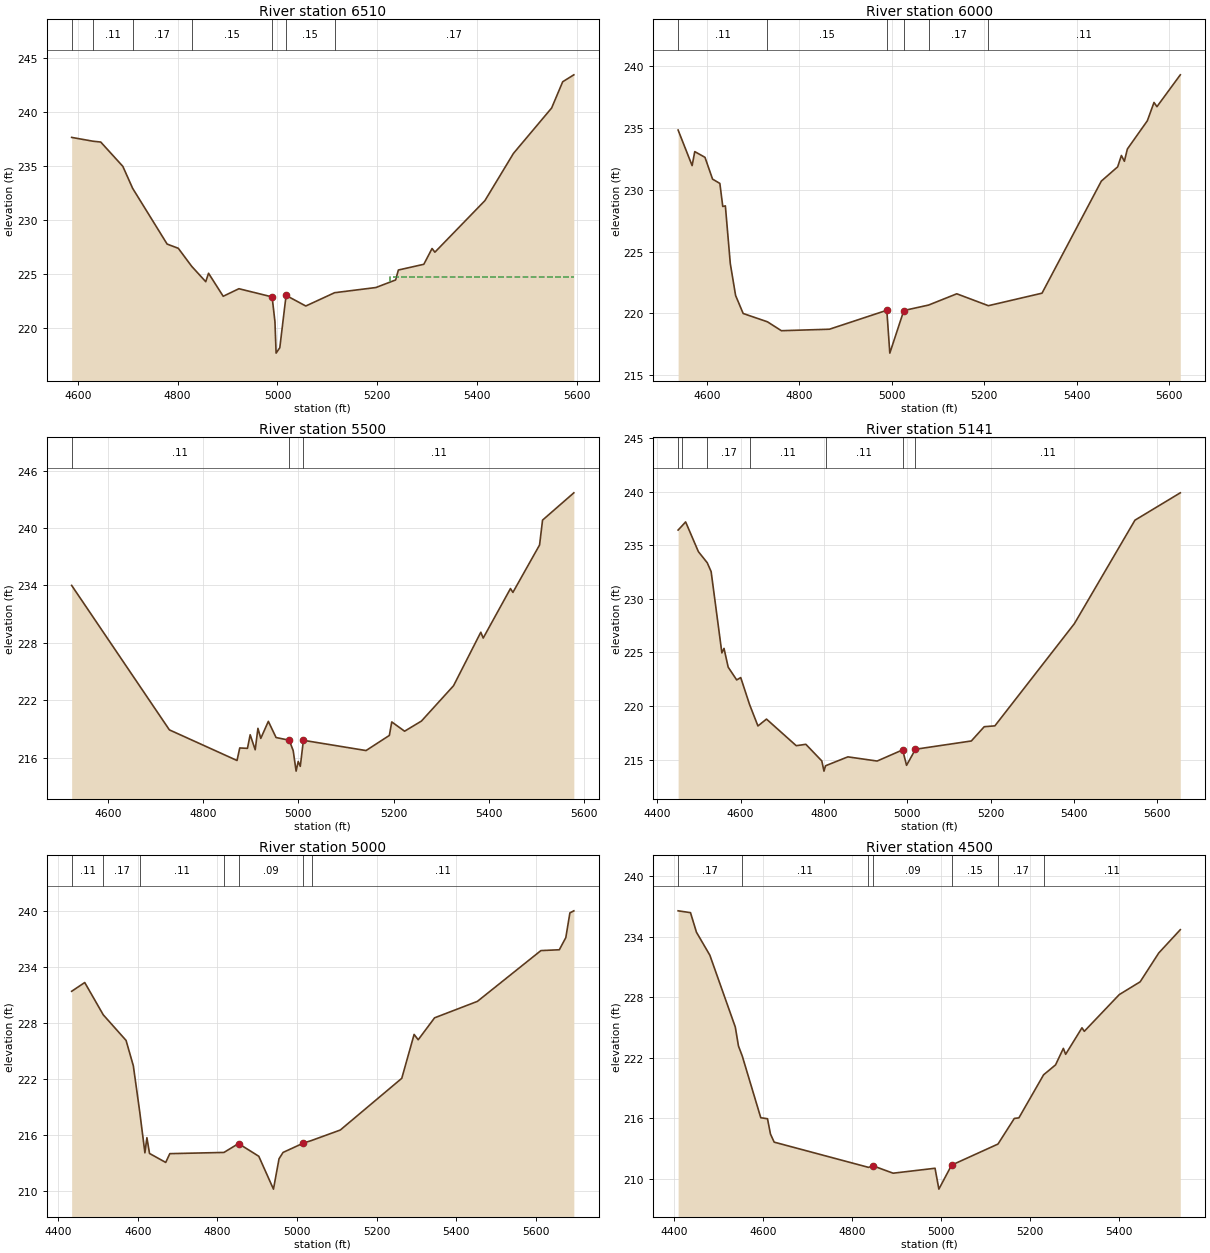
Type RM Length L Ch R = 1 ,6510    ,510,510,510
BEGIN DESCRIPTION:
WEIRS CREEK TRIBUTARY NO 2 13.0
END DESCRIPTION:
XS GIS Cut Line= 3
      3802417.88     10168011.06      3802051.22     10168199.84
      3801517.86     10168461.07
#Sta/Elev= 30
  4587.6  237.68  4630.1  237.33  4645.9  237.25  4690.2     235  4709.8  232.97
  4778.9  227.81  4801.3  227.42  4828.2  225.75  4856.3  224.33  4861.9  225.11
  4891.3  222.98  4922.8  223.68  4989.3  222.92    4995  220.62  4997.3  217.72
  5004.7  218.22  5017.3  223.06  5056.8  222.08  5114.5  223.31  5197.3  223.79
  5236.8  224.49  5242.3  225.41  5293.3  225.94  5309.8   227.4  5315.5  227.06
  5415.7  231.83  5472.9   236.2  5549.4   240.4  5571.6  242.83  5593.9  243.47
#Mann= 7 ,-1 , 0
  4587.6     .17       0  4630.1     .11       0  4709.8     .17       0
  4828.2     .15       0  4989.3     .09       0  5017.3     .15       0
  5114.5     .17       0
#XS Ineff= 2 , 0
       0  4861.9  225.11  5226.5       0  224.74
Permanent Ineff=
       F       F
Bank Sta=4989.3,5017.3
XS Rating Curve= 0 ,0
Exp/Cntr=0.3,0.1

Type RM Length L Ch R = 1 ,6000    ,500,500,500
BEGIN DESCRIPTION:
WEIRS CREEK TRIBUTARY NO 2 12.0
END DESCRIPTION:
XS GIS Cut Line= 3
      3802267.89     10167561.05      3801858.23     10167775.29
      3801367.88     10168161.05
#Sta/Elev= 30
  4537.7  234.81    4568  231.94  4573.7  233.07  4595.8  232.61  4612.2  230.85
    4628   230.5  4634.3  228.64  4639.9  228.69  4650.6  224.02    4662  221.46
  4678.4     220  4730.8  219.33  4761.1  218.61    4865  218.73  4989.1  220.26
  4995.6   216.8  5025.9  220.24  5079.4  220.68  5140.4  221.59  5208.8  220.63
  5324.8  221.64  5453.1  230.69  5488.4  231.84  5496.5  232.76  5502.9  232.29
  5509.4  233.28  5552.6  235.56    5567  237.04  5573.4   236.7  5623.9  239.27
#Mann= 6 ,-1 , 0
  4537.7     .11       0  4730.8     .15       0  4989.1     .09       0
  5025.9     .15       0  5079.4     .17       0  5208.8     .11       0
Bank Sta=4989.1,5025.9
XS Rating Curve= 0 ,0
Exp/Cntr=0.3,0.1

Type RM Length L Ch R = 1 ,5500    ,359,359,359
BEGIN DESCRIPTION:
WEIRS CREEK TRIBUTARY NO 2 11.0
END DESCRIPTION:
XS GIS Cut Line= 3
      3802267.83     10167511.06      3801848.23     10167285.67
      3801276.75     10167376.14
#Sta/Elev= 30
  4523.7     234    4729  218.91  4871.1  215.71  4876.8  217.02    4893  216.98
  4898.7   218.4  4909.3  216.83    4915  219.07    4921  218.02  4936.9   219.8
  4953.1  218.11  4980.7  217.83  4989.1  216.74  4995.2   214.6  4999.6  215.61
    5004   215.1  5010.5  217.82  5142.1  216.75  5191.1  218.33  5196.1  219.74
  5223.1  218.77  5258.5  219.83  5325.9  223.52  5383.2  229.11  5388.2   228.5
  5445.5  233.67  5450.6  233.27  5506.6  238.22  5512.9  240.82  5578.6  243.67
#Mann= 3 , 0 , 0
  4523.7     .11       0  4980.7     .06       0  5010.5     .11       0
Bank Sta=4980.7,5010.5
XS Rating Curve= 0 ,0
Exp/Cntr=0.3,0.1

Type RM Length L Ch R = 1 ,5141    ,141,141,141
BEGIN DESCRIPTION:
Mapping XS 3f74b3c2
END DESCRIPTION:
XS GIS Cut Line= 3
      3802395.47      10166824.9       3801854.4     10166936.08
      3801221.31     10167093.31
#Sta/Elev= 30
  4450.2  236.41  4459.6   236.8  4468.2  237.17  4498.8   234.4  4520.1  233.36
  4529.4  232.54  4555.2  224.96  4560.3  225.38  4570.3  223.63  4590.7  222.44
  4600.4  222.66  4621.6  220.15  4641.7  218.15  4662.2  218.79  4733.6  216.31
  4756.6  216.44  4794.9  214.89  4800.1  213.94  4803.9  214.44  4857.4  215.27
  4927.6  214.88  4988.8  215.92  4998.2  214.48  5019.6  215.98  5153.6  216.75
  5184.5  218.08  5210.1  218.16  5400.9  227.69  5546.1  237.33  5654.9  239.88
#Mann= 7 ,-1 , 0
  4450.2     .17       0  4459.6     .11       0  4520.1     .17       0
  4621.6     .11       0  4803.9     .11       0  4988.8     .06       0
  5019.6     .11       0
Bank Sta=4988.8,5019.6
XS Rating Curve= 0 ,0
Exp/Cntr=0.3,0.1

Type RM Length L Ch R = 1 ,5000    ,500,500,500
BEGIN DESCRIPTION:
WEIRS CREEK TRIBUTARY NO 2 10.0
END DESCRIPTION:
XS GIS Cut Line= 3
      3802410.23     10166691.34       3801853.5      10166796.1
      3801178.23     10166965.12
#Sta/Elev= 30
  4433.5  231.37  4466.4  232.31    4513  228.85  4570.3  226.11  4588.6  223.39
  4604.6  218.48  4617.7  214.07  4622.7  215.69  4629.3     214    4670  213.04
  4680.3  213.98  4816.4  214.11  4853.1  215.06    4904   213.7  4940.9  210.18
  4954.9  213.43    4965  214.11  5016.1  215.11  5036.7  215.39  5108.9  216.51
  5263.5  222.05  5294.5  226.75  5304.8  226.18    5346  228.53  5453.6  230.29
  5613.3  235.73  5659.6  235.82  5675.9  237.12  5686.2  239.77  5696.1  239.99
#Mann= 7 ,-1 , 0
  4433.5     .11       0    4513     .17       0  4604.6     .11       0
  4816.4     .15       0  4853.1     .09       0  5016.1     .15       0
  5036.7     .11       0
Bank Sta=4853.1,5016.1
XS Rating Curve= 0 ,0
Exp/Cntr=0.3,0.1

Type RM Length L Ch R = 1 ,4500    ,500,500,500
BEGIN DESCRIPTION:
WEIRS CREEK TRIBUTARY NO 2 9.0
END DESCRIPTION:
XS GIS Cut Line= 3
      3802371.06     10165995.95      3801878.23     10166320.88
      3801355.41     10166447.34
#Sta/Elev= 30
  4409.7  236.58  4437.5   236.4  4450.9  234.46    4481  232.18  4538.2  225.05
  4545.3  223.17  4553.9  222.17  4595.4  216.06  4610.5  215.96  4617.2  214.44
  4625.5  213.64  4837.3  211.14  4848.3  211.28  4892.7  210.56  4986.9  211.05
  4995.5  208.98  5024.1  211.36  5128.3  213.45    5165  215.99  5175.3  216.05
  5230.8  220.32  5257.6   221.3  5275.2  222.94  5280.3  222.35    5317  224.98
  5322.2  224.63  5400.7  228.27  5447.7  229.54  5489.5   232.4  5537.9  234.71
#Mann= 7 ,-1 , 0
  4409.7     .17       0  4553.9     .11       0  4837.3     .15       0
  4848.3     .09       0  5024.1     .15       0  5128.3     .17       0
  5230.8     .11       0
Bank Sta=4848.3,5024.1
XS Rating Curve= 0 ,0
Exp/Cntr=0.3,0.1

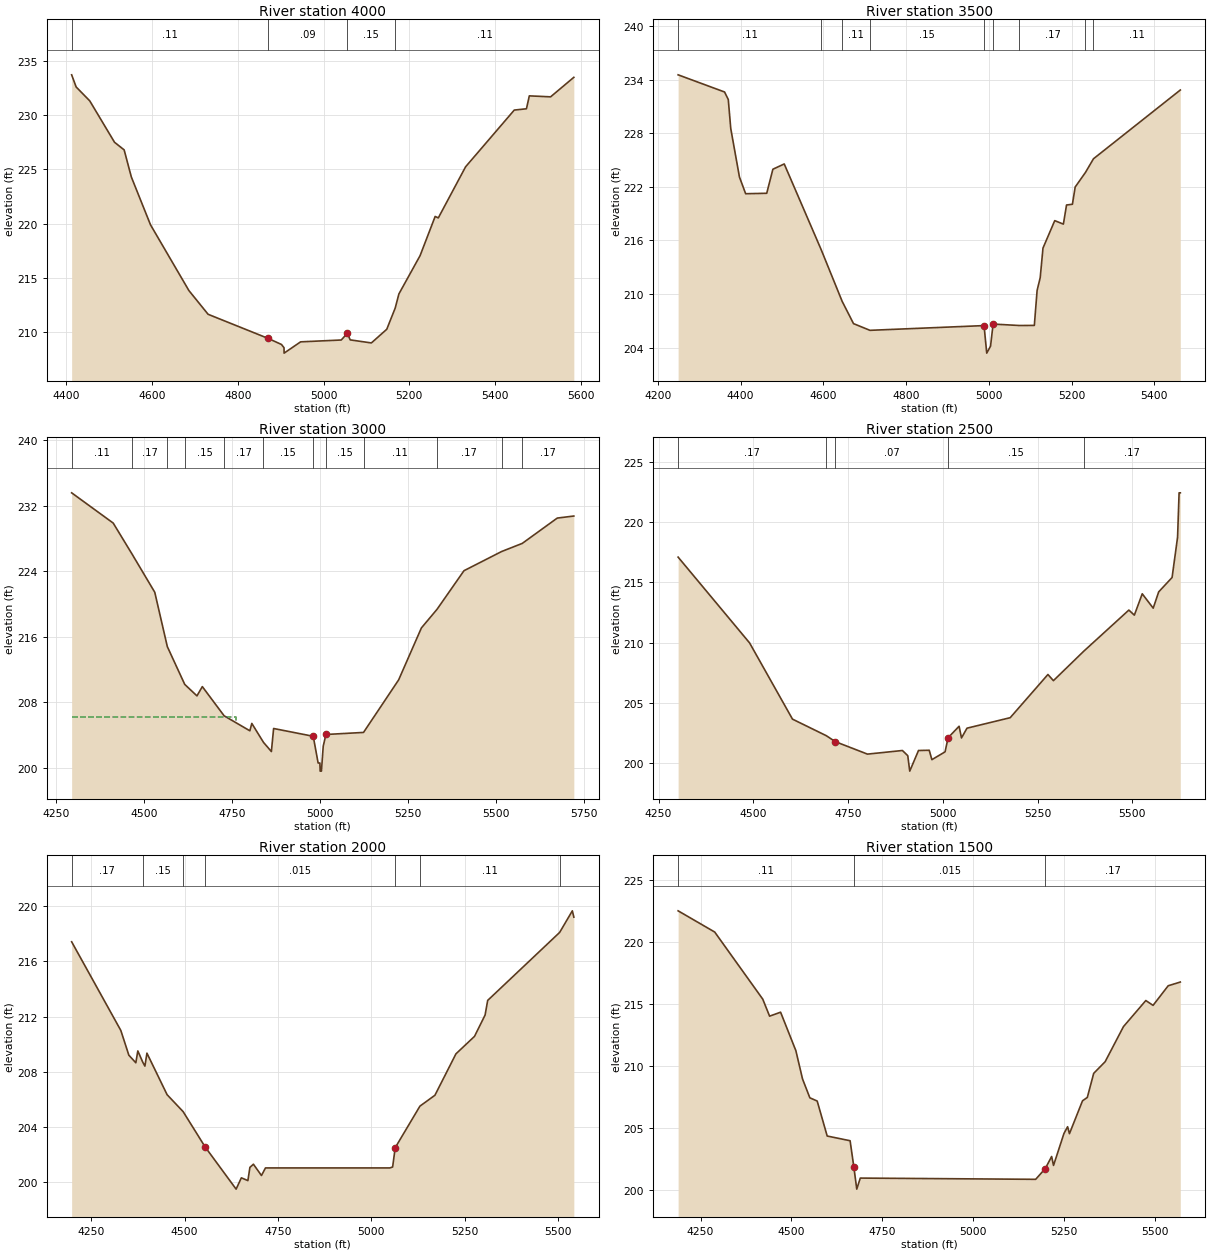
Type RM Length L Ch R = 1 ,4000    ,500,500,500
BEGIN DESCRIPTION:
WEIRS CREEK TRIBUTARY NO 2 8.0
END DESCRIPTION:
XS GIS Cut Line= 3
      3802275.63     10165653.04      3801750.02     10165915.29
      3801317.67     10166307.28
#Sta/Elev= 30
  4412.6  233.71  4423.1  232.59  4454.8  231.31  4512.6  227.49    4535  226.79
  4551.8  224.29  4596.5  219.88    4686  213.82  4730.8  211.63  4870.6  209.41
  4901.8  208.85  4907.8  208.55    4908  208.05  4946.5  209.09  5041.3  209.26
  5055.4  209.88  5062.2  209.27  5111.5  208.99  5147.4  210.25  5167.1  212.21
  5175.7  213.51  5225.1  217.04  5260.2  220.65  5267.6  220.52  5331.2  225.23
  5444.7  230.46  5473.1  230.58  5479.8  231.77  5529.4  231.68  5583.6  233.48
#Mann= 4 ,-1 , 0
  4412.6     .11       0  4870.6     .09       0  5055.4     .15       0
  5167.1     .11       0
Bank Sta=4870.6,5055.4
XS Rating Curve= 0 ,0
Exp/Cntr=0.3,0.1

Type RM Length L Ch R = 1 ,3500    ,500,500,500
BEGIN DESCRIPTION:
WEIRS CREEK TRIBUTARY NO 2 7.0
END DESCRIPTION:
XS GIS Cut Line= 3
      3802080.25      10165106.2      3801458.24     10165526.68
      3801151.63     10165873.08
#Sta/Elev= 30
  4249.2  234.53  4361.4  232.61  4370.4  231.77  4376.4  228.52  4397.4   223.1
  4412.4  221.23  4463.3  221.28  4478.2  223.97  4505.6  224.56    4595  214.96
  4645.5   209.2    4673   206.7  4712.7  205.95  4988.4  206.48  4994.9   203.4
  5004.1  204.18  5010.3  206.65  5073.8  206.49  5109.9   206.5  5116.6  210.41
  5124.1  211.84  5130.8  215.15  5159.2  218.22  5180.1  217.83  5187.7  219.97
  5201.9  220.05  5208.6  221.98  5233.4  223.61  5252.8  225.14  5462.6  232.83
#Mann= 9 ,-1 , 0
  4249.2     .11       0    4595     .17       0  4645.5     .11       0
  4712.7     .15       0  4988.4     .09       0  5010.3     .15       0
  5073.8     .17       0  5233.4     .15       0  5252.8     .11       0
Bank Sta=4988.4,5010.3
XS Rating Curve= 0 ,0
Exp/Cntr=0.3,0.1

Type RM Length L Ch R = 1 ,3000    ,500,500,500
BEGIN DESCRIPTION:
WEIRS CREEK TRIBUTARY NO 2 6.0
END DESCRIPTION:
XS GIS Cut Line= 3
      3801997.82     10164793.68      3801363.94     10165103.41
      3800934.47     10165683.41
#Sta/Elev= 30
  4294.5  233.55  4412.6  229.86  4464.9  226.17  4530.7  221.42  4566.4  214.79
  4615.9  210.18  4650.6  208.78  4665.9  209.91  4727.8  206.35    4801  204.52
  4806.5  205.42  4839.7  203.11  4862.1  201.99  4868.5   204.8  4981.1  203.85
    4995  200.59    5000  200.59  5000.8   199.6  5004.3   199.6  5009.5  202.65
  5017.2  204.07    5124  204.32  5223.8  210.73  5288.5  217.07  5332.9  219.34
  5409.5  224.05  5516.5  226.39  5575.1  227.38  5674.6  230.47  5721.7  230.72
#Mann= 12 ,-1 , 0
  4294.5     .11       0  4464.9     .17       0  4566.4     .11       0
  4615.9     .15       0  4727.8     .17       0  4839.7     .15       0
  4981.1     .09       0  5017.2     .15       0    5124     .11       0
  5332.9     .17       0  5516.5     .11       0  5575.1     .17       0
#XS Ineff= 2 , 0
       0  4761.9  206.15               0
Permanent Ineff=
       F       F
Bank Sta=4981.1,5017.2
XS Rating Curve= 0 ,0
Exp/Cntr=0.3,0.1

Type RM Length L Ch R = 1 ,2500    ,500,500,500
BEGIN DESCRIPTION:
WEIRS CREEK TRIBUTARY NO 2 5.0
END DESCRIPTION:
XS GIS Cut Line= 3
      3801693.96      10164220.8      3801211.98     10164726.22
      3800717.87     10165111.06
#Sta/Elev= 30
  4301.6  217.09  4490.1  209.98  4603.3  203.66  4692.3  202.29  4716.5  201.79
  4801.1  200.76  4893.3  201.06  4907.4  200.63  4912.6  199.35  4935.7  201.06
    4964  201.08    4971   200.3  5005.8  200.95  5013.8  202.12  5042.8  203.07
  5049.1   202.1  5063.6  202.91  5177.6  203.78  5277.1  207.36  5291.6  206.85
  5371.6  209.29  5490.6   212.7  5505.1  212.28  5525.9  214.05  5554.8  212.86
  5569.3  214.21  5604.6   215.4  5619.1  218.74  5623.1  222.42  5626.3  222.42
#Mann= 5 ,-1 , 0
  4301.6     .17       0  4692.3     .15       0  4716.5     .07       0
  5013.8     .15       0  5371.6     .17       0
Bank Sta=4716.5,5013.8
XS Rating Curve= 0 ,0
Exp/Cntr=0.3,0.1

Type RM Length L Ch R = 1 ,2000    ,500,500,500
BEGIN DESCRIPTION:
WEIRS CREEK TRIBUTARY NO 2 4.0
END DESCRIPTION:
XS GIS Cut Line= 3
      3801620.17     10164081.89      3800874.43     10164377.24
      3800501.65     10164770.68
#Sta/Elev= 30
  4197.9  217.43  4329.5  210.99    4351  209.19  4369.7  208.64    4375   209.5
  4388.5  208.67    4394   208.4  4399.4  209.34  4453.4  206.32  4496.3  205.09
  4555.3  202.52  4638.1  199.46  4652.1  200.28  4669.6  200.08    4675  201.04
  4684.4  201.27  4705.9  200.45  4716.7     201  5049.7     201    5057  201.07
  5063.9  202.47  5130.1  205.49  5170.2  206.28  5226.5  209.29  5276.2  210.56
  5304.5  212.11  5311.4  213.17    5504  218.11    5538  219.68    5542  219.22
#Mann= 7 ,-1 , 0
  4197.9     .17       0  4388.5     .15       0  4496.3     .11       0
  4555.3    .015       0  5063.9     .15       0  5130.1     .11       0
    5504     .17       0
Bank Sta=4555.3,5063.9
XS Rating Curve= 0 ,0
Exp/Cntr=0.3,0.1

Type RM Length L Ch R = 1 ,1500    ,500,500,500
BEGIN DESCRIPTION:
WEIRS CREEK TRIBUTARY NO 2 3.0
END DESCRIPTION:
XS GIS Cut Line= 3
      3801567.82     10163811.07      3800761.08     10163899.69
      3800205.28     10164021.11
#Sta/Elev= 30
  4188.4  222.54    4289  220.83  4421.1  215.42  4439.9  214.05  4470.1  214.37
  4512.1  211.27  4530.4  208.99  4550.5  207.47  4570.7  207.21  4598.2  204.39
  4661.2  204.01  4671.3  201.93  4679.5  200.11  4689.2     201  5171.3   200.9
  5197.8  201.77  5215.2  202.74  5220.4  202.02    5249  204.59  5259.1  205.14
  5264.2  204.58  5300.1  207.23  5313.3   207.5  5330.8  209.44  5362.3  210.38
  5412.7  213.21  5474.1  215.31    5494  214.92  5535.6   216.5  5568.9   216.8
#Mann= 3 ,-1 , 0
  4188.4     .11       0  4671.3    .015       0  5197.8     .17       0
Bank Sta=4671.3,5197.8
XS Rating Curve= 0 ,0
Exp/Cntr=0.3,0.1

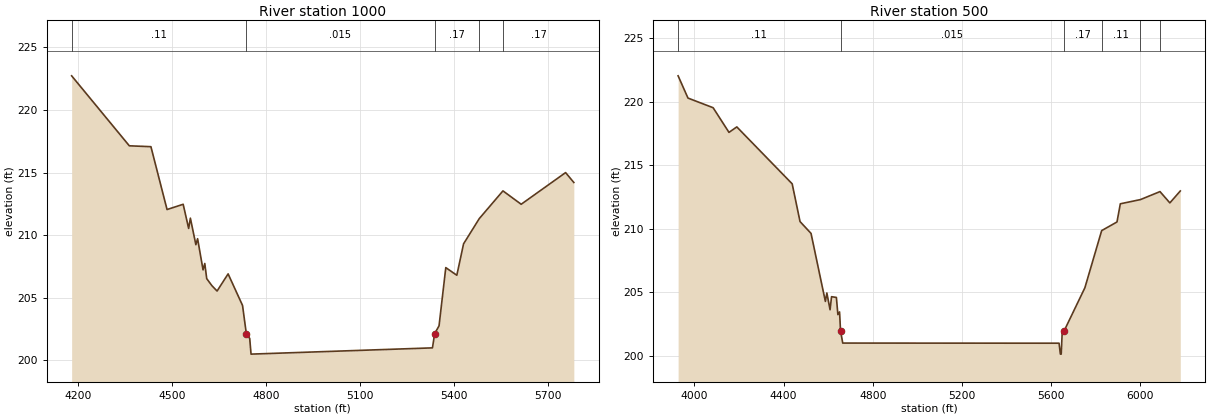
Type RM Length L Ch R = 1 ,1000    ,500,500,500
BEGIN DESCRIPTION:
WEIRS CREEK TRIBUTARY NO 2 2.0
END DESCRIPTION:
XS GIS Cut Line= 3
      3801529.09     10163743.34      3800784.16     10163400.35
      3800213.95     10163934.32
#Sta/Elev= 30
  4179.9  222.73  4363.8  217.14  4432.7  217.07  4484.1  212.05  4535.5  212.47
    4553  210.54  4558.5  211.36    4576  209.24  4581.5  209.72  4598.9  207.23
  4604.4  207.74  4610.6  206.53  4627.4  205.96  4643.6  205.54  4678.8  206.91
  4724.8  204.39 4736.84  202.14  4747.7  201.75  4751.9   200.5  5330.4     201
  5337.4  202.14  5351.4  202.76  5372.9  207.41  5408.1   206.8  5429.6  209.31
  5479.5  211.32  5555.2  213.54  5613.3  212.47  5754.9     215  5781.2  214.21
#Mann= 5 ,-1 , 0
  4179.9     .11       0 4736.84    .015       0  5337.4     .17       0
  5479.5     .11       0  5555.2     .17       0
Bank Sta=4736.84,5337.4
XS Rating Curve= 0 ,0
Exp/Cntr=0.3,0.1

Type RM Length L Ch R = 1 ,500     ,0,0,0
BEGIN DESCRIPTION:
WEIRS CREEK TRIBUTARY NO 2 1.0
END DESCRIPTION:
XS GIS Cut Line= 3
      3801546.46      10163704.3       3800832.6     10162903.61
      3800174.89     10163882.23
#Sta/Elev= 30
  3927.3  222.03  3971.5  220.28  4084.3  219.52  4155.4  217.58  4190.5  218.01
  4438.8  213.53    4474  210.56  4523.3  209.63  4587.6  204.28  4594.3  204.94
  4608.6  203.62  4615.3  204.65    4637  204.59  4643.7  203.24  4651.2  203.45
 4655.51  201.98  4665.4     201  5635.5  200.99  5641.4  200.13  5645.1  200.13
  5649.3  201.77  5658.2  201.96  5751.2  205.35  5826.5  209.85  5895.2  210.53
  5910.2  211.96  6000.2  212.29    6088  212.92  6132.3  212.03  6179.1  212.97
#Mann= 6 ,-1 , 0
  3927.3     .11       0 4655.51    .015       0  5658.2     .17       0
  5826.5     .11       0  6000.2     .17       0    6088     .11       0
Bank Sta=4655.51,5658.2
XS Rating Curve= 0 ,0
Exp/Cntr=0.3,0.1

Chan Stop Cuts=-1
Use User Specified Reach Order=0
Composite Channel Slope=5