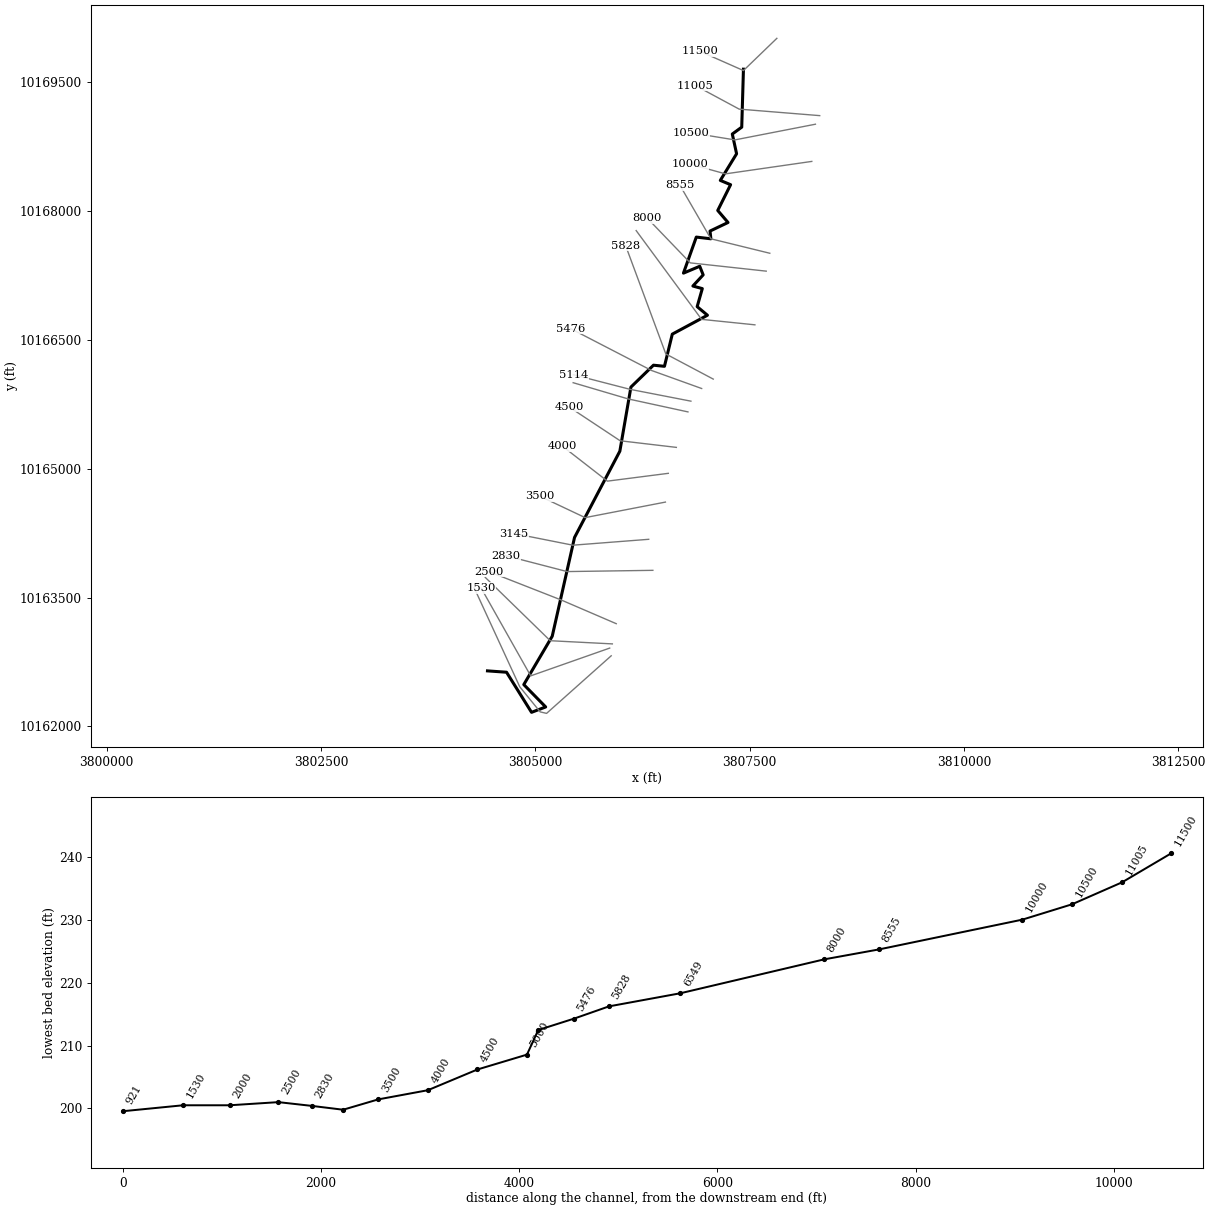
--- WEIRS CREEK TRIBUTARY NO 3.prj (project) ---

Proj Title=WEIRS CREEK TRIBUTARY NO 3 Base Level Engineering
Current Plan=p01
Default Exp/Contr=0.3,0.1
English Units
Geom File=g01
Flow File=f01
Plan File=p01
Y Axis Title=Elevation
X Axis Title(PF)=Main Channel Distance
X Axis Title(XS)=Station
BEGIN DESCRIPTION:
WEIRS CREEK TRIBUTARY NO 3
END DESCRIPTION:
DSS Export Rating Curves= 0
DSS Export Rating Curve Sorted= 0
DSS Export Volume Flow Curves= 0
DXF OffsetX= 0
DXF OffsetY= 0
DXF ScaleX= 1
DXF ScaleY= 10

--- WEIRS CREEK TRIBUTARY NO 3.p01 (plan) ---

Plan Title=Multiple Run
Short Identifier=Multiple
Geom File=g01
Flow File=f01
Subcritical Flow
K Sum by GR= 0
Std Step Tol= 0.01
Critical Tol= 0.01
Num of Std Step Trials= 20
Max Error Tol= 0.3
Flow Tol Ratio= 0.001
Split Flow NTrial= 30
Split Flow Tol= 0.02
Split Flow Ratio= 0.02
Log Output Level= 0
Friction Slope Method= 1
Unsteady Friction Slope Method= 2
Unsteady Bridges Friction Slope Method= 1
Parabolic Critical Depth
Global Vel Dist=  1 , 1 , 1
Global Log Level= 0
CheckData=True
Encroach Param= -1, 0, 0, 0
BEGIN DESCRIPTION:
Multiple Run
END DESCRIPTION:

--- WEIRS CREEK TRIBUTARY NO 3.f01 (steady flow) ---

Flow Title=Multiple
Program Version=4.10
Number of Profiles= 7
Profile Names=10-year,25-year,50-year,1pct_min,100-year,1pct_plu,500-year
River Rch & RM=WEIRS CREEK TRIB,Reach-1         ,11500
     518     690     922     406    1227    3705    2239
River Rch & RM=WEIRS CREEK TRIB,Reach-1         ,10500
     743    1012    1373     613    1851    5590    3474
River Rch & RM=WEIRS CREEK TRIB,Reach-1         ,5476
    1095    1520    2088     942    2846    8595    5464
Boundary for River Rch & Prof#=WEIRS CREEK TRIB,Reach-1         , 1
Up Type= 0
Dn Type= 3
Dn Slope=0.001
Boundary for River Rch & Prof#=WEIRS CREEK TRIB,Reach-1         , 2
Up Type= 0
Dn Type= 3
Dn Slope=0.001
Boundary for River Rch & Prof#=WEIRS CREEK TRIB,Reach-1         , 3
Up Type= 0
Dn Type= 3
Dn Slope=0.001
Boundary for River Rch & Prof#=WEIRS CREEK TRIB,Reach-1         , 4
Up Type= 0
Dn Type= 3
Dn Slope=0.001
Boundary for River Rch & Prof#=WEIRS CREEK TRIB,Reach-1         , 5
Up Type= 0
Dn Type= 3
Dn Slope=0.001
Boundary for River Rch & Prof#=WEIRS CREEK TRIB,Reach-1         , 6
Up Type= 0
Dn Type= 3
Dn Slope=0.001
Boundary for River Rch & Prof#=WEIRS CREEK TRIB,Reach-1         , 7
Up Type= 0
Dn Type= 3
Dn Slope=0.001
DSS Import GetInterval= 0
DSS Import GetPeak= 0
DSS Import FillOption= 0

--- WEIRS CREEK TRIBUTARY NO 3.g01 (geometry) ---

Geom Title=Existing Conditions
Program Version=4.10

River Reach=WEIRS CREEK TRIB,Reach-1
Reach XY= 30
      3807428.23     10169651.84      3807408.23     10168976.84
      3807298.23     10168896.84      3807348.23     10168666.84
      3807158.23     10168356.84      3807278.23     10168306.84
      3807128.23     10168006.84      3807248.23     10167866.84
      3807038.23     10167766.84      3807048.23     10167676.84
      3806878.23     10167696.84      3806728.23     10167276.84
      3806918.23     10167356.84      3806958.23     10167256.84
      3806838.23     10167126.84      3806948.23     10167096.84
      3806888.23     10166886.84      3807008.23     10166786.84
      3806598.23     10166566.84      3806506.66     10166192.07
      3806378.65     10166205.06      3806115.52      10165950.3
      3805986.33     10165203.88      3805457.71     10164199.29
      3805197.49     10163049.11      3804865.73     10162485.92
      3805120.94      10162225.5      3804956.01       10162163.
      3804664.35     10162630.01      3804442.12     10162645.64

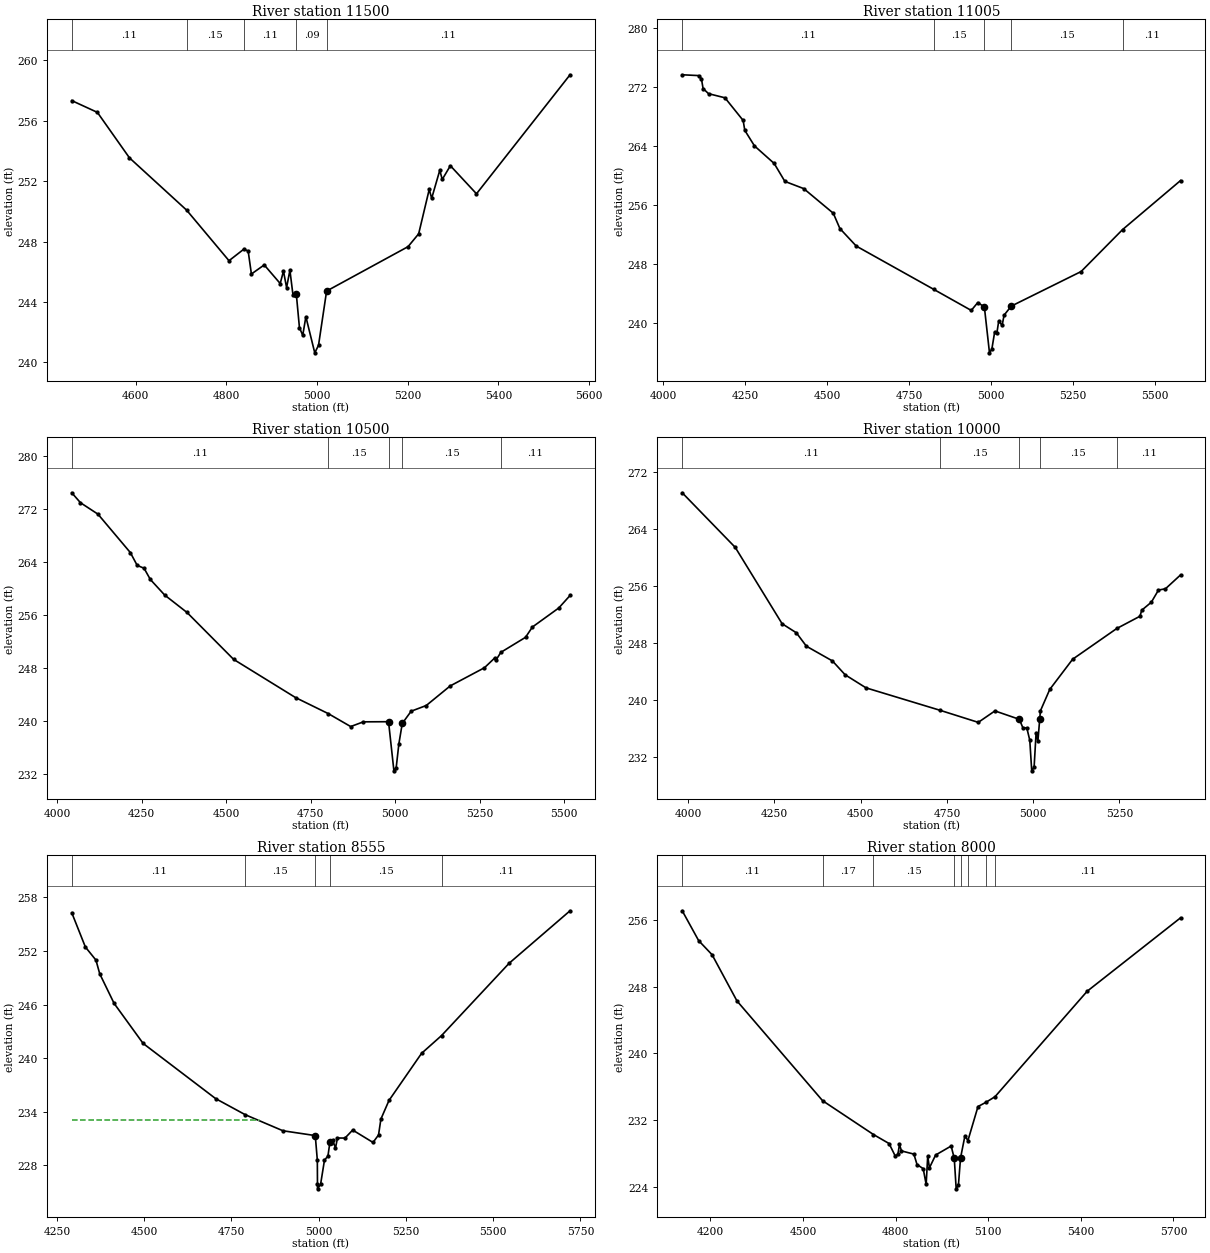
Type RM Length L Ch R = 1 ,11500   ,495,495,495
BEGIN DESCRIPTION:
WEIRS CREEK TRIBUTARY NO 3 19.0
END DESCRIPTION:
XS GIS Cut Line= 3
      3807817.85     10170011.07      3807428.23     10169635.88
       3806917.9     10169861.05
#Sta/Elev= 30
  4459.1  257.33  4515.6  256.55  4586.3  253.54  4712.3  250.08  4805.8  246.73
  4837.9  247.48    4848  247.38  4855.2  245.85  4883.5  246.45  4918.7  245.22
  4925.9  246.04  4932.8  244.95  4940.1   246.1    4947  244.43  4954.2  244.53
  4961.1   242.3  4968.4  241.79  4975.3  243.02  4994.9  240.63  5003.2  241.13
    5021  244.72  5200.6  247.66    5224  248.51  5247.3  251.45  5252.7  250.86
  5270.6  252.72    5276  252.11  5293.9  253.02  5351.5  251.16  5557.8  259.04
#Mann= 5 ,-1 , 0
  4459.1     .11       0  4712.3     .15       0  4837.9     .11       0
  4954.2     .09       0    5021     .11       0
Bank Sta=4954.2,5021
XS Rating Curve= 0 ,0
Exp/Cntr=0.3,0.1

Type RM Length L Ch R = 1 ,11005   ,505,505,505
BEGIN DESCRIPTION:
WEIRS CREEK TRIBUTARY NO 3 18.0
END DESCRIPTION:
XS GIS Cut Line= 3
      3808317.88     10169111.07      3807378.23     10169186.84
      3806867.84     10169461.08
#Sta/Elev= 30
  4057.3  273.71  4107.5   273.6    4116  273.16    4121  271.85  4137.6  271.15
  4187.8  270.59  4243.4  267.52  4248.4  266.18    4278  264.07  4338.2  261.69
  4370.8  259.26  4428.5  258.28  4518.8  254.94  4538.9  252.87    4589  250.49
  4825.8  244.62  4940.2  241.77  4960.2  242.84  4980.3  242.23  4995.9  236.02
  5003.1  236.52  5011.8  238.86  5018.5  238.71  5024.2  240.36  5034.5  239.73
  5040.4  241.12  5062.3  242.35  5275.8  247.04  5402.3  252.72  5579.4  259.37
#Mann= 5 ,-1 , 0
  4057.3     .11       0  4825.8     .15       0  4980.3     .09       0
  5062.3     .15       0  5402.3     .11       0
Bank Sta=4980.3,5062.3
XS Rating Curve= 0 ,0
Exp/Cntr=0.3,0.1

Type RM Length L Ch R = 1 ,10500   ,500,500,500
BEGIN DESCRIPTION:
WEIRS CREEK TRIBUTARY NO 3 17.0
END DESCRIPTION:
XS GIS Cut Line= 3
      3808267.84     10169011.07      3807328.23     10168828.43
      3806817.88     10168911.07
#Sta/Elev= 30
  4042.8   274.4  4068.6   272.9  4120.3  271.18    4216   265.4  4236.3  263.47
  4256.7  263.03  4275.3  261.34  4317.8  258.99  4383.8  256.37  4521.6  249.31
    4705  243.55    4802  241.13    4868  239.19  4905.6   239.9    4980  239.92
  4995.9  232.52  5002.7  233.02  5010.5  236.56  5020.6  239.66  5046.9   241.5
  5091.6  242.36  5162.5  245.31  5263.8  248.05  5293.6  249.49  5298.6  249.25
  5312.1  250.36  5385.3  252.63  5405.6  254.18  5483.7  257.05    5517  258.93
#Mann= 5 ,-1 , 0
  4042.8     .11       0    4802     .15       0    4980     .09       0
  5020.6     .15       0  5312.1     .11       0
Bank Sta=4980,5020.6
XS Rating Curve= 0 ,0
Exp/Cntr=0.3,0.1

Type RM Length L Ch R = 1 ,10000   ,1445,1445,1445
BEGIN DESCRIPTION:
WEIRS CREEK TRIBUTARY NO 3 16.0
END DESCRIPTION:
XS GIS Cut Line= 3
      3808225.36     10168577.92      3807218.23     10168432.99
      3806806.25     10168546.37
#Sta/Elev= 30
  3982.5  269.15  4136.2  261.48  4272.1  250.75  4313.4  249.48  4342.6  247.59
  4418.1  245.52  4454.8  243.58  4515.4  241.74  4730.6  238.58  4840.9  236.89
  4889.2   238.5    4960  237.32  4970.1  236.15  4981.8  236.09  4990.3  234.37
  4995.9  230.08  5002.8  230.58  5008.6  235.45  5013.8  234.24 5019.21  237.43
  5021.1  238.51  5048.2  241.52  5114.5  245.76  5242.5  250.08  5309.7   251.8
  5314.9  252.65  5342.7  253.77  5363.4  255.48  5383.7  255.66  5427.3   257.6
#Mann= 5 ,-1 , 0
  3982.5     .11       0  4730.6     .15       0    4960     .09       0
 5019.21     .15       0  5242.5     .11       0
Bank Sta=4960,5019.21
XS Rating Curve= 0 ,0
Exp/Cntr=0.3,0.1

Type RM Length L Ch R = 1 ,8555    ,555,555,555
BEGIN DESCRIPTION:
WEIRS CREEK TRIBUTARY NO 3 15.0
END DESCRIPTION:
XS GIS Cut Line= 3
      3807735.71     10167508.48      3807048.23     10167676.84
      3806687.16     10168300.11
#Sta/Elev= 30
  4292.2  256.29  4331.2  252.45  4361.5  250.98  4372.4  249.44  4413.5  246.13
  4496.7  241.64  4704.7  235.45  4789.4  233.65  4897.4  231.85  4990.1  231.31
    4996  228.55  4996.4  225.84  4996.6  225.34  5005.3  225.84  5016.5  228.56
  5026.4  229.01  5032.2  230.62  5039.6  230.84    5048  229.91  5053.8  231.04
  5075.3  231.03  5097.3  231.93  5155.6  230.54  5171.4  231.38  5178.2  233.16
  5201.4  235.25  5294.8  240.53    5352  242.52  5545.8  250.63  5720.3  256.51
#Mann= 5 ,-1 , 0
  4292.2     .11       0  4789.4     .15       0  4990.1     .09       0
  5032.2     .15       0    5352     .11       0
#XS Ineff= 2 , 0
       0  4829.6  233.02               0
Permanent Ineff=
       F       F
Bank Sta=4990.1,5032.2
XS Rating Curve= 0 ,0
Exp/Cntr=0.3,0.1

Type RM Length L Ch R = 1 ,8000    ,1451,1451,1451
BEGIN DESCRIPTION:
WEIRS CREEK TRIBUTARY NO 3 14.0
END DESCRIPTION:
XS GIS Cut Line= 3
      3807694.07     10167300.14      3806807.89     10167396.51
      3806306.22     10167917.13
#Sta/Elev= 30
  4108.6  257.13  4161.8  253.55  4205.4  251.85  4285.9  246.31  4563.4  234.33
  4728.2  230.27  4778.7  229.19  4798.9  227.68  4807.4   227.9  4812.5  229.08
    4819   228.3  4859.2  227.92  4869.3  226.67  4889.4  226.17  4898.9  224.28
    4904  227.68  4909.5  226.27  4929.6  227.81  4979.9  228.89    4990  227.41
  4996.2  223.75  5003.6  224.25  5010.3  227.45  5024.4  230.09  5034.3  229.55
  5066.9  233.63  5091.8  234.12    5122  234.81  5420.6  247.47    5723  256.28
#Mann= 8 ,-1 , 0
  4108.6     .11       0  4563.4     .17       0  4728.2     .15       0
    4990     .09       0  5010.3     .15       0  5034.3     .11       0
  5091.8     .15       0    5122     .11       0
Bank Sta=4990,5010.3
XS Rating Curve= 0 ,0
Exp/Cntr=0.3,0.1

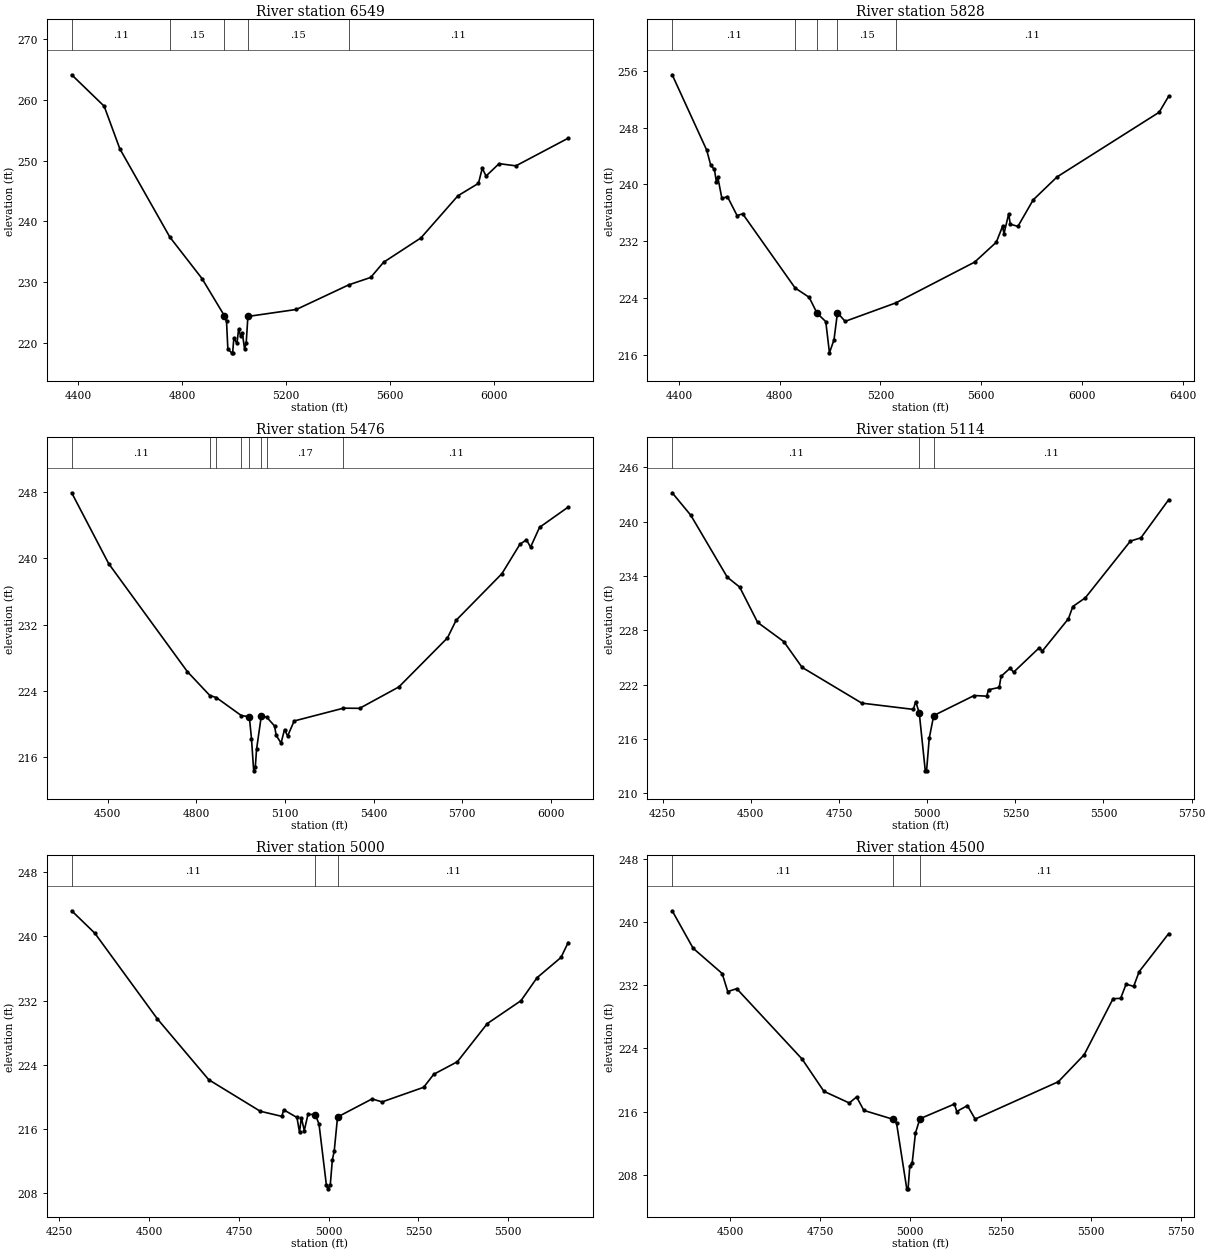
Type RM Length L Ch R = 1 ,6549    ,721,721,721
BEGIN DESCRIPTION:
WEIRS CREEK TRIBUTARY NO 3 12.0
END DESCRIPTION:
XS GIS Cut Line= 3
      3807562.16     10166675.13       3806940.1     10166738.71
      3806176.71     10167772.38
#Sta/Elev= 30
  4374.7  264.12  4499.7  258.95    4560  251.93  4752.4   237.4  4876.1  230.58
  4962.1  224.47  4970.5  223.52  4975.6  218.96  4990.5  218.35    4994  218.35
  4998.6  220.75  5010.7   219.9  5016.9  222.25  5025.3  221.04  5031.5  221.57
  5039.9  218.94  5046.2  219.98  5052.7  224.34  5239.1  225.49  5440.7  229.54
  5525.1  230.76  5574.8  233.26  5718.5  237.27  5860.7   244.2  5939.8  246.25
  5954.4  248.73    5969  247.45  6019.1  249.49  6083.9  249.13    6285  253.68
#Mann= 5 ,-1 , 0
  4374.7     .11       0  4752.4     .15       0  4962.1     .09       0
  5052.7     .15       0  5440.7     .11       0
Bank Sta=4962.1,5052.7
XS Rating Curve= 0 ,0
Exp/Cntr=0.3,0.1

Type RM Length L Ch R = 1 ,5828    ,352,352,352
BEGIN DESCRIPTION:
WEIRS CREEK TRIBUTARY NO 3 11.0
END DESCRIPTION:
XS GIS Cut Line= 3
      3807076.02      10166043.2      3806522.47     10166336.17
      3806054.06     10167596.44
#Sta/Elev= 30
  4373.7  255.47  4510.6  244.85  4526.9  242.69  4541.3  242.12  4548.9  240.39
  4554.6  241.04  4570.9  238.04  4592.9  238.29  4631.3  235.61  4653.3  235.87
  4861.5  225.41  4917.3  224.09  4948.7  221.85  4983.3  220.66  4997.9  216.26
  5015.9   218.1  5029.7  221.92  5060.1   220.7  5261.1   223.3  5574.5  229.06
  5660.2  231.86  5685.2  234.12  5690.6  233.04  5709.3  235.86  5715.6   234.4
  5745.9  234.09  5806.6  237.83  5901.4  241.07  6306.8  250.19  6344.5  252.46
#Mann= 5 ,-1 , 0
  4373.7     .11       0  4861.5     .15       0  4948.7     .09       0
  5029.7     .15       0  5261.1     .11       0
Bank Sta=4948.7,5029.7
XS Rating Curve= 0 ,0
Exp/Cntr=0.3,0.1

Type RM Length L Ch R = 1 ,5476    ,362,362,362
BEGIN DESCRIPTION:
Mapping XS 747913f0
END DESCRIPTION:
XS GIS Cut Line= 3
      3806940.68     10165933.63      3806355.65     10166143.72
      3805414.75     10166629.49
#Sta/Elev= 30
  4378.4  247.94  4503.8  239.36  4769.7  226.32    4846  223.42  4867.6  223.18
  4952.4     221  4979.6  220.85    4987  218.22  4994.4  214.31    5000  214.81
  5004.1   216.9    5020   220.9    5038  220.82    5065  219.74  5070.6   218.6
  5087.1  217.67  5098.8   219.3  5109.3  218.52  5131.4  220.34  5298.4  221.89
    5353  221.87  5485.9  224.46  5650.3  230.39  5679.6  232.52  5834.7  238.16
  5895.5  241.71  5917.7  242.25  5931.6  241.37    5962  243.76  6058.9  246.21
#Mann= 8 ,-1 , 0
  4378.4     .11       0    4846     .15       0  4867.6     .17       0
  4952.4     .15       0  4979.6     .09       0    5020     .15       0
    5038     .17       0  5298.4     .11       0
Bank Sta=4979.6,5020
XS Rating Curve= 0 ,0
Exp/Cntr=0.3,0.1

Type RM Length L Ch R = 1 ,5114    ,114,114,114
BEGIN DESCRIPTION:
WEIRS CREEK TRIBUTARY NO 3 10.0
END DESCRIPTION:
XS GIS Cut Line= 3
      3806815.58     10165786.25       3806105.9     10165923.84
      3805442.66     10166094.73
#Sta/Elev= 30
  4277.1  243.17  4329.8  240.69  4433.2  233.86  4468.3  232.77  4519.3  228.87
  4593.5  226.75  4645.3  223.91  4814.7  219.96  4960.8  219.27  4967.5  220.13
  4977.6  218.88  4994.7  212.49  4998.3  212.49    5006  216.11  5018.6  218.59
  5133.3   220.8  5168.8  220.73    5174  221.44  5204.3  221.69  5209.5  222.91
  5235.5  223.83    5245  223.37  5318.1  226.08  5326.4   225.7  5400.7  229.28
    5413  230.62  5448.5  231.58  5576.3  237.84  5606.1   238.2  5684.9  242.41
#Mann= 3 , 0 , 0
  4277.1     .11       0  4977.6     .06       0  5018.6     .11       0
Bank Sta=4977.6,5018.6
XS Rating Curve= 0 ,0
Exp/Cntr=0.3,0.1

Type RM Length L Ch R = 1 ,5000    ,500,500,500
BEGIN DESCRIPTION:
WEIRS CREEK TRIBUTARY NO 3 9.0
END DESCRIPTION:
XS GIS Cut Line= 3
      3806780.89     10165661.25      3806081.53     10165812.85
      3805441.78     10166001.18
#Sta/Elev= 30
  4284.4  243.18  4348.9  240.39  4522.9  229.73  4666.1  222.15  4809.4  218.23
  4869.6  217.59  4874.7  218.41  4911.7  217.45  4918.8  215.61  4923.9  217.43
  4932.1  215.83  4942.4  217.85  4962.8  217.81  4973.1  216.63  4993.5  209.08
  4997.5  208.57  5004.5  209.07  5010.2  212.18  5015.4  213.25  5024.7  217.51
  5120.7  219.76  5148.8  219.39  5264.5  221.21  5292.6  222.83  5358.3  224.39
  5441.7  229.14  5535.5  231.99  5580.2  234.85  5646.9  237.37  5666.9  239.23
#Mann= 3 , 0 , 0
  4284.4     .11       0  4962.8     .07       0  5024.7     .11       0
Bank Sta=4962.8,5024.7
XS Rating Curve= 0 ,0
Exp/Cntr=0.3,0.1

Type RM Length L Ch R = 1 ,4500    ,500,500,500
BEGIN DESCRIPTION:
WEIRS CREEK TRIBUTARY NO 3 8.0
END DESCRIPTION:
XS GIS Cut Line= 3
      3806645.44     10165248.06      3805989.95     10165325.07
      3805392.46     10165719.98
#Sta/Elev= 30
    4340  241.44    4398  236.69  4478.5  233.49    4494   231.2  4518.8  231.57
    4700  222.65  4760.5  218.56  4830.9  217.08  4851.1  217.85  4871.2  216.14
  4951.8  215.02  4961.8  214.54  4990.2   206.2  4993.8   206.2  4998.5  209.05
  5005.2  209.49  5014.2  213.25  5026.5  215.08  5122.4  216.95  5128.6     216
  5158.3  216.75  5179.7  215.04  5410.1  219.77    5482   223.2    5562   230.3
    5583  230.34  5598.1  232.14  5619.1  231.86  5634.2  233.72  5716.2  238.55
#Mann= 3 , 0 , 0
    4340     .11       0  4951.8     .06       0  5026.5     .11       0
Bank Sta=4951.8,5026.5
XS Rating Curve= 0 ,0
Exp/Cntr=0.3,0.1

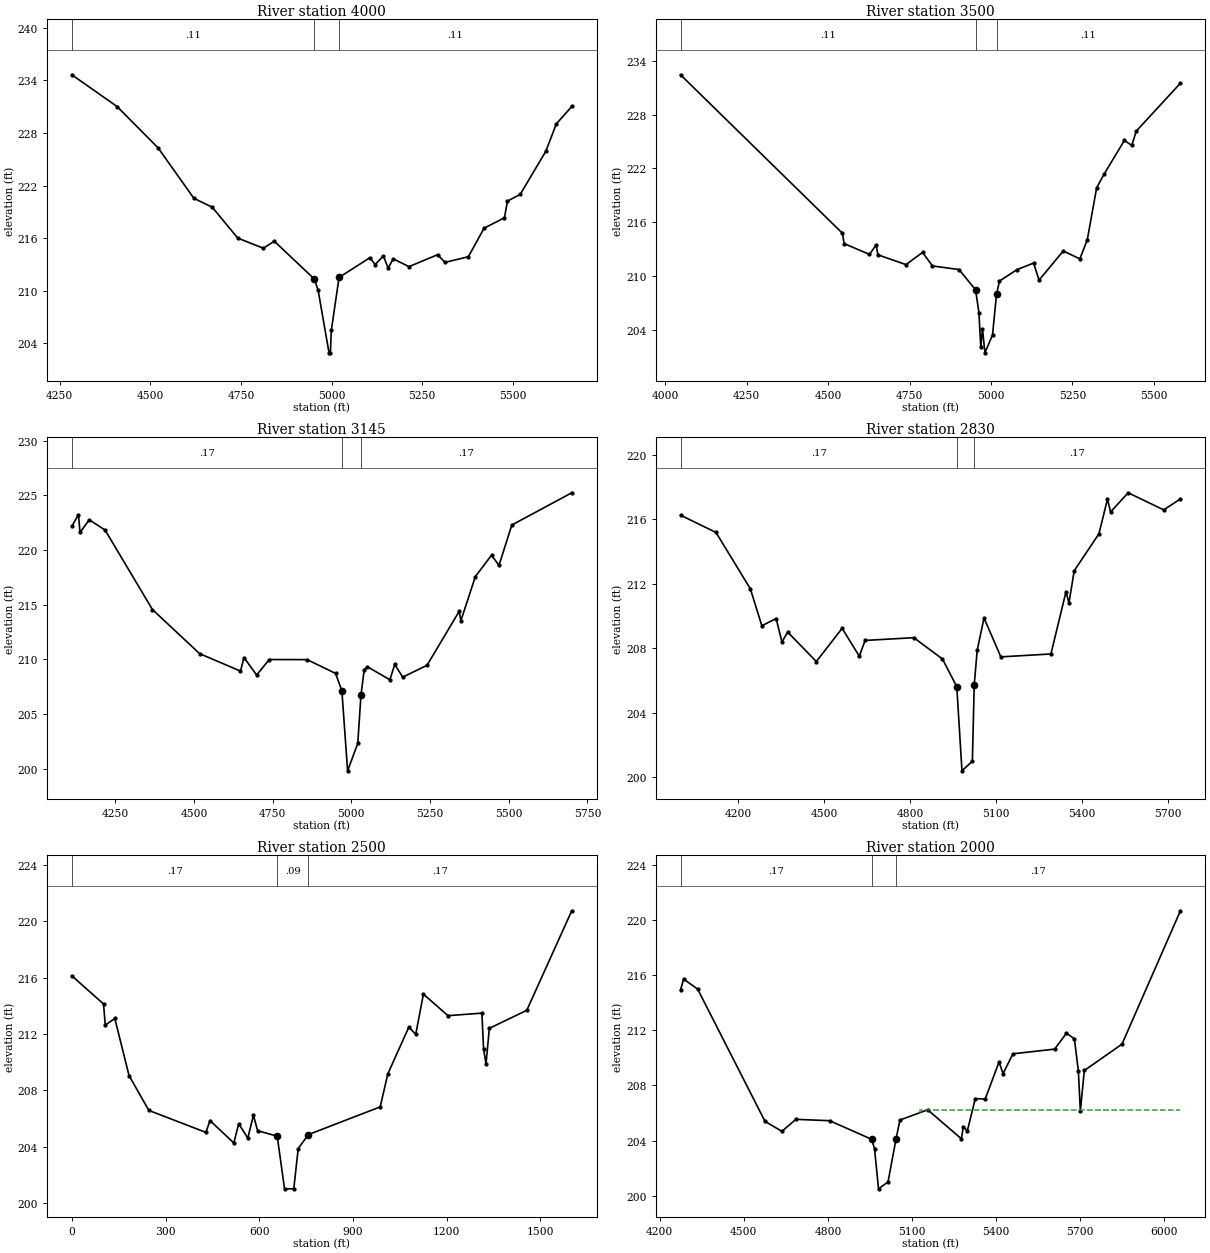
Type RM Length L Ch R = 1 ,4000    ,500,500,500
BEGIN DESCRIPTION:
WEIRS CREEK TRIBUTARY NO 3 7.0
END DESCRIPTION:
XS GIS Cut Line= 3
      3806551.77     10164945.97      3805840.98     10164854.96
      3805317.82      10165261.1
#Sta/Elev= 30
  4283.4  234.64  4408.3  231.01  4521.6  226.28    4620  220.54  4670.5  219.53
    4741     216  4811.6  214.84  4841.8  215.64  4952.7  211.31  4962.8  210.03
  4992.8   202.9  4996.5   202.9  4999.1  205.47  5020.5  211.51  5105.6  213.76
  5120.1  212.97  5142.7  213.97  5155.9  212.57  5169.9  213.63  5213.3  212.74
  5292.1   214.1  5312.9  213.23  5377.1  213.87  5420.6  217.13  5476.7  218.32
  5484.9  220.22  5520.2  220.99  5590.8  225.91  5619.7  229.03  5662.3  231.02
#Mann= 3 , 0 , 0
  4283.4     .11       0  4952.7     .07       0  5020.5     .11       0
Bank Sta=4952.7,5020.5
XS Rating Curve= 0 ,0
Exp/Cntr=0.3,0.1

Type RM Length L Ch R = 1 ,3500    ,355,355,355
BEGIN DESCRIPTION:
WEIRS CREEK TRIBUTARY NO 3 6.0
END DESCRIPTION:
XS GIS Cut Line= 3
      3806517.84     10164611.07      3805581.54     10164430.28
      3805055.18     10164678.62
#Sta/Elev= 30
  4046.4  232.45  4543.9  214.77    4549  213.62  4626.9  212.42  4647.3  213.47
  4652.7  212.37    4739  211.28  4789.9  212.64  4820.4  211.13  4901.9  210.73
  4952.8  208.46    4963  205.92  4968.8  202.07  4973.9  204.13  4981.5  201.44
  5004.8  203.43  5017.1  207.98  5026.2  209.45  5079.9  210.72    5131  211.45
  5147.8  209.55  5222.1   212.8  5273.2  211.92  5295.9  214.05  5324.7  219.85
    5347  221.33  5409.8  225.13  5432.6  224.57  5446.4  226.17    5582  231.51
#Mann= 3 , 0 , 0
  4046.4     .11       0  4952.8     .07       0  5017.1     .11       0
Bank Sta=4952.8,5017.1
XS Rating Curve= 0 ,0
Exp/Cntr=0.3,0.1

Type RM Length L Ch R = 1 ,3145    ,315,315,315
BEGIN DESCRIPTION:
WEIRS CREEK TRIBUTARY NO 3 5.0
END DESCRIPTION:
XS GIS Cut Line= 3
      3806323.11     10164177.75      3805438.06     10164109.18
      3804751.11     10164245.28
#Sta/Elev= 30
  4112.3  222.16  4133.3  223.22  4138.3  221.59  4167.7  222.75  4217.9  221.81
  4368.3  214.54  4518.1  210.51    4648  208.91  4659.2  210.15  4699.3  208.55
  4739.4  209.97  4859.8  209.96  4950.1   208.7  4970.1  207.11  4988.3  199.79
  5020.6   202.3  5030.6  206.69    5041  209.05  5051.2  209.31  5122.5  208.12
  5138.1  209.52  5163.3  208.36  5240.5  209.44    5343  214.39  5348.1  213.52
  5394.2  217.56  5445.4  219.51  5469.2  218.58  5509.9  222.27  5700.3  225.22
#Mann= 3 , 0 , 0
  4112.3     .17       0  4970.1     .07       0  5030.6     .17       0
Bank Sta=4970.1,5030.6
XS Rating Curve= 0 ,0
Exp/Cntr=0.3,0.1

Type RM Length L Ch R = 1 ,2830    ,338,338,338
BEGIN DESCRIPTION:
Mapping XS 23d3cf93
END DESCRIPTION:
XS GIS Cut Line= 3
      3806371.55     10163816.43      3805371.06     10163801.95
      3804651.37     10163988.21
#Sta/Elev= 30
  3999.4  216.26  4123.1  215.19  4243.1  211.69  4283.1   209.4  4333.1  209.85
  4353.1  208.39  4373.1  209.01  4473.2  207.18  4563.2  209.24  4623.2  207.51
  4643.2  208.49  4813.2  208.66  4913.2  207.34  4963.2  205.62  4981.3   200.4
  5017.6     201    5024  205.71  5034.3  207.87  5058.2  209.88  5116.9  207.47
  5291.6  207.65  5344.2  211.51  5354.5  210.81  5372.8  212.81  5459.2  215.11
  5488.8  217.25  5499.8  216.46  5561.1  217.65  5685.1  216.59  5743.4  217.27
#Mann= 3 , 0 , 0
  3999.4     .17       0  4963.2     .07       0    5024     .17       0
Bank Sta=4963.2,5024
XS Rating Curve= 0 ,0
Exp/Cntr=0.3,0.1

Type RM Length L Ch R = 1 ,2500    ,492,492,492
XS GIS Cut Line= 3
       3805944.3     10163195.19      3805302.19     10163471.13
      3804461.45     10163800.14
#Sta/Elev= 30
       0  216.13   101.5  214.13     107  212.63   137.6   213.1   183.1  209.05
   246.5  206.57   429.4  205.01   442.4  205.85   518.6  204.26   534.5  205.62
   563.5   204.6   581.6  206.23   594.8  205.13   657.7  204.74   681.2     201
   710.7     201     725  203.86   757.2  204.85   987.5  206.82    1012  209.17
  1079.4  212.49  1101.4  211.97  1125.9  214.83  1204.6   213.3  1313.2  213.48
  1318.6  210.95  1326.4  209.86  1337.1   212.4    1457  213.68    1601  220.75
#Mann= 3 , 0 , 0
       0     .17       0   657.7     .09       0   757.2     .17       0
Bank Sta=657.7,757.2
XS Rating Curve= 0 ,0
Exp/Cntr=0.3,0.1

Type RM Length L Ch R = 1 ,2000    ,470,470,470
BEGIN DESCRIPTION:
WEIRS CREEK TRIBUTARY NO 3 3.0
END DESCRIPTION:
XS GIS Cut Line= 3
       3805898.9     10162959.86      3805174.25      10162996.9
      3804416.29     10163734.19
#Sta/Elev= 30
  4274.4  214.92  4285.5  215.71  4335.5  214.98  4575.8  205.39  4635.9  204.67
    4686  205.54  4806.1  205.44  4956.3  204.09  4966.4  203.41  4980.6   200.5
  5014.5     201  5042.8  204.09    5057  205.49    5156  206.23  5276.1  204.13
  5283.3     205  5297.5  204.71  5325.7  207.04    5361  207.01  5410.6   209.7
  5424.8  208.85    5460  210.29  5608.7  210.63  5650.9  211.78  5679.2  211.38
  5693.3  209.07  5700.5  206.16  5714.7  209.08    5849  210.99  6057.4  220.66
#Mann= 3 , 0 , 0
  4274.4     .17       0  4956.3     .07       0  5042.8     .17       0
#XS Ineff= 2 , 0
       0                  5127.7       0   206.2
Permanent Ineff=
       F       F
Bank Sta=4956.3,5042.8
XS Rating Curve= 0 ,0
Exp/Cntr=0.3,0.1

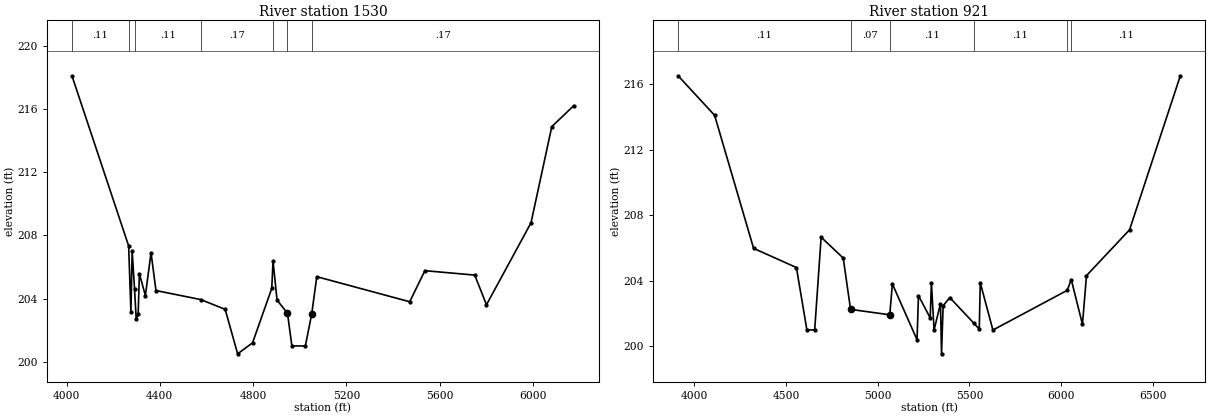
Type RM Length L Ch R = 1 ,1530    ,609,609,609
BEGIN DESCRIPTION:
WEIRS CREEK TRIBUTARY NO 3 1.0
END DESCRIPTION:
XS GIS Cut Line= 3
      3805867.84     10162911.07      3804946.25     10162587.65
      3804367.83     10163611.11
#Sta/Elev= 30
  4023.3  218.12  4266.4  207.34  4276.2  203.15  4281.5  207.01  4291.7  204.61
  4298.8  202.71  4307.2  203.01  4312.5  205.58  4338.2  204.19  4362.4  206.91
  4383.6  204.51  4575.3  203.94  4680.4  203.32  4733.8   200.5  4797.8   201.2
  4880.2  204.65  4885.5  206.39  4902.9   203.9  4947.5  203.08  4966.5     201
  5024.2     201  5051.6  203.04  5073.2  205.39  5471.7   203.8  5536.7  205.77
  5750.6  205.49  5800.9  203.61  5991.8   208.8    6081   214.9  6175.6  216.23
#Mann= 7 ,-1 , 0
  4023.3     .11       0  4266.4    .125       0  4291.7     .11       0
  4575.3     .17       0  4885.5     .11       0  4947.5     .07       0
  5051.6     .17       0
#XS Ineff= 2 , 0
       0  4885.5  206.39  5073.2       0  205.39
Permanent Ineff=
       T       T
Bank Sta=4947.5,5051.6
XS Rating Curve= 0 ,0
Exp/Cntr=0.3,0.1

Type RM Length L Ch R = 1 ,921     ,0,0,0
BEGIN DESCRIPTION:
WEIRS CREEK TRIBUTARY NO 3 1.5
END DESCRIPTION:
XS GIS Cut Line= 5
      3805885.49     10162821.33      3805131.59     10162150.83
      3805056.71     10162168.21      3804819.09     10162459.86
      3804286.07     10163615.24
#Sta/Elev= 30
  3914.2  216.48  4111.4  214.09  4323.8  205.98  4557.1  204.81    4614  201.02
  4656.6     201  4691.7  206.66  4812.1  205.39 4852.05  202.26  5065.6  201.93
  5079.9  203.81  5214.2  200.41  5222.1   203.1    5286  201.74  5292.5  203.89
  5306.9     201    5342  202.61  5347.6  199.55  5356.4  202.48  5392.6  202.98
  5522.6  201.43  5553.2  201.06  5558.7  203.88  5627.6     201  6032.3  203.42
  6054.4  204.08  6115.4  201.35  6137.4  204.32    6372  207.11  6648.6   216.5
#Mann= 6 ,-1 , 0
  3914.2     .11       0 4852.05     .07       0  5065.6     .11       0
  5522.6     .11       0  6032.3     .15       0  6054.4     .11       0
Bank Sta=4852.05,5065.6
XS Rating Curve= 0 ,0
Exp/Cntr=0.3,0.1

Chan Stop Cuts=-1
Use User Specified Reach Order=0
Composite Channel Slope=5