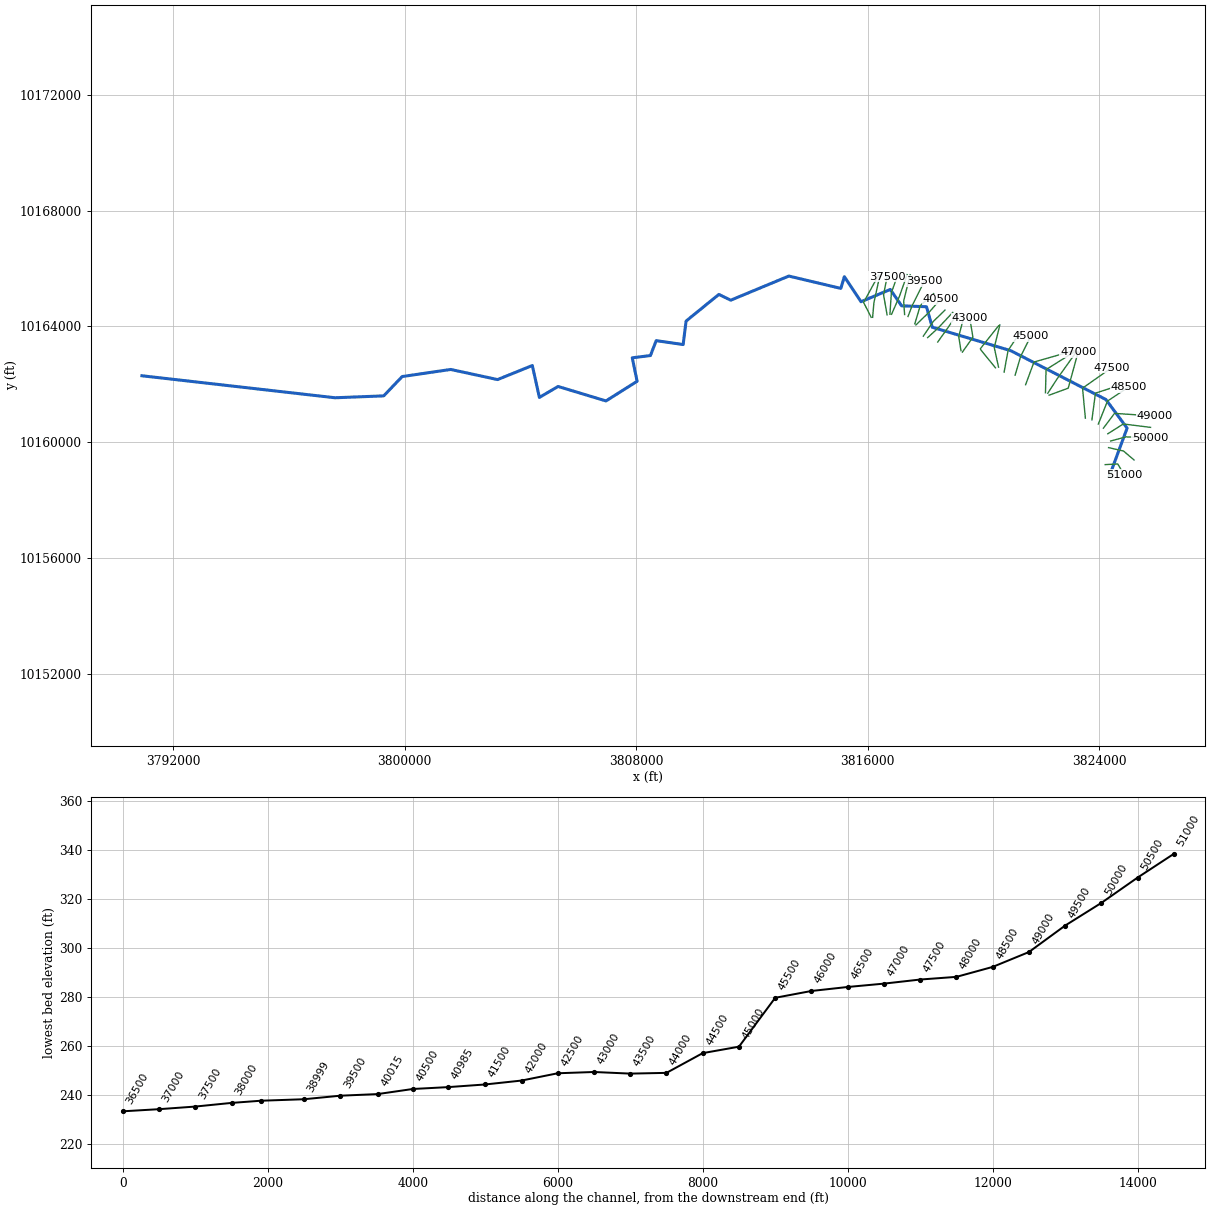
--- WEIRS CREEK.prj (project) ---

Proj Title=WEIRS CREEK Base Level Engineering
Current Plan=p01
Default Exp/Contr=0.3,0.1
English Units
Geom File=g01
Flow File=f01
Plan File=p01
Y Axis Title=Elevation
X Axis Title(PF)=Main Channel Distance
X Axis Title(XS)=Station
BEGIN DESCRIPTION:
WEIRS CREEK
END DESCRIPTION:
DSS Export Rating Curves= 0
DSS Export Rating Curve Sorted= 0
DSS Export Volume Flow Curves= 0
DXF OffsetX= 0
DXF OffsetY= 0
DXF ScaleX= 1
DXF ScaleY= 10

--- WEIRS CREEK.p01 (plan) ---

Plan Title=Multiple Run
Short Identifier=Multiple
Geom File=g01
Flow File=f01
Subcritical Flow
K Sum by GR= 0
Std Step Tol= 0.01
Critical Tol= 0.01
Num of Std Step Trials= 20
Max Error Tol= 0.3
Flow Tol Ratio= 0.001
Split Flow NTrial= 30
Split Flow Tol= 0.02
Split Flow Ratio= 0.02
Log Output Level= 0
Friction Slope Method= 1
Unsteady Friction Slope Method= 2
Unsteady Bridges Friction Slope Method= 1
Parabolic Critical Depth
Global Vel Dist=  1 , 1 , 1
Global Log Level= 0
CheckData=True
Encroach Param= -1, 0, 0, 0
BEGIN DESCRIPTION:
Multiple Run
END DESCRIPTION:

--- WEIRS CREEK.f01 (steady flow) ---

Flow Title=Multiple
Program Version=4.10
Number of Profiles= 7
Profile Names=10-year,25-year,50-year,1pct_min,100-year,1pct_plu,500-year
River Rch & RM=WEIRS CREEK,Reach-1         ,51000
     325     425     562     246     744    2247    1336
River Rch & RM=WEIRS CREEK,Reach-1         ,49500
    1405    2009    2819    1300    3926   11856    7876
River Rch & RM=WEIRS CREEK,Reach-1         ,45000
    1522    2190    3085    1429    4316   13034    8732
River Rch & RM=WEIRS CREEK,Reach-1         ,43000
    1664    2377    3332    1532    4628   13976    9240
River Rch & RM=WEIRS CREEK,Reach-1         ,38000
    1505    2121    2943    1340    4047   12222    7912
River Rch & RM=WEIRS CREEK,Reach-1         ,33515
    1750    2484    3463    1583    4781   14438    9434
River Rch & RM=WEIRS CREEK,Reach-1         ,31450
    2447    3519    4952    2282    6891   20810   13810
River Rch & RM=WEIRS CREEK,Reach-1         ,29500
    2823    4048    5683    2610    7882   23803   15692
River Rch & RM=WEIRS CREEK,Reach-1         ,28500
    2823    4048    5683    2610    7882   23803   15692
River Rch & RM=WEIRS CREEK,Reach-1         ,28041
    2823    4048    5683    2610    7882   23803   15692
River Rch & RM=WEIRS CREEK,Reach-1         ,24743
    2922    4178    5851    2679    8090   24431   16008
River Rch & RM=WEIRS CREEK,Reach-1         ,24408
    2922    4178    5851    2679    8090   24431   16008
River Rch & RM=WEIRS CREEK,Reach-1         ,23503
    2922    4178    5851    2679    8090   24431   16008
River Rch & RM=WEIRS CREEK,Reach-1         ,22832
    2922    4178    5851    2679    8090   24431   16008
River Rch & RM=WEIRS CREEK,Reach-1         ,21665
    2922    4178    5851    2679    8090   24431   16008
River Rch & RM=WEIRS CREEK,Reach-1         ,20616
    2922    4178    5851    2679    8090   24431   16008
River Rch & RM=WEIRS CREEK,Reach-1         ,13910
    3452    4969    6993    3216    9711   29327   19390
River Rch & RM=WEIRS CREEK,Reach-1         ,10500
    3726    5369    7560    3478   10503   31719   20981
River Rch & RM=WEIRS CREEK,Reach-1         ,7500
    3627    5199    7292    3341   10089   30468   19993
River Rch & RM=WEIRS CREEK,Reach-1         ,2500
    3382    4801    6688    3043    9190   27753   17952
Boundary for River Rch & Prof#=WEIRS CREEK,Reach-1         , 1
Up Type= 0
Dn Type= 3
Dn Slope=0.005
Boundary for River Rch & Prof#=WEIRS CREEK,Reach-1         , 2
Up Type= 0
Dn Type= 3
Dn Slope=0.005
Boundary for River Rch & Prof#=WEIRS CREEK,Reach-1         , 3
Up Type= 0
Dn Type= 3
Dn Slope=0.005
Boundary for River Rch & Prof#=WEIRS CREEK,Reach-1         , 4
Up Type= 0
Dn Type= 3
Dn Slope=0.005
Boundary for River Rch & Prof#=WEIRS CREEK,Reach-1         , 5
Up Type= 0
Dn Type= 3
Dn Slope=0.005
Boundary for River Rch & Prof#=WEIRS CREEK,Reach-1         , 6
Up Type= 0
Dn Type= 3
Dn Slope=0.005
Boundary for River Rch & Prof#=WEIRS CREEK,Reach-1         , 7
Up Type= 0
Dn Type= 3
Dn Slope=0.005
DSS Import GetInterval= 0
DSS Import GetPeak= 0
DSS Import FillOption= 0

--- WEIRS CREEK.g01 (geometry) ---

Geom Title=Existing Conditions
Program Version=4.10

River Reach=WEIRS CREEK     ,Reach-1
Reach XY= 30
      3824345.68     10158825.83      3824957.66     10160483.82
      3824224.15      10161473.4      3820938.67      10163159.6
      3818227.39     10163969.57      3818027.33     10164678.04
      3817168.32     10164708.83       3816778.3      10165274.8
       3815766.7     10164849.87      3815191.78      10165715.5
      3815069.37     10165311.06      3813271.91     10165737.13
      3811266.86     10164903.76      3810855.54     10165103.05
       3809723.5     10164181.46      3809622.94     10163371.79
      3808691.38     10163505.94      3808492.27     10162991.31
      3807865.36     10162914.41      3808032.17     10162102.43
       3806956.7     10161423.89      3805302.34     10161923.68
       3804657.4     10161544.94      3804412.61     10162647.37
      3803212.72     10162161.31      3801593.78     10162511.17
      3799917.49      10162266.2      3799279.75     10161598.64
      3797597.66     10161533.27      3790928.03     10162293.22

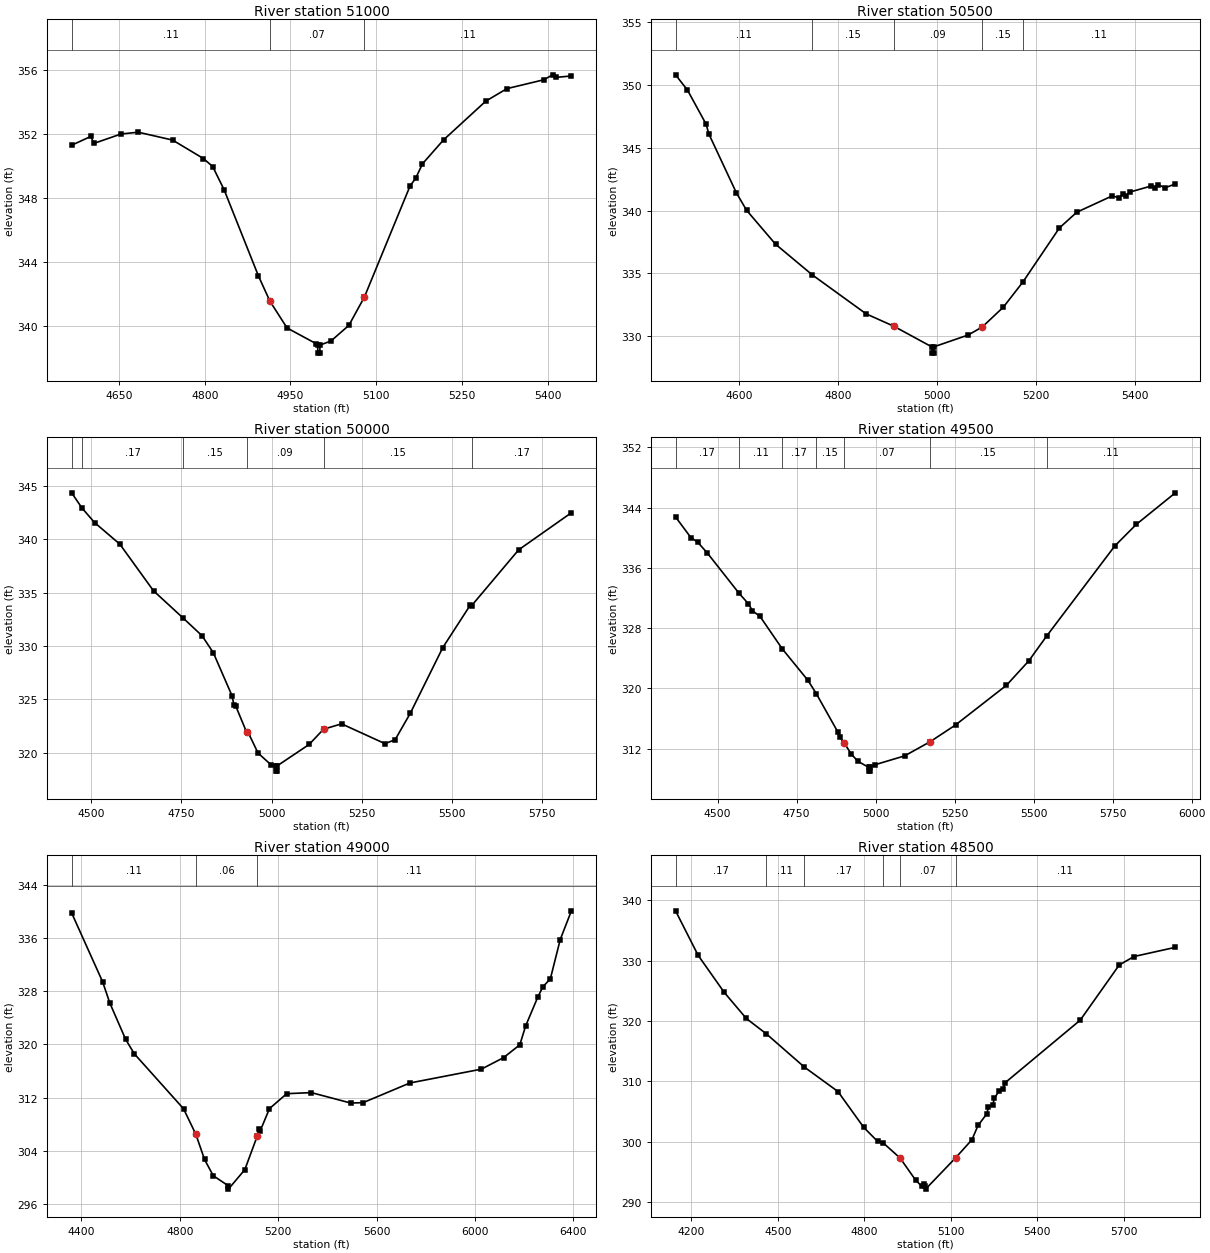
Type RM Length L Ch R = 1 ,51000   ,500,500,500
BEGIN DESCRIPTION:
WEIRS CREEK 92.0
END DESCRIPTION:
XS GIS Cut Line= 3
      3824201.52     10159224.21      3824633.74     10159246.61
      3824859.12     10158867.09
#Sta/Elev= 30
  4567.2   351.3  4600.9  351.85  4605.9  351.41  4653.7     352  4683.7  352.11
  4743.8  351.62  4797.6  350.47  4813.9  349.97  4833.9  348.52    4894  343.14
    4914  341.57    4944   339.9  4994.3  338.93  4997.6  338.83  4997.8  338.33
  5001.3  338.33  5001.6  338.83  5020.9  339.09  5052.1  340.06  5079.3  341.83
  5159.2  348.76    5169  349.24  5180.9  350.14  5217.7  351.63  5291.7  354.05
  5328.7  354.83    5393  355.38  5408.6  355.69  5414.4  355.53  5441.4  355.62
#Mann= 3 , 0 , 0
  4567.2     .11       0    4914     .07       0  5079.3     .11       0
Bank Sta=4914,5079.3
XS Rating Curve= 0 ,0
Exp/Cntr=0.3,0.1

Type RM Length L Ch R = 1 ,50500   ,500,500,500
BEGIN DESCRIPTION:
WEIRS CREEK 91.0
END DESCRIPTION:
XS GIS Cut Line= 3
      3824317.86     10159811.07      3824833.33     10159694.43
       3825199.3     10159382.92
#Sta/Elev= 30
  4471.5  350.82  4495.6   349.6    4533   346.9  4538.8   346.1  4594.5   341.4
    4615  340.02  4673.4  337.32  4747.8  334.87  4856.3  331.77  4912.4  330.78
  4988.9  329.14  4989.2  328.64  4992.7  328.64  4992.9  329.14  5062.1  330.08
  5090.7  330.72  5133.5  332.31  5172.7   334.3  5246.6  338.62  5281.7  339.87
  5353.1  341.17  5367.4  341.02    5374  341.29  5381.7   341.2  5388.3  341.47
  5431.1  341.95  5438.8  341.83  5445.4  342.07  5459.7  341.82  5480.6  342.12
#Mann= 5 ,-1 , 0
  4471.5     .11       0  4747.8     .15       0  4912.4     .09       0
  5090.7     .15       0  5172.7     .11       0
Bank Sta=4912.4,5090.7
XS Rating Curve= 0 ,0
Exp/Cntr=0.3,0.1

Type RM Length L Ch R = 1 ,50000   ,500,500,500
BEGIN DESCRIPTION:
WEIRS CREEK 90.0
END DESCRIPTION:
XS GIS Cut Line= 3
       3824388.6     10160040.55      3824924.35     10160182.74
      3825753.88     10160142.65
#Sta/Elev= 30
  4445.7  344.32  4474.3   342.9  4509.2  341.54  4579.2  339.52  4672.5  335.16
    4754  332.63    4807  330.96  4838.1  329.38  4889.8  325.37  4895.5  324.49
  4900.7  324.36  4930.5  321.94  4935.7  321.85  4962.2  319.99  4999.2  318.86
  5011.5   318.8  5011.8   318.3  5015.3   318.3  5015.5   318.8  5103.6  320.79
  5143.7  322.22  5193.7  322.72  5313.9  320.87  5342.1  321.24  5383.9   323.7
  5474.1  329.85  5550.8  333.85  5554.2  333.78  5684.3  338.99  5830.5  342.46
#Mann= 6 ,-1 , 0
  4445.7     .11       0  4474.3     .17       0    4754     .15       0
  4930.5     .09       0  5143.7     .15       0  5554.2     .17       0
#XS Ineff= 2 , 0
       0                  5193.7       0  322.72
Permanent Ineff=
       F       T
Bank Sta=4930.5,5143.7
XS Rating Curve= 0 ,0
Exp/Cntr=0.3,0.1

Type RM Length L Ch R = 1 ,49500   ,500,500,500
BEGIN DESCRIPTION:
WEIRS CREEK 89.0
END DESCRIPTION:
XS GIS Cut Line= 3
      3824292.25     10160290.01      3824826.86     10160628.59
      3825767.85     10160511.07
#Sta/Elev= 30
  4367.2  342.75  4415.6  340.02  4436.8  339.42  4467.3  337.99  4568.4  332.61
  4597.8  331.23  4610.6   330.3  4634.2  329.57  4705.1  325.24    4786  321.08
  4812.3  319.33    4880  314.27  4885.9  313.61  4901.2  312.77  4922.4  311.34
  4943.6  310.36    4978  309.54  4978.3  309.04  4981.8  309.04    4982  309.54
  4997.6  309.88  5091.7  311.06  5172.3  312.93  5252.9  315.16  5414.2  320.43
  5484.7  323.66    5541  326.94  5756.8   338.9  5824.8  341.76  5948.3  345.95
#Mann= 7 ,-1 , 0
  4367.2     .17       0  4568.4     .11       0  4705.1     .17       0
  4812.3     .15       0  4901.2     .07       0  5172.3     .15       0
    5541     .11       0
Bank Sta=4901.2,5172.3
XS Rating Curve= 0 ,0
Exp/Cntr=0.3,0.1

Type RM Length L Ch R = 1 ,49000   ,500,500,500
BEGIN DESCRIPTION:
WEIRS CREEK 88.0
END DESCRIPTION:
XS GIS Cut Line= 3
      3824139.14     10160482.71      3824523.59     10160994.24
      3825913.25     10160902.27
#Sta/Elev= 30
  4360.1  339.78  4486.1  329.42  4515.3  326.23  4579.8  320.75  4615.2  318.58
  4815.2  310.32  4865.2  306.48  4900.6  302.69    4936  300.25  4997.4  298.73
  4997.6  298.23  5064.4  301.16  5114.5  306.17  5121.6  307.25  5126.6  306.96
  5164.6  310.34  5234.8  312.59    5335  312.75  5495.3  311.18  5545.5  311.24
  5735.9   314.2  6026.5  316.28  6116.7  318.01  6182.8  319.94  6206.9  322.81
    6257  327.21    6277  328.68  6307.1  329.87  6347.2  335.77  6392.7   340.1
#Mann= 3 , 0 , 0
  4360.1     .11       0  4865.2     .06       0  5114.5     .11       0
Bank Sta=4865.2,5114.5
XS Rating Curve= 0 ,0
Exp/Cntr=0.3,0.1

Type RM Length L Ch R = 1 ,48500   ,500,500,500
BEGIN DESCRIPTION:
WEIRS CREEK 87.0
END DESCRIPTION:
XS GIS Cut Line= 3
      3823963.41     10160624.45      3824279.99     10161418.89
      3825012.24      10161905.7
#Sta/Elev= 30
  4144.8  338.26  4223.1  330.89  4313.4  324.77  4390.3  320.43  4459.9  317.88
    4592  312.37  4708.4  308.33  4797.8  302.39    4846  300.07  4866.4  299.78
  4924.1  297.31  4978.1  293.64  4998.5  292.68  5008.2  292.94  5012.2  292.66
  5012.5  292.16  5116.4  297.32  5173.5  300.35  5194.6  302.71  5224.7  304.61
  5230.7  305.71  5245.7  306.15  5251.7  307.22  5266.7  308.36  5281.8  308.72
  5287.8  309.75  5549.3  320.15  5684.6  329.28  5735.7  330.69  5879.3  332.21
#Mann= 6 ,-1 , 0
  4144.8     .17       0  4459.9     .11       0    4592     .17       0
  4866.4     .11       0  4924.1     .07       0  5116.4     .11       0
Bank Sta=4924.1,5116.4
XS Rating Curve= 0 ,0
Exp/Cntr=0.3,0.1

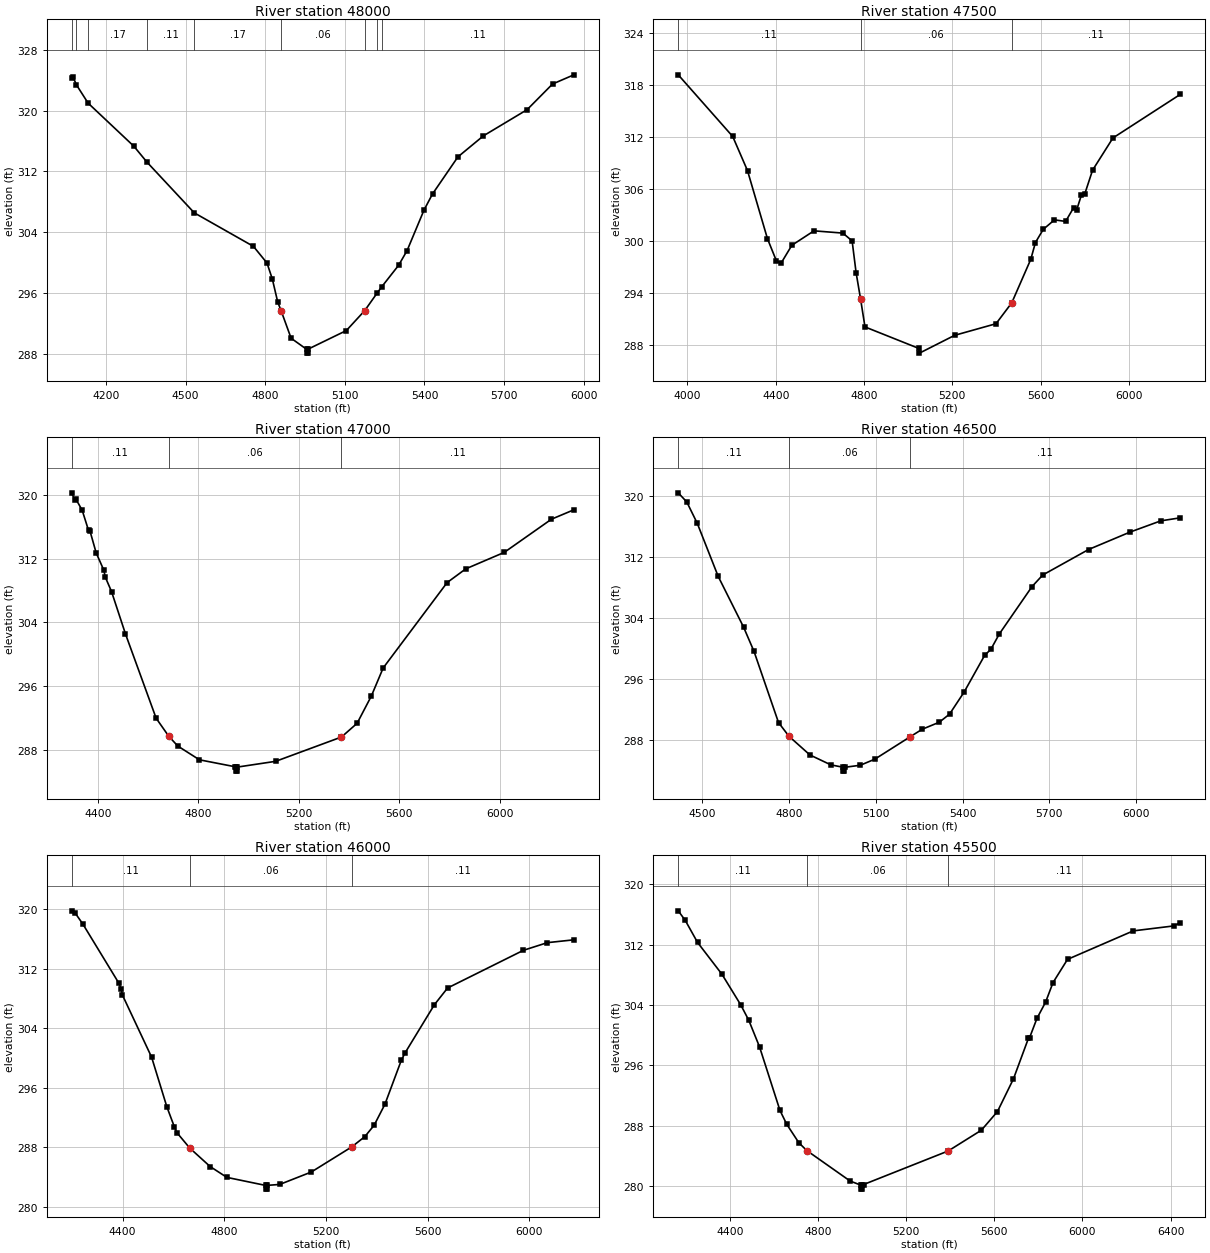
Type RM Length L Ch R = 1 ,48000   ,500,500,500
BEGIN DESCRIPTION:
WEIRS CREEK 86.0
END DESCRIPTION:
XS GIS Cut Line= 3
      3823742.34     10160771.91      3823864.41     10161692.65
       3824779.8     10161990.72
#Sta/Elev= 30
  4071.2  324.29  4075.3  324.47    4089  323.37  4132.7  320.98  4305.4   315.3
  4354.2  313.23  4532.7  306.55  4755.6  302.14  4806.7  299.95  4826.9  297.83
  4847.1  294.82  4859.8  293.68  4897.5  290.06  4956.1   288.6  4956.3   288.1
  4959.8   288.1  4960.1   288.6  5105.7  291.07  5174.8  293.69  5220.8  295.96
  5239.5  296.85  5302.5  299.65  5334.5  301.59  5398.3  306.92  5430.2  309.03
    5526  313.91  5621.8  316.67  5786.7  320.12  5882.4  323.49  5962.7   324.7
#Mann= 9 ,-1 , 0
  4071.2     .17       0    4089     .11       0  4132.7     .17       0
  4354.2     .11       0  4532.7     .17       0  4859.8     .06       0
  5174.8     .11       0  5220.8     .17       0  5239.5     .11       0
Bank Sta=4859.8,5174.8
XS Rating Curve= 0 ,0
Exp/Cntr=0.3,0.1

Type RM Length L Ch R = 1 ,47500   ,500,500,500
BEGIN DESCRIPTION:
WEIRS CREEK 85.0
END DESCRIPTION:
XS GIS Cut Line= 3
      3823515.57     10160828.52      3823419.04     10161865.94
      3824428.28     10162574.62
#Sta/Elev= 30
  3958.1  319.19    4205  312.06    4272  308.11  4362.4  300.24  4402.6   297.7
  4423.4  297.38  4472.9  299.48  4573.3  301.15  4703.9  300.89    4746  299.99
  4764.1  296.31  4784.2  293.29  4804.3  290.04  5046.9  287.57  5051.2  287.01
  5210.7  289.07  5398.1  290.41  5469.5  292.83  5555.8  297.87  5576.7   299.8
  5612.4  301.33    5663  302.42  5713.5  302.24  5749.3  303.81  5764.1  303.61
    5785  305.29  5799.8  305.38  5835.5  308.16  5927.9  311.89  6233.2  316.93
#Mann= 3 , 0 , 0
  3958.1     .11       0  4784.2     .06       0  5469.5     .11       0
Bank Sta=4784.2,5469.5
XS Rating Curve= 0 ,0
Exp/Cntr=0.3,0.1

Type RM Length L Ch R = 1 ,47000   ,500,500,500
BEGIN DESCRIPTION:
WEIRS CREEK 84.0
END DESCRIPTION:
XS GIS Cut Line= 3
      3822262.72     10161622.23      3822923.69     10161864.57
      3823266.13     10163113.17
#Sta/Elev= 30
    4296  320.25    4307  319.32  4312.3  319.47  4337.5  318.06  4362.7  315.54
    4368  315.52  4393.2  312.71  4423.7  310.54  4429.3  309.69  4454.2  307.87
  4509.8  302.55  4631.8  291.98  4682.2  289.71    4718  288.49  4804.2  286.76
    4946  285.89  4949.4  285.84  4949.6  285.34  4953.1  285.34  4953.4  285.84
  5107.7  286.57  5369.7  289.62  5431.9  291.34  5488.6  294.76  5535.6  298.28
  5790.2  308.99  5864.3  310.71  6017.7  312.78  6205.5  316.94  6294.7  318.12
#Mann= 3 , 0 , 0
    4296     .11       0  4682.2     .06       0  5369.7     .11       0
Bank Sta=4682.2,5369.7
XS Rating Curve= 0 ,0
Exp/Cntr=0.3,0.1

Type RM Length L Ch R = 1 ,46500   ,500,500,500
BEGIN DESCRIPTION:
WEIRS CREEK 83.0
END DESCRIPTION:
XS GIS Cut Line= 3
      3822217.36     10161690.26      3822535.15     10162179.27
      3823203.77     10163118.85
#Sta/Elev= 30
  4416.8   320.4  4446.4   319.2  4482.7   316.4  4555.1  309.45  4642.8  302.82
    4679  299.63  4763.6  290.33  4799.6  288.54  4872.1  286.09  4944.6  284.79
    4988  284.47  4988.3  283.97  4991.8  283.97    4992  284.47  5046.5  284.74
  5096.9  285.54  5218.6  288.46  5260.4  289.45  5319.5  290.37  5355.1  291.43
  5405.5  294.32  5476.9  299.15  5497.8   299.9  5527.3  301.93  5640.4  308.13
  5677.3  309.64  5835.9  312.98  5978.6  315.25  6085.5  316.73  6153.2  317.13
#Mann= 3 , 0 , 0
  4416.8     .11       0  4799.6     .06       0  5218.6     .11       0
Bank Sta=4799.6,5218.6
XS Rating Curve= 0 ,0
Exp/Cntr=0.3,0.1

Type RM Length L Ch R = 1 ,46000   ,500,500,500
BEGIN DESCRIPTION:
WEIRS CREEK 82.0
END DESCRIPTION:
XS GIS Cut Line= 3
      3822137.99     10161707.24      3822157.46      10162506.7
      3823152.79     10163130.21
#Sta/Elev= 30
  4200.3  319.77  4214.1  319.45  4244.1  317.98  4384.2  310.11  4394.2  309.32
  4399.7  308.43  4514.2  300.09  4574.2  293.41  4604.2  290.67  4614.3  289.91
  4664.3  287.86  4744.3  285.38  4810.1  283.92  4962.4  282.84  4962.6  282.34
  4966.1  282.34  4966.4  282.84  5017.9  282.97  5142.1  284.64  5300.8  288.01
  5352.6   289.4  5389.2  290.93  5431.6  293.75  5496.1  299.67  5510.6  300.65
  5626.1  307.14    5678  309.39  5976.2  314.46  6070.4  315.49  6174.5  315.87
#Mann= 3 , 0 , 0
  4200.3     .11       0  4664.3     .06       0  5300.8     .11       0
Bank Sta=4664.3,5300.8
XS Rating Curve= 0 ,0
Exp/Cntr=0.3,0.1

Type RM Length L Ch R = 1 ,45500   ,500,500,500
BEGIN DESCRIPTION:
WEIRS CREEK 81.0
END DESCRIPTION:
XS GIS Cut Line= 3
      3821452.05     10161985.08      3821741.15     10162767.58
      3823130.03     10163164.19
#Sta/Elev= 30
  4165.8  316.48  4197.9   315.2  4253.4  312.29  4364.1  308.07  4449.4  304.01
  4486.1  301.95  4534.7  298.44  4627.5     290  4657.9  288.18  4713.5   285.7
  4749.2  284.68  4946.1  280.63  4997.2  280.06  4997.4  279.56  5000.9  279.56
  5001.2  280.06    5007  280.17  5390.8  284.62  5541.7  287.38  5614.5  289.85
  5687.3   294.2  5754.9  299.55  5760.1  299.63  5793.9  302.22  5832.9  304.36
  5866.7  306.96  5932.5  310.04  6230.8  313.82  6415.5  314.48  6444.4  314.92
#Mann= 3 , 0 , 0
  4165.8     .11       0  4749.2     .06       0  5390.8     .11       0
Bank Sta=4749.2,5390.8
XS Rating Curve= 0 ,0
Exp/Cntr=0.3,0.1

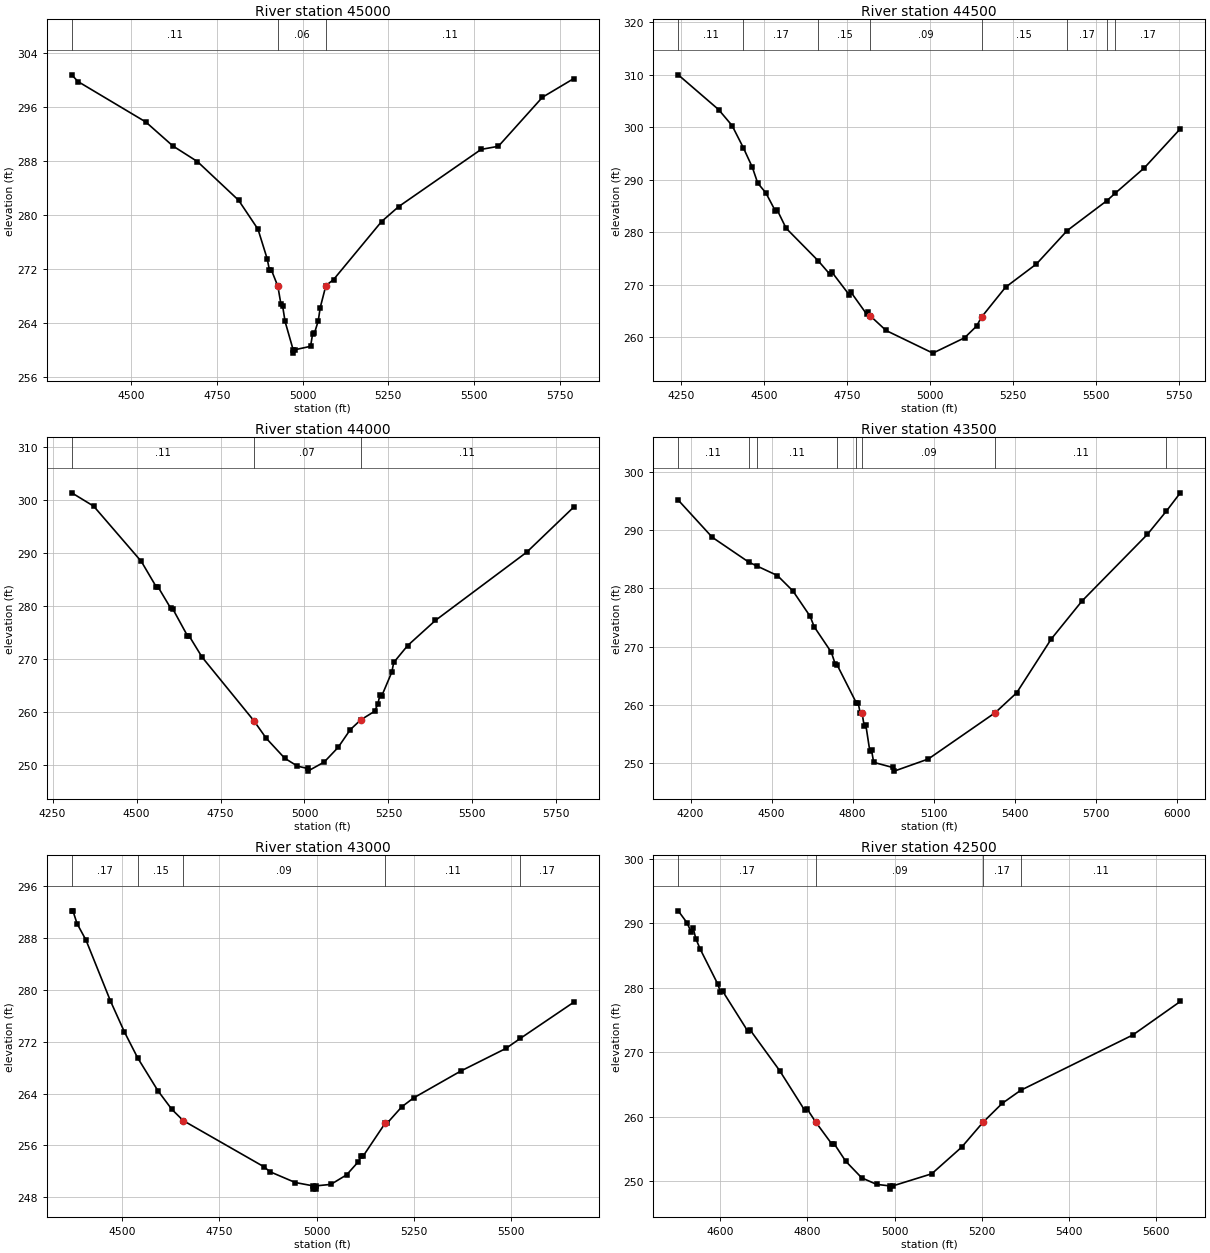
Type RM Length L Ch R = 1 ,45000   ,500,500,500
BEGIN DESCRIPTION:
WEIRS CREEK 80.0
END DESCRIPTION:
XS GIS Cut Line= 3
      3821089.21     10162313.84      3821279.98     10162960.48
      3821633.46     10163668.78
#Sta/Elev= 30
  4325.8   300.8  4343.8  299.81  4541.9  293.82  4620.7  290.28  4692.6  287.96
  4812.9  282.23  4869.5  277.94  4896.4  273.55  4902.8  271.91  4908.1  271.97
  4927.6  269.48  4936.2  266.91  4941.4  266.57  4948.5  264.29  4972.1   260.1
  4972.5   259.6  4977.3   260.1    5023  260.61  5028.7  262.38  5034.3  262.56
  5045.4  264.38  5051.1  266.33  5067.7   269.6  5090.1  270.49  5230.1  279.07
  5280.4   281.3  5520.9  289.76  5571.3  290.22  5699.9  297.48  5791.6  300.25
#Mann= 3 , 0 , 0
  4325.8     .11       0  4927.6     .06       0  5067.7     .11       0
Bank Sta=4927.6,5067.7
XS Rating Curve= 0 ,0
Exp/Cntr=0.3,0.1

Type RM Length L Ch R = 1 ,44500   ,500,500,500
BEGIN DESCRIPTION:
WEIRS CREEK 79.0
END DESCRIPTION:
XS GIS Cut Line= 3
      3820709.38     10162421.52      3820846.55     10163167.21
      3821262.86     10163795.98
#Sta/Elev= 30
  4241.8  309.95  4363.4  303.33    4404  300.29  4438.2  296.03    4465  292.35
  4481.2  289.34  4505.7  287.48  4534.2  284.05  4539.3  284.29  4566.7  280.75
    4664  274.51  4698.5  271.98  4703.6  272.47  4756.6  268.09  4761.7   268.6
  4809.7  264.36  4814.8  264.77  4820.9  264.02  4867.8  261.28  5008.8  256.97
  5104.3  259.89  5140.4  262.11  5155.4  263.83  5227.6  269.51  5320.9  273.95
  5413.4   280.3  5532.7  285.98  5557.5  287.38  5645.8  292.24  5754.1  299.68
#Mann= 8 ,-1 , 0
  4241.8     .11       0  4438.2     .17       0    4664     .15       0
  4820.9     .09       0  5155.4     .15       0  5413.4     .17       0
  5532.7     .15       0  5557.5     .17       0
Bank Sta=4820.9,5155.4
XS Rating Curve= 0 ,0
Exp/Cntr=0.3,0.1

Type RM Length L Ch R = 1 ,44000   ,500,500,500
BEGIN DESCRIPTION:
WEIRS CREEK 78.0
END DESCRIPTION:
XS GIS Cut Line= 3
      3820516.63     10162591.66      3820368.81     10163268.61
      3820561.67     10164047.28
#Sta/Elev= 30
  4307.1  301.37  4372.4  298.85  4514.3  288.43  4558.2   283.7  4563.3   283.7
  4602.1  279.58  4607.3  279.56  4651.2  274.47  4656.3  274.42  4695.1   270.4
    4849  258.44  4886.1  255.11  4941.1  251.35    4979  249.85  5009.6  249.41
    5010  248.91  5058.8  250.62  5100.2  253.38  5136.5  256.73  5167.4  258.56
  5208.6  260.18  5218.9  261.58  5224.4  263.27  5229.6     263  5260.1  267.57
  5265.8  269.39  5307.2  272.57    5390  277.32  5661.9  290.18  5802.2   298.7
#Mann= 3 , 0 , 0
  4307.1     .11       0    4849     .07       0  5167.4     .11       0
Bank Sta=4849,5167.4
XS Rating Curve= 0 ,0
Exp/Cntr=0.3,0.1

Type RM Length L Ch R = 1 ,43500   ,500,500,500
BEGIN DESCRIPTION:
WEIRS CREEK 77.0
END DESCRIPTION:
XS GIS Cut Line= 4
       3820410.8     10162566.54      3819899.65     10163193.97
      3819888.67     10163228.48      3820519.52     10164020.94
#Sta/Elev= 30
  4154.5  295.19  4280.4   288.8  4414.6  284.56  4444.6  283.89  4521.7  282.22
  4579.1  279.57    4643   275.2  4657.4  273.44  4721.3  269.03  4735.7  266.99
  4742.5  266.87  4813.5  260.36  4820.4  260.34  4828.3  258.55  4834.8  258.65
  4842.7  256.36  4849.1  256.46  4863.5  252.09    4870  252.22  4877.9  250.12
  4948.2  249.24  4953.9  248.61    5080  250.69  5328.5  258.68    5407  262.06
  5535.2  271.32  5648.9  277.84  5890.7  289.28  5961.7  293.32  6012.9  296.44
#Mann= 8 ,-1 , 0
  4154.5     .11       0  4414.6    .125       0  4444.6     .11       0
  4742.5     .15       0  4813.5     .11       0  4834.8     .09       0
  5328.5     .11       0  5961.7     .17       0
Bank Sta=4834.8,5328.5
XS Rating Curve= 0 ,0
Exp/Cntr=0.3,0.1

Type RM Length L Ch R = 1 ,43000   ,500,500,500
BEGIN DESCRIPTION:
WEIRS CREEK 76.0
END DESCRIPTION:
XS GIS Cut Line= 3
      3819267.87     10163111.09      3819631.78     10163624.87
      3819524.39     10164277.69
#Sta/Elev= 30
  4370.4  292.17  4373.4  292.17  4383.9  290.21  4407.1  287.64    4470  278.26
  4505.7  273.51  4539.8  269.51  4591.9  264.44  4627.7  261.57  4657.1  259.83
  4865.1   252.7  4879.8  251.96  4945.1  250.29  4991.2  249.77  4991.7  249.27
  4997.5  249.27    4998  249.77  5036.7     250  5077.2  251.47  5107.6  253.51
  5114.6  254.34  5119.7  254.36  5175.9  259.39  5180.9   259.4  5219.1  261.96
  5249.5  263.33  5371.1  267.48    5487  270.96  5523.6  272.49  5661.6  278.09
#Mann= 5 ,-1 , 0
  4370.4     .17       0  4539.8     .15       0  4657.1     .09       0
  5175.9     .11       0  5523.6     .17       0
Bank Sta=4657.1,5175.9
XS Rating Curve= 0 ,0
Exp/Cntr=0.3,0.1

Type RM Length L Ch R = 1 ,42500   ,500,500,500
BEGIN DESCRIPTION:
WEIRS CREEK 75.0
END DESCRIPTION:
XS GIS Cut Line= 3
      3819217.86     10163161.03      3819141.48     10163652.03
      3819308.83     10164286.73
#Sta/Elev= 30
  4503.1  291.95  4523.4  290.08  4532.1  288.74  4537.1  289.35  4543.6  287.61
  4553.7  285.99  4594.2  280.54    4600  279.33  4605.1  279.48  4662.9  273.27
    4668  273.48  4735.9  267.16  4793.7  260.98  4798.8  261.23  4819.2  259.13
  4856.6  255.69  4861.7  255.75  4887.7  253.09  4924.6   250.5  4958.6  249.49
  4989.1  249.25  4989.6  248.75  4995.9  249.25  5085.4  251.13  5154.1  255.26
  5203.4  259.14  5247.2  262.06  5289.8  264.09  5547.1  272.67  5656.4  277.88
#Mann= 4 ,-1 , 0
  4503.1     .17       0  4819.2     .09       0  5203.4     .17       0
  5289.8     .11       0
Bank Sta=4819.2,5203.4
XS Rating Curve= 0 ,0
Exp/Cntr=0.3,0.1

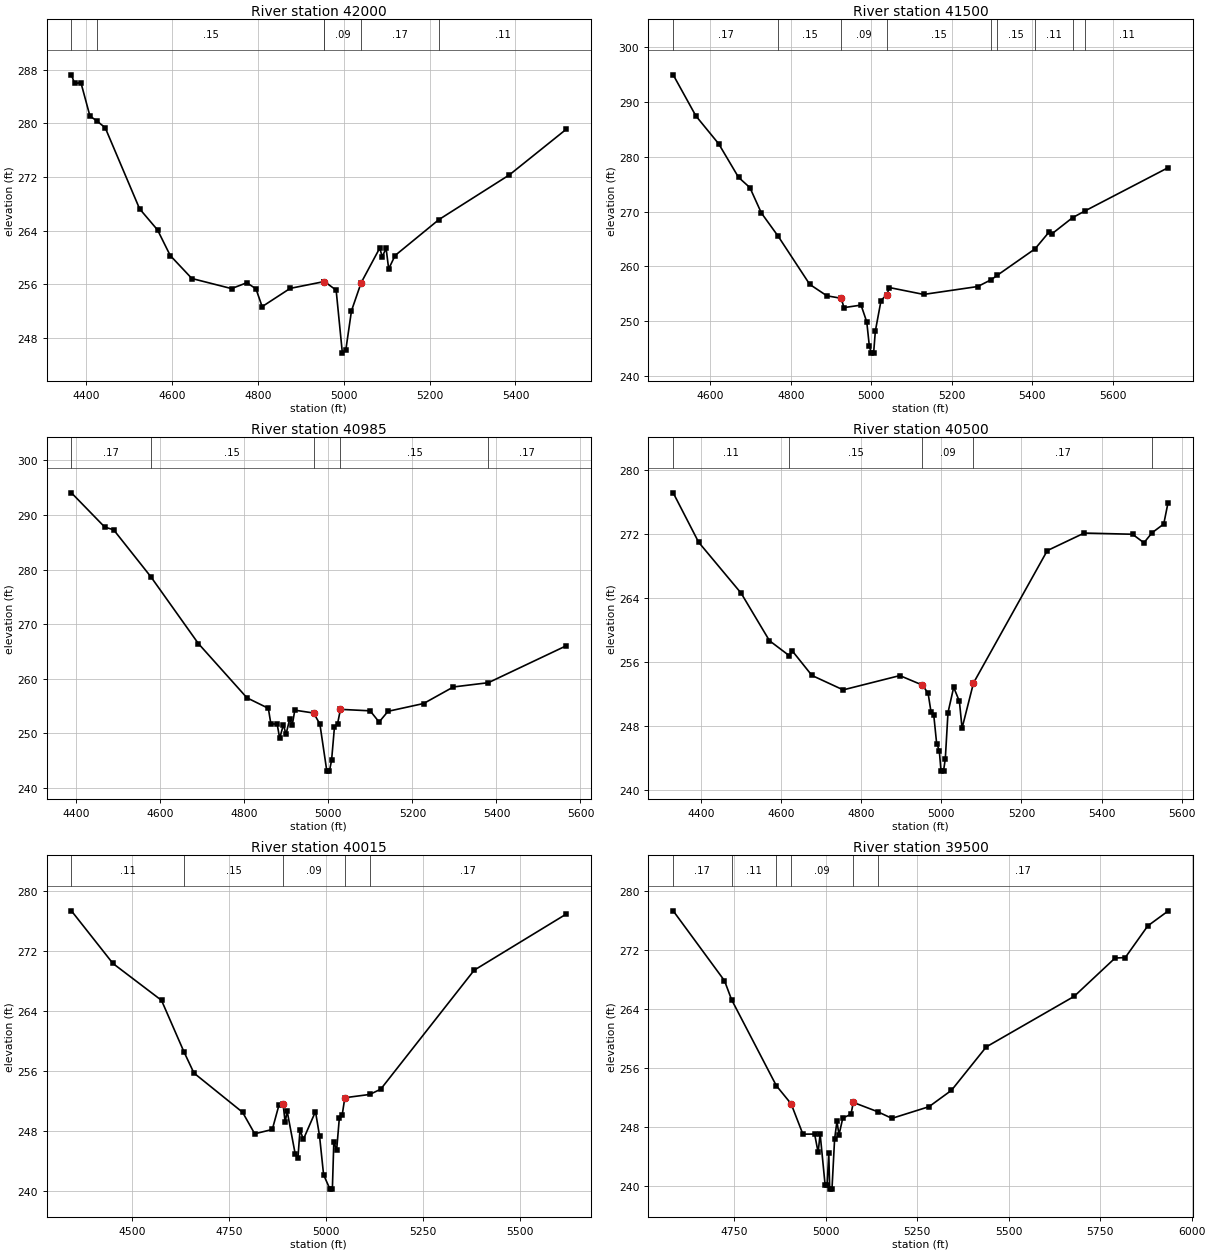
Type RM Length L Ch R = 1 ,42000   ,500,500,500
BEGIN DESCRIPTION:
WEIRS CREEK 74.0
END DESCRIPTION:
XS GIS Cut Line= 3
      3818417.83     10163461.05        3818785.     10163977.42
       3819077.7     10164405.16
#Sta/Elev= 30
  4366.4  287.25  4373.8  285.97  4388.6  286.07  4409.5  281.11  4426.4  280.34
  4445.1  279.36  4525.1  267.28  4566.9  264.13  4596.4  260.32  4646.8  256.89
  4739.1  255.39  4774.7  256.26  4795.9  255.36  4810.4   252.7  4875.6  255.42
  4954.3  256.43  4955.4  256.44  4982.6  255.16  4997.1  245.77  5005.2  246.27
  5018.3  252.08  5040.8  256.26    5084  261.42    5090  260.15  5098.9  261.39
  5104.9  258.32  5119.8  260.32    5222  265.68  5385.9  272.34  5518.3  279.14
#Mann= 6 ,-1 , 0
  4366.4     .17       0  4426.4     .15       0  4954.3     .17       0
  4955.4     .09       0  5040.8     .17       0    5222     .11       0
#XS Ineff= 2 , 0
       0                    5084       0  261.42
Permanent Ineff=
       F       F
Bank Sta=4955.4,5040.8
XS Rating Curve= 0 ,0
Exp/Cntr=0.3,0.1

Type RM Length L Ch R = 1 ,41500   ,515,515,515
BEGIN DESCRIPTION:
WEIRS CREEK 73.0
END DESCRIPTION:
XS GIS Cut Line= 3
      3818067.88      10163611.1      3818432.14     10163942.71
      3818935.66     10164482.27
#Sta/Elev= 30
  4507.4     295  4563.8   287.5  4620.5  282.41  4669.9  276.28  4698.2   274.4
  4726.6  269.78  4768.6  265.51  4846.9  256.74  4889.5  254.65  4925.3  254.19
    4932  252.49  4974.6  252.95  4988.8  249.87  4995.1  245.51  4999.8  244.18
  5005.8  244.18  5010.1  248.21  5024.3  253.79  5038.5  254.87  5045.3  256.15
  5130.3   254.9  5264.7  256.34  5298.3  257.59  5313.4   258.4  5407.2  263.22
  5441.5  266.24  5448.8  265.94  5500.4  268.91    5531  270.13    5738  278.04
#Mann= 9 ,-1 , 0
  4507.4     .17       0  4768.6     .15       0  4925.3     .09       0
  5038.5     .15       0  5298.3     .17       0  5313.4     .15       0
  5407.2     .11       0  5500.4     .17       0    5531     .11       0
Bank Sta=4925.3,5038.5
XS Rating Curve= 0 ,0
Exp/Cntr=0.3,0.1

Type RM Length L Ch R = 1 ,40985   ,485,485,485
BEGIN DESCRIPTION:
WEIRS CREEK 72.0
END DESCRIPTION:
XS GIS Cut Line= 3
      3817917.83     10163661.03      3818261.18     10164167.16
      3818667.87     10164561.09
#Sta/Elev= 30
  4388.4  294.04  4467.8  287.76  4488.8  287.28  4577.4  278.68  4690.5  266.45
  4806.2  256.51  4857.1  254.59  4863.1  251.75  4878.1  251.69  4884.1   249.1
    4893   251.6  4899.1  249.81    4908  252.65    4914  251.51  4920.1  254.25
  4964.9  253.73  4979.8   251.7  4996.3  243.09  5002.4  243.09  5007.6  245.07
  5014.5   251.2  5021.7  251.71  5028.7   254.4  5099.4  254.13  5120.7  252.08
  5141.9  254.04  5226.7  255.47  5297.5   258.5  5380.7  259.28  5566.2  266.04
#Mann= 5 ,-1 , 0
  4388.4     .17       0  4577.4     .15       0  4964.9     .09       0
  5028.7     .15       0  5380.7     .17       0
Bank Sta=4964.9,5028.7
XS Rating Curve= 0 ,0
Exp/Cntr=0.3,0.1

Type RM Length L Ch R = 1 ,40500   ,485,485,485
BEGIN DESCRIPTION:
WEIRS CREEK 71.0
END DESCRIPTION:
XS GIS Cut Line= 3
      3817661.26     10164047.98      3818142.28     10164513.07
       3818513.2     10164940.46
#Sta/Elev= 30
  4330.9   277.2  4394.4  271.01  4500.4  264.63  4571.2  258.67    4621  256.78
  4627.7  257.42  4677.1  254.32  4755.1  252.51  4896.5   254.3  4952.9  253.11
  4967.1  252.08  4974.3  249.76  4981.2  249.35  4988.4  245.79    4995  244.91
  4999.3  242.33  5005.5  242.33    5010  243.87  5016.7  249.66  5030.9  252.83
  5045.2  251.07  5051.8  247.71  5080.3  253.37  5264.5  269.96  5356.6  272.16
  5477.2  272.01  5505.7  270.94    5526   272.2  5555.1  273.29  5565.9  275.98
#Mann= 5 ,-1 , 0
  4330.9     .11       0    4621     .15       0  4952.9     .09       0
  5080.3     .17       0    5526     .11       0
Bank Sta=4952.9,5080.3
XS Rating Curve= 0 ,0
Exp/Cntr=0.3,0.1

Type RM Length L Ch R = 1 ,40015   ,515,515,515
BEGIN DESCRIPTION:
WEIRS CREEK 70.0
END DESCRIPTION:
XS GIS Cut Line= 3
      3817624.73     10164088.57       3817813.1     10164717.15
      3818273.49     10165131.06
#Sta/Elev= 30
  4343.8  277.37  4450.8  270.35    4576  265.43  4633.6  258.59  4659.6  255.73
  4784.9   250.5  4816.2  247.63  4861.5  248.21  4878.8  251.49  4889.3  251.63
  4894.6  249.16  4899.8  250.64  4920.6  244.92  4927.6  244.43  4932.9  248.16
  4941.5  246.88  4972.8   250.6  4983.2  247.36  4993.7  242.16  5010.1  240.25
  5016.3  240.25    5020  246.49  5027.4  245.52  5034.2  249.69  5041.6  250.13
  5048.4  252.44  5112.7  252.88  5140.9  253.58  5381.7  269.45  5619.1  276.94
#Mann= 5 ,-1 , 0
  4343.8     .11       0  4633.6     .15       0  4889.3     .09       0
  5048.4     .15       0  5112.7     .17       0
Bank Sta=4889.3,5048.4
XS Rating Curve= 0 ,0
Exp/Cntr=0.3,0.1

Type RM Length L Ch R = 1 ,39500   ,501,501,501
BEGIN DESCRIPTION:
WEIRS CREEK 69.0
END DESCRIPTION:
XS GIS Cut Line= 3
      3817389.35     10164340.22      3817538.74     10164729.33
      3817957.52     10165565.86
#Sta/Elev= 30
  4583.2   277.3  4723.4  267.83  4742.7  265.27    4865  253.61  4905.5  251.15
  4937.6  247.04  4969.7  247.05  4979.3  244.56  4984.7   247.1  4998.3  240.17
  5003.8  240.17  5008.4  244.45  5010.9  239.59  5017.1  239.59  5024.3  246.39
  5030.7  248.77  5036.3  246.94  5046.7  249.23    5069  249.73  5075.4  251.34
    5142  250.08  5180.9  249.18  5282.2  250.76  5343.7  252.98  5438.7  258.86
  5678.9  265.71  5790.7   270.9  5818.6  270.97  5880.1  275.26  5935.5  277.27
#Mann= 6 ,-1 , 0
  4583.2     .17       0  4742.7     .11       0    4865     .15       0
  4905.5     .09       0  5075.4     .15       0    5142     .17       0
Bank Sta=4905.5,5075.4
XS Rating Curve= 0 ,0
Exp/Cntr=0.3,0.1

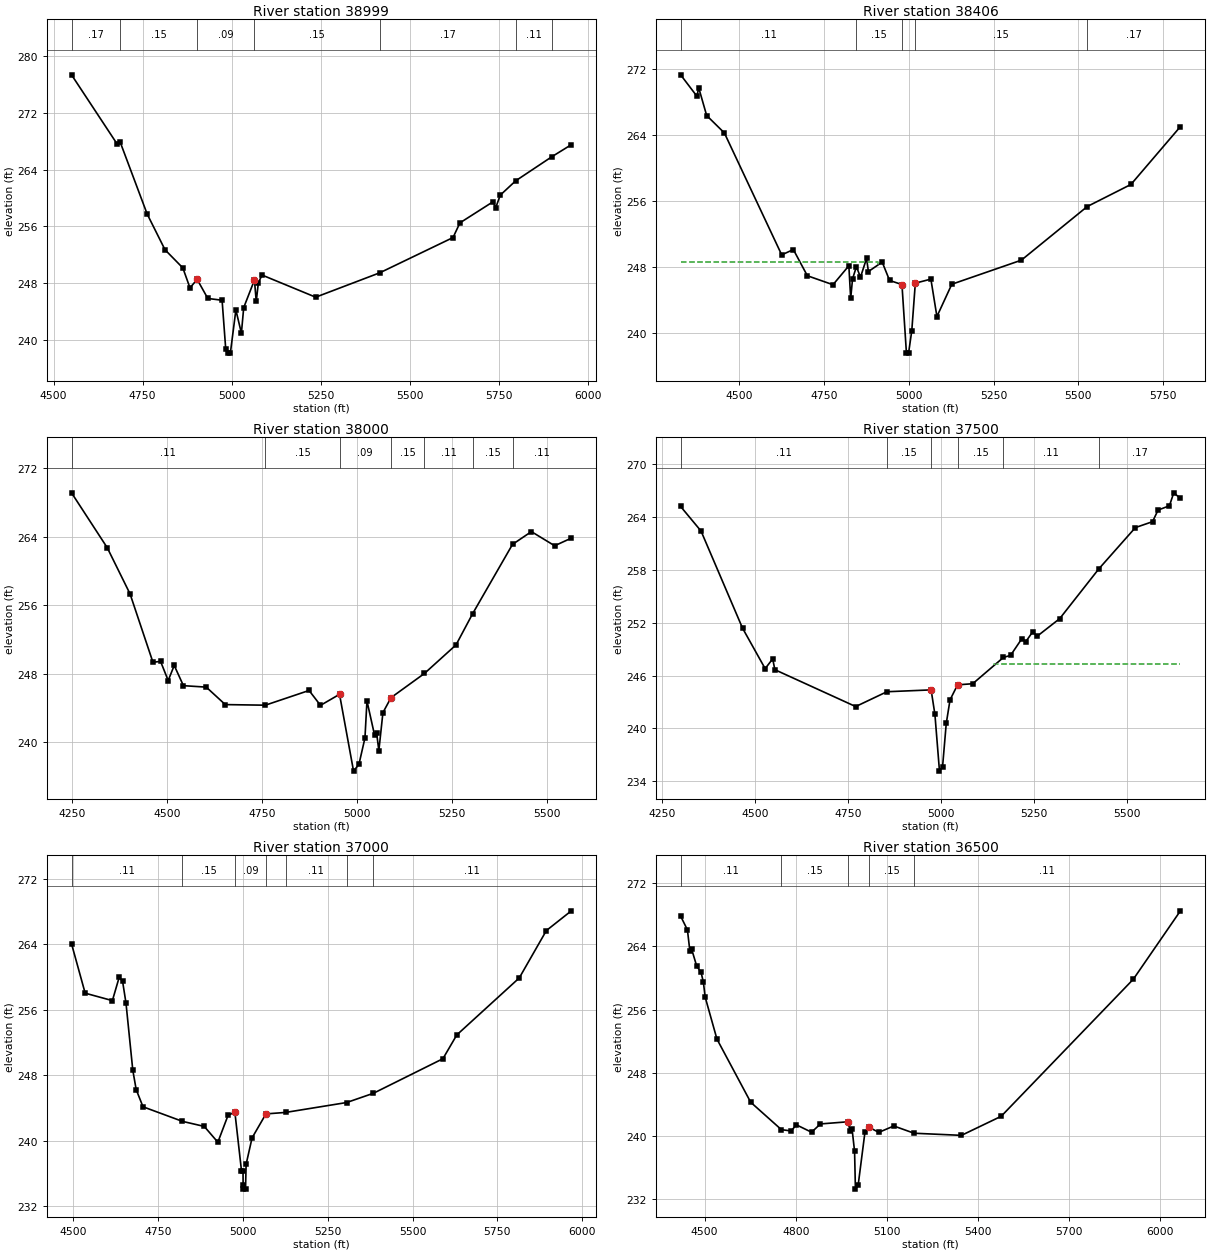
Type RM Length L Ch R = 1 ,38999   ,593,593,593
BEGIN DESCRIPTION:
WEIRS CREEK 68.0
END DESCRIPTION:
XS GIS Cut Line= 3
      3817271.64     10164409.19      3817240.35     10164873.23
      3817462.38     10165784.99
#Sta/Elev= 30
  4550.2  277.35  4679.1  267.54    4687  267.85  4762.6  257.74  4812.7  252.71
  4862.8  250.15  4882.8  247.34  4902.9  248.54  4932.9  245.85    4973   245.6
  4983.1  238.79  4989.9  238.15  4996.2  238.15  5011.7  244.23  5027.2  240.96
  5033.7  244.56  5063.8  248.44  5068.9  245.43  5074.8  248.05  5085.1  249.15
  5235.8  246.03    5416  249.47  5621.5  254.43  5640.9   256.5  5733.5  259.46
  5741.5  258.65  5754.1   260.4  5797.4  262.42  5899.5  265.83  5953.7  267.51
#Mann= 7 ,-1 , 0
  4550.2     .17       0    4687     .15       0  4902.9     .09       0
  5063.8     .15       0    5416     .17       0  5797.4     .11       0
  5899.5     .17       0
Bank Sta=4902.9,5063.8
XS Rating Curve= 0 ,0
Exp/Cntr=0.3,0.1

Type RM Length L Ch R = 1 ,38406   ,406,406,406
BEGIN DESCRIPTION:
WEIRS CREEK 67.0
END DESCRIPTION:
XS GIS Cut Line= 3
      3816821.66     10164416.64      3817091.52     10165032.84
      3817360.39     10165787.58
#Sta/Elev= 30
  4327.3  271.31  4375.2  268.72  4380.7  269.73  4404.1  266.37  4456.3  264.26
  4625.4  249.46  4659.7  250.11    4701  246.93  4776.6  245.84  4823.4  248.14
  4828.8  244.18  4834.3  246.55  4845.7  248.03  4857.7  246.75  4875.6  249.03
  4881.1  247.44  4921.7  248.59  4943.5  246.36    4980  245.86  4993.2  237.54
  4999.5  237.54    5009  240.27  5019.4  246.03  5065.3  246.52  5083.1  241.98
    5127   245.9  5332.1  248.82  5526.5  255.33  5655.3  258.01  5801.2  265.03
#Mann= 5 ,-1 , 0
  4327.3     .11       0  4845.7     .15       0    4980     .09       0
  5019.4     .15       0  5526.5     .17       0
#XS Ineff= 2 , 0
       0  4910.7  248.62               0
Permanent Ineff=
       F       F
Bank Sta=4980,5019.4
XS Rating Curve= 0 ,0
Exp/Cntr=0.3,0.1

Type RM Length L Ch R = 1 ,38000   ,500,500,500
BEGIN DESCRIPTION:
WEIRS CREEK 66.0
END DESCRIPTION:
XS GIS Cut Line= 3
      3816764.32      10164417.3      3816815.68     10165167.44
      3817007.84     10165697.27
#Sta/Elev= 30
  4248.1  269.15  4342.1  262.74  4402.2  257.34  4462.4  249.36  4482.4  249.47
  4502.5  247.23  4518.4  248.99  4542.6  246.63  4602.7  246.46  4652.8  244.42
  4758.2  244.35  4873.3  246.07  4903.4  244.33  4953.5  245.62  4990.4  236.65
  5004.6  237.45  5020.4  240.52  5025.7  244.85  5045.7  240.85    5051  241.14
    5057  239.04  5067.7  243.48    5089  245.23  5177.1  248.06  5260.1  251.39
  5303.5  255.01  5408.8  263.13  5458.5  264.62  5519.7  262.97  5563.6  263.86
#Mann= 7 ,-1 , 0
  4248.1     .11       0  4758.2     .15       0  4953.5     .09       0
    5089     .15       0  5177.1     .11       0  5303.5     .15       0
  5408.8     .11       0
#XS Ineff= 2 , 0
       0  4518.4  248.99               0
Permanent Ineff=
       F       F
Bank Sta=4953.5,5089
XS Rating Curve= 0 ,0
Exp/Cntr=0.3,0.1

Type RM Length L Ch R = 1 ,37500   ,500,500,500
BEGIN DESCRIPTION:
WEIRS CREEK 65.0
END DESCRIPTION:
XS GIS Cut Line= 3
      3816666.91     10164397.03      3816545.62     10165086.65
      3816666.92     10165720.14
#Sta/Elev= 30
  4299.8  265.16  4354.7  262.38  4466.4  251.37  4527.3  246.78  4547.6  247.89
  4553.4  246.66    4771  242.48    4855  244.16    4974  244.37  4984.2  241.59
  4996.5  235.16  5004.8  235.66  5014.7  240.56  5024.9  243.24  5045.2  244.94
    5086  245.07  5168.6  248.05  5187.8  248.28  5218.3  250.18  5228.5  249.82
  5247.5  250.96    5259  250.44  5320.1  252.45  5425.2  258.08  5523.8  262.77
  5569.9  263.44  5584.9  264.76  5615.4  265.24    5627  266.71    5645  266.08
#Mann= 6 ,-1 , 0
  4299.8     .11       0    4855     .15       0    4974     .09       0
  5045.2     .15       0  5168.6     .11       0  5425.2     .17       0
#XS Ineff= 2 , 0
       0  4547.6  247.89  5143.4       0  247.28
Permanent Ineff=
       F       F
Bank Sta=4974,5045.2
XS Rating Curve= 0 ,0
Exp/Cntr=0.3,0.1

Type RM Length L Ch R = 1 ,37000   ,500,500,500
BEGIN DESCRIPTION:
WEIRS CREEK 64.0
END DESCRIPTION:
XS GIS Cut Line= 3
      3816167.85     10164311.07      3816211.36     10164814.99
      3816417.86     10165761.12
#Sta/Elev= 30
  4494.2  264.06  4534.4  258.03  4614.7  257.12  4634.7  259.96  4644.8  259.47
  4654.8  256.83  4674.9  248.62  4684.9  246.25    4705  244.15  4821.3  242.37
  4885.7  241.75  4925.8  239.82  4955.9  243.11    4976  243.49  4995.5  236.34
    5000  236.34  5000.3  234.59  5000.8  234.09  5007.4  234.09  5009.2  237.13
  5026.7  240.35  5067.6  243.28  5125.5  243.46  5305.7  244.67  5384.6   245.8
  5589.6  250.02  5630.6  252.93  5814.8  259.89  5894.8  265.68  5968.4  268.09
#Mann= 7 ,-1 , 0
  4494.2     .11       0  4821.3     .15       0    4976     .09       0
  5067.6     .15       0  5125.5     .11       0  5305.7     .15       0
  5384.6     .11       0
Bank Sta=4976,5067.6
XS Rating Curve= 0 ,0
Exp/Cntr=0.3,0.1

Type RM Length L Ch R = 1 ,36500   ,500,500,500
BEGIN DESCRIPTION:
WEIRS CREEK 63.0
END DESCRIPTION:
XS GIS Cut Line= 3
      3816117.85     10164311.08      3815854.89     10164826.92
      3816367.84     10165761.05
#Sta/Elev= 30
    4421  267.85  4443.4   266.1  4451.5  263.38  4457.1  263.68  4473.8  261.52
  4488.3  260.71    4496  259.44  4501.6   257.6  4540.5  252.25  4651.6  244.24
  4752.7  240.76    4785   240.6  4801.7  241.38  4851.7  240.44  4881.2  241.49
    4971  241.76  4979.5  240.56  4985.1  240.86  4993.4  238.01  4996.2  233.22
  5005.2  233.72  5027.6  240.46    5041  241.06  5073.2  240.42  5122.5  241.23
  5189.2  240.31  5345.1  240.04  5475.9  242.46  5910.8  259.85  6065.7  268.52
#Mann= 5 ,-1 , 0
    4421     .11       0  4752.7     .15       0    4971     .09       0
    5041     .15       0  5189.2     .11       0
Bank Sta=4971,5041
XS Rating Curve= 0 ,0
Exp/Cntr=0.3,0.1