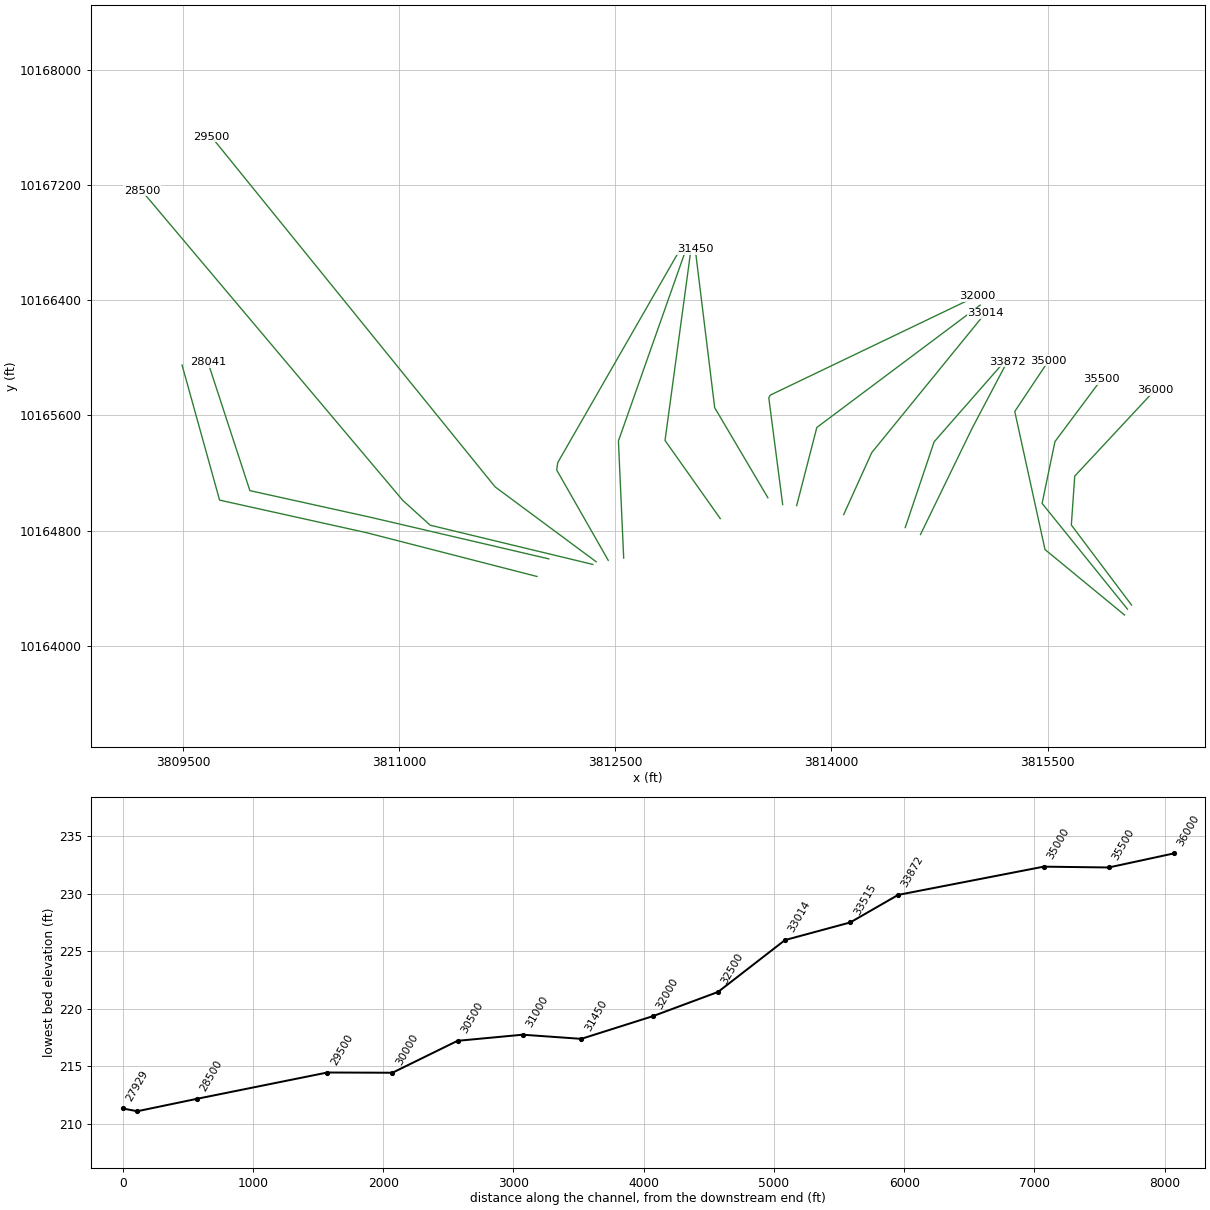
HEC-RAS study WEIRS CREEK.prj: WEIRS CREEK Base Level Engineering

--- WEIRS CREEK.g01 (geometry) --- (continued)

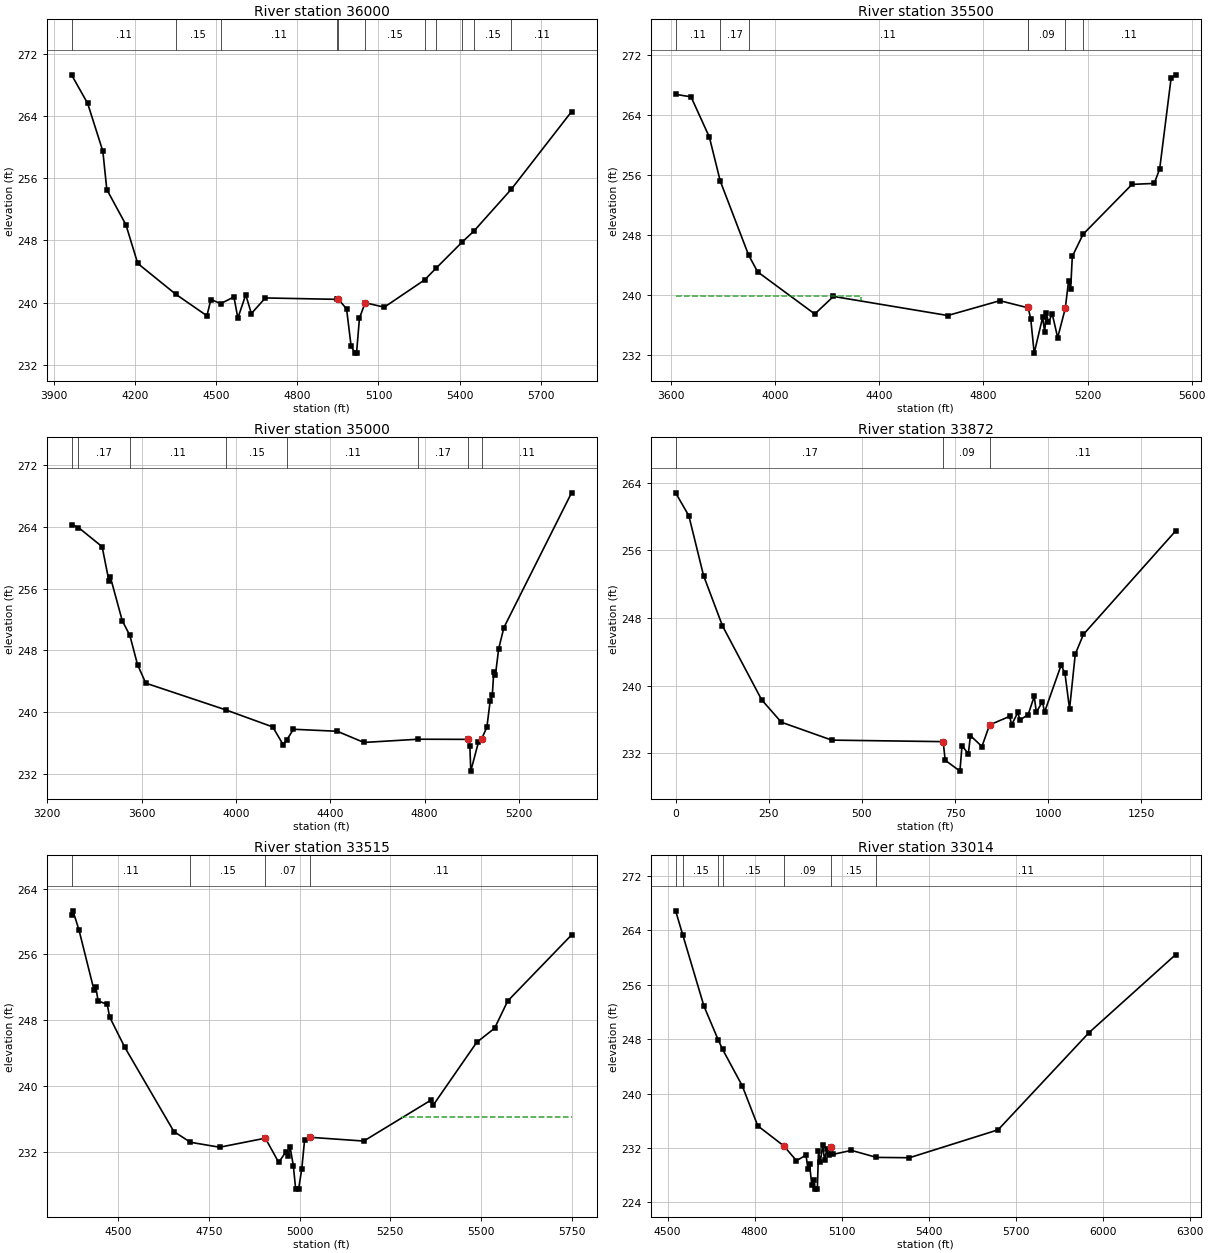
Type RM Length L Ch R = 1 ,36000   ,500,500,500
BEGIN DESCRIPTION:
WEIRS CREEK 62.0
END DESCRIPTION:
XS GIS Cut Line= 4
      3816082.48     10164283.38      3815664.46     10164839.39
      3815688.17     10165179.25      3816243.43     10165775.41
#Sta/Elev= 30
  3963.7  269.34  4023.4  265.65  4079.6   259.5  4094.2  254.56    4165  250.02
  4208.7  245.04  4349.1  241.08  4464.9  238.29  4479.5  240.39  4515.9  239.86
  4564.9  240.72  4579.4  237.99  4608.6     241  4629.4  238.58  4681.1  240.59
  4945.5  240.41  4951.7  240.42  4981.8  239.18  4998.4  234.45  5012.1  233.48
  5018.7  233.48  5029.6     238  5050.6  239.97  5121.5   239.4  5270.4  242.91
  5313.9  244.45  5409.7  247.79    5453   249.2  5592.1  254.62  5814.7   264.6
#Mann= 11 ,-1 , 0
  3963.7     .11       0  4349.1     .15       0  4515.9     .11       0
  4945.5     .15       0  4951.7     .09       0  5050.6     .15       0
  5270.4     .11       0  5313.9     .15       0  5409.7     .11       0
    5453     .15       0  5592.1     .11       0
Bank Sta=4951.7,5050.6
XS Rating Curve= 0 ,0
Exp/Cntr=0.3,0.1

Type RM Length L Ch R = 1 ,35500   ,500,500,500
BEGIN DESCRIPTION:
WEIRS CREEK 61.0
END DESCRIPTION:
XS GIS Cut Line= 4
      3816054.05       10164255.      3815461.53     10164989.56
      3815550.92     10165419.01      3815872.84     10165850.69
#Sta/Elev= 30
  3617.6  266.72  3676.8  266.39  3747.2  261.03  3788.9  255.19  3897.8  245.33
  3932.7  243.08  4152.2  237.47  4223.8  239.81    4663  237.27  4863.2  239.24
  4969.9  238.31  4971.5  238.35  4981.7  236.85  4995.1  232.26  5027.5  237.02
  5035.2   235.1  5041.5  237.64  5049.8  236.34  5064.4  237.49  5085.3  234.32
  5114.5  238.21  5127.3   241.9  5135.3  240.85  5141.5  245.14  5182.9  248.09
  5370.9  254.73  5456.4  254.86  5477.2   256.8    5521  268.86  5538.5  269.32
#Mann= 7 ,-1 , 0
  3617.6     .11       0  3788.9     .17       0  3897.8     .11       0
  4969.9     .15       0  4971.5     .09       0  5114.5     .15       0
  5182.9     .11       0
#XS Ineff= 2 , 0
       0  4330.9  239.87               0
Permanent Ineff=
       F       F
Bank Sta=4971.5,5114.5
XS Rating Curve= 0 ,0
Exp/Cntr=0.3,0.1

Type RM Length L Ch R = 1 ,35000   ,1117,1117,1117
BEGIN DESCRIPTION:
WEIRS CREEK 60.0
END DESCRIPTION:
XS GIS Cut Line= 4
      3816033.81     10164214.36      3815481.83     10164668.93
      3815271.86     10165627.84       3815506.2     10165979.88
#Sta/Elev= 30
  3303.3  264.31  3332.7  263.93    3433  261.44  3461.7  257.01  3468.1  257.48
  3518.3  251.84  3550.5  249.93  3582.9  246.15    3618  243.74  3958.6  240.26
  4156.3  238.06  4200.1  235.77  4215.3  236.36    4244  237.76  4429.6   237.5
  4542.6  236.05  4773.6  236.47  4982.8  236.45  4991.7  235.61  4995.7  232.33
  5027.9  236.06  5041.9  236.54  5063.9  238.02    5078  241.47    5087  242.22
    5093  245.13    5100  244.77    5114   248.2    5136  250.95  5422.9  268.43
#Mann= 8 ,-1 , 0
  3303.3     .11       0  3332.7     .17       0  3550.5     .11       0
  3958.6     .15       0  4215.3     .11       0  4773.6     .17       0
  4982.8     .09       0  5041.9     .11       0
Bank Sta=4982.8,5041.9
XS Rating Curve= 0 ,0
Exp/Cntr=0.3,0.1

Type RM Length L Ch R = 1 ,33872   ,368,368,368
XS GIS Cut Line= 3
      3814617.69     10164773.48      3814975.23      10165509.9
      3815219.22     10165972.91
#Sta/Elev= 30
       0  262.82    35.5   260.1      75  253.02   125.7  247.08   230.8  238.33
   283.7  235.67   419.1  233.55     718  233.37   723.5  231.17   763.1  229.88
   768.6  232.88   785.7  231.94   791.2  234.09   822.1  232.79   842.6  235.35
   896.4  236.36     902  235.38   918.4  236.82   924.1  235.93   946.1  236.57
   962.5  238.72   968.1  236.85   984.5   238.1   990.1  236.86  1034.7  242.43
  1044.9  241.46  1057.3  237.23  1072.6  243.73  1094.6  246.07    1342  258.31
#Mann= 3 , 0 , 0
       0     .17       0     718     .09       0   842.6     .11       0
Bank Sta=718,842.6
XS Rating Curve= 0 ,0
Exp/Cntr=0.3,0.1

Type RM Length L Ch R = 1 ,33515   ,501,501,501
BEGIN DESCRIPTION:
WEIRS CREEK 59.0
END DESCRIPTION:
XS GIS Cut Line= 3
      3814511.81     10164821.73      3814712.22     10165417.31
      3815206.27     10165981.47
#Sta/Elev= 30
  4371.6  260.84  4375.5   261.3    4392  258.99  4433.3  251.71  4438.5  252.04
  4444.8  250.35    4470  249.94  4476.4  248.42  4518.6   244.7  4653.8  234.48
  4699.5  233.18  4779.8  232.58  4905.8  233.68  4942.6  230.74  4961.8  231.97
  4968.8  231.46  4974.1  232.59  4982.9  230.36  4989.4  227.49  4997.4  227.49
  5006.3  229.97  5013.9  233.41  5028.1  233.79  5177.1  233.33  5361.2  238.27
  5367.9  237.65  5488.4  245.32  5537.8  247.04  5573.8  250.34  5749.9  258.37
#Mann= 4 ,-1 , 0
  4371.6     .11       0  4699.5     .15       0  4905.8     .07       0
  5028.1     .11       0
#XS Ineff= 2 , 0
       0                  5283.4       0   236.2
Permanent Ineff=
       F       F
Bank Sta=4905.8,5028.1
XS Rating Curve= 0 ,0
Exp/Cntr=0.3,0.1

Type RM Length L Ch R = 1 ,33014   ,514,514,514
BEGIN DESCRIPTION:
WEIRS CREEK 58.0
END DESCRIPTION:
XS GIS Cut Line= 3
      3814084.74     10164912.05      3814279.35     10165342.17
      3815067.85     10166311.07
#Sta/Elev= 30
  4527.9  266.83  4552.1  263.35  4625.7   252.8  4674.2  247.91  4689.6  246.48
  4757.3  241.13  4810.6  235.26    4900  232.32  4943.9  230.14  4976.8  230.96
  4983.3  228.93  4988.8  229.66  4996.7  226.59  5005.3  227.23  5007.7  225.96
  5015.8  225.96  5019.7  231.55  5026.1  229.91    5034  232.44  5040.5  230.26
  5048.4   231.8  5054.8   230.9  5062.8  232.09  5069.2  231.06  5133.1  231.65
  5219.4  230.62  5332.8  230.57    5638  234.67  5951.2  248.95  6249.2   260.4
#Mann= 7 ,-1 , 0
  4527.9     .11       0  4552.1     .15       0  4674.2     .11       0
  4689.6     .15       0    4900     .09       0  5062.8     .15       0
  5219.4     .11       0
Bank Sta=4900,5062.8
XS Rating Curve= 0 ,0
Exp/Cntr=0.3,0.1

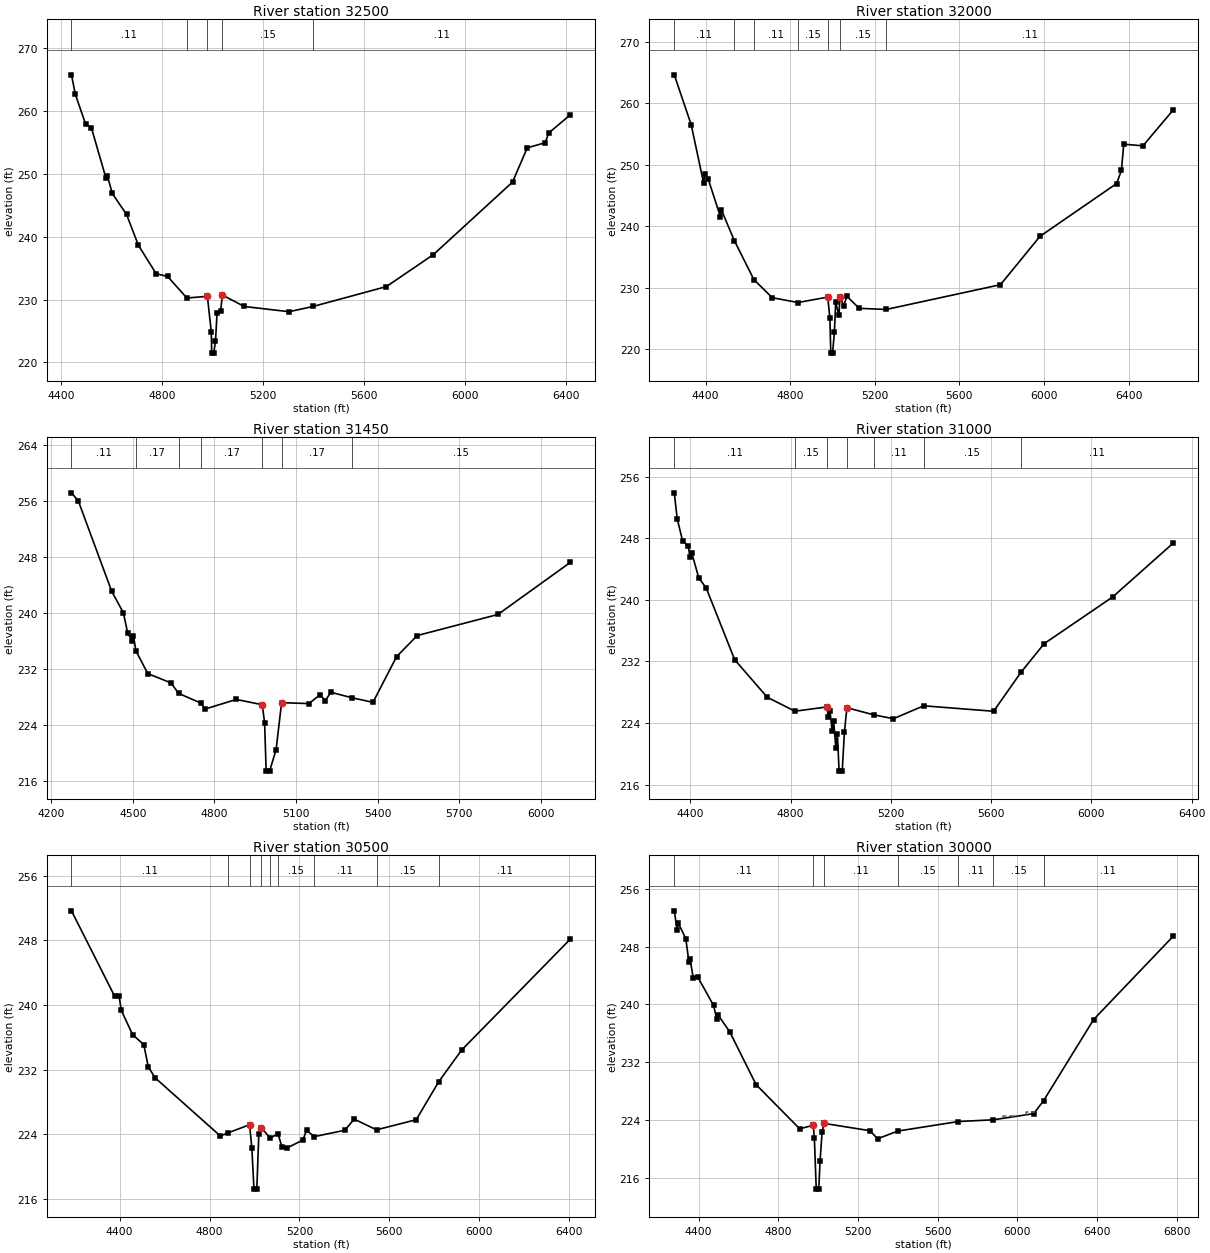
Type RM Length L Ch R = 1 ,32500   ,500,500,500
BEGIN DESCRIPTION:
WEIRS CREEK 57.0
END DESCRIPTION:
XS GIS Cut Line= 3
      3813758.34     10164974.51      3813898.23     10165516.97
       3815032.1     10166366.47
#Sta/Elev= 30
  4439.8   265.8  4454.8  262.73  4495.5  257.98  4518.9  257.34  4576.8  249.29
    4582  249.72  4601.5   246.9  4658.2  243.55  4704.8  238.66  4775.1  234.12
  4820.9  233.67  4897.2  230.24  4978.4  230.51  4993.9  224.83  4995.5  221.46
  5003.6  221.46  5010.5  223.38  5016.7  227.79  5031.3  228.25  5037.6  230.72
  5124.5  228.89  5302.2  228.06  5397.7   228.9  5687.7  232.06  5874.2  237.16
  6187.7  248.71  6246.1  254.17  6316.9  254.98  6331.5  256.54  6416.8  259.43
#Mann= 5 ,-1 , 0
  4439.8     .11       0  4897.2     .15       0  4978.4     .09       0
  5037.6     .15       0  5397.7     .11       0
Bank Sta=4978.4,5037.6
XS Rating Curve= 0 ,0
Exp/Cntr=0.3,0.1

Type RM Length L Ch R = 1 ,32000   ,550,550,550
BEGIN DESCRIPTION:
WEIRS CREEK 56.0
END DESCRIPTION:
XS GIS Cut Line= 4
      3813661.11     10164981.49      3813564.88     10165722.97
      3813575.76     10165741.87      3815008.33     10166429.37
#Sta/Elev= 30
  4252.3  264.66  4332.5  256.52  4391.1  247.03  4396.1  248.51  4413.2  247.66
  4470.3  241.57  4475.3  242.66  4536.4  237.67  4628.9  231.32  4715.7  228.38
  4837.6   227.6  4977.9  228.48    4988  225.05  4992.3  219.36  5000.7  219.36
  5009.3  222.74  5015.5  227.62  5030.6  225.54  5036.1  228.49  5053.2  227.07
  5068.5  228.61  5126.7  226.65  5254.7  226.47  5794.6   230.5  5981.4  238.37
  6343.7  246.96  6366.3  249.09  6377.5  253.37  6468.1   253.1  6610.8  258.92
#Mann= 7 ,-1 , 0
  4252.3     .11       0  4536.4     .17       0  4628.9     .11       0
  4837.6     .15       0  4977.9     .09       0  5036.1     .15       0
  5254.7     .11       0
Bank Sta=4977.9,5036.1
XS Rating Curve= 0 ,0
Exp/Cntr=0.3,0.1

Type RM Length L Ch R = 1 ,31450   ,450,450,450
BEGIN DESCRIPTION:
WEIRS CREEK 55.0
END DESCRIPTION:
XS GIS Cut Line= 3
      3813558.31     10165029.06      3813189.32     10165654.41
      3813054.41     10166755.68
#Sta/Elev= 30
  4273.9  257.19    4299  256.04  4421.9   243.1  4464.8  240.04  4480.4   237.2
  4496.1  236.06  4501.9  236.78  4510.8  234.61  4554.6  231.34  4640.4     230
  4667.9  228.51  4751.7  227.09  4763.9  226.25  4880.4  227.64    4976  226.89
  4984.5  224.27  4990.3  217.39  5002.8  217.39  5026.9  220.46    5047  227.18
  5147.8  227.05  5188.1   228.3  5208.2  227.49  5228.4  228.67    5307  227.87
  5383.3  227.23  5470.2  233.76  5546.2  236.78  5842.9  239.79  6109.5  247.24
#Mann= 7 ,-1 , 0
  4273.9     .11       0  4510.8     .17       0  4667.9     .15       0
  4751.7     .17       0    4976     .09       0    5047     .17       0
    5307     .15       0
#XS Ineff= 2 , 0
       0    4619  230.04               0
Permanent Ineff=
       F       F
Bank Sta=4976,5047
XS Rating Curve= 0 ,0
Exp/Cntr=0.3,0.1

Type RM Length L Ch R = 1 ,31000   ,500,500,500
BEGIN DESCRIPTION:
WEIRS CREEK 54.0
END DESCRIPTION:
XS GIS Cut Line= 3
        3813228.     10164884.19      3812844.79      10165426.7
      3813023.01     10166740.67
#Sta/Elev= 30
  4335.8  253.92  4347.5  250.55  4368.7  247.71  4391.9  246.95    4398  245.62
  4405.4  246.13  4433.7  242.85  4463.3  241.55  4576.8  232.23  4707.1  227.34
  4817.3  225.54  4944.1  226.09  4950.8  224.81  4956.9  225.59  4965.6  222.97
  4971.7  224.27  4980.4  220.78  4986.5  222.61  4993.4  217.75  5005.9  217.75
  5014.5  222.78  5024.6  225.99  5131.4  225.07    5210  224.56  5330.8  226.24
  5609.9  225.53  5719.2   230.6  5811.7  234.32  6084.2  240.37    6326  247.37
#Mann= 7 ,-1 , 0
  4335.8     .11       0  4817.3     .15       0  4944.1     .09       0
  5024.6     .15       0  5131.4     .11       0  5330.8     .15       0
  5719.2     .11       0
Bank Sta=4944.1,5024.6
XS Rating Curve= 0 ,0
Exp/Cntr=0.3,0.1

Type RM Length L Ch R = 1 ,30500   ,500,500,500
BEGIN DESCRIPTION:
WEIRS CREEK 53.0
END DESCRIPTION:
XS GIS Cut Line= 3
      3812557.88     10164609.87      3812521.32     10165422.85
      3812987.99     10166747.45
#Sta/Elev= 30
  4186.2  251.66  4377.6  241.12  4397.6  241.17  4407.6  239.35  4457.7  236.35
  4507.7   235.1  4527.7  232.36  4557.8     231  4848.1   223.8  4882.1  224.18
  4978.2  225.19  4988.2  222.31  4997.7  217.22  5010.3  217.22  5019.3  224.08
  5029.7  224.83  5069.8  223.55  5104.5  224.06  5122.5  222.41  5146.6  222.34
  5215.4   223.3  5231.4   224.5  5265.8  223.72  5401.1   224.5  5443.4  225.88
  5542.7  224.56  5719.1  225.81  5819.2  230.51  5920.5  234.41  6404.4  248.16
#Mann= 9 ,-1 , 0
  4186.2     .11       0  4882.1     .15       0  4978.2     .09       0
  5029.7     .15       0  5069.8     .11       0  5104.5     .15       0
  5265.8     .11       0  5542.7     .15       0  5819.2     .11       0
Bank Sta=4978.2,5029.7
XS Rating Curve= 0 ,0
Exp/Cntr=0.3,0.1

Type RM Length L Ch R = 1 ,30000   ,500,500,500
BEGIN DESCRIPTION:
WEIRS CREEK 52.0
END DESCRIPTION:
XS GIS Cut Line= 4
      3812450.48     10164594.27      3812092.98     10165221.43
      3812099.97      10165272.3      3812960.67     10166773.06
#Sta/Elev= 30
  4278.1  252.94  4292.6   250.3  4298.3  251.24  4335.8  249.09  4351.7  245.88
  4357.4  246.23  4373.3  243.68  4394.9  243.83  4475.5  239.85  4491.4  237.93
  4497.2  238.56  4556.2  236.22  4688.8   228.9  4907.5  222.79  4975.4  223.28
  4981.2   221.5  4990.6  214.45  5003.2  214.45  5009.7   218.3  5019.8   222.3
  5029.9  223.54  5260.7  222.53  5298.1  221.41  5399.6  222.48    5704   223.8
  5879.9  224.04    6082  224.89  6131.1  226.67  6382.6  237.91  6781.4  249.41
#Mann= 7 ,-1 , 0
  4278.1     .11       0  4975.4     .06       0  5029.9     .11       0
  5399.6     .15       0    5704     .11       0  5879.9     .15       0
  6131.1     .11       0
#XS Ineff= 2 ,-1
  6044.6  6087.7  225.06  5926.6  6001.4  224.51
Permanent Ineff=
       F       F
Bank Sta=4975.4,5029.9
XS Rating Curve= 0 ,0
Exp/Cntr=0.3,0.1

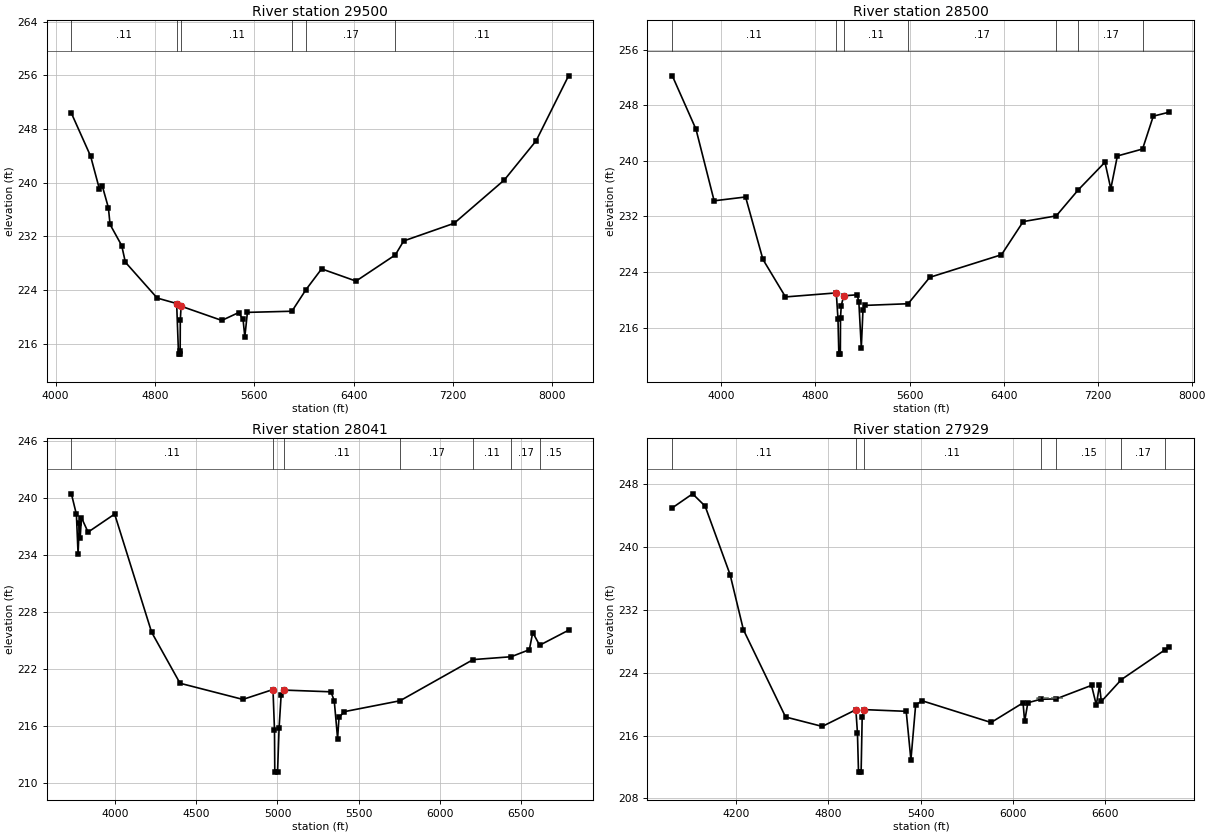
Type RM Length L Ch R = 1 ,29500   ,1000,1000,1000
BEGIN DESCRIPTION:
WEIRS CREEK 51.0
END DESCRIPTION:
XS GIS Cut Line= 3
      3812367.09      10164583.9      3811665.62     10165104.25
      3809696.37     10167536.24
#Sta/Elev= 30
  4126.6  250.36  4281.3  243.96  4352.2  239.06  4374.7  239.57  4424.5  236.28
  4437.8  233.79  4531.7  230.64  4560.9  228.17  4817.6  222.82    4974  222.01
  4989.1  214.47  5001.8  214.47  5002.3  214.97  5003.4   219.5  5009.8  221.61
  5337.5  219.49    5472  220.65  5508.5  219.67  5522.9  217.04  5543.7  220.69
  5902.1  220.86  6015.4  224.08  6141.1  227.17  6418.2  225.35  6734.5  229.25
  6801.9  231.33  7207.9  233.96  7612.4  240.42  7868.2  246.25  8129.3  255.93
#Mann= 6 ,-1 , 0
  4126.6     .11       0    4974     .06       0  5009.8     .11       0
  5902.1     .15       0  6015.4     .17       0  6734.5     .11       0
Bank Sta=4974,5009.8
XS Rating Curve= 0 ,0
Exp/Cntr=0.3,0.1

Type RM Length L Ch R = 1 ,28500   ,459,459,459
BEGIN DESCRIPTION:
WEIRS CREEK 49.0
END DESCRIPTION:
XS GIS Cut Line= 4
      3812343.66     10164565.66      3811215.32     10164837.96
      3811024.62      10165010.5      3809213.79     10167160.78
#Sta/Elev= 30
  3582.1  252.23  3783.5  244.54  3937.8  234.25  4205.3   234.8  4352.8  225.82
  4544.8  220.42    4977     221  4991.2  217.28  4998.7  212.19  5011.4  212.19
  5012.8  217.43  5019.3  219.18  5040.2  220.58  5154.5  220.73  5168.8   219.7
  5189.7  213.11    5204  218.56  5218.3   219.2  5587.9  219.44  5772.1  223.24
  6382.2  226.49  6566.9  231.26  6847.9  232.08  7034.7  235.81  7262.5   239.8
  7312.1  235.98    7368   240.7  7582.3   241.7  7673.6  246.43  7811.2  247.01
#Mann= 7 ,-1 , 0
  3582.1     .11       0    4977     .06       0  5040.2     .11       0
  5587.9     .17       0  6847.9     .11       0  7034.7     .17       0
  7582.3     .11       0
#XS Ineff= 2 , 0
       0                  5772.1       0  223.24
Permanent Ineff=
       F       F
Bank Sta=4977,5040.2
XS Rating Curve= 0 ,0
Exp/Cntr=0.3,0.1

Type RM Length L Ch R = 1 ,28041   ,112,112,112
BEGIN DESCRIPTION:
WEIRS CREEK 48.0
END DESCRIPTION:
XS GIS Cut Line= 4
      3812037.94     10164604.34      3810799.92     10164893.33
      3809963.76     10165078.17      3809672.39     10165971.08
#Sta/Elev= 30
  3728.7  240.39  3759.6  238.23  3769.9  234.05  3777.7  237.37  3782.8  235.71
  3790.4  237.89  3831.5  236.36  3995.5  238.26  4223.5  225.83  4398.8  220.46
  4786.5  218.76  4972.3   219.8  4981.6  215.52  4983.4  211.11  5000.4  211.11
    5010  215.79  5022.6  219.22  5043.1  219.74  5329.8  219.56  5350.3  218.61
  5370.8  214.64  5379.6  216.86  5411.8  217.47  5756.2  218.62  6207.1  222.95
  6441.5  223.25  6553.7  223.99  6574.7   225.8  6617.2  224.46  6795.6  226.04
#Mann= 7 ,-1 , 0
  3728.7     .11       0  4972.3     .06       0  5043.1     .11       0
  5756.2     .17       0  6207.1     .11       0  6441.5     .17       0
  6617.2     .15       0
Bank Sta=4972.3,5043.1
XS Rating Curve= 0 ,0
Exp/Cntr=0.3,0.1

Type RM Length L Ch R = 1 ,27929   ,929,929,929
BEGIN DESCRIPTION:
WEIRS CREEK 47.0
END DESCRIPTION:
XS GIS Cut Line= 4
      3811956.29     10164481.98      3810777.04     10164785.18
      3809753.52     10165012.28      3809493.08     10165950.49
#Sta/Elev= 30
  3782.4  244.95  3914.6  246.73    3996  245.17    4159  236.45  4245.6  229.45
  4520.4  218.36  4759.6  217.16  4978.5  219.28  4988.8  216.34  4995.7  211.35
  5012.7  211.35  5019.7   218.4  5029.9   219.3  5306.5  219.08  5337.2   212.9
  5367.9  219.86  5408.9  220.43  5859.6  217.66  6067.9  220.16  6078.3  217.79
  6099.1  220.17  6182.7  220.61  6283.6  220.66  6514.2  222.38  6545.3  219.89
  6566.1  222.39    6578  220.33  6708.9  223.12  6990.2  226.86  7022.1  227.29
#Mann= 7 ,-1 , 0
  3782.4     .11       0  4978.5     .06       0  5029.9     .11       0
  6182.7     .17       0  6283.6     .15       0  6708.9     .17       0
  6990.2     .15       0
#XS Ineff= 2 ,-1
  5408.9  6159.6  220.43  6159.6  6327.4  220.82
Permanent Ineff=
       T       T
Bank Sta=4978.5,5029.9
XS Rating Curve= 0 ,0
Exp/Cntr=0.3,0.1