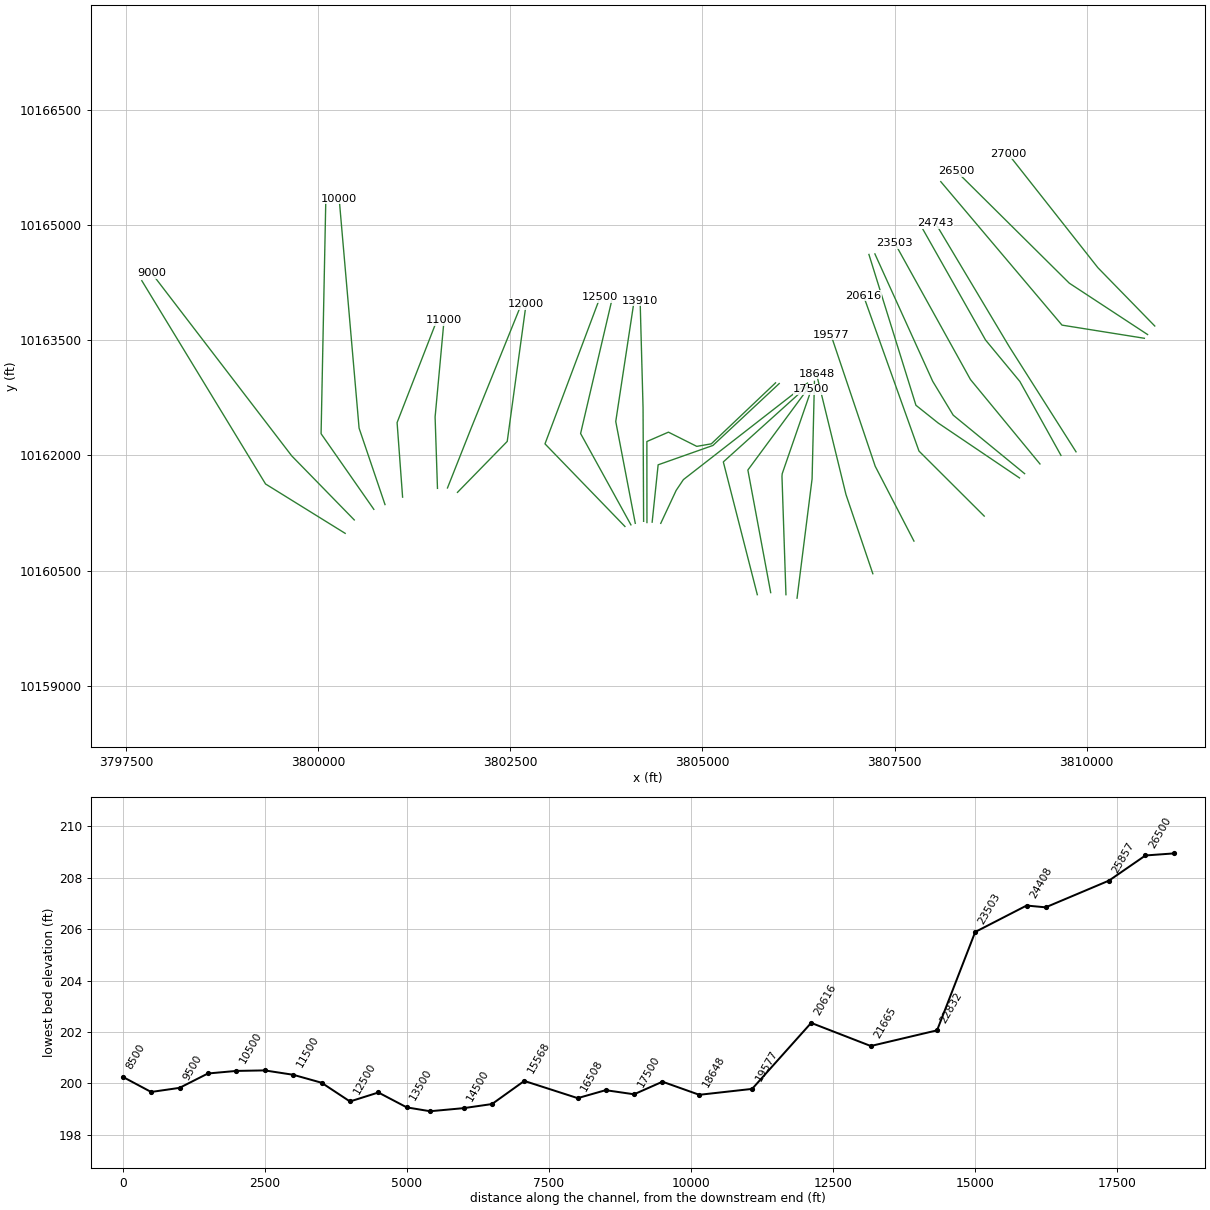
HEC-RAS study WEIRS CREEK.prj: WEIRS CREEK Base Level Engineering

--- WEIRS CREEK.g01 (geometry) --- (continued)

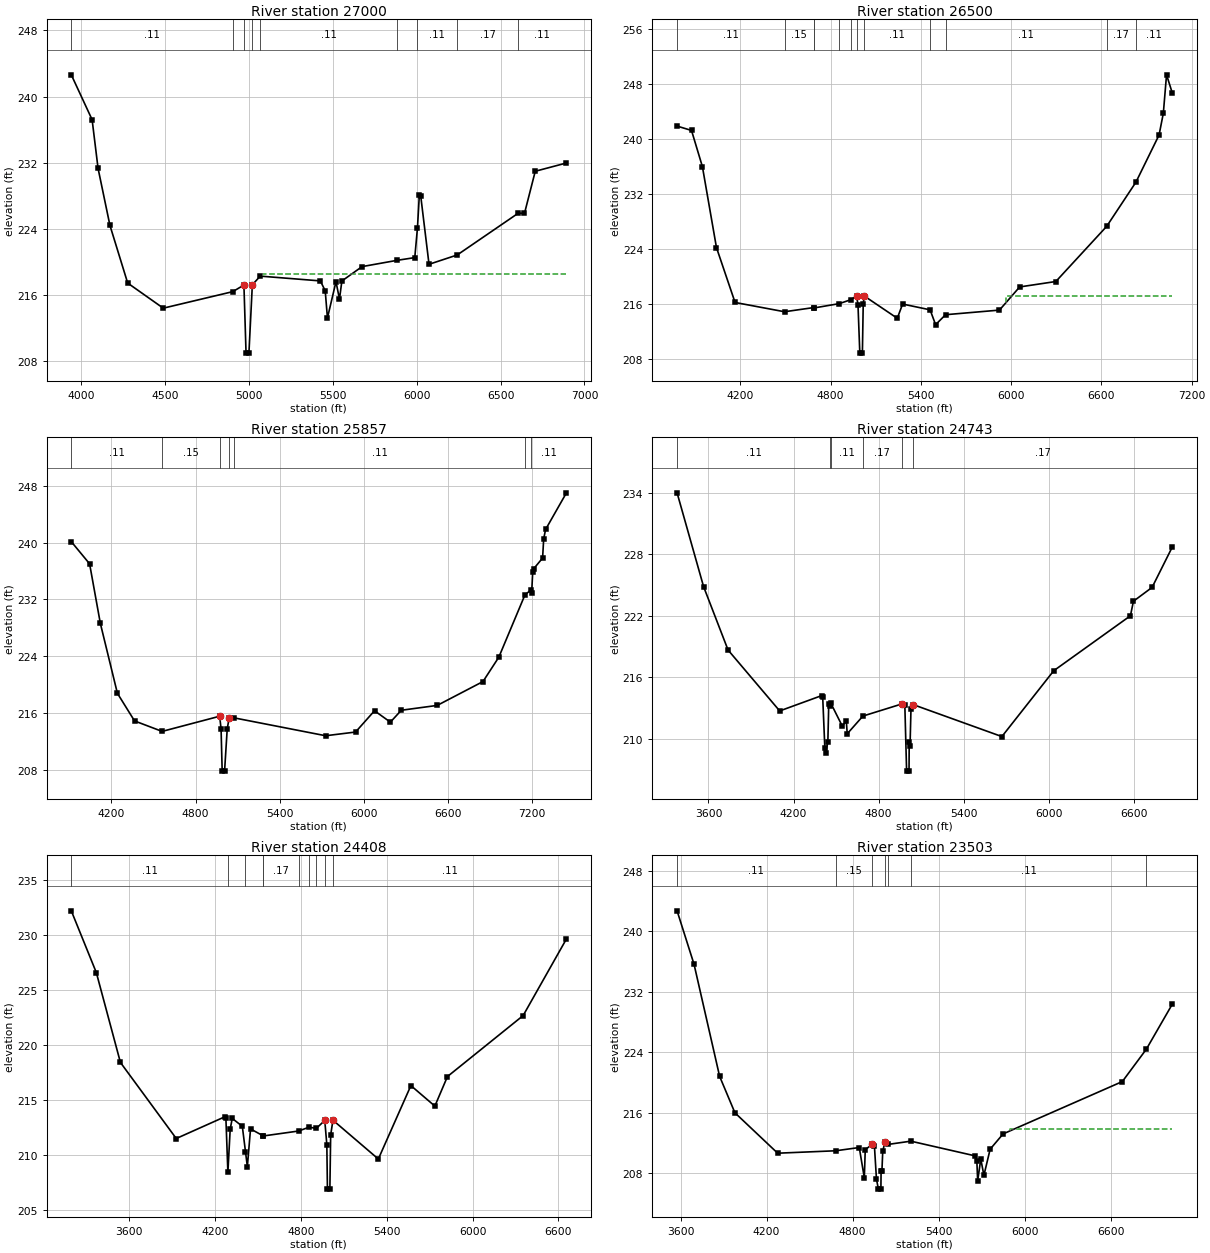
Type RM Length L Ch R = 1 ,27000   ,500,500,500
BEGIN DESCRIPTION:
WEIRS CREEK 46.0
END DESCRIPTION:
XS GIS Cut Line= 3
       3810887.7     10163685.44      3810147.59     10164444.01
      3808976.26     10165930.21
#Sta/Elev= 30
  3940.2  242.63  4064.3   237.2  4099.7  231.32  4170.4  224.42  4276.4  217.43
  4488.6  214.39  4902.8  216.39  4969.4  217.19  4982.1  208.95  4999.2  208.95
  5019.6  217.22  5066.6  218.27  5425.2  217.69  5454.1  216.49  5467.4   213.2
  5518.3   217.6  5539.1  215.49  5553.5  217.68  5673.7  219.42  5882.6  220.18
  5988.1  220.51  6004.1  224.11  6015.2  228.07  6023.3  228.02    6073   219.7
  6241.2  220.83  6605.4  225.89  6642.2  225.86  6706.4  230.96  6892.3  231.96
#Mann= 9 ,-1 , 0
  3940.2     .11       0  4902.8     .15       0  4969.4     .09       0
  5019.6     .15       0  5066.6     .11       0  5882.6     .17       0
  6004.1     .11       0  6241.2     .17       0  6605.4     .11       0
#XS Ineff= 2 , 0
       0                  5083.7       0  218.51
Permanent Ineff=
       F       T
Bank Sta=4969.4,5019.6
XS Rating Curve= 0 ,0
Exp/Cntr=0.3,0.1

Type RM Length L Ch R = 1 ,26500   ,643,643,643
BEGIN DESCRIPTION:
WEIRS CREEK 45.0
END DESCRIPTION:
XS GIS Cut Line= 3
      3810794.22     10163574.22      3809774.68     10164243.32
      3808304.41     10165701.02
#Sta/Elev= 30
  3780.5   241.9  3876.4  241.27  3948.8     236  4042.2  224.23  4165.8  216.24
  4494.5  214.89  4688.9   215.5  4692.5  215.45  4858.1  216.07  4934.6  216.64
  4973.4  217.17  4982.5  215.93  4994.7  208.87  5011.8  208.87  5017.4  216.07
  5024.4  217.18  5243.7  213.94    5279  216.01  5461.7  215.17  5498.2  213.01
  5564.6  214.46  5922.5  215.13  6056.8   218.5  6297.2  219.29  6634.8  227.31
  6829.5  233.75  6983.1  240.61  7011.4  243.77  7032.7  249.36  7070.4  246.76
#Mann= 12 ,-1 , 0
  3780.5     .11       0  4494.5     .15       0  4688.9     .11       0
  4692.5     .17       0  4858.1     .15       0  4934.6     .11       0
  4973.4     .06       0  5024.4     .11       0  5461.7     .17       0
  5564.6     .11       0  6634.8     .17       0  6829.5     .11       0
#XS Ineff= 2 , 0
       0                  5964.9       0   217.2
Permanent Ineff=
       F       F
Bank Sta=4973.4,5024.4
XS Rating Curve= 0 ,0
Exp/Cntr=0.3,0.1

Type RM Length L Ch R = 1 ,25857   ,1114,1114,1114
BEGIN DESCRIPTION:
WEIRS CREEK 44.0
END DESCRIPTION:
XS GIS Cut Line= 3
      3810752.54     10163525.62      3809680.33     10163696.86
      3808102.09     10165564.65
#Sta/Elev= 30
  3914.2  240.12  4044.7  237.01  4121.5  228.63    4243  218.82  4365.3  214.94
  4561.9  213.47  4972.1   215.6  4982.3  213.85  4990.2  207.89  5007.3  207.89
  5026.1  213.81  5040.4  215.42  5075.5  215.37  5728.2  212.86  5941.4  213.38
  6076.6  216.37  6189.7  214.77  6267.7  216.44  6523.8  217.12  6850.1  220.47
  6963.3   223.9  7148.9  232.62  7190.9  233.33  7197.3  232.96    7205  235.89
  7211.6  236.31  7275.3  237.82  7283.1  240.52  7296.6  241.83  7445.3  246.98
#Mann= 7 ,-1 , 0
  3914.2     .11       0  4561.9     .15       0  4972.1     .09       0
  5040.4     .15       0  5075.5     .11       0  7148.9     .17       0
  7190.9     .11       0
#XS Ineff= 2 , 0
       0                  6076.6       0  216.37
Permanent Ineff=
       F       F
Bank Sta=4972.1,5040.4
XS Rating Curve= 0 ,0
Exp/Cntr=0.3,0.1

Type RM Length L Ch R = 1 ,24743   ,335,335,335
BEGIN DESCRIPTION:
WEIRS CREEK 43.0
END DESCRIPTION:
XS GIS Cut Line= 3
      3809862.72     10162047.94      3808993.45     10163416.87
      3808033.81     10165022.79
#Sta/Elev= 30
  3378.4  233.99  3565.2  224.85    3738  218.66  4102.2  212.72  4399.5  214.22
  4405.5  214.09  4420.7  209.09  4426.6  208.57  4441.9  209.71  4448.2  213.37
  4456.2  213.22  4461.9   213.5    4543  211.26  4572.3  211.73  4578.5  210.49
  4689.2  212.22  4963.7   213.4  4984.8  213.32  4997.4  206.85  5014.5  206.85
  5015.7  209.65  5021.5  209.26  5028.2   212.9  5042.9  213.34  5669.4  210.22
  6035.1  216.64    6576     222  6597.4  223.42    6729  224.77  6870.8  228.69
#Mann= 6 ,-1 , 0
  3378.4     .11       0  4456.2     .15       0  4461.9     .11       0
  4689.2     .17       0  4963.7     .09       0  5042.9     .17       0
Bank Sta=4963.7,5042.9
XS Rating Curve= 0 ,0
Exp/Cntr=0.3,0.1

Type RM Length L Ch R = 1 ,24408   ,905,905,905
BEGIN DESCRIPTION:
WEIRS CREEK 200.0
END DESCRIPTION:
XS GIS Cut Line= 4
      3809666.61      10162001.4      3809131.88     10162963.16
      3808684.79     10163503.32      3807869.71     10164944.15
#Sta/Elev= 30
  3198.4  232.16  3373.1  226.56  3541.3  218.41  3931.2  211.51    4272  213.49
  4277.7  213.38  4291.7  208.45  4307.8  212.36  4322.1  213.33  4392.4  212.62
  4414.5  210.32  4427.6  208.96  4449.8  212.38  4534.2  211.78  4538.2  211.74
  4785.6  212.19  4858.8  212.54  4909.3  212.43  4968.1  213.15  4982.5  210.96
  4986.7  206.92  5003.8  206.92  5009.3  211.83  5025.2  213.17  5342.1  209.65
  5569.4  216.31  5736.8  214.45  5824.6  217.13  6353.1  222.66  6655.4  229.61
#Mann= 10 ,-1 , 0
  3198.4     .11       0  4291.7     .15       0  4414.5     .11       0
  4534.2     .15       0  4538.2     .17       0  4785.6     .15       0
  4858.8     .17       0  4909.3     .11       0  4968.1     .06       0
  5025.2     .11       0
#XS Ineff= 2 , 0
       0                  5569.4       0  216.31
Permanent Ineff=
       F       F
Bank Sta=4968.1,5025.2
XS Rating Curve= 0 ,0
Exp/Cntr=0.3,0.1

Type RM Length L Ch R = 1 ,23503   ,671,671,671
BEGIN DESCRIPTION:
WEIRS CREEK 42.0
END DESCRIPTION:
XS GIS Cut Line= 3
      3809393.41     10161889.78      3808488.37     10162989.05
      3807505.14     10164761.84
#Sta/Elev= 30
  3576.1  242.68  3694.4  235.61  3872.6   220.8  3979.3  215.98  4277.2  210.64
  4681.8  210.96    4846  211.39  4881.2  207.38  4887.7   211.1  4937.9  211.85
  4951.5  211.62  4965.9  207.19  4979.5  205.89  4996.7  205.89  4998.1  208.35
    5004  208.35  5009.7  210.91  5025.2  212.13  5046.4   211.8  5205.4  212.23
  5655.2  210.28  5665.5  209.62  5671.2  206.98    5693  209.86  5714.7  207.71
  5758.2  211.17  5848.5  213.19  6679.5  220.11    6847  224.39  7027.2  230.32
#Mann= 7 ,-1 , 0
  3576.1     .11       0  4681.8     .15       0  4937.9     .09       0
  5025.2     .15       0  5046.4     .15       0  5205.4     .11       0
    6847     .17       0
#XS Ineff= 2 , 0
       0                  5893.2       0   213.8
Permanent Ineff=
       F       F
Bank Sta=4937.9,5025.2
XS Rating Curve= 0 ,0
Exp/Cntr=0.3,0.1

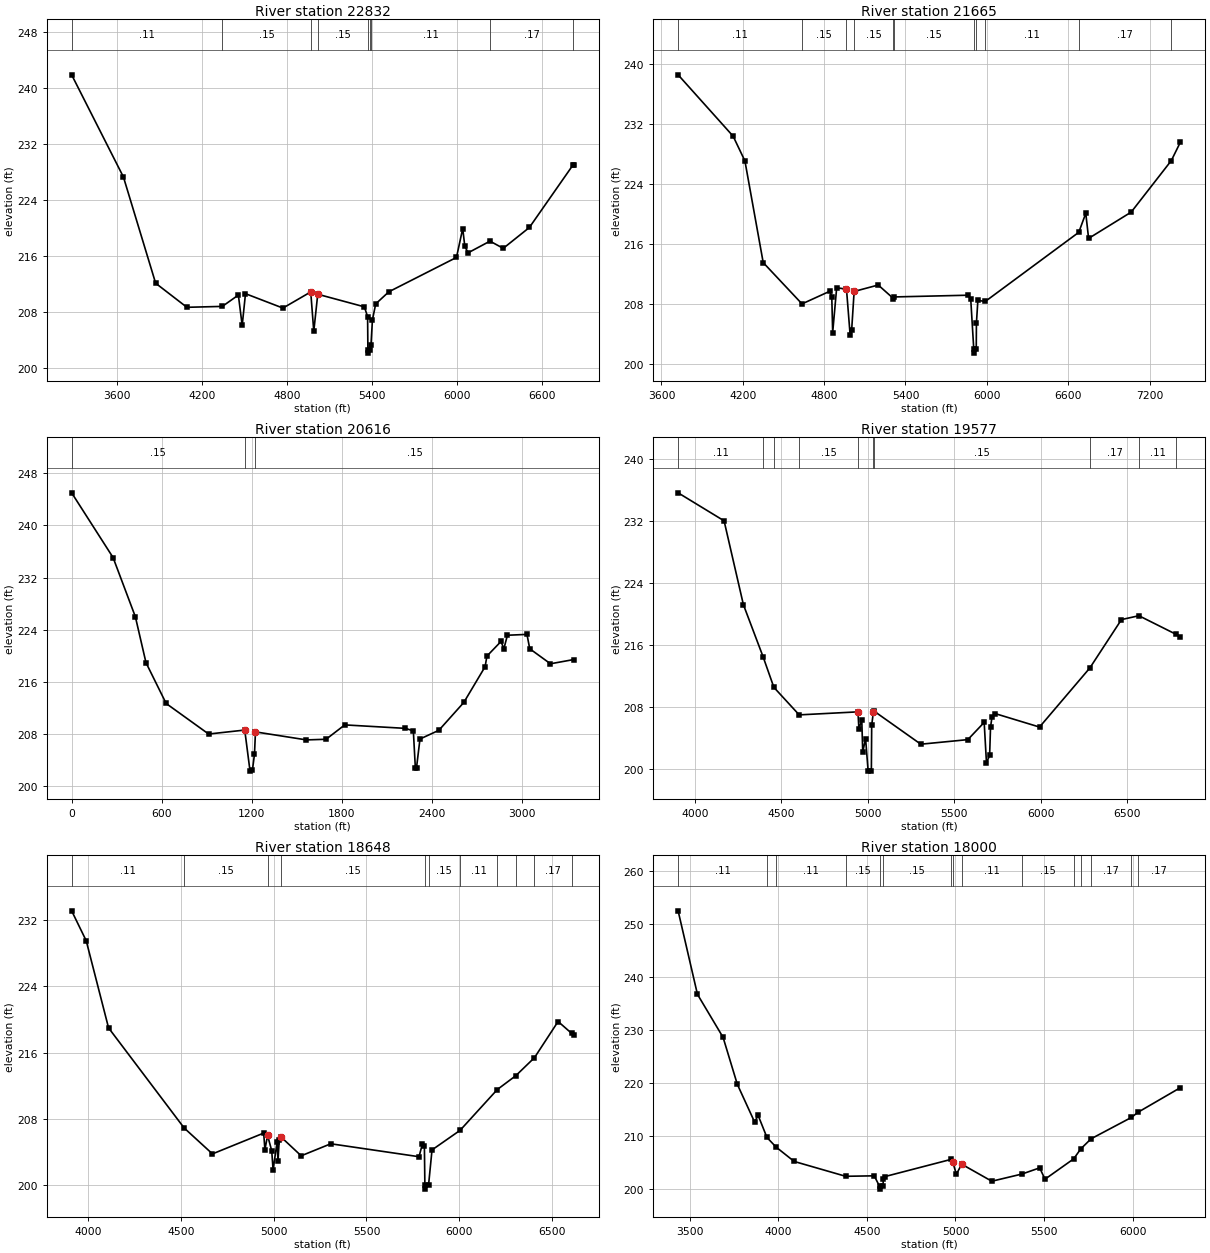
Type RM Length L Ch R = 1 ,22832   ,1167,1167,1167
BEGIN DESCRIPTION:
WEIRS CREEK 201.0
END DESCRIPTION:
XS GIS Cut Line= 4
      3809193.47     10161763.61      3808264.14     10162524.84
      3807997.32     10162965.45       3807244.7     10164623.86
#Sta/Elev= 30
  3283.6   241.9  3648.4  227.27  3875.2  212.07  4095.5  208.62  4344.9  208.75
    4458  210.37  4484.9  206.02  4508.2  210.57  4771.9  208.51  4967.8  210.82
  4989.2  205.18  5017.2  210.49  5345.3  208.69  5368.4  207.29  5370.4  202.56
  5370.9  202.06  5388.6  202.56    5392  203.18  5402.5  206.84  5425.6  209.11
  5517.9  210.84  5994.5  215.76  6038.4   219.9  6053.1  217.36  6076.2  216.42
  6230.5  218.09    6324  217.06  6508.1  220.05  6813.8  228.95  6821.2  229.04
#Mann= 9 ,-1 , 0
  3283.6     .11       0  4344.9     .15       0  4967.8     .09       0
  5017.2     .15       0  5370.4     .12       0  5388.6     .15       0
    5392     .11       0  6230.5     .17       0  6813.8     .11       0
Bank Sta=4967.8,5017.2
XS Rating Curve= 0 ,0
Exp/Cntr=0.3,0.1

Type RM Length L Ch R = 1 ,21665   ,1049,1049,1049
BEGIN DESCRIPTION:
WEIRS CREEK 41.0
END DESCRIPTION:
XS GIS Cut Line= 4
       3809127.1     10161707.52      3808068.79     10162422.34
      3807778.86     10162653.63      3807167.05     10164616.82
#Sta/Elev= 30
  3722.9  238.59  4128.7   230.4  4215.6   227.1  4350.6  213.53  4636.8  208.02
    4842  209.71  4856.3     209    4863   204.2  4892.5  210.18  4964.9  209.98
    4992  203.82    5003  204.53  5021.2  209.68  5198.9  210.54    5311  208.74
  5318.8  208.95  5863.7  209.18  5881.4  208.64  5903.8  201.95  5904.3  201.45
    5922  201.95  5923.3  205.46    5934  208.49  5988.1  208.34  6678.2  217.57
  6729.9  220.11  6750.8  216.76    7065  220.27  7360.7  227.14  7427.2  229.58
#Mann= 11 ,-1 , 0
  3722.9     .11       0  4636.8     .15       0  4964.9     .09       0
  5021.2     .15       0    5311     .11       0  5318.8     .15       0
  5903.8     .12       0    5922     .15       0  5988.1     .11       0
  6678.2     .17       0  7360.7     .11       0
Bank Sta=4964.9,5021.2
XS Rating Curve= 0 ,0
Exp/Cntr=0.3,0.1

Type RM Length L Ch R = 1 ,20616   ,1039,1039,1039
XS GIS Cut Line= 3
      3808667.85     10161211.07      3807818.67     10162057.55
      3807096.42       10164079.
#Sta/Elev= 30
       0  244.97   275.8  235.06   424.3  225.99     495  218.96   629.3  212.71
   912.2  208.03  1152.6  208.64  1187.9  202.35  1203.5  202.45  1217.5  204.95
    1224  208.36  1563.8  207.13  1694.2  207.23  1818.7  209.43  2221.9   208.9
  2275.3  208.52  2288.7  202.84  2296.5  202.88  2319.5  207.27  2445.2   208.6
  2611.5  212.87  2753.1  218.34  2765.4  219.97  2859.3  222.21    2878  221.08
  2901.8  223.16  3031.9  223.29  3050.5  221.09  3188.5  218.79  3344.1  219.44
#Mann= 3 , 0 , 0
       0     .15       0  1152.6     .09       0    1224     .15       0
Bank Sta=1152.6,1224
XS Rating Curve= 0 ,0
Exp/Cntr=0.3,0.1

Type RM Length L Ch R = 1 ,19577   ,930,930,930
BEGIN DESCRIPTION:
WEIRS CREEK 38.0
END DESCRIPTION:
XS GIS Cut Line= 3
      3807753.01      10160885.7      3807248.79     10161859.84
      3806671.37     10163573.89
#Sta/Elev= 30
  3903.1  235.65  4169.1  232.04  4280.7  221.24  4395.2  214.49  4457.1  210.58
  4603.6  207.03  4943.6  207.42  4949.2  205.19  4965.7  206.39  4971.3  202.26
  4987.8  203.97  5002.5  199.78  5021.2  199.78  5023.1  205.69    5033  207.41
  5038.9  207.48  5307.3  203.25  5579.4  203.84  5673.9  206.06  5687.2  200.86
  5705.4   201.8  5710.7  205.43  5718.9  206.73  5736.9   207.2  5994.1  205.46
  6285.4  213.08  6468.1  219.31  6569.2  219.81  6784.5  217.41  6808.7  217.11
#Mann= 10 ,-1 , 0
  3903.1     .11       0  4395.2     .15       0  4457.1     .11       0
  4603.6     .15       0  4943.6     .09       0    5033     .15       0
  5038.9     .15       0  6285.4     .17       0  6569.2     .11       0
  6784.5     .15       0
Bank Sta=4943.6,5033
XS Rating Curve= 0 ,0
Exp/Cntr=0.3,0.1

Type RM Length L Ch R = 1 ,18648   ,648,648,648
BEGIN DESCRIPTION:
WEIRS CREEK 36.0
END DESCRIPTION:
XS GIS Cut Line= 3
      3807217.86     10160461.06      3806868.04     10161492.24
      3806483.87     10163063.46
#Sta/Elev= 30
  3911.1  233.12  3989.6  229.51    4110     219  4517.2  206.93  4669.9   203.8
    4946  206.31  4952.6  204.32  4967.1  206.02  4989.3  204.18  4996.7  201.87
    5018   205.2  5023.2  202.93  5029.7  205.49    5040  205.83  5148.1  203.57
  5307.6  205.02    5783  203.46  5801.8  205.02  5812.1  204.71  5814.7  200.05
  5815.2  199.55  5834.6  200.05  5853.2  204.28  6004.4  206.64  6204.9  211.56
  6305.1  213.24  6405.4  215.41  6532.6  219.77  6606.2  218.33  6617.5  218.11
#Mann= 11 ,-1 , 0
  3911.1     .11       0  4517.2     .15       0  4967.1     .09       0
    5040     .15       0  5814.7     .12       0  5834.6     .15       0
  6004.4     .11       0  6204.9     .17       0  6305.1     .11       0
  6405.4     .17       0  6606.2     .11       0
Bank Sta=4967.1,5040
XS Rating Curve= 0 ,0
Exp/Cntr=0.3,0.1

Type RM Length L Ch R = 1 ,18000   ,500,500,500
BEGIN DESCRIPTION:
WEIRS CREEK 35.0
END DESCRIPTION:
XS GIS Cut Line= 3
      3806231.31     10160142.88      3806427.11     10161695.88
      3806457.82     10162964.51
#Sta/Elev= 30
  3434.7  252.55  3543.8   236.8  3688.4  228.69  3768.7  219.84  3866.3  212.72
  3886.4  213.96  3936.1   209.8    3988  207.98  4089.8  205.28  4380.3  202.48
  4541.6  202.57    4572  200.56  4572.5  200.06  4591.9  200.56    4592  201.98
  4602.1  202.43  4977.6  205.69  4985.1  205.12  5005.2  202.87  5035.2  204.76
  5205.2  201.55  5375.6  202.91  5475.3  204.07  5505.3  201.93  5666.8  205.76
  5707.9  207.67  5765.2  209.55  5993.5  213.59  6029.8  214.55    6269  219.19
#Mann= 15 ,-1 , 0
  3434.7     .11       0  3936.1     .17       0    3988     .11       0
  4380.3     .15       0    4572     .11       0  4591.9     .15       0
  4977.6     .11       0  4985.1     .07       0  5035.2     .11       0
  5375.6     .15       0  5666.8     .17       0  5707.9     .11       0
  5765.2     .17       0  5993.5     .11       0  6029.8     .17       0
Bank Sta=4985.1,5035.2
XS Rating Curve= 0 ,0
Exp/Cntr=0.3,0.1

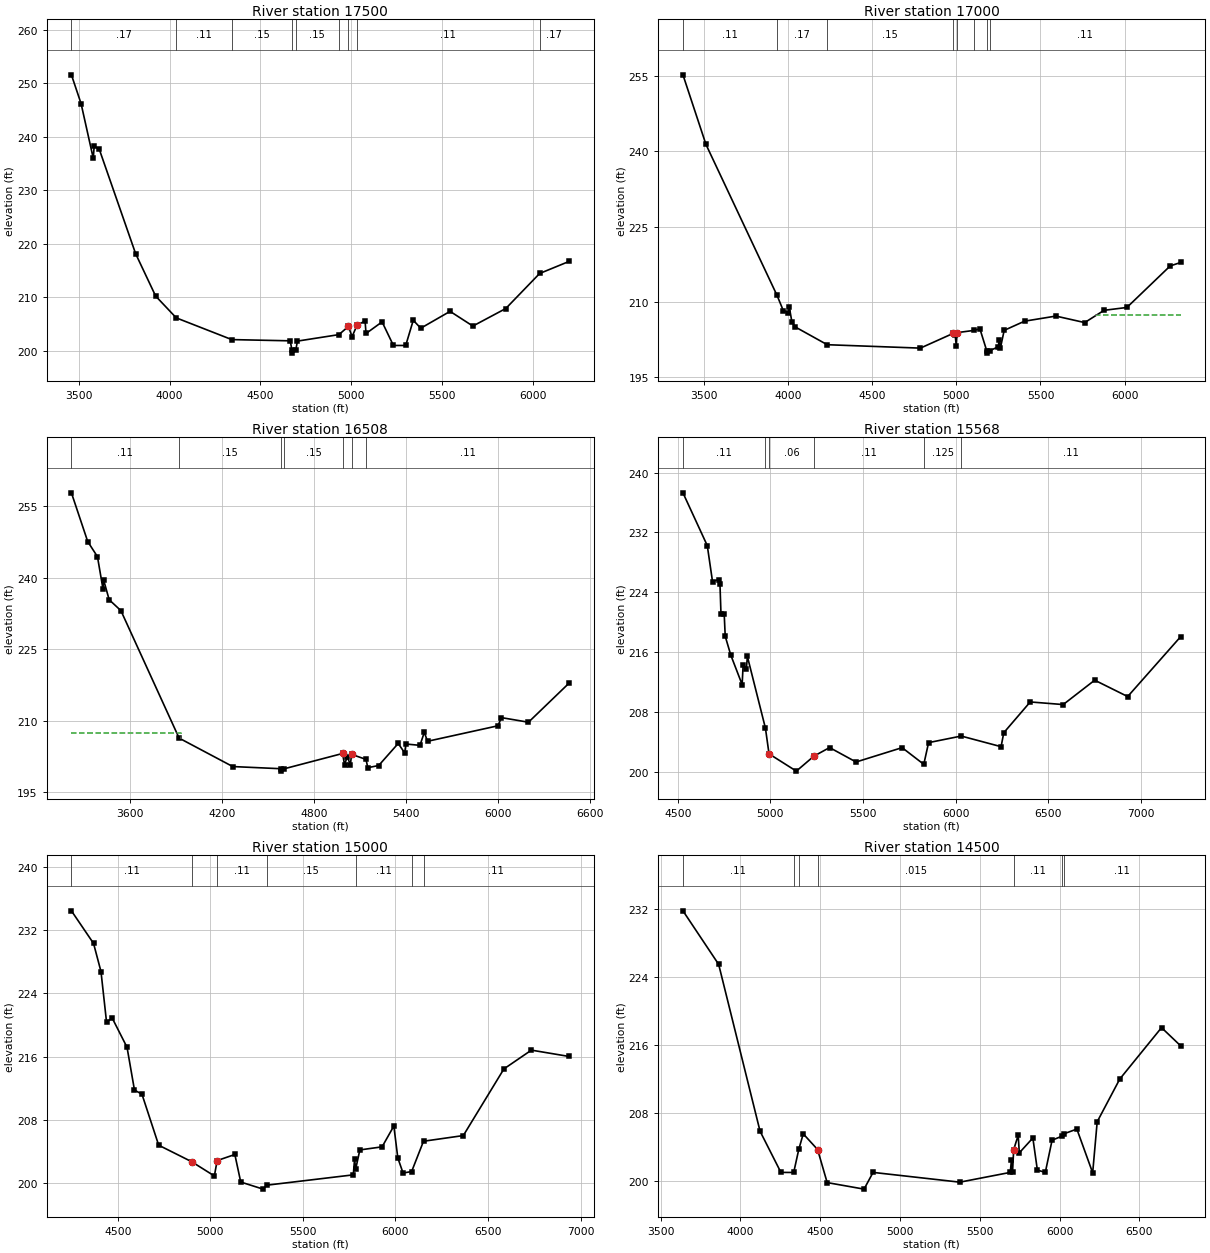
Type RM Length L Ch R = 1 ,17500   ,500,500,500
BEGIN DESCRIPTION:
WEIRS CREEK 34.0
END DESCRIPTION:
XS GIS Cut Line= 4
      3806086.96     10160187.95       3806035.2     10161726.88
        3806038.     10161762.13      3806417.85     10162861.07
#Sta/Elev= 30
  3460.2   251.6  3513.4  246.21  3580.4  235.99  3585.4  238.25  3613.4  237.69
  3813.5  218.16  3923.6  210.24  4037.1  206.16  4342.6   202.1    4664  201.87
  4674.1  200.07  4674.6  199.57    4694  200.07    4704  201.82    4932  203.03
  4984.2  204.56  5004.6  202.65  5032.3  204.85    5076  205.55  5081.3  203.24
  5169.6  205.41  5231.9     201  5299.6     201  5341.1  205.71  5382.5  204.23
  5543.7  207.38  5669.1  204.63  5850.2  207.91  6036.5  214.46  6198.1  216.71
#Mann= 9 ,-1 , 0
  3460.2     .17       0  4037.1     .11       0  4342.6     .15       0
  4674.1     .11       0    4694     .15       0    4932     .11       0
  4984.2     .08       0  5032.3     .11       0  6036.5     .17       0
#XS Ineff= 2 , 0
       0                  5543.7       0  207.38
Permanent Ineff=
       F       F
Bank Sta=4984.2,5032.3
XS Rating Curve= 0 ,0
Exp/Cntr=0.3,0.1

Type RM Length L Ch R = 1 ,17000   ,492,492,492
BEGIN DESCRIPTION:
WEIRS CREEK 33.0
END DESCRIPTION:
XS GIS Cut Line= 3
      3805888.48     10160215.02       3805591.3     10161810.69
       3806381.7     10162882.58
#Sta/Elev= 30
  3376.9  255.31  3513.5  241.41  3935.9  211.24    3973  208.21  4003.4  207.76
  4008.5  208.93  4023.9  205.96  4044.2  204.95  4233.8  201.41  4786.8  200.73
    4980  203.65  4993.4  203.36    5000  201.23  5004.7  203.82  5102.9  204.26
  5140.4  204.58  5180.6  200.23  5181.1  199.73  5200.5  200.23    5249     201
  5255.3  202.36  5261.5  200.66  5284.6  204.28  5405.6  206.11  5591.5  207.13
  5762.7  205.83  5877.6  208.28  6013.3  208.85  6270.2  217.14  6331.8  217.83
#Mann= 8 ,-1 , 0
  3376.9     .11       0  3935.9     .17       0  4233.8     .15       0
    4980     .08       0  5004.7     .12       0  5102.9     .11       0
  5180.6     .12       0  5200.5     .11       0
#XS Ineff= 2 , 0
       0  4008.5  208.93  5827.5       0  207.25
Permanent Ineff=
       F       F
Bank Sta=4980,5004.7
XS Rating Curve= 0 ,0
Exp/Cntr=0.3,0.1

Type RM Length L Ch R = 1 ,16508   ,940,940,940
BEGIN DESCRIPTION:
WEIRS CREEK 32.0
END DESCRIPTION:
XS GIS Cut Line= 3
      3805714.04     10160188.01      3805271.75     10161916.52
      3806357.61     10162894.58
#Sta/Elev= 30
  3215.8  257.81  3322.2  247.58  3385.6  244.42  3421.3  237.71  3426.4  239.45
  3462.1  235.38  3538.6  233.09  3918.2  206.35    4268  200.38  4584.6  199.92
  4585.1  199.42  4604.6  199.92  4984.1  203.12  4997.5  200.77  5014.6  202.44
  5035.5  200.77    5043  202.94  5137.3  201.88  5149.1  200.14  5220.1   200.6
  5347.2  205.22  5389.8  203.24  5397.3  205.11  5489.2  204.83  5517.6  207.56
  5538.5  205.68  5998.9  208.94  6019.9  210.65    6197  209.68  6461.4  217.87
#Mann= 7 ,-1 , 0
  3215.8     .11       0  3918.2     .15       0  4584.6     .12       0
  4604.6     .15       0  4984.1     .07       0    5043     .11       0
  5137.3     .11       0
#XS Ineff= 2 , 0
       0  3931.2  207.37  5517.6       0  207.56
Permanent Ineff=
       F       F
Bank Sta=4984.1,5043
XS Rating Curve= 0 ,0
Exp/Cntr=0.3,0.1

Type RM Length L Ch R = 1 ,15568   ,568,568,568
BEGIN DESCRIPTION:
WEIRS CREEK 31.0
END DESCRIPTION:
XS GIS Cut Line= 4
      3804457.35     10161116.66       3804657.4     10161544.94
      3804751.85     10161685.73      3806366.66     10162942.72
#Sta/Elev= 30
  4527.3   237.3  4658.8  230.24  4687.1  225.43  4719.8  225.71  4727.3  225.08
  4732.8  221.11  4750.2  221.11  4755.7  218.12    4786  215.59  4847.1  211.66
  4852.6  214.32    4870   213.8  4875.5  215.42  4973.1  205.82 4992.39   202.4
    5140  200.09  5234.7  202.09  5319.7  203.24  5462.7  201.31  5711.5  203.23
  5828.6     201  5854.5   203.9  6030.9  204.78  6246.3  203.36  6260.7  205.22
  6403.7  209.34  6581.9  208.99  6752.1  212.25  6930.3  210.06  7215.9  218.05
#Mann= 6 ,-1 , 0
  4527.3     .11       0  4973.1     .15       0 4992.39     .06       0
  5234.7     .11       0  5828.6    .125       0  6030.9     .11       0
Bank Sta=4992.39,5234.7
XS Rating Curve= 0 ,0
Exp/Cntr=0.3,0.1

Type RM Length L Ch R = 1 ,15000   ,500,500,500
BEGIN DESCRIPTION:
WEIRS CREEK 30.0
END DESCRIPTION:
XS GIS Cut Line= 4
      3804345.36     10161132.26      3804423.15     10161878.62
      3805136.64     10162130.72      3805999.44      10162936.4
#Sta/Elev= 30
  4249.6  234.47  4369.1  230.34  4409.3  226.77  4439.4  220.34  4469.6  220.89
    4550  217.17  4590.2  211.74  4630.5  211.23  4720.9  204.76  4898.8  202.67
  5021.6  200.86  5036.8  202.81  5132.3  203.58  5164.1  200.09    5285  199.19
  5304.7  199.69  5772.1     201  5779.1  203.03  5784.6   201.7  5807.4  204.16
  5927.6  204.55  5991.1  207.19  6012.6  203.14  6040.9  201.23  6087.2  201.42
  6151.3  205.26  6366.3  205.98  6585.6  214.43  6734.1  216.81  6937.2  216.01
#Mann= 7 ,-1 , 0
  4249.6     .11       0  4898.8     .06       0  5036.8     .11       0
  5304.7     .15       0  5784.6     .11       0  6087.2    .125       0
  6151.3     .11       0
#XS Ineff= 2 , 0
       0                  5991.1       0  207.19
Permanent Ineff=
       F       F
Bank Sta=4898.8,5036.8
XS Rating Curve= 0 ,0
Exp/Cntr=0.3,0.1

Type RM Length L Ch R = 1 ,14500   ,590,590,590
BEGIN DESCRIPTION:
WEIRS CREEK 29.0
END DESCRIPTION:
XS GIS Cut Line= 6
      3804277.65     10161127.27      3804276.54     10162181.84
      3804557.24     10162303.69      3804926.13     10162118.69
      3805115.59     10162151.77      3805951.66     10162945.74
#Sta/Elev= 30
  3639.3  231.79  3863.1  225.49  4122.7  205.84  4253.2     201  4333.4  200.99
  4365.2   203.7  4393.2  205.54  4483.2  203.69  4543.2   199.8  4774.4  199.03
  4830.9     201  5374.7  199.85  5690.9     201  5698.1  202.45    5705  201.04
  5712.2  203.68  5740.5  205.37  5747.4   203.3  5832.4  205.05  5860.7  201.27
  5910.4     201  5952.9  204.79    6017  205.28  6029.6  205.56  6108.2   206.1
  6207.3  200.95  6235.6  206.96  6377.2  211.99  6638.9  218.04    6758  215.91
#Mann= 7 ,-1 , 0
  3639.3     .11       0  4333.4     .15       0  4365.2     .11       0
  4483.2    .015       0  5712.2     .11       0    6017    .125       0
  6029.6     .11       0
Bank Sta=4483.2,5712.2
XS Rating Curve= 0 ,0
Exp/Cntr=0.3,0.1

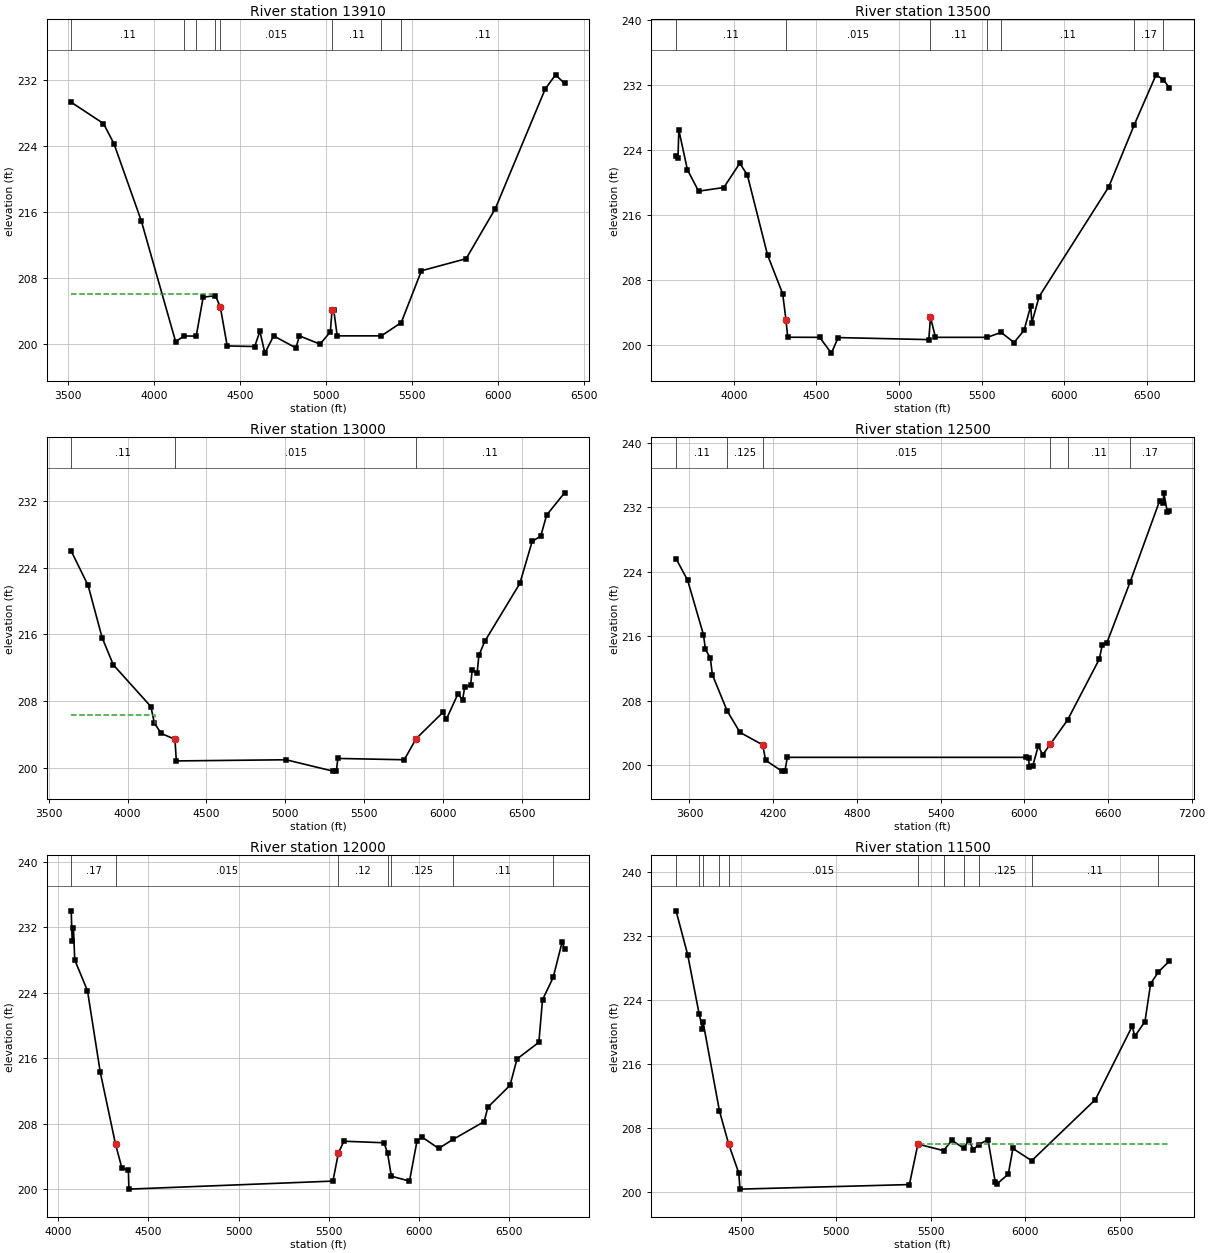
Type RM Length L Ch R = 1 ,13910   ,410,410,410
BEGIN DESCRIPTION:
WEIRS CREEK 28.0
END DESCRIPTION:
XS GIS Cut Line= 3
      3804234.04     10161143.22      3804226.85      10162624.8
      3804188.78     10164013.78
#Sta/Elev= 30
  3518.4  229.28  3706.3   226.7  3767.2  224.26  3926.3  214.92  4126.3  200.28
  4174.4  200.99  4245.9  200.97  4286.3  205.68    4358  205.87  4386.3  204.46
  4426.3  199.78  4586.3  199.71  4616.3  201.57  4645.5  198.91  4696.3     201
  4826.3  199.54  4846.3     201  4966.3     200  5026.3  201.47  5036.3  204.09
  5046.3  204.13  5066.3     201  5323.1     201  5438.8   202.6  5556.5  208.88
  5816.6  210.34  5986.6  216.41  6276.7  230.88  6336.8   232.6  6389.5  231.56
#Mann= 8 ,-1 , 0
  3518.4     .11       0  4174.4     .15       0  4245.9     .11       0
    4358     .15       0  4386.3    .015       0  5036.3     .11       0
  5323.1     .15       0  5438.8     .11       0
#XS Ineff= 2 , 0
       0  4336.3  206.05               0
Permanent Ineff=
       F       F
Bank Sta=4386.3,5036.3
XS Rating Curve= 0 ,0
Exp/Cntr=0.3,0.1

Type RM Length L Ch R = 1 ,13500   ,500,500,500
BEGIN DESCRIPTION:
WEIRS CREEK 27.0
END DESCRIPTION:
XS GIS Cut Line= 3
      3804125.54     10161117.16      3803871.47     10162442.43
      3804117.85     10164061.08
#Sta/Elev= 30
  3650.6  223.32  3662.3  223.04  3667.4  226.47  3719.4  221.58    3787  218.95
  3939.7   219.4  4036.5  222.38  4082.2  220.94  4204.4  211.12  4296.1  206.35
  4316.4  203.08  4326.6  201.01  4520.1     201  4590.8  199.06  4632.1  200.97
  5180.7  200.72  5190.8  203.45  5221.2     201    5535     201  5618.5  201.61
  5696.6  200.36  5757.3  201.86  5797.7  204.85  5804.7   202.8  5848.3  205.99
  6269.9  219.47  6424.9  227.12  6556.4  233.24    6601  232.64  6637.3  231.63
#Mann= 7 ,-1 , 0
  3650.6     .11       0  4316.4    .015       0  5190.8     .11       0
    5535     .15       0  5618.5     .11       0  6424.9     .17       0
    6601     .11       0
Bank Sta=4316.4,5190.8
XS Rating Curve= 0 ,0
Exp/Cntr=0.3,0.1

Type RM Length L Ch R = 1 ,13000   ,500,500,500
BEGIN DESCRIPTION:
WEIRS CREEK 26.0
END DESCRIPTION:
XS GIS Cut Line= 3
      3804068.96     10161097.17      3803413.86     10162285.92
      3803817.85     10164011.05
#Sta/Elev= 30
  3642.7  225.98  3749.9  221.86  3838.7  215.62  3909.8  212.36  4148.2  207.36
    4170  205.39  4213.6  204.15  4300.7  203.45  4309.4  200.86  5005.3     201
  5302.7  199.64  5324.2  199.64    5334  201.16    5755     201  5830.5  203.53
  6000.4  206.68  6022.1  205.85  6095.6  208.89  6124.8  208.14    6138  209.66
  6175.4   209.9  6186.4  211.77  6217.2  211.37  6228.1  213.48  6265.4  215.17
  6488.1   222.1  6566.4  227.15  6620.6  227.76  6657.9  230.28  6771.8  232.95
#Mann= 3 ,-1 , 0
  3642.7     .11       0  4300.7    .015       0  5830.5     .11       0
#XS Ineff= 2 , 0
       0  4175.7  206.33  6000.4       0  206.68
Permanent Ineff=
       F       F
Bank Sta=4300.7,5830.5
XS Rating Curve= 0 ,0
Exp/Cntr=0.3,0.1

Type RM Length L Ch R = 1 ,12500   ,500,500,500
BEGIN DESCRIPTION:
WEIRS CREEK 25.0
END DESCRIPTION:
XS GIS Cut Line= 3
      3803990.89     10161076.26       3802950.4     10162151.29
      3803667.85     10164061.07
#Sta/Elev= 30
  3503.9  225.65  3587.2  222.96  3700.4  216.21  3714.6   214.4  3749.8  213.31
    3764  211.26  3869.8  206.78    3962   204.1  4124.6  202.55    4146  200.63
  4262.4  199.29  4284.2  199.29  4301.6     201  6014.6     201  6030.6  200.93
    6036   199.8  6060.9  199.96  6100.1   202.4  6132.1  201.32  6185.5  202.61
  6309.9  205.63  6537.6  213.19  6559.4     215  6591.4  215.19  6759.4   222.8
  6969.8  232.82  6994.7  232.56  7000.1  233.82    7025  231.43  7040.1  231.56
#Mann= 6 ,-1 , 0
  3503.9     .11       0  3869.8    .125       0  4124.6    .015       0
  6185.5     .17       0  6309.9     .11       0  6759.4     .17       0
Bank Sta=4124.6,6185.5
XS Rating Curve= 0 ,0
Exp/Cntr=0.3,0.1

Type RM Length L Ch R = 1 ,12000   ,500,500,500
BEGIN DESCRIPTION:
WEIRS CREEK 24.0
END DESCRIPTION:
XS GIS Cut Line= 3
       3801811.3     10161520.05      3802458.88     10162183.08
       3802704.4     10163972.11
#Sta/Elev= 30
  4073.2     234  4078.5  230.33  4085.7  231.88  4092.7  228.01  4163.4  224.24
  4234.1   214.3    4319  205.47  4354.3  202.57  4389.7  202.38  4392.8  200.02
  5522.8     201  5553.1  204.43  5583.4  205.87  5805.5  205.68  5825.1  204.45
  5846.3   201.6  5946.8     201  5988.8  205.94  6017.4  206.36  6108.3  204.99
  6188.3  206.09  6360.6  208.27  6380.8  210.02  6503.6  212.69  6542.3  215.91
  6663.4  217.95  6683.6  223.14  6742.8  225.87    6792  230.17  6805.8  229.37
#Mann= 7 ,-1 , 0
  4073.2     .17       0    4319    .015       0  5553.1     .12       0
  5825.1     .11       0  5846.3    .125       0  6188.3     .11       0
  6742.8     .17       0
#XS Ineff= 2 , 0
       0                  5583.4       0  205.87
Permanent Ineff=
       F       F
Bank Sta=4319,5553.1
XS Rating Curve= 0 ,0
Exp/Cntr=0.3,0.1

Type RM Length L Ch R = 1 ,11500   ,500,500,500
BEGIN DESCRIPTION:
WEIRS CREEK 23.0
END DESCRIPTION:
XS GIS Cut Line= 3
      3801681.11     10161577.35      3801991.84     10162361.63
      3802652.33       10163993.
#Sta/Elev= 30
  4156.4  235.18  4217.5  229.71  4277.9  222.31  4295.9   220.4  4299.4  221.21
  4385.3  210.13  4433.7     206  4487.7  202.32  4493.5  200.33  5387.8   200.9
  5432.7  205.97  5568.1  205.15  5612.3  206.45  5675.8  205.42  5700.8  206.51
  5724.9  205.26  5752.6   205.9  5802.6  206.52  5840.9   201.2  5850.8     201
  5909.9  202.21    5934  205.42  6033.1  203.89  6369.5  211.55  6563.7  220.73
  6577.4  219.46    6631  221.32  6660.8  226.06  6702.3  227.53    6760   228.9
#Mann= 11 ,-1 , 0
  4156.4     .17       0  4277.9     .11       0  4299.4     .17       0
  4385.3     .11       0  4433.7    .015       0  5432.7     .11       0
  5568.1    .125       0  5675.8     .11       0  5752.6    .125       0
  6033.1     .11       0  6702.3     .17       0
#XS Ineff= 2 , 0
       0                  5441.7       0  206.03
Permanent Ineff=
       F       F
Bank Sta=4433.7,5432.7
XS Rating Curve= 0 ,0
Exp/Cntr=0.3,0.1

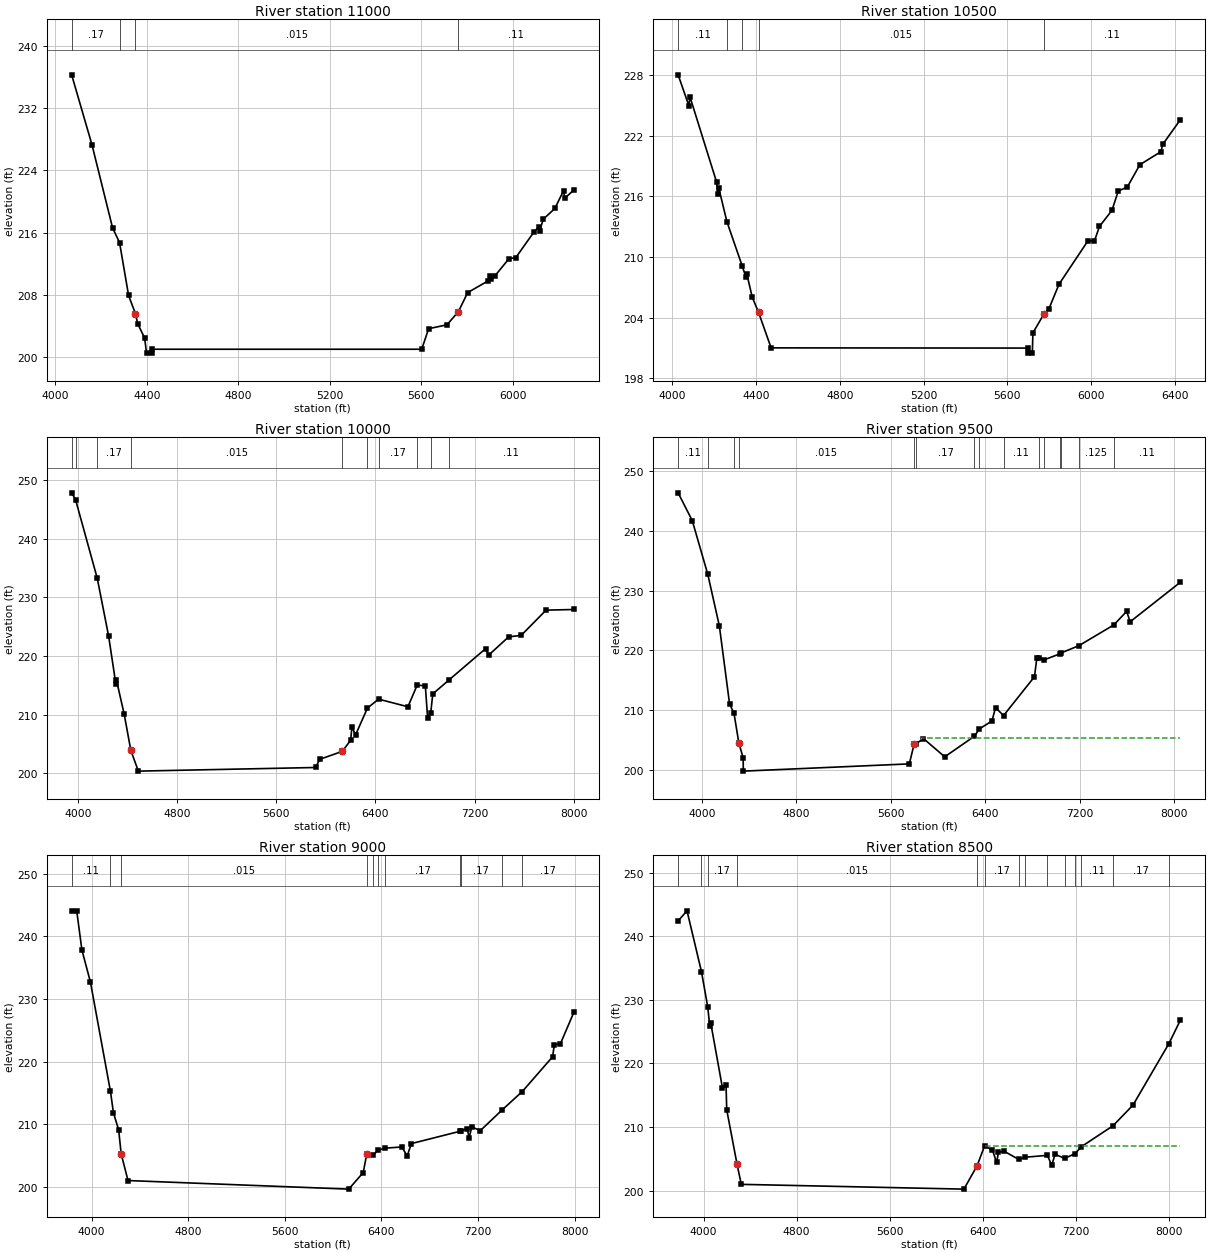
Type RM Length L Ch R = 1 ,11000   ,500,500,500
BEGIN DESCRIPTION:
WEIRS CREEK 22.0
END DESCRIPTION:
XS GIS Cut Line= 3
      3801550.91     10161572.13      3801520.03     10162500.91
       3801636.7     10163763.84
#Sta/Elev= 30
  4070.7  236.28  4159.7  227.28  4249.7  216.61  4280.3  214.72  4319.8  207.92
  4349.8  205.58  4359.8  204.27  4389.8  202.46  4398.7   200.5  4420.9   200.5
  4421.4     201  5602.7     201  5632.8  203.64  5713.2  204.14  5763.4  205.85
  5803.6  208.28  5893.9   209.8  5899.7  210.48  5904.7  210.06  5924.1  210.47
  5984.3  212.64  6014.5  212.79  6094.8  216.12  6113.8  216.67  6118.9  216.26
    6135  217.73  6185.2   219.1  6223.4  221.39  6228.4  220.41  6268.3  221.47
#Mann= 4 ,-1 , 0
  4070.7     .17       0  4280.3     .11       0  4349.8    .015       0
  5763.4     .11       0
Bank Sta=4349.8,5763.4
XS Rating Curve= 0 ,0
Exp/Cntr=0.3,0.1

Type RM Length L Ch R = 1 ,10500   ,500,500,500
BEGIN DESCRIPTION:
WEIRS CREEK 21.0
END DESCRIPTION:
XS GIS Cut Line= 3
      3801096.88     10161458.03      3801025.32     10162428.39
      3801542.41     10163757.23
#Sta/Elev= 30
    4027  228.01  4078.5  224.95  4083.5  225.84  4210.5  217.42  4216.7  216.27
  4221.7  216.77  4259.9  213.49  4333.5  209.08  4349.8  208.06  4354.8  208.34
    4381  206.02  4411.1  204.52  4471.2     201  5696.3  200.98  5696.8  200.48
    5719  200.48  5721.8  202.48  5775.5  204.39  5797.6  204.83  5846.6   207.3
  5985.3  211.61  6015.2  211.55  6039.7  213.01  6099.5  214.61  6129.6  216.52
  6172.5   216.9  6232.8  219.12  6333.5  220.41  6341.6  221.12  6425.9  223.56
#Mann= 5 ,-1 , 0
    4027     .11       0  4259.9     .17       0  4333.5     .11       0
  4411.1    .015       0  5775.5     .11       0
Bank Sta=4411.1,5775.5
XS Rating Curve= 0 ,0
Exp/Cntr=0.3,0.1

Type RM Length L Ch R = 1 ,10000   ,500,500,500
BEGIN DESCRIPTION:
WEIRS CREEK 20.0
END DESCRIPTION:
XS GIS Cut Line= 3
      3800867.85     10161361.08       3800530.6     10162355.87
      3800271.12     10165344.33
#Sta/Elev= 30
  3949.6  247.85  3980.8  246.71  4156.1  233.27    4248  223.39  4305.5   215.3
  4310.8  215.91  4373.7  210.06    4427   203.9  4487.5  200.38  5918.6     201
  5948.8  202.38  6132.2  203.75  6199.7  205.65  6209.7  207.87  6239.8  206.58
    6335  211.13  6424.7  212.66  6661.4  211.36  6736.3  215.05    6802  214.93
  6820.3  209.47  6845.1  210.26  6862.2  213.55    6989  215.86  7287.4  221.26
  7313.9  220.19  7474.5  223.29  7574.9  223.53  7775.6  227.84  7999.7  227.95
#Mann= 10 ,-1 , 0
  3949.6     .17       0  3980.8     .11       0  4156.1     .17       0
    4427    .015       0  6132.2     .17       0    6335     .11       0
  6424.7     .17       0  6736.3     .11       0  6845.1     .17       0
    6989     .11       0
Bank Sta=4427,6132.2
XS Rating Curve= 0 ,0
Exp/Cntr=0.3,0.1

Type RM Length L Ch R = 1 ,9500    ,500,500,500
BEGIN DESCRIPTION:
WEIRS CREEK 19.0
END DESCRIPTION:
XS GIS Cut Line= 3
      3800722.48     10161299.18      3800035.89     10162283.35
      3800097.51     10165335.63
#Sta/Elev= 30
    3800  246.32  3919.9  241.67    4051  232.72  4149.4  224.07  4235.7  211.06
  4273.2  209.49  4314.4  204.51    4351  202.03    4352  199.82  5757.9  201.03
  5797.9  204.27  5817.4  204.43  5877.9  205.26  6057.9  202.21  6309.4  205.65
  6351.9  206.88    6458   208.2    6488  210.44  6555.9   209.1  6818.1   215.6
  6838.1  218.77  6855.1  218.73  6899.7  218.42    7038  219.45  7042.5  219.56
  7194.9  220.79    7490  224.25  7598.3  226.51  7628.3  224.78  8052.9  231.37
#Mann= 15 ,-1 , 0
    3800     .11       0    4051     .17       0  4273.2     .11       0
  4314.4    .015       0  5797.9     .15       0  5817.4     .17       0
  6309.4     .11       0  6351.9     .17       0  6555.9     .11       0
  6855.1     .17       0  6899.7     .11       0    7038     .17       0
  7042.5     .11       0  7194.9    .125       0    7490     .11       0
#XS Ineff= 2 , 0
       0                  5857.9       0   205.3
Permanent Ineff=
       F       F
Bank Sta=4314.4,5797.9
XS Rating Curve= 0 ,0
Exp/Cntr=0.3,0.1

Type RM Length L Ch R = 1 ,9000    ,500,500,500
BEGIN DESCRIPTION:
WEIRS CREEK 18.0
END DESCRIPTION:
XS GIS Cut Line= 3
      3800467.83     10161161.09       3799653.5     10161995.33
      3797832.38     10164371.41
#Sta/Elev= 30
  3834.2  244.08  3876.5  244.03    3919  237.84  3989.7  232.71  4155.4  215.28
  4180.7   211.8  4223.2  209.16  4244.3  205.31  4300.9  201.03  6129.4  199.66
  6249.3  202.31  6278.4  205.25  6334.1  205.12  6371.4  205.89  6432.6   206.2
  6569.6  206.39  6612.9  204.94  6648.2  206.93  7054.4  208.91  7055.6  208.92
  7111.4  209.33  7125.9  207.82  7148.7  209.59  7219.4     209  7395.9  212.23
  7566.7  215.24  7817.6  220.78  7832.2  222.72    7882  222.84  7993.7  227.88
#Mann= 11 ,-1 , 0
  3834.2     .11       0  4155.4     .17       0  4244.3    .015       0
  6278.4     .11       0  6334.1     .17       0  6371.4     .11       0
  6432.6     .17       0  7054.4     .11       0  7055.6     .17       0
  7395.9     .11       0  7566.7     .17       0
Bank Sta=4244.3,6278.4
XS Rating Curve= 0 ,0
Exp/Cntr=0.3,0.1

Type RM Length L Ch R = 1 ,8500    ,500,500,500
BEGIN DESCRIPTION:
WEIRS CREEK 17.0
END DESCRIPTION:
XS GIS Cut Line= 3
      3800349.25     10160986.64      3799313.07     10161629.12
       3797702.4     10164275.39
#Sta/Elev= 30
  3780.8   242.4  3857.3  243.98  3981.8   234.4  4035.1   228.9  4053.1  225.87
  4061.7  226.32  4162.1  216.13  4192.8  216.54  4198.7  212.71  4287.3  204.17
  4323.7     201  6237.8  200.25  6350.6  203.91  6415.1  207.02  6482.3  206.41
  6519.1  204.44  6534.6  206.03  6583.1  206.21  6709.4  204.91  6763.4  205.26
  6955.6  205.56  6992.4  203.97  7020.8  205.73  7103.2  205.08  7192.4  205.82
  7248.5  206.93  7519.6  210.21    7691  213.45  8000.3  223.13  8097.9  226.78
#Mann= 14 ,-1 , 0
  3780.8     .17       0  3981.8     .11       0  4035.1     .17       0
  4287.3    .015       0  6350.6     .11       0  6415.1     .17       0
  6709.4     .15       0  6763.4     .11       0  6955.6     .17       0
  7103.2     .11       0  7192.4     .17       0  7248.5     .11       0
  7519.6     .17       0  8000.3     .11       0
#XS Ineff= 2 , 0
       0                  6418.3       0   207.1
Permanent Ineff=
       F       F
Bank Sta=4287.3,6350.6
XS Rating Curve= 0 ,0
Exp/Cntr=0.3,0.1