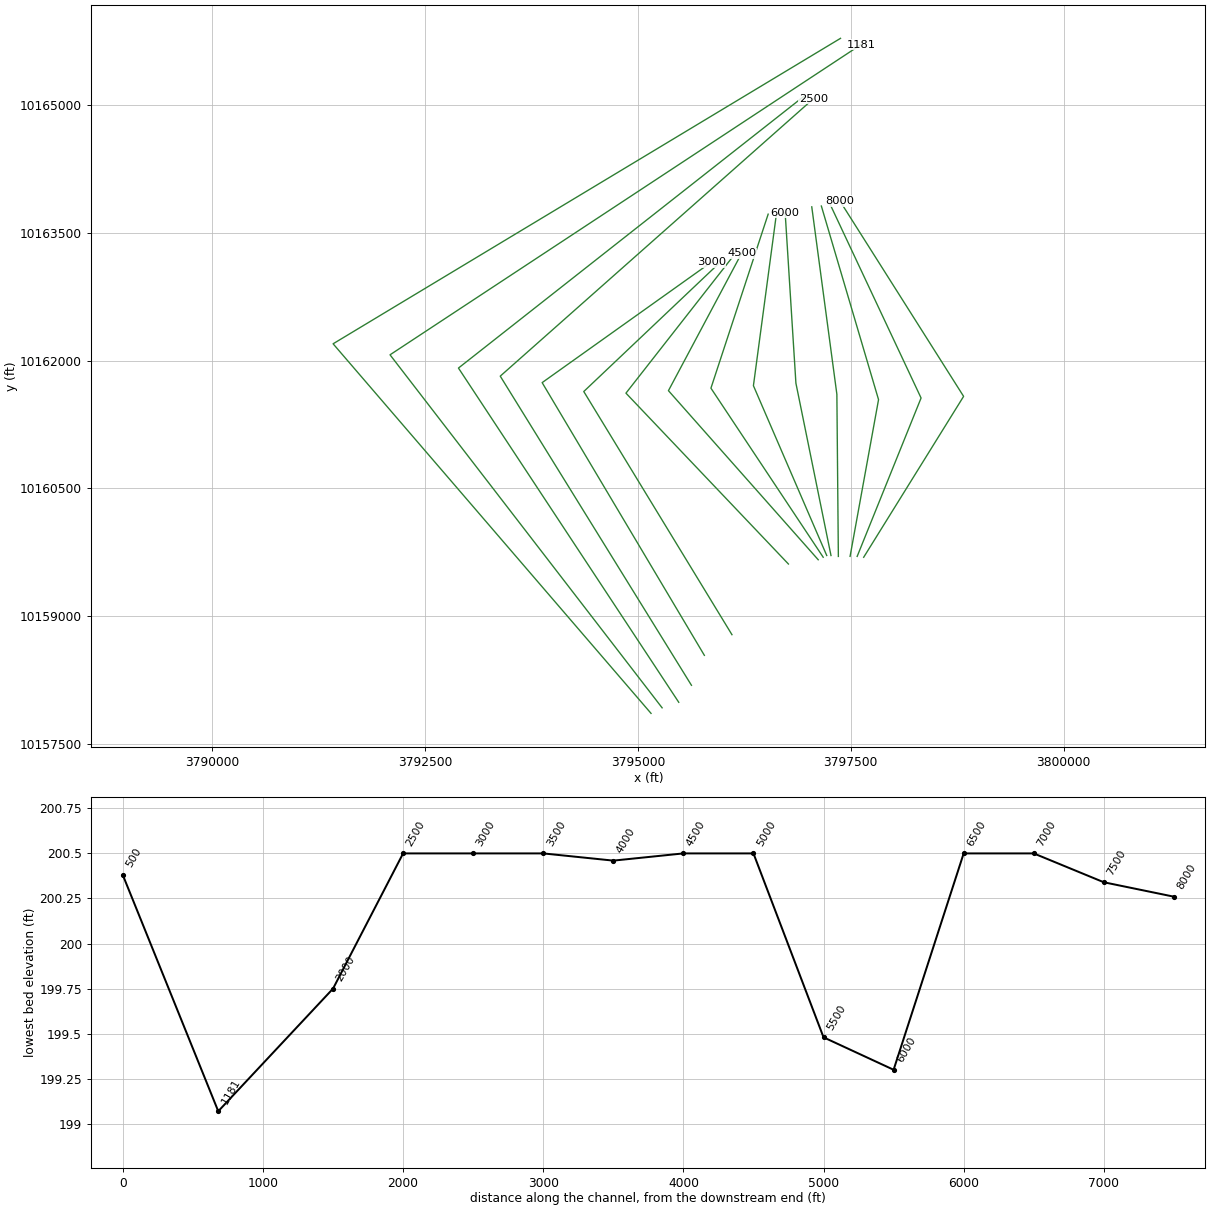
HEC-RAS study WEIRS CREEK.prj: WEIRS CREEK Base Level Engineering

--- WEIRS CREEK.g01 (geometry) --- (continued)

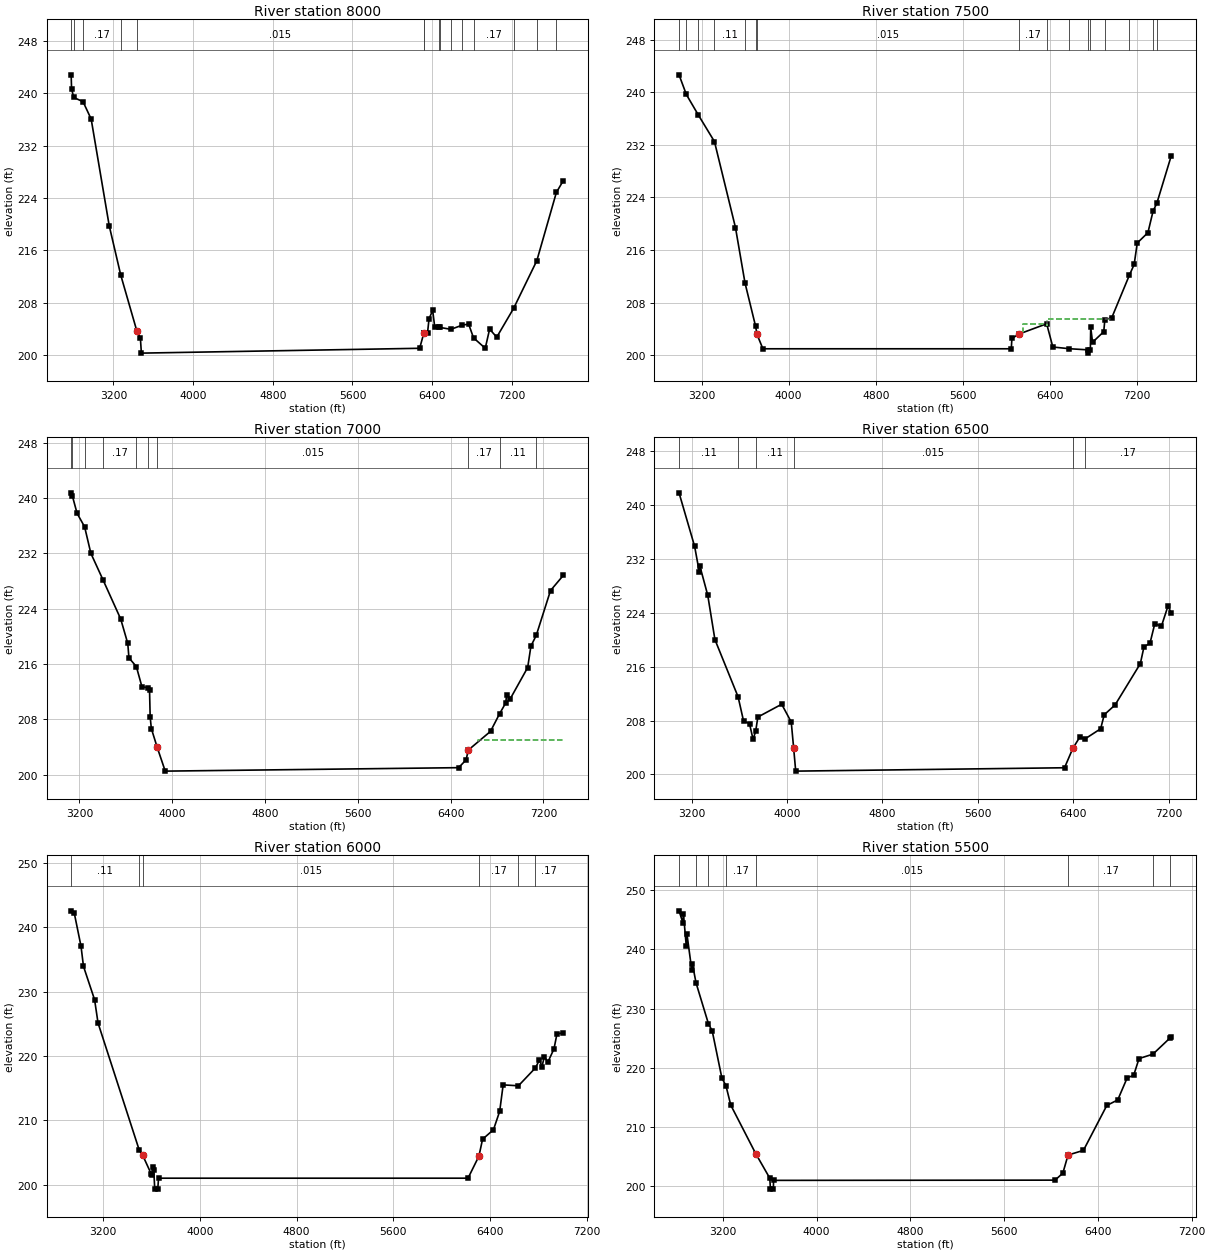
Type RM Length L Ch R = 1 ,8000    ,500,500,500
BEGIN DESCRIPTION:
WEIRS CREEK 16.0
END DESCRIPTION:
XS GIS Cut Line= 3
       3797651.9     10159690.33      3798825.84     10161580.43
      3797372.72     10163875.84
#Sta/Elev= 30
    2775  242.82  2779.3  240.69  2800.7  239.36  2894.4  238.71    2976  236.06
  3157.2  219.75  3273.2  212.19  3434.7  203.65  3470.4  202.55  3480.3  200.26
    6275     201  6317.3  203.36  6317.9  203.37  6353.8  203.35  6369.1  205.51
  6405.5   206.8  6426.7  204.19  6469.6  204.24  6475.1   204.2  6588.7   203.9
  6702.3  204.54  6766.6   204.7  6815.8   202.6  6933.5     201  6977.3  203.93
  7048.8   202.7  7218.5  207.11  7451.5   214.4  7647.9  224.84  7716.7  226.62
#Mann= 15 ,-1 , 0
    2775     .17       0  2800.7     .11       0  2894.4     .17       0
  3273.2     .11       0  3434.7    .015       0  6317.3    .065       0
  6317.9     .11       0  6469.6     .17       0  6475.1     .11       0
  6588.7     .17       0  6702.3     .11       0  6815.8     .17       0
  7218.5     .11       0  7451.5     .17       0  7647.9     .11       0
#XS Ineff= 2 , 0
       0                  6405.5       0   206.8
Permanent Ineff=
       F       F
Bank Sta=3434.7,6317.3
XS Rating Curve= 0 ,0
Exp/Cntr=0.3,0.1

Type RM Length L Ch R = 1 ,7500    ,500,500,500
BEGIN DESCRIPTION:
WEIRS CREEK 15.0
END DESCRIPTION:
XS GIS Cut Line= 3
      3797575.51     10159700.73      3798326.21     10161561.29
      3797258.97     10163833.87
#Sta/Elev= 30
  2993.7  242.64  3060.8  239.65  3168.5   236.6  3318.7   232.5  3511.7  219.43
  3599.1  211.02    3696  204.45  3709.7  203.18  3763.4     201  6043.4     201
  6049.3  202.58  6117.3  203.26  6368.3   204.8  6424.9  201.27  6577.1  201.01
  6743.5  200.84    6744  200.34  6769.3  200.84  6772.6  204.24  6789.5  201.99
  6892.2   203.6  6902.1  205.38  6966.3  205.74  7126.6  212.15  7171.4  213.82
  7199.8  217.08  7297.7  218.65  7345.4  221.95  7379.4  223.11  7510.7  230.27
#Mann= 16 ,-1 , 0
  2993.7     .17       0  3060.8     .11       0  3168.5     .17       0
  3318.7     .11       0  3599.1     .17       0    3696     .11       0
  3709.7    .015       0  6117.3     .17       0  6368.3     .11       0
  6577.1     .17       0  6743.5     .11       0  6769.3     .17       0
  6902.1     .11       0  7126.6     .17       0  7345.4     .11       0
  7379.4     .17       0
#XS Ineff= 2 ,-1
  6148.7  6373.8  204.79  6373.8  6955.1  205.55
Permanent Ineff=
       F       F
Bank Sta=3709.7,6117.3
XS Rating Curve= 0 ,0
Exp/Cntr=0.3,0.1

Type RM Length L Ch R = 1 ,7000    ,500,500,500
BEGIN DESCRIPTION:
WEIRS CREEK 14.0
END DESCRIPTION:
XS GIS Cut Line= 3
      3797492.19     10159700.76      3797826.58     10161542.15
      3797154.86     10163816.32
#Sta/Elev= 30
  3128.5  240.74  3139.9  240.24  3179.6  237.78  3244.7  235.82  3298.3     232
  3403.4  228.15  3555.7   222.5  3616.7  218.96  3626.8  216.88  3690.9  215.61
  3738.6  212.71  3791.5  212.54  3804.3   212.3  3809.8  208.35  3819.9  206.66
  3870.8  203.92  3939.7   200.5  6469.1     201    6534  202.13  6552.5  203.54
  6744.2  206.25  6822.9  208.81  6875.8  210.37  6882.6  211.51  6915.9     211
  7064.7  215.48  7092.7  218.58  7138.7  220.13  7261.6  226.61  7371.3  228.79
#Mann= 10 ,-1 , 0
  3128.5     .11       0  3139.9     .17       0  3244.7     .11       0
  3403.4     .17       0  3690.9     .11       0  3791.5     .17       0
  3870.8    .015       0  6552.5     .17       0  6822.9     .11       0
  7138.7     .17       0
#XS Ineff= 2 , 0
       0                  6633.9       0  204.96
Permanent Ineff=
       F       F
Bank Sta=3870.8,6552.5
XS Rating Curve= 0 ,0
Exp/Cntr=0.3,0.1

Type RM Length L Ch R = 1 ,6500    ,500,500,500
BEGIN DESCRIPTION:
WEIRS CREEK 13.0
END DESCRIPTION:
XS GIS Cut Line= 3
      3797354.46     10159700.21      3797336.98     10161605.03
      3797042.07     10163806.97
#Sta/Elev= 30
  3095.1  241.77    3226  233.82  3265.4     230  3270.4  230.88    3336  226.57
    3396  220.01  3590.5  211.51    3636  207.94    3686  207.54    3716   205.2
    3738  206.44    3756  208.52    3956  210.42    4036  207.78    4056  203.97
  4073.5   200.5  6327.8     201  6396.8  203.86  6458.1  205.61  6495.4  205.23
  6630.5  206.78  6660.7  208.86  6751.5  210.31  6963.4  216.44  6994.2  218.95
  7044.1  219.45  7084.5  222.35  7140.2  221.99  7195.5  224.99  7221.6  223.97
#Mann= 6 ,-1 , 0
  3095.1     .11       0  3590.5     .17       0    3738     .11       0
    4056    .015       0  6396.8     .11       0  6495.4     .17       0
Bank Sta=4056,6396.8
XS Rating Curve= 0 ,0
Exp/Cntr=0.3,0.1

Type RM Length L Ch R = 1 ,6000    ,500,500,500
BEGIN DESCRIPTION:
WEIRS CREEK 12.0
END DESCRIPTION:
XS GIS Cut Line= 3
      3797267.85     10159711.06      3796855.84     10161735.25
      3796729.53     10163737.27
#Sta/Elev= 30
  2934.3  242.55  2959.6  242.25    3016  237.04  3036.4  233.92  3128.2  228.74
  3156.8  225.12  3497.3  205.39  3526.2  204.56  3597.6  201.63  3606.9  201.43
  3612.1  202.67  3618.1  202.23    3626   199.3    3651   199.3  3657.5     201
  6218.2     201  6308.4  204.43  6338.5  207.06  6428.7  208.53  6480.2   211.4
  6508.8   215.5  6635.3  215.36  6776.3  218.15  6809.4  219.39  6829.5  218.32
  6849.5  219.85  6879.5  219.06  6929.6  221.11  6953.9  223.41    7006  223.61
#Mann= 6 ,-1 , 0
  2934.3     .11       0  3497.3     .17       0  3526.2    .015       0
  6308.4     .17       0  6635.3     .11       0  6776.3     .17       0
Bank Sta=3526.2,6308.4
XS Rating Curve= 0 ,0
Exp/Cntr=0.3,0.1

Type RM Length L Ch R = 1 ,5500    ,500,500,500
BEGIN DESCRIPTION:
WEIRS CREEK 11.0
END DESCRIPTION:
XS GIS Cut Line= 3
      3797217.84     10159711.09      3796356.69     10161705.96
      3796625.29     10163712.36
#Sta/Elev= 30
  2827.2  246.52  2859.7  244.54  2865.2  245.94  2888.7  240.63  2894.1  242.68
  2935.7  236.54  2941.1  237.57  2972.4  234.33  3077.7  227.45  3110.4   226.2
  3192.5  218.27  3227.2  216.97  3268.5  213.68  3480.7   205.5  3601.3  201.33
  3606.8  199.48    3632  199.48  3633.2  200.96  6034.3     201  6100.7  202.18
  6145.2  205.24  6276.4  206.03  6475.7  213.62    6569  214.56  6649.7   218.3
  6704.8  218.71  6750.6  221.55  6868.8  222.29  7017.1  225.07  7024.3  225.18
#Mann= 8 ,-1 , 0
  2827.2     .11       0  2972.4     .17       0  3077.7     .11       0
  3227.2     .17       0  3480.7    .015       0  6145.2     .17       0
  6868.8     .11       0  7017.1     .17       0
Bank Sta=3480.7,6145.2
XS Rating Curve= 0 ,0
Exp/Cntr=0.3,0.1

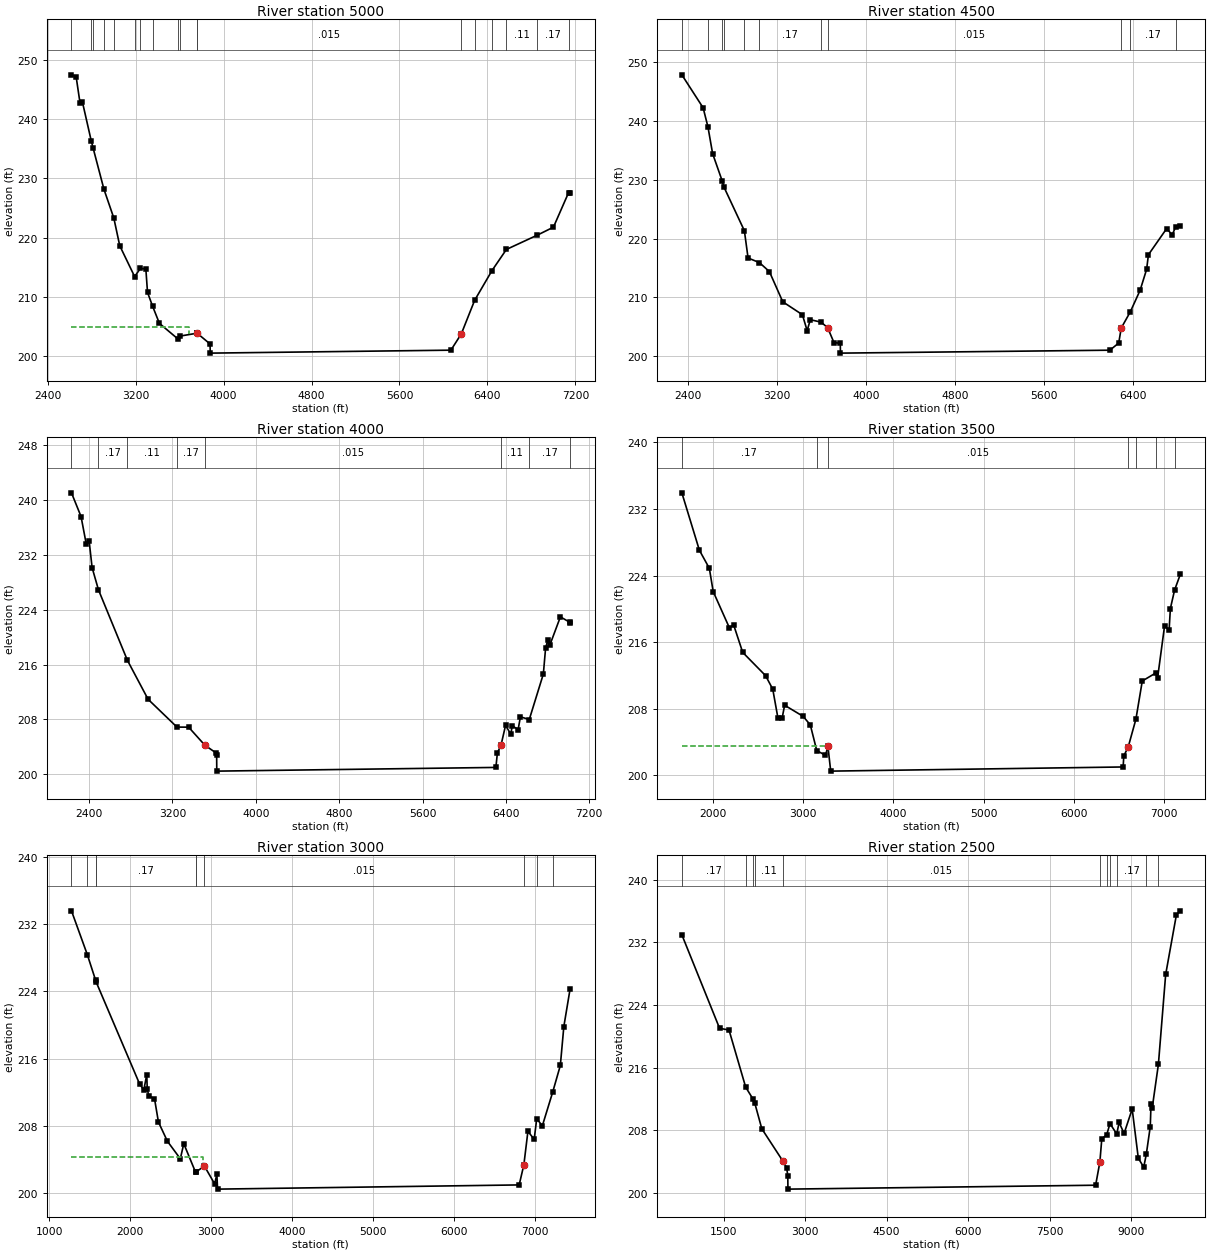
Type RM Length L Ch R = 1 ,5000    ,500,500,500
BEGIN DESCRIPTION:
WEIRS CREEK 10.0
END DESCRIPTION:
XS GIS Cut Line= 3
      3797176.23     10159691.02      3795857.55     10161676.75
      3796529.81     10163721.05
#Sta/Elev= 30
  2616.3  247.45  2658.5  247.16  2694.5  242.64  2715.6  242.89  2796.5  236.28
  2812.2  235.17  2911.6  228.15  3001.5  223.29  3055.4  218.62  3190.8  213.41
  3243.2  214.79  3292.9  214.69    3308  210.75  3354.3  208.41  3416.2  205.52
  3582.1  202.93    3602  203.37  3758.7  203.86    3762  203.82  3876.8  202.05
  3878.6   200.5  6067.8     201  6162.5  203.75  6283.7  209.41  6441.6  214.43
  6572.4  217.99  6855.4  220.42  7000.5  221.75  7138.3  227.58    7152  227.46
#Mann= 18 ,-1 , 0
  2616.3     .11       0  2796.5     .17       0  2812.2     .11       0
  2911.6     .17       0  3001.5     .11       0  3190.8     .17       0
  3243.2     .11       0  3354.3     .17       0  3582.1     .11       0
    3602     .17       0  3758.7     .11       0    3762    .015       0
  6162.5     .11       0  6283.7     .11       0  6441.6     .17       0
  6572.4     .11       0  6855.4     .17       0  7138.3     .11       0
#XS Ineff= 2 , 0
       0  3689.8  204.92               0
Permanent Ineff=
       F       F
Bank Sta=3762,6162.5
XS Rating Curve= 0 ,0
Exp/Cntr=0.3,0.1

Type RM Length L Ch R = 1 ,4500    ,500,500,500
BEGIN DESCRIPTION:
WEIRS CREEK 9.0
END DESCRIPTION:
XS GIS Cut Line= 3
      3797117.84     10159661.09       3795358.4     10161647.53
      3796217.87     10163261.11
#Sta/Elev= 30
  2346.4  247.89  2537.5  242.28  2581.1  239.01  2622.8  234.48  2708.1  229.87
  2724.6  228.79  2908.4  221.34  2941.5   216.7  3043.7  215.91    3133  214.39
  3253.5  209.24  3429.9  207.04  3472.6  204.33    3501  206.19  3597.1  205.78
  3656.6  204.84  3713.5   202.3  3770.4  202.17  3771.9   200.5  6193.7     201
    6273  202.22  6295.6  204.77  6377.6  207.55  6465.6  211.22  6523.8  214.77
  6540.1  217.26  6703.5   221.7  6754.1  220.65  6784.4  221.99  6828.2  222.18
#Mann= 11 ,-1 , 0
  2346.4     .11       0  2581.1     .17       0  2708.1     .11       0
  2724.6     .17       0  2908.4     .11       0  3043.7     .17       0
  3597.1     .11       0  3656.6    .015       0  6295.6     .11       0
  6377.6     .17       0  6784.4     .11       0
Bank Sta=3656.6,6295.6
XS Rating Curve= 0 ,0
Exp/Cntr=0.3,0.1

Type RM Length L Ch R = 1 ,4000    ,500,500,500
BEGIN DESCRIPTION:
WEIRS CREEK 8.0
END DESCRIPTION:
XS GIS Cut Line= 3
      3796767.85     10159611.07      3794859.26     10161618.32
      3796102.55     10163206.43
#Sta/Elev= 30
  2230.2  241.03  2322.2  237.57  2371.6   233.6  2399.9     234  2428.2  230.13
  2489.3  226.89  2767.2  216.61  2965.8  210.93  3242.9  206.88  3354.9  206.87
  3510.6  204.24  3616.6  203.13  3623.8  202.88    3625  200.46  6304.4     201
  6318.9  203.12  6354.2  204.28  6397.5  207.14  6447.3  205.84  6461.7  207.07
  6517.8  206.52  6540.2  208.38  6624.9  207.98  6760.1  214.62  6781.5  218.37
  6803.5  219.58  6824.3  218.91  6923.8  222.95  7011.2  222.18  7016.9  222.03
#Mann= 8 ,-1 , 0
  2230.2     .11       0  2489.3     .17       0  2767.2     .11       0
  3242.9     .17       0  3510.6    .015       0  6354.2     .11       0
  6624.9     .17       0  7011.2     .11       0
Bank Sta=3510.6,6354.2
XS Rating Curve= 0 ,0
Exp/Cntr=0.3,0.1

Type RM Length L Ch R = 1 ,3500    ,500,500,500
BEGIN DESCRIPTION:
WEIRS CREEK 7.0
END DESCRIPTION:
XS GIS Cut Line= 3
      3796104.47     10158780.88      3794363.67     10161637.45
      3795948.23     10163139.44
#Sta/Elev= 30
  1654.8  233.94  1849.2  227.04  1959.5  224.87  2002.1  222.08  2182.3  217.71
  2228.7  218.08  2329.4  214.77  2583.2  211.97  2662.6  210.35  2720.7  206.84
  2767.1   206.9  2794.2  208.42  2999.5  207.08  3078.9  206.06  3150.5  202.97
  3247.3   202.4  3274.5  203.46  3305.2   200.5  6547.7     201  6554.6  202.32
  6604.1  203.42  6689.3  206.75  6759.7  211.33  6907.4  212.28  6929.6  211.71
  7007.3  217.99    7057  217.41  7071.2  220.04  7118.1  222.26  7183.3   224.2
#Mann= 7 ,-1 , 0
  1654.8     .17       0  3150.5     .15       0  3274.5    .015       0
  6604.1    .125       0  6689.3    .125       0  6907.4     .11       0
  7118.1     .17       0
#XS Ineff= 2 , 0
       0  3268.7  203.54               0
Permanent Ineff=
       F       F
Bank Sta=3274.5,6604.1
XS Rating Curve= 0 ,0
Exp/Cntr=0.3,0.1

Type RM Length L Ch R = 1 ,3000    ,500,500,500
BEGIN DESCRIPTION:
WEIRS CREEK 6.0
END DESCRIPTION:
XS GIS Cut Line= 3
      3795780.39     10158538.24      3793874.73     10161742.02
      3795860.88     10163156.41
#Sta/Elev= 30
  1272.3  233.58    1468  228.38    1570  225.35  1579.8  225.07  2113.9  213.02
  2166.5  212.29  2203.5  214.11  2209.3  212.36  2230.7  211.54    2299  211.26
  2347.6  208.48  2458.6  206.19  2618.3  204.11  2661.2   205.9    2808  202.48
  2809.6  202.52  2916.3  203.24  3042.9  201.12  3070.2  202.27  3078.9   200.5
  6808.5     201  6866.3  203.38  6916.7  207.37  6994.1  206.42  7025.7  208.87
    7095  208.02    7223  212.03  7317.5   215.2  7360.9  219.83  7438.3   224.3
#Mann= 10 ,-1 , 0
  1272.3     .11       0    1468     .17       0    1570     .11       0
  1579.8     .17       0    2808     .11       0  2809.6     .17       0
  2916.3    .015       0  6866.3     .11       0  7025.7    .125       0
    7223     .11       0
#XS Ineff= 2 , 0
       0  2904.5  204.33               0
Permanent Ineff=
       F       F
Bank Sta=2916.3,6866.3
XS Rating Curve= 0 ,0
Exp/Cntr=0.3,0.1

Type RM Length L Ch R = 1 ,2500    ,500,500,500
BEGIN DESCRIPTION:
WEIRS CREEK 5.0
END DESCRIPTION:
XS GIS Cut Line= 3
      3795628.75     10158186.31      3793382.47     10161818.07
       3797059.3     10165075.17
#Sta/Elev= 30
   729.7  232.98  1424.2  221.04    1598  220.82  1905.1  213.52  2035.9  212.05
  2073.2  211.47    2202  208.21  2593.1  204.05  2659.4  203.25  2680.6   202.2
    2683   200.5  8349.3     201  8427.2  203.94  8463.1  206.94  8551.4  207.41
  8614.1  208.87  8738.1  207.54  8781.7  209.01  8873.7  207.61  9022.6  210.73
  9135.5  204.44  9235.1  203.31  9282.2  204.94  9355.5  208.48  9369.7  211.41
  9390.6  210.82  9505.2  216.43  9639.1  227.91  9837.3  235.55    9912  236.04
#Mann= 11 ,-1 , 0
   729.7     .17       0  1905.1     .11       0  2035.9     .17       0
  2073.2     .11       0  2593.1    .015       0  8427.2     .17       0
  8551.4     .17       0  8614.1     .11       0  8738.1     .17       0
  9282.2    .125       0  9505.2     .17       0
Bank Sta=2593.1,8427.2
XS Rating Curve= 0 ,0
Exp/Cntr=0.3,0.1

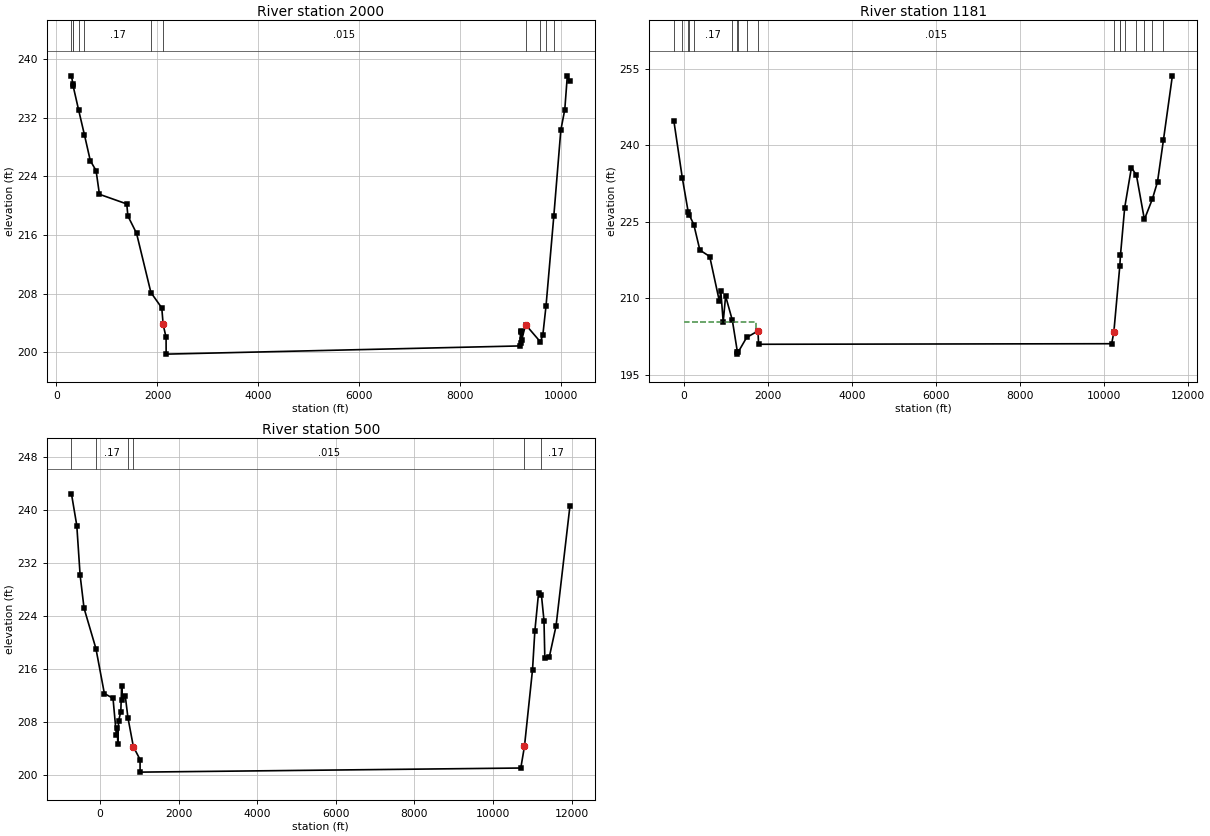
Type RM Length L Ch R = 1 ,2000    ,819,819,819
BEGIN DESCRIPTION:
WEIRS CREEK 4.0
END DESCRIPTION:
XS GIS Cut Line= 3
      3795479.47     10157986.62      3792891.58      10161913.1
      3796954.04     10165109.03
#Sta/Elev= 30
   297.4  237.74   325.5  236.63   331.6  236.32   440.3  233.04   555.1  229.66
   670.4  226.16   784.8   224.8   851.1  221.57  1392.6  220.25  1414.2  218.62
  1585.8  216.25  1870.5  208.16  2085.8  206.06  2112.8  203.81  2171.1  202.02
    2172  199.75  9182.6  200.87  9190.7  202.85  9197.1  201.31  9205.1   202.8
  9211.5  201.63  9290.1  203.78  9583.2  201.42  9631.7  202.37  9695.3  206.37
  9848.6  218.56  9987.7  230.32 10066.3  233.14   10116  237.69 10168.9  237.01
#Mann= 11 ,-1 , 0
   297.4     .17       0   325.5     .11       0   331.6     .17       0
   440.3     .11       0   555.1     .17       0  1870.5     .11       0
  2112.8    .015       0  9290.1     .17       0  9583.2     .17       0
  9695.3    .125       0  9848.6     .17       0
#XS Ineff= 2 , 0
       0                  9190.7       0  202.85
Permanent Ineff=
       F       F
Bank Sta=2112.8,9290.1
XS Rating Curve= 0 ,0
Exp/Cntr=0.3,0.1

Type RM Length L Ch R = 1 ,1181    ,681,681,681
BEGIN DESCRIPTION:
WEIRS CREEK 3.0
END DESCRIPTION:
XS GIS Cut Line= 3
      3795284.12     10157921.56      3792087.75     10162068.71
      3797617.81     10165711.05
#Sta/Elev= 30
    -236  244.73   -36.1  233.62   105.1   226.9     134  226.26     238  224.45
     382  219.45   616.8  218.19     845  209.48   880.4  211.36   937.6  205.38
   994.5  210.44  1154.7   205.7  1273.5  199.57    1274  199.07  1300.7  199.57
  1494.9  202.33  1764.5  203.61  1779.1     201 10177.7  201.11   10229  203.35
 10371.7  216.37 10387.1  218.44   10487  227.73 10647.6  235.61 10766.6  234.11
 10956.3  225.45 11146.1  229.45   11268  232.81 11409.1  241.01 11621.8  253.58
#Mann= 18 ,-1 , 0
    -236     .17       0   -36.1     .11       0   105.1     .17       0
     134     .11       0     238     .17       0  1154.7     .15       0
  1273.5     .11       0  1300.7     .15       0  1494.9     .11       0
  1764.5    .015       0   10229     .17       0 10371.7    .125       0
 10387.1     .11       0   10487     .17       0 10766.6     .11       0
 10956.3     .17       0 11146.1     .11       0 11409.1     .17       0
#XS Ineff= 2 , 0
       0  1729.2  205.37               0
Permanent Ineff=
       F       F
Bank Sta=1764.5,10229
XS Rating Curve= 0 ,0
Exp/Cntr=0.3,0.1

Type RM Length L Ch R = 1 ,500     ,0,0,0
BEGIN DESCRIPTION:
WEIRS CREEK 1.0
END DESCRIPTION:
XS GIS Cut Line= 3
      3795153.92     10157856.46      3791418.92     10162198.19
      3797379.78     10165786.56
#Sta/Elev= 30
  -727.2  242.37  -591.7  237.59  -507.2   230.1  -407.3  225.12  -104.8  219.02
   109.9  212.24     330  211.52   414.5  206.02   443.1  206.98   450.7  204.64
   471.6  208.09   528.6  209.52   549.5  213.43   563.7  211.25   641.7  211.88
     709  208.62   847.9  204.22    1018  202.28  1019.1  200.38 10706.4     201
 10799.8  204.27 11005.3  215.86 11063.6  221.65 11158.8  227.42   11230  227.17
 11296.7  223.25   11318  217.55 11434.5  217.82 11603.5  222.44 11957.6  240.57
#Mann= 6 ,-1 , 0
  -727.2     .11       0  -104.8     .17       0     709     .11       0
   847.9    .015       0 10799.8     .11       0   11230     .17       0
Bank Sta=847.9,10799.8
XS Rating Curve= 0 ,0
Exp/Cntr=0.3,0.1

Chan Stop Cuts=-1
Use User Specified Reach Order=0
Composite Channel Slope=5