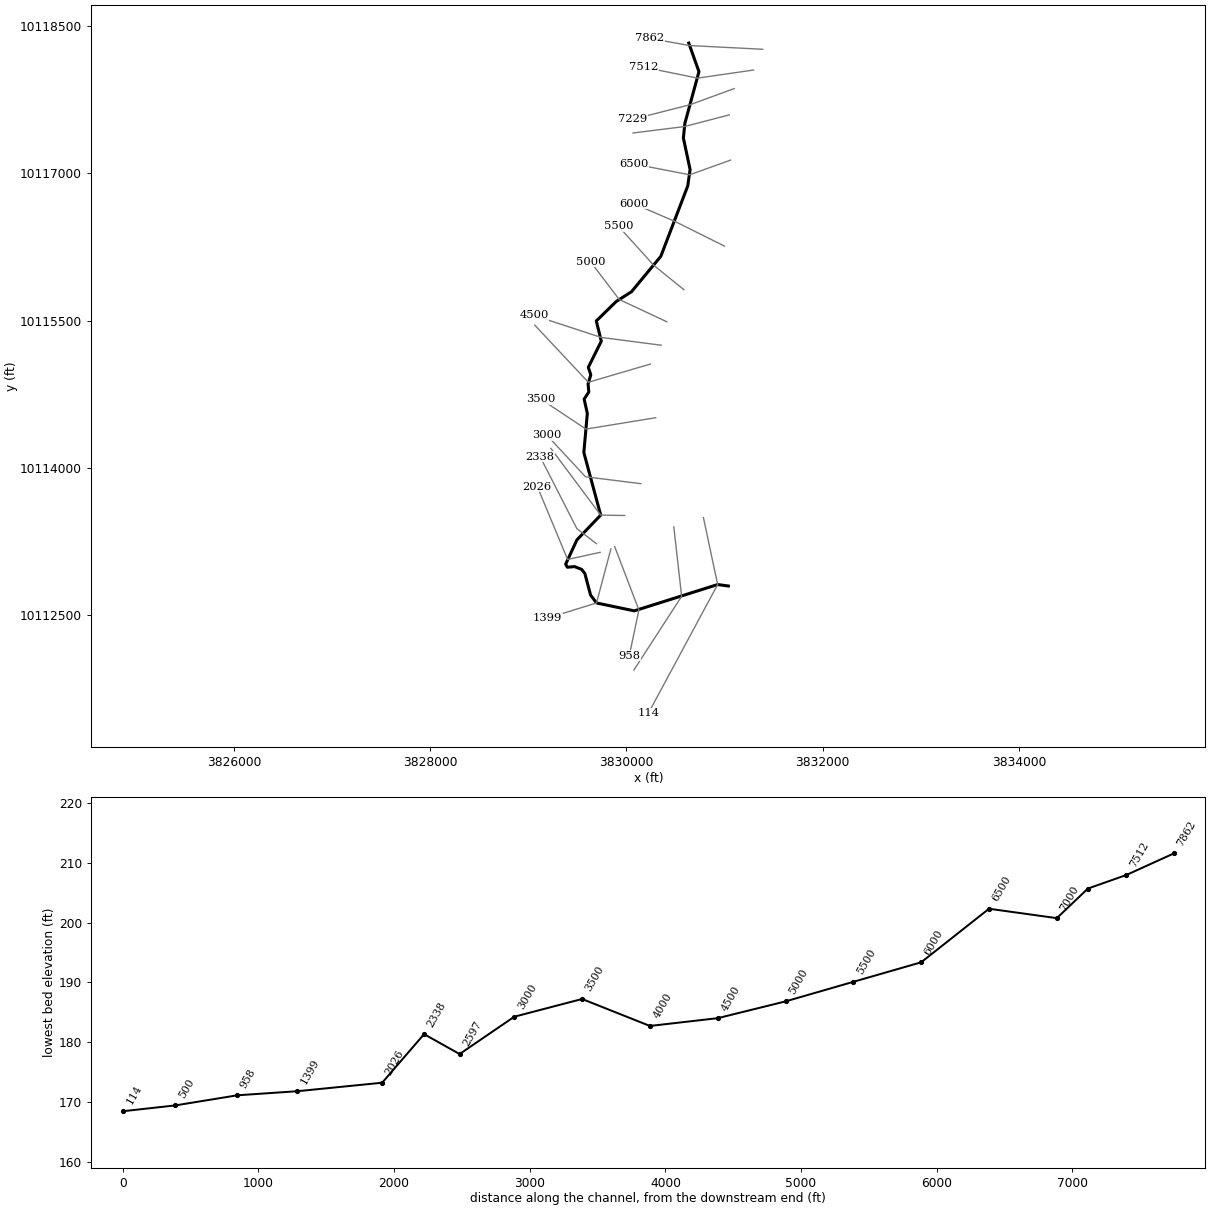
--- WEST BRANCH ALLIGATOR CREEK.prj (project) ---

Proj Title=WEST BRANCH ALLIGATOR CREEK Base Level Engineering
Current Plan=p01
Default Exp/Contr=0.3,0.1
English Units
Geom File=g01
Flow File=f01
Plan File=p01
Y Axis Title=Elevation
X Axis Title(PF)=Main Channel Distance
X Axis Title(XS)=Station
BEGIN DESCRIPTION:
WEST BRANCH ALLIGATOR CREEK
END DESCRIPTION:
DSS File=dss
DSS Export Rating Curves= 0
DSS Export Rating Curve Sorted= 0
DSS Export Volume Flow Curves= 0
DXF OffsetX= 0
DXF OffsetY= 0
DXF ScaleX= 1
DXF ScaleY= 10

--- WEST BRANCH ALLIGATOR CREEK.p01 (plan) ---

Plan Title=Multiple Run
Program Version=4.10
Short Identifier=Multiple Run
Geom File=g01
Flow File=f01
Subcritical Flow
K Sum by GR= 0
Std Step Tol= 0.01
Critical Tol= 0.01
Num of Std Step Trials= 20
Max Error Tol= 0.3
Flow Tol Ratio= 0.001
Split Flow NTrial= 30
Split Flow Tol= 0.02
Split Flow Ratio= 0.02
Log Output Level= 0
Friction Slope Method= 1
Unsteady Friction Slope Method= 2
Unsteady Bridges Friction Slope Method= 1
Parabolic Critical Depth
Global Vel Dist= 1 , 1 , 1
Global Log Level= 0
CheckData=True
Encroach Param=-1 ,0,0, 0
BEGIN DESCRIPTION:
Multiple Run
END DESCRIPTION:
Computation Interval=1HOUR
Output Interval=1HOUR
Run HTab= 0
Run UNet= 0
Run PostProcess= 0
Run WQNet= 0
UNET Theta= 1
UNET Theta Warmup= 1
UNET ZTol= 0.02
UNET ZSATol= 0.05
UNET MxIter= 20
UNET MaxInSteps= 0
UNET DtIC= 0
UNET DtMin= 0
UNET MaxCRTS= 20
UNET WFStab= 2
UNET SFStab= 1
UNET WFX= 1
UNET SFX= 1
UNET DSS MLevel= 4
UNET DZMax Abort= 100
UNET Convert EG Bridges= 0
UNET Use Existing IB Tables=-1
UNET Froude Reduction=False
UNET Froude Limit= 1
UNET Froude Power= 10
UNET Time Slicing=0,0, 5
UNET Junction Losses=0
Instantaneous Interval=1HOUR
DSS File=dss
Write IC File= 0
Write IC File at Sim End=0
Echo Input=False
Echo Parameters=False
Echo Output=False
Write Detailed= 0
WQ AD Non Conservative
WQ ULTIMATE=-1
WQ Max Comp Step=1HOUR
WQ Output Interval=15MIN
WQ Output Selected Increments= 0
WQ Output face flow=0
WQ Output face velocity=0
WQ Output face area=0
WQ Output face dispersion=0
WQ Output cell volume=0
WQ Output cell surface area=0
WQ Output cell continuity=0
WQ Output cumulative cell continuity=0
WQ Output face conc=0
WQ Output face dconc_dx=0
WQ Output face courant=0
WQ Output face peclet=0
WQ Output face adv mass=0
WQ Output face disp mass=0
WQ Output cell mass=0
WQ Output cell source sink temp=0
WQ Output cell source sink nsm=0
WQ Output MaxMinRange=-1
WQ Daily Max Min Mean=-1
WQ Daily Range=0
WQ Daily Time=0
WQ Create Restart=0
WQ Fixed Restart=0
WQ System Summary=0
WQ Use Fixed Temperature=0
Sorting and Armoring Iterations= 10
XS Update Threshold= 0.02
Hydraulics Update Threshold= 0.02
Energy Slope Method= 1
Volume Change Method= 0
XS Weighting Method= 0
Number of US Weighted Cross Sections= 1
Number of DS Weighted Cross Sections= 1
Upstream XS Weight=0.25
Main XS Weight=0.5
Downstream XS Weight=0.25
Number of DS XS's Weighted with US Boundary= 1
Upstream Boundary Weight= 1
Weight of XSs Associated with US Boundary= 0
Number of US XS's Weighted with DS Boundary= 1
Downstream Boundary Weight= 0.5
Weight of XSs Associated with DS Boundary= 0.5
Sediment Output Level= 4
Mass or Volume Output= 0
Output Increment Type= 1
Profile and TS Output Increment= 10
XS Output Flag= 0
XS Output Increment= 10
Disregard all LS=0
Disregard all Conn=0
Disregard all Breaches=0
Disregard all Pumps=0

--- WEST BRANCH ALLIGATOR CREEK.f01 (steady flow) ---

Flow Title=Multiple
Program Version=4.10
Number of Profiles= 7
Profile Names=10-year,25-year,50-year,1pct_min,100-year,1pct_plu,500-year
River Rch & RM=WEST BRANCH ALLI,Reach-1         ,7862
     214     269     347     148     447    1350     762
River Rch & RM=WEST BRANCH ALLI,Reach-1         ,7000
     521     695     929     410    1238    3739    2264
River Rch & RM=WEST BRANCH ALLI,Reach-1         ,1399
     985    1363    1868     842    2542    7677    4866
Boundary for River Rch & Prof#=WEST BRANCH ALLI,Reach-1         , 1
Up Type= 0
Dn Type= 3
Dn Slope=0.005
Boundary for River Rch & Prof#=WEST BRANCH ALLI,Reach-1         , 2
Up Type= 0
Dn Type= 3
Dn Slope=0.005
Boundary for River Rch & Prof#=WEST BRANCH ALLI,Reach-1         , 3
Up Type= 0
Dn Type= 3
Dn Slope=0.005
Boundary for River Rch & Prof#=WEST BRANCH ALLI,Reach-1         , 4
Up Type= 0
Dn Type= 3
Dn Slope=0.005
Boundary for River Rch & Prof#=WEST BRANCH ALLI,Reach-1         , 5
Up Type= 0
Dn Type= 3
Dn Slope=0.005
Boundary for River Rch & Prof#=WEST BRANCH ALLI,Reach-1         , 6
Up Type= 0
Dn Type= 3
Dn Slope=0.005
Boundary for River Rch & Prof#=WEST BRANCH ALLI,Reach-1         , 7
Up Type= 0
Dn Type= 3
Dn Slope=0.005
DSS Import GetInterval= 0
DSS Import GetPeak= 0
DSS Import FillOption= 0

--- WEST BRANCH ALLIGATOR CREEK.g01 (geometry) ---

Geom Title=Existing Conditions
Program Version=4.10

River Reach=WEST BRANCH ALLI,Reach-1
Reach XY= 30
      3830635.23     10118326.96      3830739.02     10118035.77
      3830595.48     10117509.44      3830580.29      10117359.7
      3830648.65     10117038.52      3830624.77     10116871.42
      3830350.25     10116154.19      3830051.86     10115793.94
      3829894.52     10115693.03       3829692.7     10115495.55
       3829743.7     10115289.39      3829611.32     10115023.55
      3829636.61     10114946.68      3829609.01     10114855.01
       3829616.3     10114771.68       3829568.9     10114699.28
       3829601.2     10114553.45      3829565.72     10114155.39
      3829737.65     10113517.51      3829494.97     10113265.22
      3829380.36     10113016.99      3829398.07     10112986.26
      3829470.47     10112993.03      3829543.38     10112964.39
       3829576.2      10112922.2      3829634.49     10112702.31
       3829694.9     10112622.45      3830079.62     10112541.89
      3830929.62     10112809.95      3831038.92     10112795.24

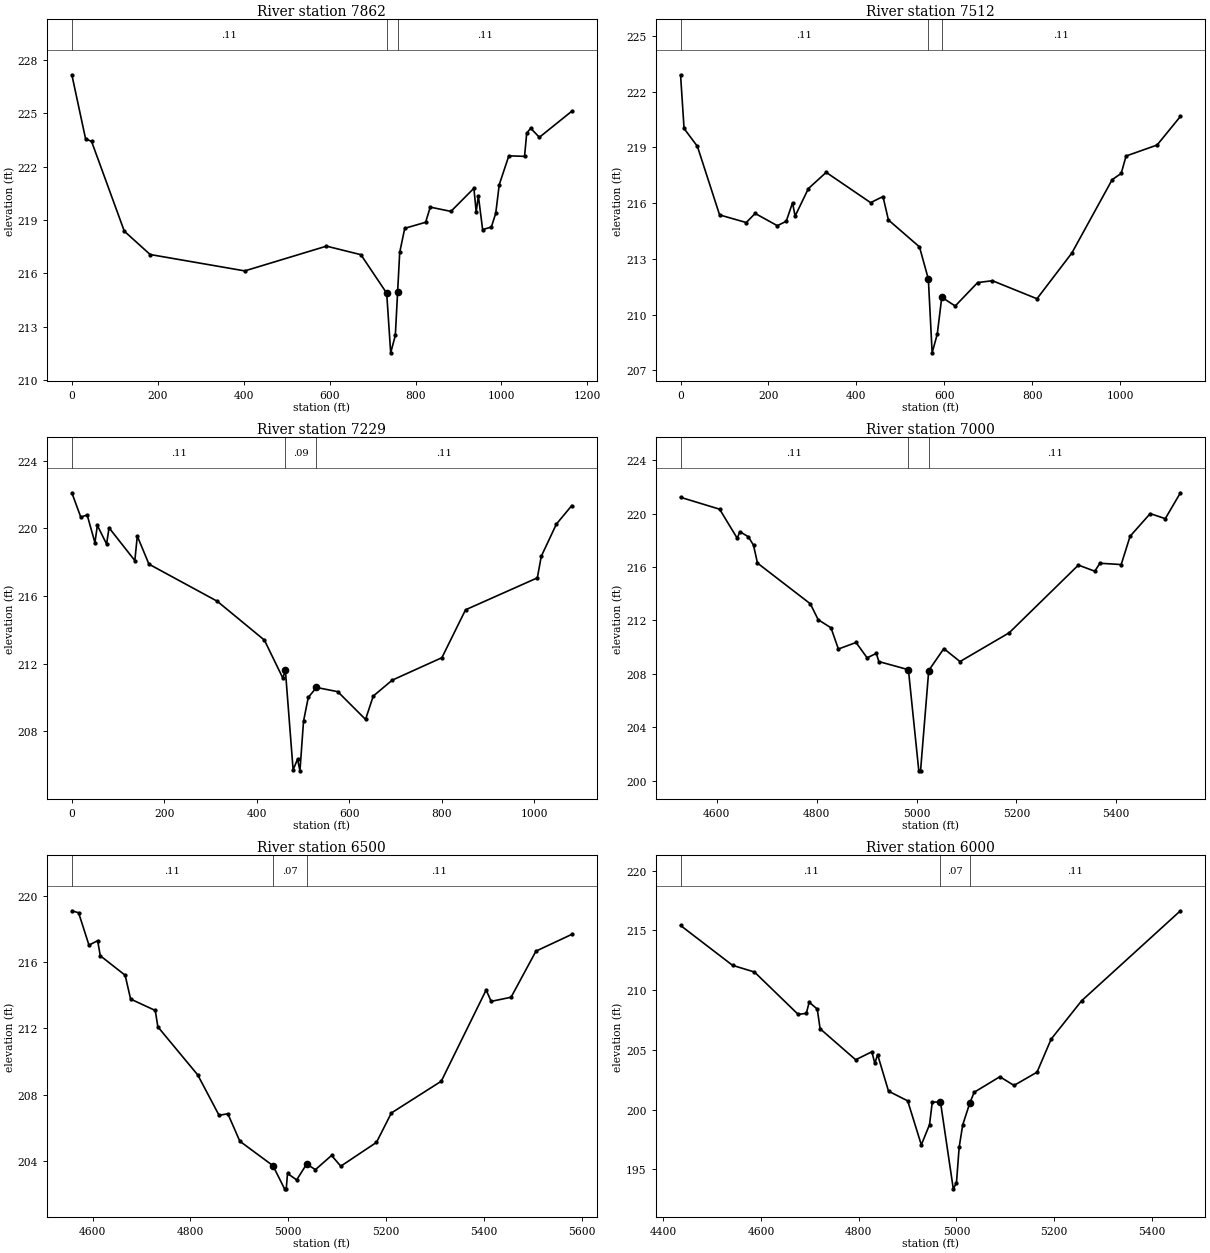
Type RM Length L Ch R = 1 ,7862    ,350,350,350
XS GIS Cut Line= 3
       3831389.8      10118263.8      3830644.24      10118301.7
      3830233.66     10118375.27
#Sta/Elev= 30
       0  227.15      32  223.55    45.9  223.41   122.1  218.37   182.2  217.06
   402.5  216.14   592.7  217.53   672.8  217.05   732.9  214.89   742.2  211.54
     753  212.52  758.26  214.93   763.2  217.18   774.9  218.53   823.5  218.87
   834.3  219.72   882.4  219.48   935.9  220.78   941.2  219.46   946.3  220.35
   956.2  218.46   976.5   218.6   986.7  219.37   994.9  220.98  1017.2   222.6
  1053.8  222.57  1058.8  223.87    1068  224.15  1088.3  223.64  1163.6   225.1
#Mann= 3 , 0 , 0
       0     .11       0   732.9     .09       0  758.26     .11       0
#Block Obstruct= 2 , 0
       0                   935.9       0  220.78
Bank Sta=732.9,758.26
XS Rating Curve= 0 ,0
Exp/Cntr=0.3,0.1

Type RM Length L Ch R = 1 ,7512    ,284,284,284
XS GIS Cut Line= 3
      3831295.76     10118052.43      3830725.93     10117969.97
      3830175.73     10118081.45
#Sta/Elev= 30
       0   222.9       8  220.01    38.3  219.05    88.8  215.36   149.5  214.95
   169.7  215.44   220.2  214.78   240.4  215.02   254.7  216.01   260.6   215.3
   290.9  216.78   331.3  217.65   432.4  216.02   460.5  216.35   472.8  215.09
   543.5  213.64   563.7  211.91   572.3  207.94     584  208.95   594.2  210.93
   624.8  210.46   675.8  211.72   709.4  211.82   810.8  210.85   890.1  213.31
   981.9  217.26  1002.3  217.59  1013.5  218.53    1084  219.12  1137.1  220.66
#Mann= 3 , 0 , 0
       0     .11       0   563.7     .09       0   594.2     .11       0
Bank Sta=563.7,594.2
XS Rating Curve= 0 ,0
Exp/Cntr=0.3,0.1

Type RM Length L Ch R = 1 ,7229    ,229,229,229
XS GIS Cut Line= 3
      3831098.93     10117863.44      3830646.16      10117698.2
      3830065.83     10117550.66
#Sta/Elev= 30
       0  222.11    19.3  220.67    33.1   220.8    49.9  219.16    55.2  220.18
    75.1  219.08    80.4  220.04   136.2   218.1   141.5  219.55   166.7  217.89
   314.2   215.7   416.3   213.4   456.3  211.15   461.6  211.65   478.4  205.73
     488  206.36   493.2  205.67   500.9   208.6   511.2  210.01   528.9   210.6
     575  210.35     635  208.71   651.7  210.09   692.6  211.03   800.1  212.36
   851.2  215.19  1006.5  217.08  1014.9  218.35  1047.7  220.26  1080.8  221.35
#Mann= 3 , 0 , 0
       0     .11       0   461.6     .09       0   528.9     .11       0
Bank Sta=461.6,528.9
XS Rating Curve= 0 ,0
Exp/Cntr=0.3,0.1

Type RM Length L Ch R = 1 ,7000    ,500,500,500
BEGIN DESCRIPTION:
WEST BRANCH ALLIGATOR CREEK 14.0
END DESCRIPTION:
XS GIS Cut Line= 3
      3831049.28     10117595.58      3830592.14      10117476.5
       3830067.8     10117411.07
#Sta/Elev= 30
  4527.6  221.23  4605.8  220.34  4641.1  218.16  4646.3  218.66  4663.4  218.27
  4673.7  217.64  4681.6   216.3  4787.4  213.25  4803.1  212.06  4828.8  211.45
  4843.6  209.86    4879  210.35  4901.1   209.2  4919.5  209.53  4924.6  208.92
  4983.8  208.31  5004.6  200.73  5008.1  200.73  5024.5  208.25  5054.7  209.89
  5087.1  208.92  5185.7  211.08  5324.1  216.15    5357  215.69  5367.1  216.29
  5409.8  216.19  5427.6  218.31  5467.9  220.01  5498.1  219.63  5528.4  221.57
#Mann= 3 , 0 , 0
  4527.6     .11       0  4983.8     .07       0  5024.5     .11       0
Bank Sta=4983.8,5024.5
XS Rating Curve= 0 ,0
Exp/Cntr=0.3,0.1

Type RM Length L Ch R = 1 ,6500    ,500,500,500
BEGIN DESCRIPTION:
WEST BRANCH ALLIGATOR CREEK 13.0
END DESCRIPTION:
XS GIS Cut Line= 3
      3831060.82      10117134.5      3830644.65     10116985.02
      3830076.22     10117095.13
#Sta/Elev= 30
  4557.8  219.12  4571.6     219  4592.8  217.04  4610.5  217.31  4615.9   216.4
  4666.7  215.22  4677.8  213.78  4728.2  213.09  4733.5   212.1    4815  209.19
  4858.5  206.75  4876.5  206.84    4901  205.18  4968.7   203.7  4992.3   202.3
  4995.8   202.3  4998.4  203.23  5017.1  202.84  5037.5   203.8  5055.4  203.46
  5088.4  204.32  5107.2  203.67  5180.1  205.11  5210.6  206.89  5312.5  208.81
  5404.2  214.33  5414.4  213.64  5455.1  213.89    5506  216.68    5579  217.69
#Mann= 3 , 0 , 0
  4557.8     .11       0  4968.7     .07       0  5037.5     .11       0
Bank Sta=4968.7,5037.5
XS Rating Curve= 0 ,0
Exp/Cntr=0.3,0.1

Type RM Length L Ch R = 1 ,6000    ,500,500,500
BEGIN DESCRIPTION:
WEST BRANCH ALLIGATOR CREEK 12.0
END DESCRIPTION:
XS GIS Cut Line= 3
      3830998.28     10116258.75      3830492.93      10116510.3
      3830072.18     10116691.73
#Sta/Elev= 30
  4435.5  215.42  4541.9  212.08  4586.7  211.52  4676.2  207.97  4692.9  208.06
  4698.6  208.99  4715.2  208.42    4721  206.77  4793.8  204.17  4826.9  204.84
    4833  203.86  4838.6  204.61    4861  201.54  4900.2  200.73  4928.1  197.04
  4944.9  198.74  4950.5  200.63  4967.3  200.63  4993.5  193.36    5000  193.86
  5005.5  196.84  5012.8  198.72  5027.3  200.55  5036.3  201.45  5088.8  202.75
  5117.7  202.02  5164.8  203.13  5193.7   205.9    5256  209.11  5458.2  216.65
#Mann= 3 , 0 , 0
  4435.5     .11       0  4967.3     .07       0  5027.3     .11       0
Bank Sta=4967.3,5027.3
XS Rating Curve= 0 ,0
Exp/Cntr=0.3,0.1

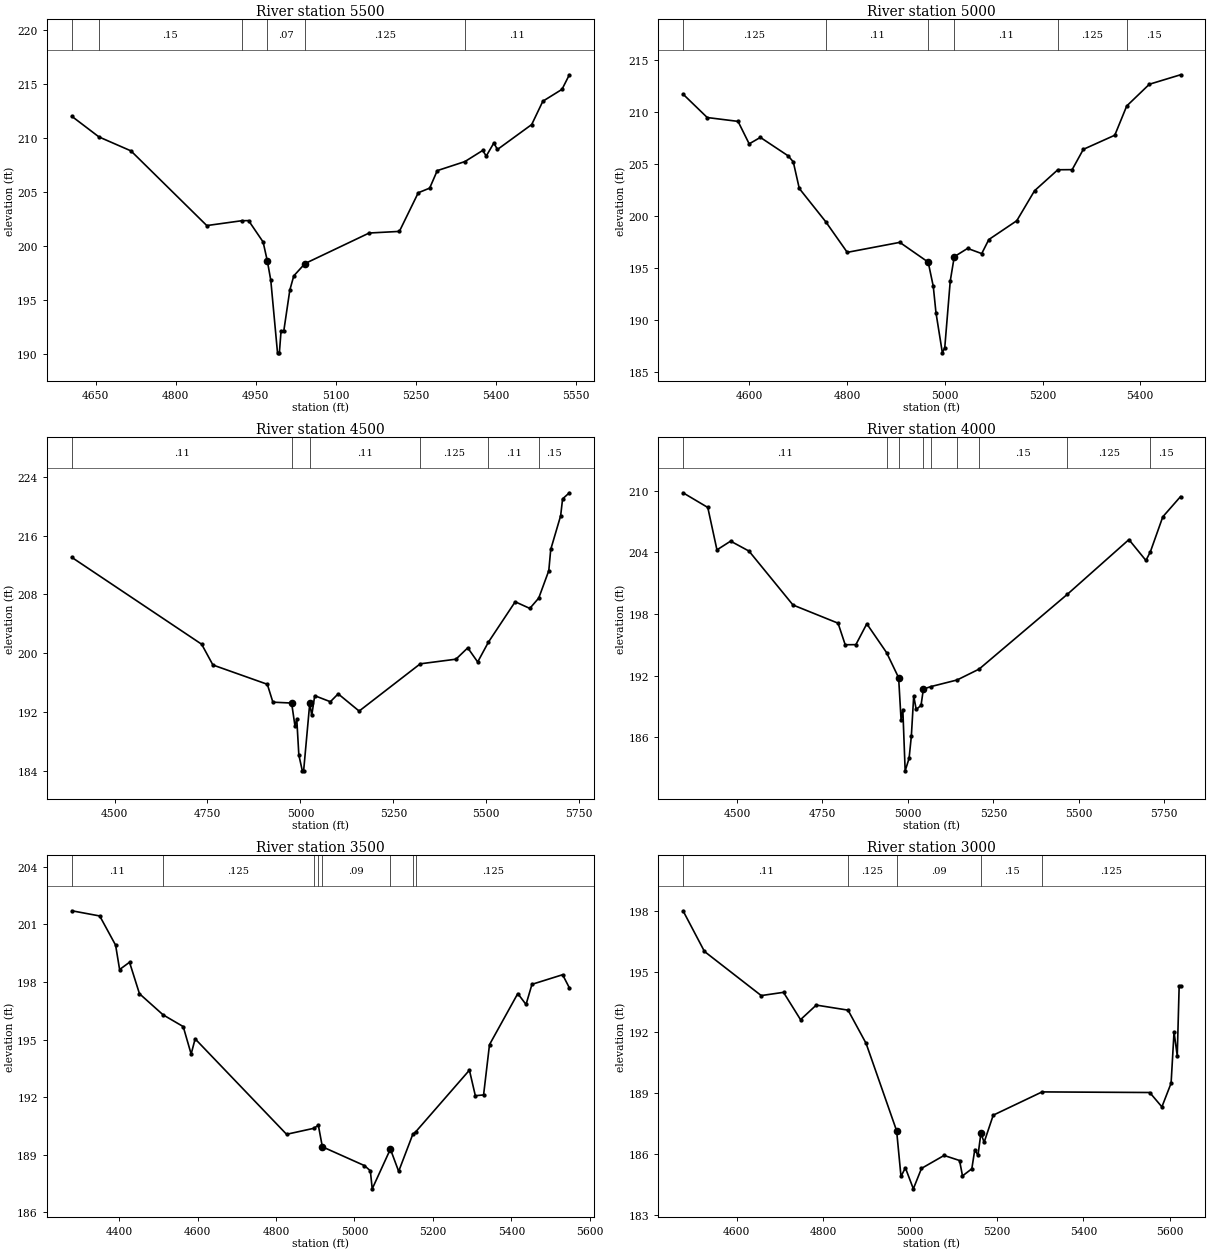
Type RM Length L Ch R = 1 ,5500    ,500,500,500
BEGIN DESCRIPTION:
WEST BRANCH ALLIGATOR CREEK 11.0
END DESCRIPTION:
XS GIS Cut Line= 3
      3830585.88     10115813.91      3830279.03     10116062.18
      3829917.86     10116461.06
#Sta/Elev= 30
  4605.3  212.01  4656.2   210.1  4716.1  208.81  4858.3  201.89  4923.9  202.34
  4936.7  202.35  4963.9  200.37  4971.9  198.59  4978.3  196.82  4990.9   190.1
  4994.4   190.1  4997.5   192.1  5002.6   192.1    5014  195.92  5021.4  197.23
  5042.4  198.37  5162.7   201.2  5219.4  201.35  5254.8  204.93  5276.2  205.36
  5290.4  206.98  5342.3  207.82  5375.6  208.85  5382.3  208.33  5396.5  209.54
  5403.3  208.94  5467.5  211.25  5488.4  213.41  5524.3  214.51  5538.1  215.86
#Mann= 6 ,-1 , 0
  4605.3    .125       0  4656.2     .15       0  4923.9     .11       0
  4971.9     .07       0  5042.4    .125       0  5342.3     .11       0
Bank Sta=4971.9,5042.4
XS Rating Curve= 0 ,0
Exp/Cntr=0.3,0.1

Type RM Length L Ch R = 1 ,5000    ,500,500,500
BEGIN DESCRIPTION:
WEST BRANCH ALLIGATOR CREEK 10.0
END DESCRIPTION:
XS GIS Cut Line= 3
      3830412.15     10115487.21      3829927.13     10115713.95
      3829634.71     10116097.49
#Sta/Elev= 30
  4464.6   211.7  4514.1  209.45  4577.1  209.08  4599.9  206.92  4622.8  207.54
  4679.5  205.77  4690.1  205.19  4702.4  202.63  4756.4  199.44  4800.5  196.49
    4908  197.45  4966.1  195.55  4976.5  193.22    4982  190.69  4995.1  186.83
    5000  187.33  5011.2  193.73  5019.4  196.07  5046.7  196.87  5075.6  196.37
  5090.1  197.72  5147.3  199.53  5183.6  202.41  5231.3  204.43  5260.6  204.44
  5283.4  206.39  5347.8  207.75  5372.2  210.56  5418.5  212.65  5482.3  213.56
#Mann= 6 ,-1 , 0
  4464.6    .125       0  4756.4     .11       0  4966.1     .07       0
  5019.4     .11       0  5231.3    .125       0  5372.2     .15       0
Bank Sta=4966.1,5019.4
XS Rating Curve= 0 ,0
Exp/Cntr=0.3,0.1

Type RM Length L Ch R = 1 ,4500    ,500,500,500
BEGIN DESCRIPTION:
WEST BRANCH ALLIGATOR CREEK 9.0
END DESCRIPTION:
XS GIS Cut Line= 3
      3830354.19     10115248.58      3829744.47     10115327.47
      3829056.73      10115552.1
#Sta/Elev= 30
  4385.2  213.03  4734.4  201.23  4764.7  198.41    4911  195.79    4926  193.36
  4976.4  193.24  4985.3  190.16  4990.3  191.02  4995.8  186.18  5005.2  184.03
  5008.7  184.03  5025.2  193.23  5030.5  191.56  5038.5  194.24  5080.6  193.42
  5101.6  194.49    5158  192.15  5322.4  198.57  5418.4   199.2  5450.2  200.74
  5476.9  198.82  5505.7  201.51  5577.8     207  5617.1   206.1  5641.1   207.5
  5668.2  211.23  5673.4  214.11  5700.1  218.69  5705.3  220.98  5723.5  221.81
#Mann= 6 ,-1 , 0
  4385.2     .11       0  4976.4     .05       0  5025.2     .11       0
  5322.4    .125       0  5505.7     .11       0  5641.1     .15       0
Bank Sta=4976.4,5025.2
XS Rating Curve= 0 ,0
Exp/Cntr=0.3,0.1

Type RM Length L Ch R = 1 ,4000    ,500,500,500
BEGIN DESCRIPTION:
WEST BRANCH ALLIGATOR CREEK 8.0
END DESCRIPTION:
XS GIS Cut Line= 3
        3830243.     10115056.27      3829611.85     10114870.94
      3829065.99     10115452.49
#Sta/Elev= 30
  4342.2  209.81  4414.6  208.38  4441.4  204.25  4481.4   205.1  4535.2  204.13
  4663.9  198.88  4795.7  197.11  4816.6  195.01  4847.8  195.02  4879.8  197.05
  4937.7  194.24  4972.9   191.8    4980  187.71  4985.2   188.7    4992  182.73
  5003.5  183.95  5010.1  186.12    5017  190.02  5024.3  188.71  5038.4   189.1
  5045.3  190.69  5066.7  190.93    5144  191.58  5208.4  192.64  5466.7  199.93
  5646.6  205.25  5696.3  203.22  5709.3  204.06  5745.7  207.47  5797.6  209.44
#Mann= 9 ,-1 , 0
  4342.2     .11       0  4937.7    .125       0  4972.9     .09       0
  5045.3    .125       0  5066.7     .15       0    5144     .11       0
  5208.4     .15       0  5466.7    .125       0  5709.3     .15       0
Bank Sta=4972.9,5045.3
XS Rating Curve= 0 ,0
Exp/Cntr=0.3,0.1

Type RM Length L Ch R = 1 ,3500    ,500,500,500
BEGIN DESCRIPTION:
WEST BRANCH ALLIGATOR CREEK 7.0
END DESCRIPTION:
XS GIS Cut Line= 3
      3830297.94     10114509.68      3829586.99     10114394.03
      3829130.92     10114697.14
#Sta/Elev= 30
  4279.7  201.71  4350.7  201.44  4391.2  199.92  4401.4  198.65  4426.7  199.03
    4452  197.39  4512.3  196.29  4563.5  195.68  4583.7  194.25  4593.9  195.04
  4826.9  190.07  4895.8  190.38  4907.9  190.54  4918.1  189.42  5025.4  188.44
  5040.4  188.17  5045.2  187.23  5091.5   189.3  5112.6  188.14  5148.6  190.07
  5156.5  190.21  5292.9  193.41    5308  192.08    5329  192.12  5344.1  194.74
  5416.2   197.4  5437.2  196.83  5452.3  197.88  5530.4  198.38  5547.6   197.7
#Mann= 8 ,-1 , 0
  4279.7     .11       0  4512.3    .125       0  4895.8     .15       0
  4907.9     .12       0  4918.1     .09       0  5091.5     .15       0
  5148.6     .15       0  5156.5    .125       0
Bank Sta=4918.1,5091.5
XS Rating Curve= 0 ,0
Exp/Cntr=0.3,0.1

Type RM Length L Ch R = 1 ,3000    ,403,403,403
BEGIN DESCRIPTION:
WEST BRANCH ALLIGATOR CREEK 6.0
END DESCRIPTION:
XS GIS Cut Line= 4
      3830146.85     10113837.81        3829627.      10113902.8
      3829582.49       10113908.      3829188.56     10114332.59
#Sta/Elev= 30
  4476.1  198.01  4525.5     196  4656.5  193.82  4707.9  193.98  4747.2  192.63
  4783.5  193.35  4856.8   193.1  4898.4  191.46  4968.9  187.14    4979  184.88
  4989.1  185.31  5007.5  184.27  5026.3  185.28  5078.4  185.92  5114.1  185.67
  5120.9  184.91  5142.4  185.26  5149.3  186.21  5156.6  185.92  5163.4  187.02
  5170.8  186.57  5191.8  187.91  5304.6  189.06  5552.9  189.03    5581  188.32
  5602.2  189.49    5609  192.02  5616.4  190.84  5620.8  194.27    5624  194.27
#Mann= 5 ,-1 , 0
  4476.1     .11       0  4856.8    .125       0  4968.9     .09       0
  5163.4     .15       0  5304.6    .125       0
Bank Sta=4968.9,5163.4
XS Rating Curve= 0 ,0
Exp/Cntr=0.3,0.1

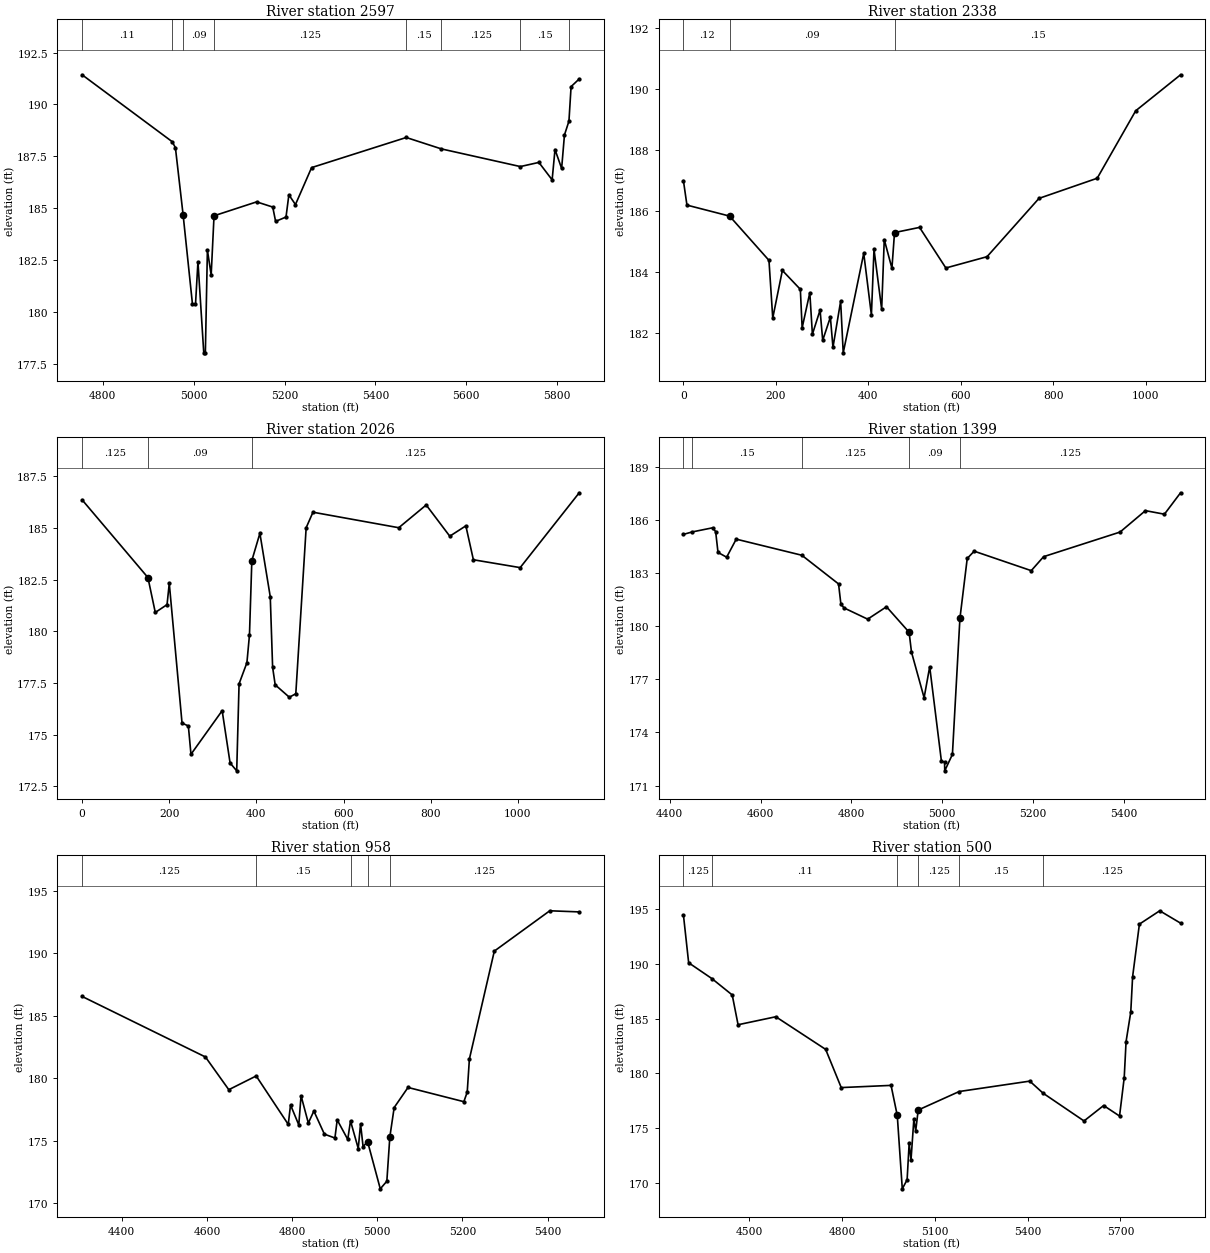
Type RM Length L Ch R = 1 ,2597    ,262,262,262
BEGIN DESCRIPTION:
WEST BRANCH ALLIGATOR CREEK 5.0
END DESCRIPTION:
XS GIS Cut Line= 3
      3829983.22     10113513.54      3829737.65     10113517.51
      3829229.73     10114197.19
#Sta/Elev= 30
  4754.4  191.43  4952.6  188.21  4959.8  187.92 4976.82  184.67  4997.4  180.37
    5004  180.37  5009.4  182.43  5022.2  178.04  5025.7  178.04  5030.2  182.99
  5038.5  181.79  5044.8  184.64  5138.6  185.31    5174  185.06  5180.3  184.37
  5203.2  184.58  5209.5  185.65    5224  185.18  5259.5  186.96  5467.8  188.41
  5545.2  187.86  5718.9  187.01  5759.7  187.21  5788.9  186.37  5795.2  187.83
  5809.8  186.92    5816  188.53  5825.9   189.2  5830.6  190.86  5848.5  191.23
#Mann= 8 ,-1 , 0
  4754.4     .11       0  4952.6    .125       0 4976.82     .09       0
  5044.8    .125       0  5467.8     .15       0  5545.2    .125       0
  5718.9     .15       0  5825.9    .125       0
Bank Sta=4976.82,5044.8
XS Rating Curve= 0 ,0
Exp/Cntr=0.3,0.1

Type RM Length L Ch R = 1 ,2338    ,309,309,309
XS GIS Cut Line= 3
      3829693.86     10113226.62      3829495.24     10113379.01
      3829119.31     10114113.89
#Sta/Elev= 30
       0     187     7.6   186.2    99.9  185.84   185.1  184.39   193.3   182.5
   214.1  184.06     253  183.44   256.9  182.18   273.5  183.33   279.1  181.97
   295.7  182.76   301.4  181.77     318  182.53   323.6  181.54   340.2  183.05
   345.8  181.36   390.2  184.62   406.8   182.6   412.4  184.75     429  182.79
   434.6  185.07   451.2  184.13   456.8   185.3     511  185.47   567.9  184.14
     657  184.51   769.4  186.42   895.4  187.08   978.7  189.29  1075.8  190.47
#Mann= 3 , 0 , 0
       0     .12       0    99.9     .09       0   456.8     .15       0
Bank Sta=99.9,456.8
XS Rating Curve= 0 ,0
Exp/Cntr=0.3,0.1

Type RM Length L Ch R = 1 ,2026    ,627,627,627
XS GIS Cut Line= 3
      3829731.95     10113138.06      3829400.15     10113065.43
      3829091.32     10113808.34
#Sta/Elev= 30
       0  186.36   151.1   182.6     168  180.91     195  181.29   200.1  182.32
   229.4  175.56   243.9  175.42   249.9  174.05   321.5  176.16   339.7  173.63
   354.9  173.25   360.3  177.46   378.3  178.48   384.2  179.83   389.6  183.42
   408.1  184.74   431.9  181.67   437.3  178.26   443.2  177.41   475.7  176.81
   490.5  176.98   514.3  185.01   529.9  185.76   726.8  185.01   789.8  186.11
   843.9   184.6   880.8   185.1   898.1  183.46  1005.5  183.08    1141   186.7
#Mann= 3 , 0 , 0
       0    .125       0   151.1     .09       0   389.6    .125       0
Bank Sta=151.1,389.6
XS Rating Curve= 0 ,0
Exp/Cntr=0.3,0.1

Type RM Length L Ch R = 1 ,1399    ,441,441,441
BEGIN DESCRIPTION:
WEST BRANCH ALLIGATOR CREEK 3.0
END DESCRIPTION:
XS GIS Cut Line= 3
      3829841.54     10113172.95       3829694.9     10112622.45
      3829194.04     10112467.09
#Sta/Elev= 30
  4430.3  185.19    4450  185.33  4494.3  185.56  4501.2  185.35  4506.4  184.17
  4525.4   183.9  4546.5  184.92  4690.9  184.01  4771.7  182.39  4776.9  181.24
  4784.1  181.03  4835.8   180.4  4877.2   181.1    4927  179.66  4932.2  178.54
    4960  175.96  4972.3  177.71  4998.1  172.37    5005  172.33  5005.4  171.83
  5022.3  172.76  5038.8  180.44  5054.9  183.83  5070.2  184.24  5195.8  183.14
    5223  183.93  5391.2  185.32  5447.1  186.53  5488.9  186.33  5524.4  187.54
#Mann= 5 ,-1 , 0
  4430.3    .125       0    4450     .15       0  4690.9    .125       0
    4927     .09       0  5038.8    .125       0
Bank Sta=4927,5038.8
XS Rating Curve= 0 ,0
Exp/Cntr=0.3,0.1

Type RM Length L Ch R = 1 ,958     ,458,458,458
BEGIN DESCRIPTION:
WEST BRANCH ALLIGATOR CREEK 2.0
END DESCRIPTION:
XS GIS Cut Line= 3
      3829879.73     10113197.21       3830127.1     10112549.86
      3830029.04     10112086.12
#Sta/Elev= 30
    4307  186.56  4596.6  181.71  4651.4  179.09  4715.7  180.19    4791  176.31
  4796.3  177.87  4815.7  176.27    4821  178.61  4838.1  176.42  4851.1  177.38
  4875.8  175.53  4900.5  175.22  4905.9  176.67  4930.6  175.11  4937.1  176.59
  4955.3  174.38  4960.7  176.36  4966.6  174.54  4977.3  174.92    5007  171.15
  5022.4  171.76  5029.4   175.3  5039.6  177.66  5072.1  179.27  5203.2  178.13
  5211.1   178.9  5216.2  181.55  5274.7  190.19  5404.9  193.42    5474  193.33
#Mann= 5 ,-1 , 0
    4307    .125       0  4715.7     .15       0  4937.1    .125       0
  4977.3     .09       0  5029.4    .125       0
Bank Sta=4977.3,5029.4
XS Rating Curve= 0 ,0
Exp/Cntr=0.3,0.1

Type RM Length L Ch R = 1 ,500     ,386,386,386
BEGIN DESCRIPTION:
WEST BRANCH ALLIGATOR CREEK 1.5
END DESCRIPTION:
XS GIS Cut Line= 3
      3830482.62     10113397.82      3830562.53     10112689.91
      3830076.36     10111939.43
#Sta/Elev= 30
  4287.6  194.48  4304.5  190.11  4379.4  188.67  4445.3  187.17  4464.2  184.45
  4586.2  185.18  4747.2   182.2  4797.6  178.71  4958.6  178.91  4978.7  176.16
  4994.9  169.46  5010.5  170.29  5017.1  173.61  5023.1  172.11  5032.3  175.82
  5038.3  174.76  5046.3  176.66  5178.8  178.35  5406.9   179.3  5449.8   178.2
  5582.2  175.66  5645.6  177.07    5697  176.11  5712.1  179.61  5718.1  182.91
  5733.3  185.61  5739.2  188.83  5761.2  193.64  5826.9  194.86  5894.2  193.73
#Mann= 6 ,-1 , 0
  4287.6    .125       0  4379.4     .11       0  4978.7     .07       0
  5046.3    .125       0  5178.8     .15       0  5449.8    .125       0
Bank Sta=4978.7,5046.3
XS Rating Curve= 0 ,0
Exp/Cntr=0.3,0.1

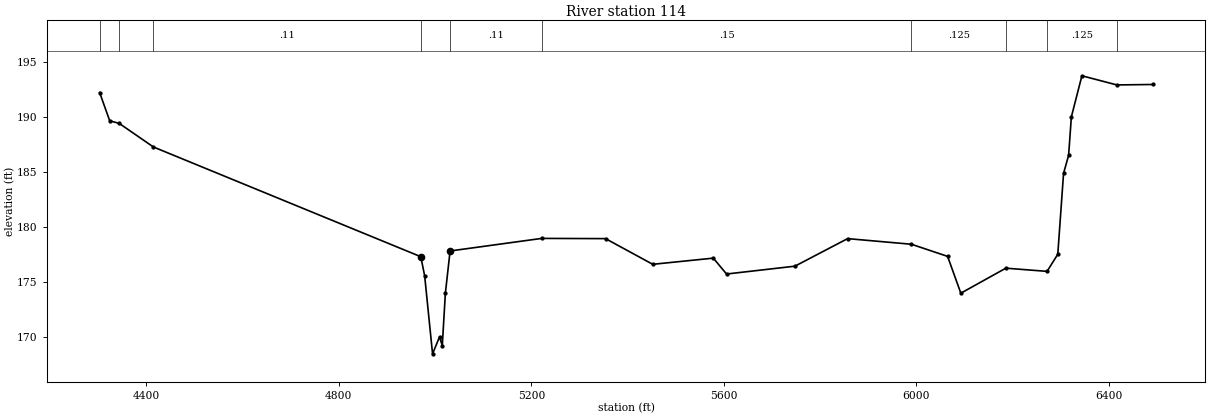
Type RM Length L Ch R = 1 ,114     ,0,0,0
BEGIN DESCRIPTION:
WEST BRANCH ALLIGATOR CREEK 1.0
END DESCRIPTION:
XS GIS Cut Line= 3
      3830784.71     10113491.51      3830929.62     10112809.95
      3830222.55     10111497.38
#Sta/Elev= 30
  4303.2  192.19  4324.1  189.63  4343.9  189.39    4415  187.25  4970.4   177.3
  4978.4  175.56  4994.8  168.49  5009.3  170.03    5015  169.24  5021.4  173.98
  5031.2  177.82  5221.6  178.96  5354.1  178.94  5452.2  176.61    5578  177.17
  5605.5  175.73  5747.5  176.44    5857  178.94  5989.5  178.43  6064.7  177.33
  6092.2  173.99  6185.7  176.26  6271.3  175.97  6293.6  177.52  6305.6  184.86
  6316.1   186.5  6321.8  189.98  6343.7  193.71  6416.3  192.88  6490.9  192.92
#Mann= 10 ,-1 , 0
  4303.2     .15       0  4343.9    .125       0    4415     .11       0
  4970.4     .09       0  5031.2     .11       0  5221.6     .15       0
  5989.5    .125       0  6185.7     .15       0  6271.3    .125       0
  6416.3     .15       0
Bank Sta=4970.4,5031.2
XS Rating Curve= 0 ,0
Exp/Cntr=0.3,0.1

Chan Stop Cuts=-1
Use User Specified Reach Order=0
Composite Channel Slope=5