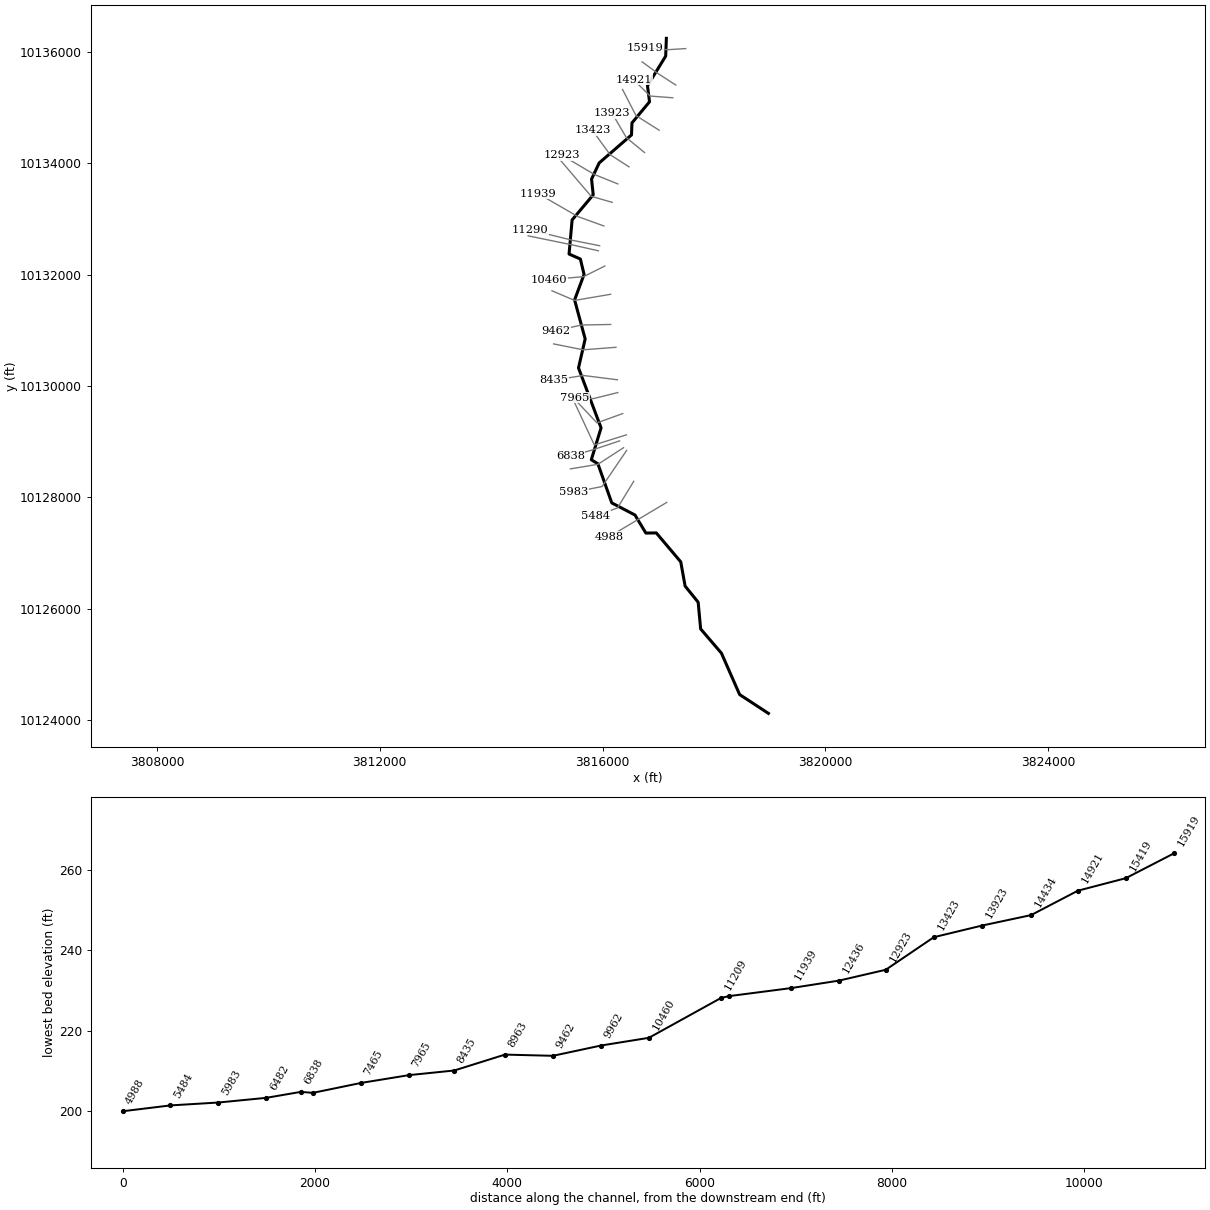
--- WEST FORK OF WHITE OAK CREEK N.prj (project) ---

Proj Title=WEST FORK OF WHITE OAK CREEK N Base Level Engineering
Current Plan=p01
Default Exp/Contr=0.3,0.1
English Units
Geom File=g01
Flow File=f01
Plan File=p01
Y Axis Title=Elevation
X Axis Title(PF)=Main Channel Distance
X Axis Title(XS)=Station
BEGIN DESCRIPTION:
WEST FORK OF WHITE OAK CREEK N
END DESCRIPTION:
DSS Export Rating Curves= 0
DSS Export Rating Curve Sorted= 0
DSS Export Volume Flow Curves= 0
DXF OffsetX= 0
DXF OffsetY= 0
DXF ScaleX= 1
DXF ScaleY= 10

--- WEST FORK OF WHITE OAK CREEK N.p01 (plan) ---

Plan Title=Multiple Run
Program Version=4.10
Short Identifier=Multiple
Geom File=g01
Flow File=f01
Subcritical Flow
K Sum by GR= 0
Std Step Tol= 0.01
Critical Tol= 0.01
Num of Std Step Trials= 20
Max Error Tol= 0.3
Flow Tol Ratio= 0.001
Split Flow NTrial= 30
Split Flow Tol= 0.02
Split Flow Ratio= 0.02
Log Output Level= 0
Friction Slope Method= 1
Unsteady Friction Slope Method= 2
Unsteady Bridges Friction Slope Method= 1
Parabolic Critical Depth
Global Vel Dist= 1 , 1 , 1
Global Log Level= 0
CheckData=True
Encroach Param=-1 ,0,0, 0
BEGIN DESCRIPTION:
Multiple Run
END DESCRIPTION:
Computation Interval=1HOUR
Output Interval=1HOUR
Run HTab= 0
Run UNet= 0
Run PostProcess= 0
Run WQNet= 0
UNET Theta= 1
UNET Theta Warmup= 1
UNET ZTol= 0.02
UNET ZSATol= 0.05
UNET MxIter= 20
UNET MaxInSteps= 0
UNET DtIC= 0
UNET DtMin= 0
UNET MaxCRTS= 20
UNET WFStab= 2
UNET SFStab= 1
UNET WFX= 1
UNET SFX= 1
UNET DSS MLevel= 4
UNET DZMax Abort= 100
UNET Convert EG Bridges= 0
UNET Use Existing IB Tables=-1
UNET Froude Reduction=False
UNET Froude Limit= 1
UNET Froude Power= 10
UNET Time Slicing=0,0, 5
UNET Junction Losses=0
Instantaneous Interval=1HOUR
Write IC File= 0
Write IC File at Sim End=0
Echo Input=False
Echo Parameters=False
Echo Output=False
Write Detailed= 0
WQ AD Non Conservative
WQ ULTIMATE=-1
WQ Max Comp Step=1HOUR
WQ Output Interval=15MIN
WQ Output Selected Increments= 0
WQ Output face flow=0
WQ Output face velocity=0
WQ Output face area=0
WQ Output face dispersion=0
WQ Output cell volume=0
WQ Output cell surface area=0
WQ Output cell continuity=0
WQ Output cumulative cell continuity=0
WQ Output face conc=0
WQ Output face dconc_dx=0
WQ Output face courant=0
WQ Output face peclet=0
WQ Output face adv mass=0
WQ Output face disp mass=0
WQ Output cell mass=0
WQ Output cell source sink temp=0
WQ Output cell source sink nsm=0
WQ Output MaxMinRange=-1
WQ Daily Max Min Mean=-1
WQ Daily Range=0
WQ Daily Time=0
WQ Create Restart=0
WQ Fixed Restart=0
WQ System Summary=0
WQ Use Fixed Temperature=0
Sorting and Armoring Iterations= 10
XS Update Threshold= 0.02
Hydraulics Update Threshold= 0.02
Energy Slope Method= 1
Volume Change Method= 0
XS Weighting Method= 0
Number of US Weighted Cross Sections= 1
Number of DS Weighted Cross Sections= 1
Upstream XS Weight=0.25
Main XS Weight=0.5
Downstream XS Weight=0.25
Number of DS XS's Weighted with US Boundary= 1
Upstream Boundary Weight= 1
Weight of XSs Associated with US Boundary= 0
Number of US XS's Weighted with DS Boundary= 1
Downstream Boundary Weight= 0.5
Weight of XSs Associated with DS Boundary= 0.5
Sediment Output Level= 4
Mass or Volume Output= 0
Output Increment Type= 1
Profile and TS Output Increment= 10
XS Output Flag= 0
XS Output Increment= 10
Disregard all LS=0
Disregard all Conn=0
Disregard all Breaches=0
Disregard all Pumps=0

--- WEST FORK OF WHITE OAK CREEK N.f01 (steady flow) ---

Flow Title=Multiple
Program Version=4.10
Number of Profiles= 7
Profile Names=10-year,25-year,50-year,1pct_min,100-year,1pct_plu,500-year
River Rch & RM=WEST FORK OF WHI,Reach-1         ,15919
    1082    1523    2115     966    2917    8809    5738
River Rch & RM=WEST FORK OF WHI,Reach-1         ,12436
    1239    1747    2428    1109    3348   10111    6582
River Rch & RM=WEST FORK OF WHI,Reach-1         ,6838
    1664    2378    3333    1533    4629   13979    9245
River Rch & RM=WEST FORK OF WHI,Reach-1         ,4988
    2020    2911    4104    1897    5730   17304   11562
River Rch & RM=WEST FORK OF WHI,Reach-1         ,4489
    2020    2911    4104    1897    5730   17304   11562
River Rch & RM=WEST FORK OF WHI,Reach-1         ,3011
    2236    3230    4561    2111    6375   19252   12886
Boundary for River Rch & Prof#=WEST FORK OF WHI,Reach-1         , 1
Up Type= 0
Dn Type= 3
Dn Slope=0.035
Boundary for River Rch & Prof#=WEST FORK OF WHI,Reach-1         , 2
Up Type= 0
Dn Type= 3
Dn Slope=0.035
Boundary for River Rch & Prof#=WEST FORK OF WHI,Reach-1         , 3
Up Type= 0
Dn Type= 3
Dn Slope=0.035
Boundary for River Rch & Prof#=WEST FORK OF WHI,Reach-1         , 4
Up Type= 0
Dn Type= 3
Dn Slope=0.035
Boundary for River Rch & Prof#=WEST FORK OF WHI,Reach-1         , 5
Up Type= 0
Dn Type= 3
Dn Slope=0.035
Boundary for River Rch & Prof#=WEST FORK OF WHI,Reach-1         , 6
Up Type= 0
Dn Type= 3
Dn Slope=0.035
Boundary for River Rch & Prof#=WEST FORK OF WHI,Reach-1         , 7
Up Type= 0
Dn Type= 3
Dn Slope=0.035
DSS Import GetInterval= 0
DSS Import GetPeak= 0
DSS Import FillOption= 0

--- WEST FORK OF WHITE OAK CREEK N.g01 (geometry) ---

Geom Title=Existing Conditions
Program Version=4.10

River Reach=WEST FORK OF WHI,Reach-1
Reach XY= 30
      3817146.25     10136246.77      3817134.21     10135927.62
      3816807.53     10135394.24      3816843.95      10135106.8
      3816528.74     10134727.45      3816520.15       10134511.
        3815940.     10134007.79      3815802.98     10133717.46
      3815832.82     10133435.27      3815453.85     10132983.19
        3815399.     10132370.93      3815602.35     10132281.04
      3815668.38     10132004.27       3815498.2     10131546.43
      3815688.27     10130844.84      3815568.68     10130323.95
      3815973.79     10129247.38      3815798.56     10128673.93
      3815916.47     10128602.48      3816166.11     10127898.95
      3816583.11     10127681.04      3816778.23     10127356.84
      3816965.33      10127359.6       3817404.7     10126839.31
      3817483.09     10126403.76      3817717.05      10126114.4
      3817761.85     10125634.58      3818135.19     10125198.41
      3818461.97     10124454.89      3818978.23     10124116.84

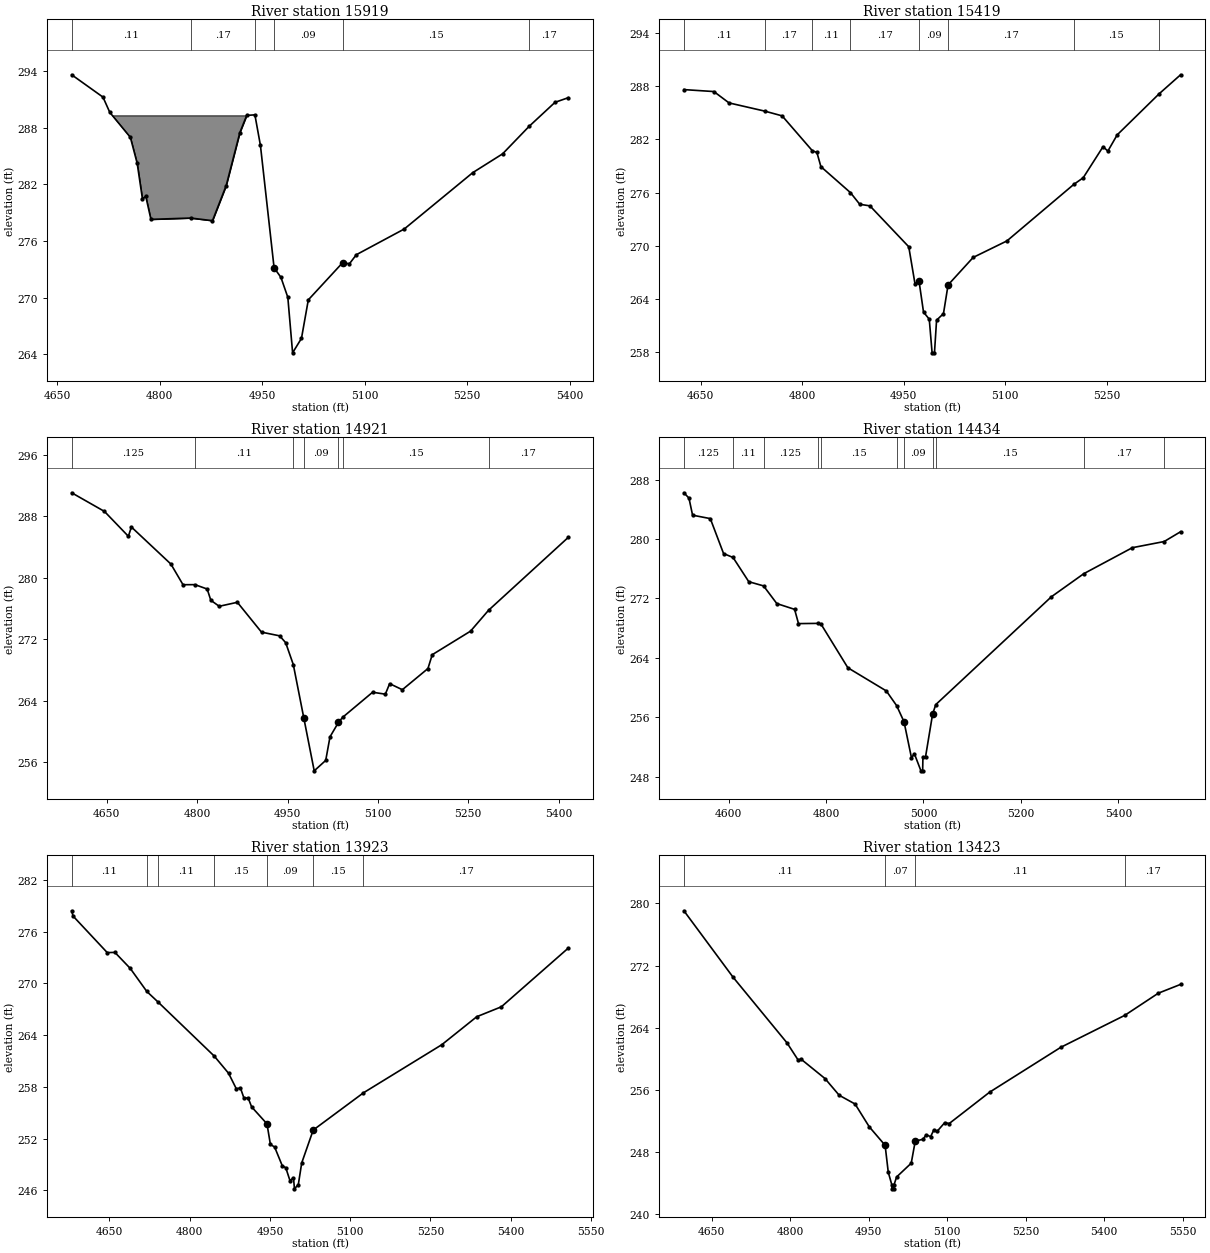
Type RM Length L Ch R = 1 ,15919   ,500,500,500
BEGIN DESCRIPTION:
WEST FORK OF WHITE OAK CREEK N 32.0
END DESCRIPTION:
XS GIS Cut Line= 3
      3817493.58     10136062.75      3817165.33     10136042.06
       3816768.4     10136073.91
#Sta/Elev= 30
  4671.1  293.63  4716.9  291.26  4726.9  289.64    4757  286.99    4767  284.23
  4774.6   280.5  4779.6  280.72  4787.1  278.29  4845.4  278.43  4877.2  278.15
  4897.3  281.88  4917.3   287.5  4927.3  289.32  4939.3  289.38  4947.4  286.14
  4967.4  273.15  4977.4  272.14  4987.5  270.02  4994.5  264.13  5007.5  265.67
  5017.5  269.75  5067.7  273.69  5077.7  273.58  5087.8  274.54    5158  277.27
  5258.3  283.25  5301.9  285.24  5340.9  288.17  5378.7  290.71  5398.2   291.2
#Mann= 6 ,-1 , 0
  4671.1     .11       0  4845.4     .17       0  4939.3     .12       0
  4967.4     .09       0  5067.7     .15       0  5340.9     .17       0
#Block Obstruct= 2 , 0
       0  4927.3  289.32               0
Bank Sta=4967.4,5067.7
XS Rating Curve= 0 ,0
Exp/Cntr=0.3,0.1

Type RM Length L Ch R = 1 ,15419   ,498,498,498
BEGIN DESCRIPTION:
WEST FORK OF WHITE OAK CREEK N 31.0
END DESCRIPTION:
XS GIS Cut Line= 3
      3817315.05     10135407.37      3817000.36     10135611.33
      3816711.34     10135824.61
#Sta/Elev= 30
    4625  287.62  4669.3   287.4  4691.7  286.12  4744.8  285.19  4770.2  284.66
    4815  280.72  4821.6  280.54  4827.5  278.94  4871.2  276.01  4884.9   274.7
    4900  274.52  4957.4  269.91  4966.6  265.74  4972.6  266.03  4979.2  262.55
  4987.7  261.75  4991.9  257.96  4995.4  257.96  4998.5  261.64  5008.7  262.38
  5015.5  265.61  5052.6  268.71  5102.5  270.57  5201.2  276.93  5215.3  277.69
  5244.6  281.19  5251.7  280.69  5265.5  282.52  5327.4  287.14  5359.2  289.29
#Mann= 8 ,-1 , 0
    4625     .11       0  4744.8     .17       0    4815     .11       0
  4871.2     .17       0  4972.6     .09       0  5015.5     .17       0
  5201.2     .15       0  5327.4     .17       0
Bank Sta=4972.6,5015.5
XS Rating Curve= 0 ,0
Exp/Cntr=0.3,0.1

Type RM Length L Ch R = 1 ,14921   ,487,487,487
BEGIN DESCRIPTION:
WEST FORK OF WHITE OAK CREEK N 30.0
END DESCRIPTION:
XS GIS Cut Line= 3
      3817262.09     10135178.68      3816854.84     10135209.29
      3816559.28     10135502.18
#Sta/Elev= 30
  4591.6  291.08    4646  288.65  4685.7  285.41  4690.7  286.62  4756.3  281.79
  4776.4   279.1  4796.2  279.11  4816.5  278.54  4822.6  277.07  4836.5  276.29
  4866.6  276.81  4906.7  272.92  4936.8  272.44  4946.8  271.55  4959.5  268.69
  4976.9  261.75  4994.2  254.85  5013.3  256.21  5020.4  259.28  5034.5  261.17
  5041.5  261.83  5091.1  265.09  5112.3  264.84  5119.4  266.21  5140.5  265.42
    5183  268.18  5190.1  269.98  5253.7  273.05  5283.6  275.77  5416.1  285.28
#Mann= 7 ,-1 , 0
  4591.6    .125       0  4796.2     .11       0  4959.5     .12       0
  4976.9     .09       0  5034.5     .12       0  5041.5     .15       0
  5283.6     .17       0
Bank Sta=4976.9,5034.5
XS Rating Curve= 0 ,0
Exp/Cntr=0.3,0.1

Type RM Length L Ch R = 1 ,14434   ,511,511,511
BEGIN DESCRIPTION:
WEST FORK OF WHITE OAK CREEK N 29.0
END DESCRIPTION:
XS GIS Cut Line= 3
      3817016.66     10134595.81      3816601.07     10134858.59
      3816359.32     10135327.65
#Sta/Elev= 30
  4508.3  286.24  4518.7  285.52  4526.1  283.22  4562.5  282.76  4589.7  278.05
  4609.2  277.52  4641.4  274.26  4671.8  273.69    4699  271.31  4735.5  270.53
  4743.5  268.61  4782.6  268.64  4790.2  268.49  4844.8  262.66  4923.7  259.54
  4944.9  257.56  4960.1  255.38  4975.4  250.52  4981.3  251.08  4994.8  248.77
  4998.3  248.77  4998.9  250.64  5004.2  250.64  5018.8  256.44  5025.3   257.7
  5262.6  272.23  5329.1  275.34  5428.7  278.84    5494  279.67  5527.7  280.99
#Mann= 11 ,-1 , 0
  4508.3    .125       0  4609.2     .11       0  4671.8    .125       0
  4782.6     .11       0  4790.2     .15       0  4944.9     .12       0
  4960.1     .09       0  5018.8     .12       0  5025.3     .15       0
  5329.1     .17       0    5494     .15       0
Bank Sta=4960.1,5018.8
XS Rating Curve= 0 ,0
Exp/Cntr=0.3,0.1

Type RM Length L Ch R = 1 ,13923   ,500,500,500
BEGIN DESCRIPTION:
WEST FORK OF WHITE OAK CREEK N 28.0
END DESCRIPTION:
XS GIS Cut Line= 3
       3816754.5     10134194.22      3816429.26     10134460.75
      3816172.26     10134898.72
#Sta/Elev= 30
  4579.5  278.42    4582  277.81  4645.9  273.57  4660.3  273.59    4689  271.73
  4719.9  269.06    4741  267.83  4845.8  261.57  4872.7  259.57  4887.1  257.78
  4894.9  257.86  4901.4   256.7  4909.3   256.7  4915.8  255.67  4944.5   253.7
  4950.9  251.31  4958.8  251.01  4973.2  248.82  4979.6  248.61  4987.5  247.11
    4994  247.44  4995.9  246.16  5003.1  246.66  5009.4  249.16  5030.9  252.98
  5124.8   257.3  5271.2  262.88  5336.6  266.13  5382.6  267.28  5507.8   274.1
#Mann= 7 ,-1 , 0
  4579.5     .11       0  4719.9     .17       0    4741     .11       0
  4845.8     .15       0  4944.5     .09       0  5030.9     .15       0
  5124.8     .17       0
Bank Sta=4944.5,5030.9
XS Rating Curve= 0 ,0
Exp/Cntr=0.3,0.1

Type RM Length L Ch R = 1 ,13423   ,500,500,500
BEGIN DESCRIPTION:
WEST FORK OF WHITE OAK CREEK N 27.0
END DESCRIPTION:
XS GIS Cut Line= 3
      3816475.64     10133937.63      3816136.71     10134155.66
      3815815.57     10134597.35
#Sta/Elev= 30
    4597  279.04    4691  270.49    4794  262.05  4815.1  259.86  4821.1  259.94
  4866.6  257.46  4893.7  255.31  4924.1  254.18  4951.2  251.25  4981.5  248.87
  4987.5  245.41  4994.4  243.77  4994.6  243.27  4998.1  243.27  4998.4  243.77
  5003.5   244.8  5031.4  246.57  5039.1  249.42  5053.8  249.64    5060  250.22
  5068.5  249.99  5074.6  250.85  5080.9  250.67  5095.5  251.79    5104  251.67
  5181.3  255.71  5317.3  261.48  5439.5  265.59  5503.6  268.44  5546.1  269.57
#Mann= 4 ,-1 , 0
    4597     .11       0  4981.5     .07       0  5039.1     .11       0
  5439.5     .17       0
Bank Sta=4981.5,5039.1
XS Rating Curve= 0 ,0
Exp/Cntr=0.3,0.1

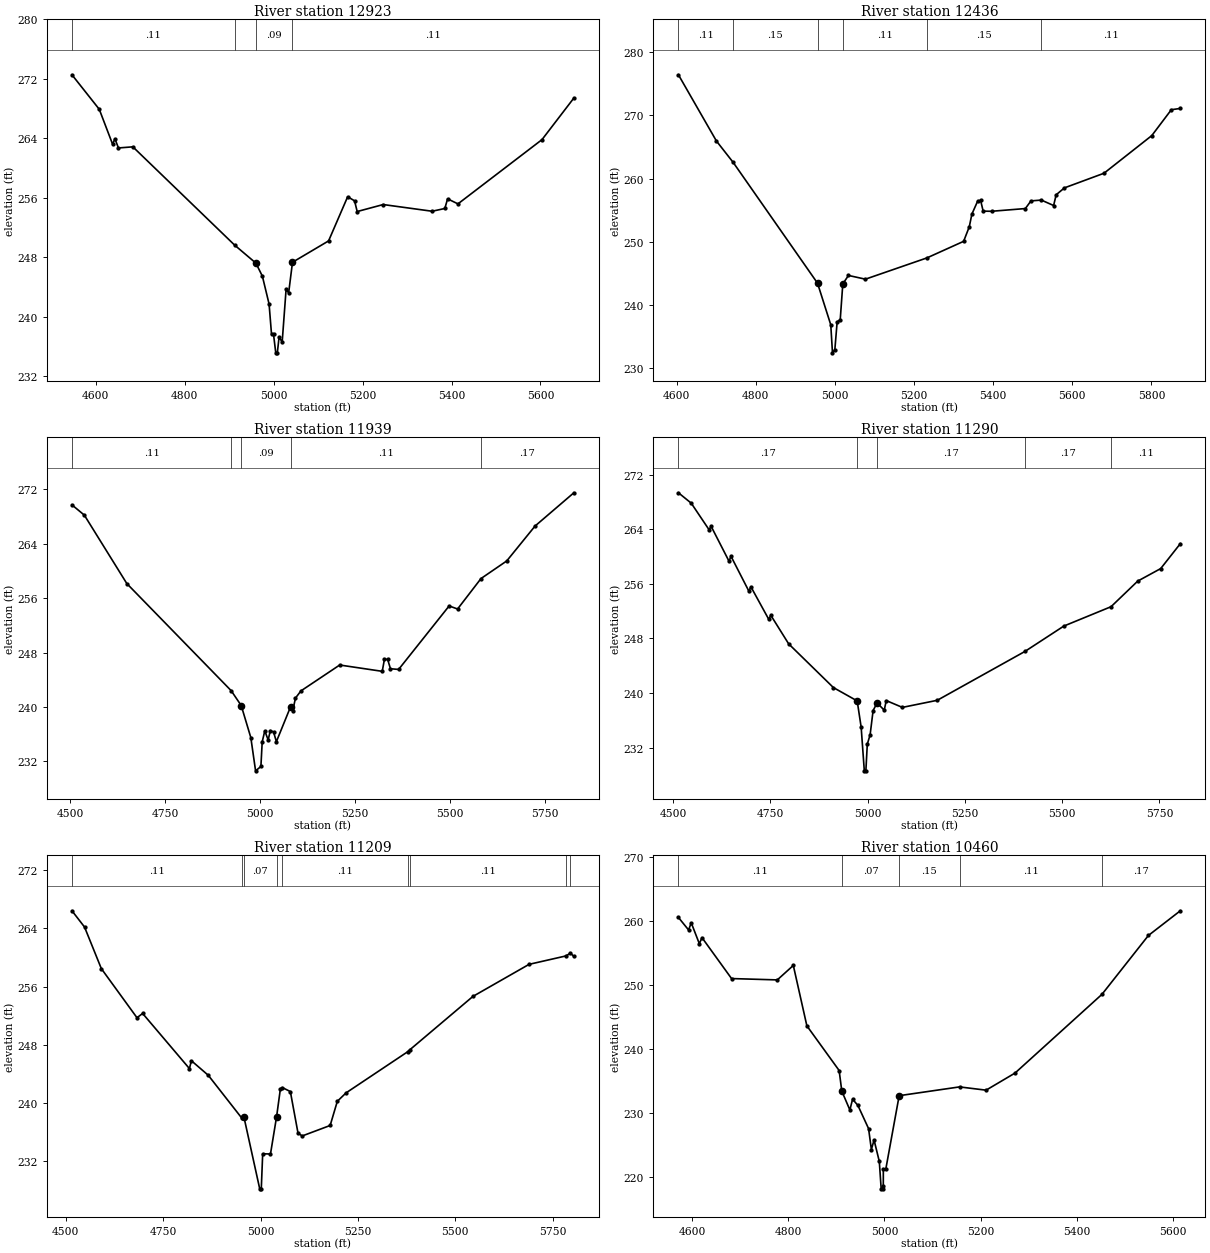
Type RM Length L Ch R = 1 ,12923   ,487,487,487
BEGIN DESCRIPTION:
WEST FORK OF WHITE OAK CREEK N 26.0
END DESCRIPTION:
XS GIS Cut Line= 3
       3816274.8     10133630.88      3815854.53     10133800.22
      3815273.64     10134144.01
#Sta/Elev= 30
  4546.9  272.55  4608.3  267.91  4638.2  263.22  4643.5  263.94  4651.4  262.71
  4683.8  262.86  4912.3  249.66  4960.4  247.22  4974.9  245.47    4990  241.72
  4995.5  237.63    5000  237.63    5005  235.16  5008.5  235.16  5012.5  237.29
  5019.4   236.6  5028.2  243.68    5034  243.24  5042.6  247.34  5123.7  250.21
  5166.6  256.15  5182.1   255.6    5188  254.16  5246.5   255.1  5356.4   254.2
    5385  254.57  5391.2  255.87  5414.5  255.19  5603.4  263.83    5675  269.42
#Mann= 4 ,-1 , 0
  4546.9     .11       0  4912.3     .15       0  4960.4     .09       0
  5042.6     .11       0
Bank Sta=4960.4,5042.6
XS Rating Curve= 0 ,0
Exp/Cntr=0.3,0.1

Type RM Length L Ch R = 1 ,12436   ,497,497,497
BEGIN DESCRIPTION:
WEST FORK OF WHITE OAK CREEK N 25.0
END DESCRIPTION:
XS GIS Cut Line= 3
      3816174.38     10133299.01      3815794.84      10133409.5
        3815229.      10134074.3
#Sta/Elev= 30
  4604.7   276.4  4700.8  265.93    4743  262.56  4956.2  243.47  4989.7  236.89
    4994  232.46    5000  232.96  5005.8  237.35  5013.6   237.7  5020.1  243.35
  5034.4  244.69  5077.2   244.1  5232.6  247.46  5325.4  250.08  5339.7  252.38
  5346.3  254.38  5360.6   256.4  5368.3  256.56  5374.8  254.85    5396  254.83
  5481.4  255.26  5495.6  256.47  5521.8   256.6  5552.8  255.74  5559.3  257.44
  5580.2  258.53  5680.1  260.84  5800.9  266.79  5850.3  270.88    5873  271.08
#Mann= 6 ,-1 , 0
  4604.7     .11       0    4743     .15       0  4956.2     .09       0
  5020.1     .11       0  5232.6     .15       0  5521.8     .11       0
Bank Sta=4956.2,5020.1
XS Rating Curve= 0 ,0
Exp/Cntr=0.3,0.1

Type RM Length L Ch R = 1 ,11939   ,649,649,649
BEGIN DESCRIPTION:
WEST FORK OF WHITE OAK CREEK N 24.0
END DESCRIPTION:
XS GIS Cut Line= 3
      3816023.83     10132875.09      3815558.58     10133043.82
       3814843.7     10133456.61
#Sta/Elev= 30
  4505.1  269.73  4537.7  268.22  4649.5  258.15  4923.9   242.4  4950.4  240.21
  4975.7  235.49  4988.2   230.6  5002.2  231.24  5005.6  234.86  5012.4  236.48
  5021.3  235.15  5027.1  236.52  5035.5  236.32  5042.9  234.89  5080.2  240.02
    5086  239.47  5093.2  241.31  5107.5  242.36  5209.5  246.17  5321.4  245.24
  5327.2  247.02  5335.7  246.99    5343  245.62  5364.5  245.52  5497.4  254.86
  5519.6  254.41  5581.2  258.89  5648.9  261.48  5723.5  266.62  5825.5  271.51
#Mann= 5 ,-1 , 0
  4505.1     .11       0  4923.9     .15       0  4950.4     .09       0
  5080.2     .11       0  5581.2     .17       0
Bank Sta=4950.4,5080.2
XS Rating Curve= 0 ,0
Exp/Cntr=0.3,0.1

Type RM Length L Ch R = 1 ,11290   ,81,81,81
BEGIN DESCRIPTION:
WEST FORK OF WHITE OAK CREEK N 23.0
END DESCRIPTION:
XS GIS Cut Line= 3
      3815948.28     10132520.29      3815471.72     10132615.11
       3814691.5     10132807.53
#Sta/Elev= 30
  4514.1  269.35    4547  267.83    4593  263.92  4598.1  264.44  4644.1  259.32
  4649.2  260.04  4695.2  254.92  4700.3  255.57  4746.3  250.79  4751.4   251.4
  4797.4   247.2  4912.2   240.8  4973.4  238.84  4983.6     235  4991.7  228.59
  4995.7  228.59  4999.4  232.51  5006.6  233.86  5014.3  237.43  5024.6  238.55
  5042.9  237.48  5048.1  238.89  5089.5  237.89  5179.1  238.93  5404.3  246.09
  5504.3  249.81  5625.6  252.65  5694.1   256.4  5753.2  258.24  5803.6  261.89
#Mann= 5 ,-1 , 0
  4514.1     .17       0  4973.4     .09       0  5024.6     .17       0
  5404.3     .17       0  5625.6     .11       0
Bank Sta=4973.4,5024.6
XS Rating Curve= 0 ,0
Exp/Cntr=0.3,0.1

Type RM Length L Ch R = 1 ,11209   ,749,749,749
BEGIN DESCRIPTION:
WEST FORK OF WHITE OAK CREEK N 22.0
END DESCRIPTION:
XS GIS Cut Line= 3
      3815924.77     10132429.05      3815452.91     10132535.88
      3814665.27     10132697.26
#Sta/Elev= 30
  4516.2  266.44  4548.5   264.2  4591.6  258.47    4683  251.71  4697.6  252.29
  4817.6   244.7  4822.7  245.78  4865.9  243.78  4952.2  237.86  4957.3  238.07
    4998  228.13    5002  228.13  5005.6  232.96  5025.6  232.93 5041.34  238.09
  5050.9  241.86  5056.2  242.08  5076.6  241.53  5096.3  235.79  5107.2  235.42
  5178.7  236.86  5197.1  240.19  5219.5  241.35  5377.7  247.02  5382.5  247.26
    5545  254.64  5689.1  259.06  5783.8  260.22  5795.2  260.61    5804  260.15
#Mann= 9 ,-1 , 0
  4516.2     .11       0  4952.2     .11       0  4957.3     .07       0
 5041.34     .11       0  5056.2     .11       0  5377.7     .17       0
  5382.5     .11       0  5783.8     .17       0  5795.2     .11       0
Bank Sta=4957.3,5041.34
XS Rating Curve= 0 ,0
Exp/Cntr=0.3,0.1

Type RM Length L Ch R = 1 ,10460   ,498,498,498
BEGIN DESCRIPTION:
WEST FORK OF WHITE OAK CREEK N 21.0
END DESCRIPTION:
XS GIS Cut Line= 3
       3816041.5     10132155.61      3815658.32     10131964.05
      3815045.46     10131910.41
#Sta/Elev= 30
  4571.6  260.58  4592.7  258.63  4598.3  259.74  4615.1  256.48  4620.6  257.43
  4682.1  251.04  4777.2  250.83  4810.5  253.09  4838.7  243.66  4905.8  236.69
  4911.3  233.48  4928.1  230.53  4933.7   232.2  4944.6  231.27    4967  227.62
  4972.8  224.36  4978.4  225.84  4989.3   222.5  4993.2  218.22  4997.3  218.22
  4997.6  218.72  4997.7  221.25  5002.7  221.25  5030.6  232.76  5156.1  234.13
  5211.3  233.62  5271.5  236.29  5452.3  248.58  5548.9  257.77  5615.2  261.62
#Mann= 5 ,-1 , 0
  4571.6     .11       0  4911.3     .07       0  5030.6     .15       0
  5156.1     .11       0  5452.3     .17       0
Bank Sta=4911.3,5030.6
XS Rating Curve= 0 ,0
Exp/Cntr=0.3,0.1

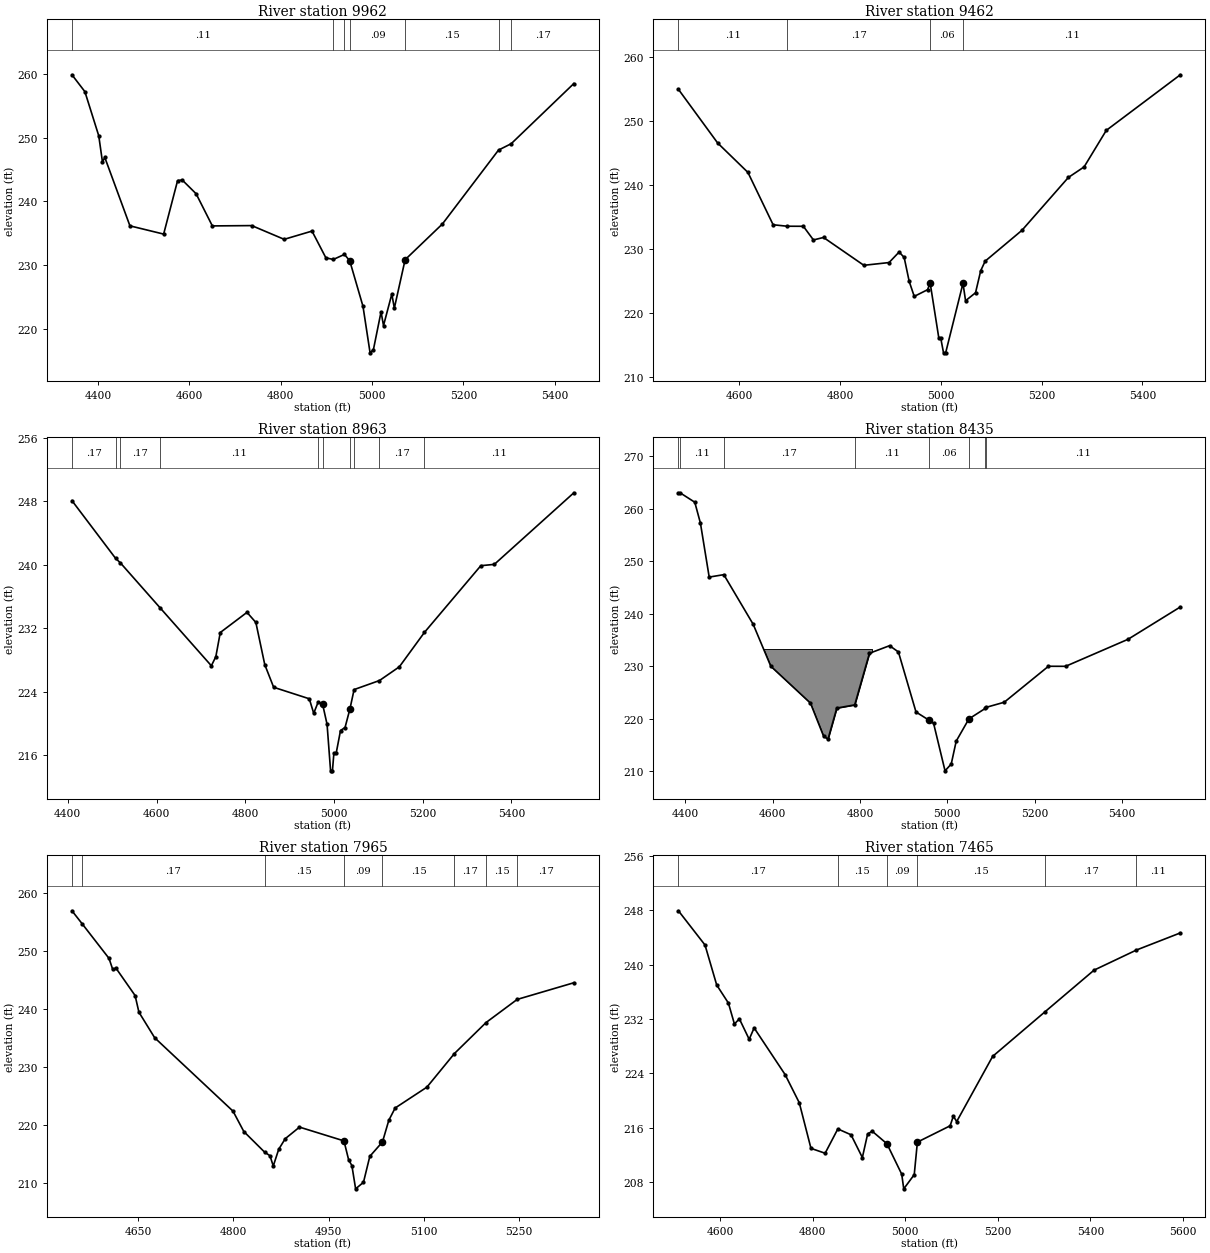
Type RM Length L Ch R = 1 ,9962    ,500,500,500
BEGIN DESCRIPTION:
WEST FORK OF WHITE OAK CREEK N 20.0
END DESCRIPTION:
XS GIS Cut Line= 3
      3816145.72     10131647.82      3815498.19     10131537.24
      3815091.94     10131710.36
#Sta/Elev= 30
  4343.1  259.83  4371.4  257.19  4401.8  250.27  4409.9  246.17    4415  246.89
    4470  236.18  4543.8  234.89  4574.3  243.26  4584.4  243.36  4614.8  241.21
  4650.4  236.17  4736.6  236.22  4807.6  234.07  4868.5  235.36  4898.9  231.17
  4915.2  230.92  4939.5  231.71  4951.1  230.71  4980.1  223.58  4995.6   216.3
  5002.9   216.8  5019.6  222.71    5025  220.57  5043.2   225.5  5048.7   223.3
  5072.3  230.88    5154  236.48  5276.7  248.04  5304.5  249.04  5441.6  258.46
#Mann= 7 ,-1 , 0
  4343.1     .11       0  4915.2     .15       0  4939.5     .12       0
  4951.1     .09       0  5072.3     .15       0  5276.7     .11       0
  5304.5     .17       0
Bank Sta=4951.1,5072.3
XS Rating Curve= 0 ,0
Exp/Cntr=0.3,0.1

Type RM Length L Ch R = 1 ,9462    ,499,499,499
BEGIN DESCRIPTION:
WEST FORK OF WHITE OAK CREEK N 19.0
END DESCRIPTION:
XS GIS Cut Line= 3
      3816145.71     10131105.29       3815625.3     10131095.61
      3815160.89     10130994.44
#Sta/Elev= 30
  4479.5  255.01  4557.4   246.6  4617.4     242  4667.4   233.8  4695.3  233.57
  4727.4  233.56  4747.4  231.42  4767.4  231.81  4847.4  227.45  4897.4  227.88
  4917.4  229.53  4927.4  228.68  4937.4  224.92  4947.4  222.58  4973.9  223.63
  4978.9  224.71  4996.2  216.03    5000  216.03  5005.5  213.74  5009.7  213.74
  5044.1  224.63  5049.2   221.9    5069  223.15  5079.3  226.61  5088.1   228.1
  5161.1  232.93  5253.2  241.21  5284.4  242.86  5328.4  248.58  5475.3  257.29
#Mann= 4 ,-1 , 0
  4479.5     .11       0  4695.3     .17       0  4978.9     .06       0
  5044.1     .11       0
#XS Ineff= 2 , 0
       0  4917.4  229.53               0
Permanent Ineff=
       F       F
Bank Sta=4978.9,5044.1
XS Rating Curve= 0 ,0
Exp/Cntr=0.3,0.1

Type RM Length L Ch R = 1 ,8963    ,528,528,528
BEGIN DESCRIPTION:
WEST FORK OF WHITE OAK CREEK N 18.0
END DESCRIPTION:
XS GIS Cut Line= 3
      3816241.15     10130695.13      3815652.29     10130649.83
      3815122.17     10130755.74
#Sta/Elev= 30
  4409.4  248.09  4507.7  240.82  4518.7  240.24  4608.1  234.58  4723.6  227.28
  4733.7  228.43  4743.7  231.47  4803.9  234.01  4823.9  232.74    4844  227.42
    4864  224.57  4944.3  223.12  4954.3  221.29  4964.3   222.7  4974.4  222.42
  4984.4   219.9  4992.3  214.04  4996.5  214.04  4999.7  216.23  5004.8  216.23
  5014.7  219.12  5024.9   219.5    5036  221.86  5045.3  224.28  5102.5  225.42
  5147.3  227.15  5203.9  231.49  5330.9  239.89  5361.4  240.06  5540.6  249.08
#Mann= 10 ,-1 , 0
  4409.4     .17       0  4507.7     .11       0  4518.7     .17       0
  4608.1     .11       0  4964.3     .12       0  4974.4     .09       0
    5036     .12       0  5045.3     .15       0  5102.5     .17       0
  5203.9     .11       0
Bank Sta=4974.4,5036
XS Rating Curve= 0 ,0
Exp/Cntr=0.3,0.1

Type RM Length L Ch R = 1 ,8435    ,470,470,470
BEGIN DESCRIPTION:
WEST FORK OF WHITE OAK CREEK N 17.0
END DESCRIPTION:
XS GIS Cut Line= 3
      3816267.81     10130111.08      3815656.72     10130188.64
      3815129.35     10130105.98
#Sta/Elev= 30
    4384  263.02  4388.1     263  4421.5  261.22  4434.4  257.25  4454.5  246.97
    4488  247.43  4555.3  237.98  4595.6     230  4686.4  222.98  4716.6  216.67
  4726.7  216.12  4746.8  222.03  4787.9  222.64  4821.6  232.46  4867.8  233.91
    4888  232.71  4928.3  221.28  4958.5   219.7  4968.6  219.11  4994.8  210.08
    5009  211.38  5020.4  215.74  5049.5  219.97  5087.1  221.97  5089.5  222.18
  5130.4  223.14  5231.7  229.99    5271  229.98  5413.9  235.12  5533.8  241.28
#Mann= 8 ,-1 , 0
    4384     .17       0  4388.1     .11       0    4488     .17       0
  4787.9     .11       0  4958.5     .06       0  5049.5     .11       0
  5087.1     .15       0  5089.5     .11       0
#Block Obstruct= 2 , 0
       0  4827.5  233.28               0
Bank Sta=4958.5,5049.5
XS Rating Curve= 0 ,0
Exp/Cntr=0.3,0.1

Type RM Length L Ch R = 1 ,7965    ,500,500,500
BEGIN DESCRIPTION:
WEST FORK OF WHITE OAK CREEK N 16.0
END DESCRIPTION:
XS GIS Cut Line= 3
      3816274.64     10129881.72      3815833.01     10129772.22
       3815496.2     10129790.37
#Sta/Elev= 30
    4545  256.95    4561  254.72  4603.5  248.73  4609.3  246.84  4614.5  247.04
  4644.7  242.31  4650.7  239.44  4675.6  235.02  4799.3  222.34  4816.3  218.83
  4849.2  215.26  4857.6  214.65  4862.8  212.87  4871.4  215.76  4881.7  217.59
  4904.2  219.59  4974.4  217.21  4981.8  213.93  4986.9  212.95  4992.8  208.93
  5005.2  210.06  5015.2  214.54  5035.2  217.03  5045.2  220.77  5055.2  222.89
  5105.3  226.49  5148.8   232.3  5198.6  237.64  5247.8  241.64  5337.3  244.52
#Mann= 8 ,-1 , 0
    4545     .11       0    4561     .17       0  4849.2     .15       0
  4974.4     .09       0  5035.2     .15       0  5148.8     .17       0
  5198.6     .15       0  5247.8     .17       0
Bank Sta=4974.4,5035.2
XS Rating Curve= 0 ,0
Exp/Cntr=0.3,0.1

Type RM Length L Ch R = 1 ,7465    ,498,498,498
BEGIN DESCRIPTION:
WEST FORK OF WHITE OAK CREEK N 15.0
END DESCRIPTION:
XS GIS Cut Line= 3
      3816361.74      10129503.9      3815900.38     10129336.76
      3815492.42      10129769.2
#Sta/Elev= 30
  4509.3  247.92  4566.8  242.88  4592.1  236.99  4617.4  234.33  4630.4  231.25
  4641.1  232.01  4662.3     229    4673  230.67    4740   223.8  4770.6  219.66
  4795.9  212.94  4826.5  212.22    4854   215.8  4882.5  214.94    4907  211.59
  4918.4  215.05  4928.2  215.47  4960.1  213.62  4992.1  209.14  4996.5  206.98
  5019.2  209.07    5026  213.86  5096.8  216.26  5103.7  217.68    5111  216.89
  5188.7  226.48  5302.3  233.07    5408  239.18  5499.6  242.14  5594.5  244.66
#Mann= 6 ,-1 , 0
  4509.3     .17       0    4854     .15       0  4960.1     .09       0
    5026     .15       0  5302.3     .17       0  5499.6     .11       0
Bank Sta=4960.1,5026
XS Rating Curve= 0 ,0
Exp/Cntr=0.3,0.1

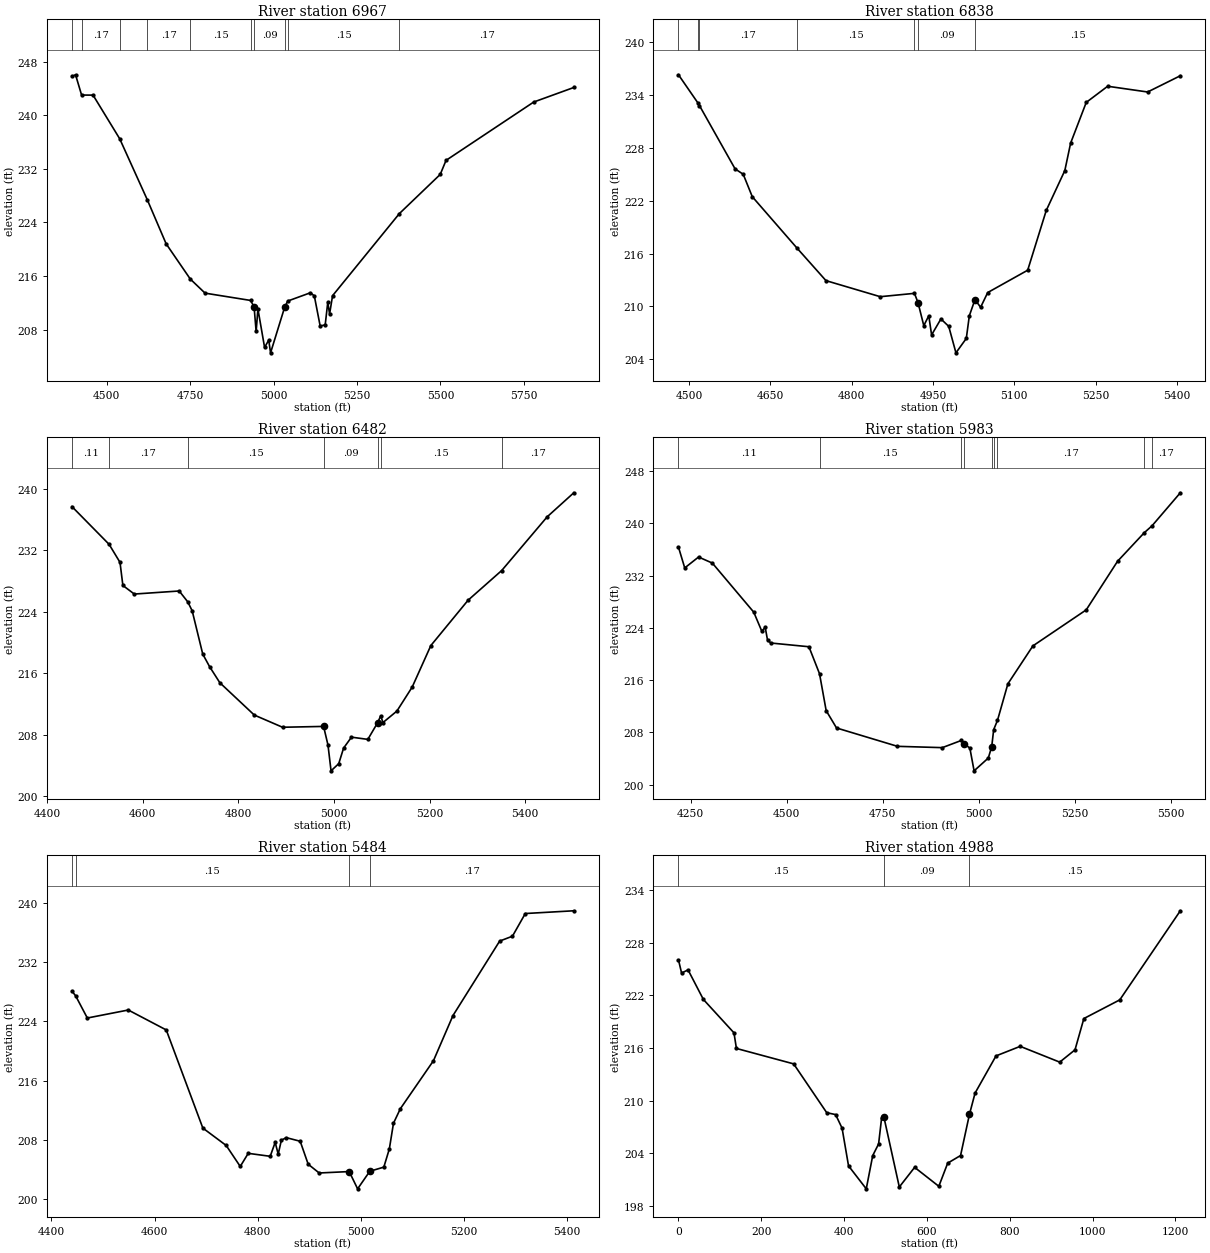
Type RM Length L Ch R = 1 ,6967    ,129,129,129
BEGIN DESCRIPTION:
WEST FORK OF WHITE OAK CREEK N 33.0
END DESCRIPTION:
XS GIS Cut Line= 3
      3816428.16     10129121.95       3815852.4     10128940.75
      3815472.78     10129755.99
#Sta/Elev= 30
  4396.4  245.82  4407.2  246.07  4425.3  243.04  4459.6  243.03  4539.4  236.51
    4622   227.4  4678.5  220.81  4750.9  215.54  4795.1  213.44  4931.4  212.35
  4941.9  211.38    4948  207.71  4953.3  211.09  4973.3  205.33  4985.7  206.42
  4991.2  204.52  5033.5  211.35  5042.6  212.26  5110.7   213.5  5122.3  213.02
  5139.7  208.54  5154.8  208.69  5162.5  212.06    5168  210.34  5176.9  213.06
    5377  225.33  5499.3  231.18  5516.7  233.28  5779.4     242  5899.3  244.17
#Mann= 10 ,-1 , 0
  4396.4     .11       0  4425.3     .17       0  4539.4     .11       0
    4622     .17       0  4750.9     .15       0  4931.4     .12       0
  4941.9     .09       0  5033.5     .12       0  5042.6     .15       0
    5377     .17       0
Bank Sta=4941.9,5033.5
XS Rating Curve= 0 ,0
Exp/Cntr=0.3,0.1

Type RM Length L Ch R = 1 ,6838    ,356,356,356
BEGIN DESCRIPTION:
WEST FORK OF WHITE OAK CREEK N 14.0
END DESCRIPTION:
XS GIS Cut Line= 3
       3816306.9     10129013.62      3815814.47     10128849.04
      3815422.95     10128740.44
#Sta/Elev= 30
  4480.8  236.25  4516.3  233.09  4519.5  232.76  4585.2  225.59  4600.2  224.98
  4616.9  222.44  4698.9  216.65  4752.8  212.93  4852.9  211.11    4916  211.49
  4922.6  210.43  4933.2  207.83  4942.4  208.95  4947.6  206.78  4964.8  208.59
  4979.2  207.75  4992.5  204.75  5011.6  206.38  5017.2  208.95  5027.6  210.78
    5038  209.91  5051.1  211.58  5124.8  214.11  5159.1  220.89  5193.3   225.4
    5204  228.51  5232.8  233.12  5272.3  234.95    5346   234.3  5406.3  236.14
#Mann= 7 ,-1 , 0
  4480.8     .17       0  4516.3     .11       0  4519.5     .17       0
  4698.9     .15       0    4916     .12       0  4922.6     .09       0
  5027.6     .15       0
Bank Sta=4922.6,5027.6
XS Rating Curve= 0 ,0
Exp/Cntr=0.3,0.1

Type RM Length L Ch R = 1 ,6482    ,499,499,499
BEGIN DESCRIPTION:
WEST FORK OF WHITE OAK CREEK N 13.0
END DESCRIPTION:
XS GIS Cut Line= 3
      3816377.21     10128890.73      3815917.63     10128592.25
      3815422.99      10128510.2
#Sta/Elev= 30
    4452  237.72  4529.7   232.8  4552.5  230.45  4558.5  227.44  4582.4  226.32
  4676.3  226.72  4694.2   225.3  4703.4  224.14  4725.5   218.5  4739.7  216.87
  4761.3  214.76  4833.3  210.55  4892.4  208.96  4978.2  209.07  4987.4  206.64
  4993.8  203.28  5009.9  204.22    5020  206.24  5036.5  207.67  5070.7  207.38
    5091  209.53  5097.5  210.43  5102.5  209.58  5131.5  211.07  5163.5   214.2
  5202.5  219.61  5280.4  225.52  5350.7  229.39  5445.8  236.39  5501.4  239.52
#Mann= 7 ,-1 , 0
    4452     .11       0  4529.7     .17       0  4694.2     .15       0
  4978.2     .09       0    5091     .12       0  5097.5     .15       0
  5350.7     .17       0
Bank Sta=4978.2,5091
XS Rating Curve= 0 ,0
Exp/Cntr=0.3,0.1

Type RM Length L Ch R = 1 ,5983    ,499,499,499
BEGIN DESCRIPTION:
WEST FORK OF WHITE OAK CREEK N 12.0
END DESCRIPTION:
XS GIS Cut Line= 3
       3816431.8     10128839.95      3815992.08     10128193.41
      3815477.64     10128090.67
#Sta/Elev= 30
  4218.1  236.34  4234.4  233.16  4270.4  234.83  4306.3   233.9  4414.1  226.39
    4435  223.48  4443.9  224.07    4450   222.1  4458.6  221.67  4557.7   221.1
  4585.3  216.97  4602.6  211.32  4629.6  208.67  4788.2  205.86  4904.9  205.66
  4954.5  206.76  4961.8  206.26  4976.7  205.59  4987.7  202.11  5024.7  204.07
  5033.6  205.81  5038.7  208.42  5048.6  209.83  5075.7  215.43  5140.8  221.23
  5279.6  226.74  5361.2  234.18  5430.4  238.53    5451  239.61  5524.6  244.66
#Mann= 9 ,-1 , 0
  4218.1     .11       0  4585.3     .15       0  4954.5     .12       0
  4961.8     .09       0  5033.6     .12       0  5038.7     .15       0
  5048.6     .17       0  5430.4     .11       0    5451     .17       0
Bank Sta=4961.8,5033.6
XS Rating Curve= 0 ,0
Exp/Cntr=0.3,0.1

Type RM Length L Ch R = 1 ,5484    ,496,496,496
BEGIN DESCRIPTION:
WEST FORK OF WHITE OAK CREEK N 11.0
END DESCRIPTION:
XS GIS Cut Line= 3
      3816560.61     10128287.77      3816269.39     10127809.33
      3815883.49     10127663.33
#Sta/Elev= 30
  4439.9  228.07    4447  227.44  4469.7  224.44  4549.1  225.52  4622.7  222.83
  4693.6  209.59  4738.9  207.24  4766.1  204.41  4781.6  206.18  4824.2  205.78
  4833.8  207.66  4839.7  206.07  4845.8  207.95  4855.2   208.3  4882.3  207.81
  4897.8  204.71  4919.1  203.53  4977.3  203.72  4993.6  201.39  5017.2  203.76
  5044.4  204.32  5055.1  206.78  5063.1  210.24  5076.5  212.21  5140.6  218.68
  5178.4  224.77  5268.9  234.82  5293.7  235.48  5318.6  238.54  5412.6  238.91
#Mann= 4 ,-1 , 0
  4439.9     .17       0    4447     .15       0  4977.3     .09       0
  5017.2     .17       0
Bank Sta=4977.3,5017.2
XS Rating Curve= 0 ,0
Exp/Cntr=0.3,0.1

Type RM Length L Ch R = 1 ,4988    ,499,499,499
XS GIS Cut Line= 3
      3817152.99     10127907.72      3816618.16     10127589.11
      3816111.79     10127286.73
#Sta/Elev= 30
       0  226.05     7.5  224.55    23.1  224.91    60.1  221.54     134  217.73
   139.9  215.95   278.1  214.19     358  208.62   379.4  208.41     395  206.86
   410.6  202.56   453.4  199.94     469  203.73   483.2  205.06   490.4  207.99
   496.2  208.08   533.2  200.15   570.2  202.39   628.6  200.23     650  202.87
   681.1  203.74   702.5  208.42   716.1  210.86   766.7   215.1   825.1  216.19
   920.5  214.39   957.4  215.79   978.8  219.36  1065.5  221.49  1211.7  231.65
#Mann= 3 , 0 , 0
       0     .15       0   496.2     .09       0   702.5     .15       0
Bank Sta=496.2,702.5
XS Rating Curve= 0 ,0
Exp/Cntr=0.3,0.1