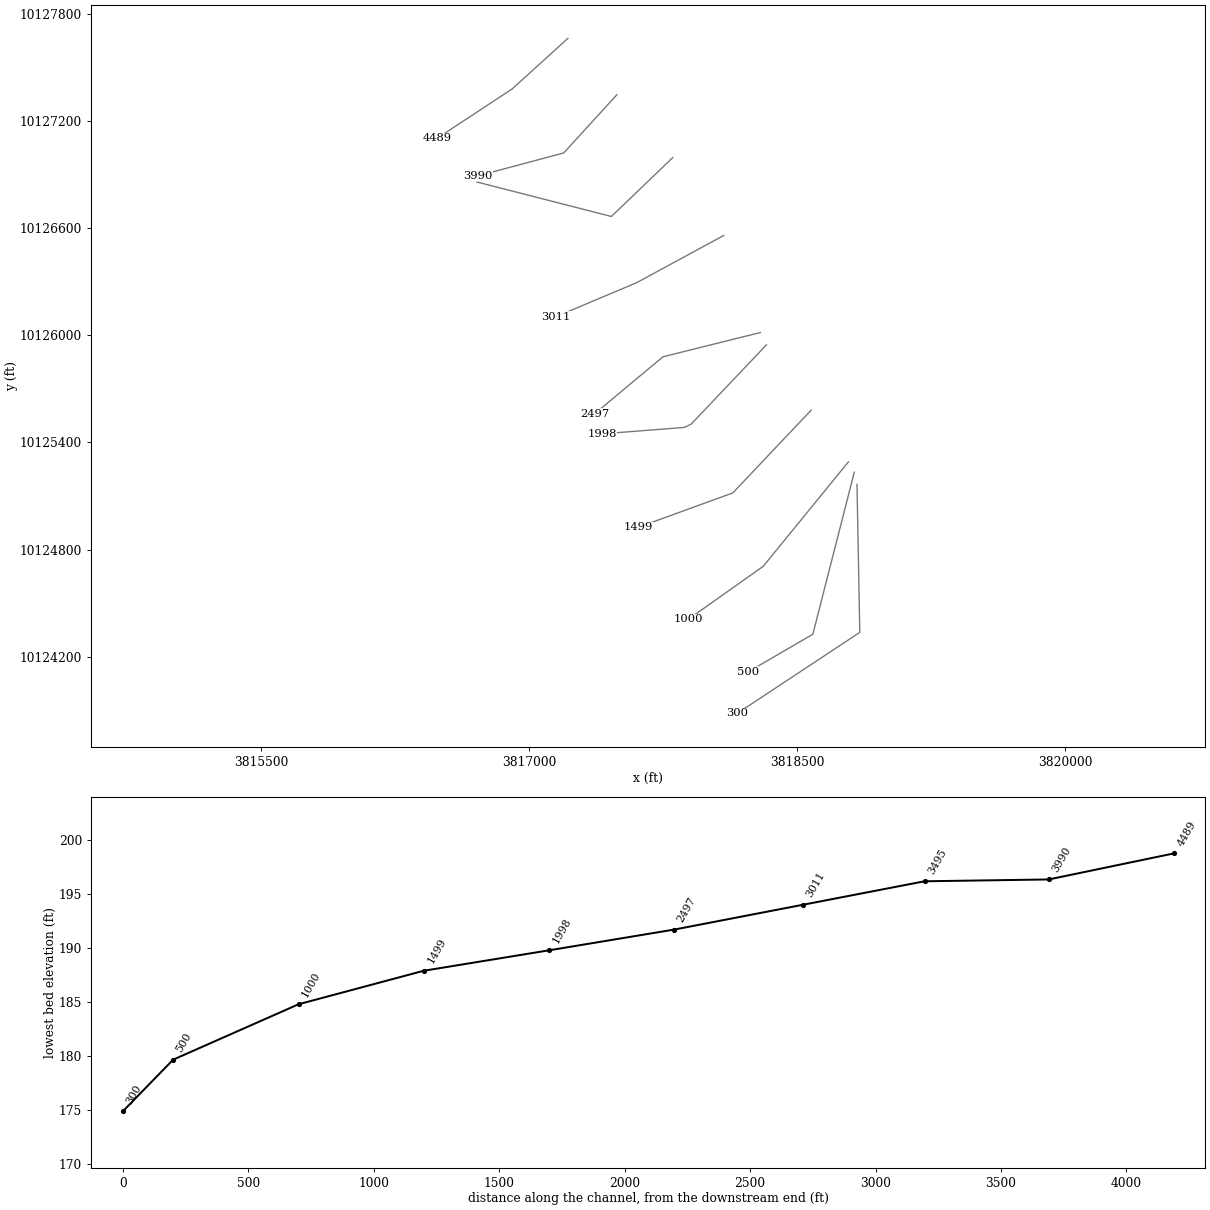
HEC-RAS study WEST FORK OF WHITE OAK CREEK N.prj: WEST FORK OF WHITE OAK CREEK N Base Level Engineering

--- WEST FORK OF WHITE OAK CREEK N.g01 (geometry) --- (continued)

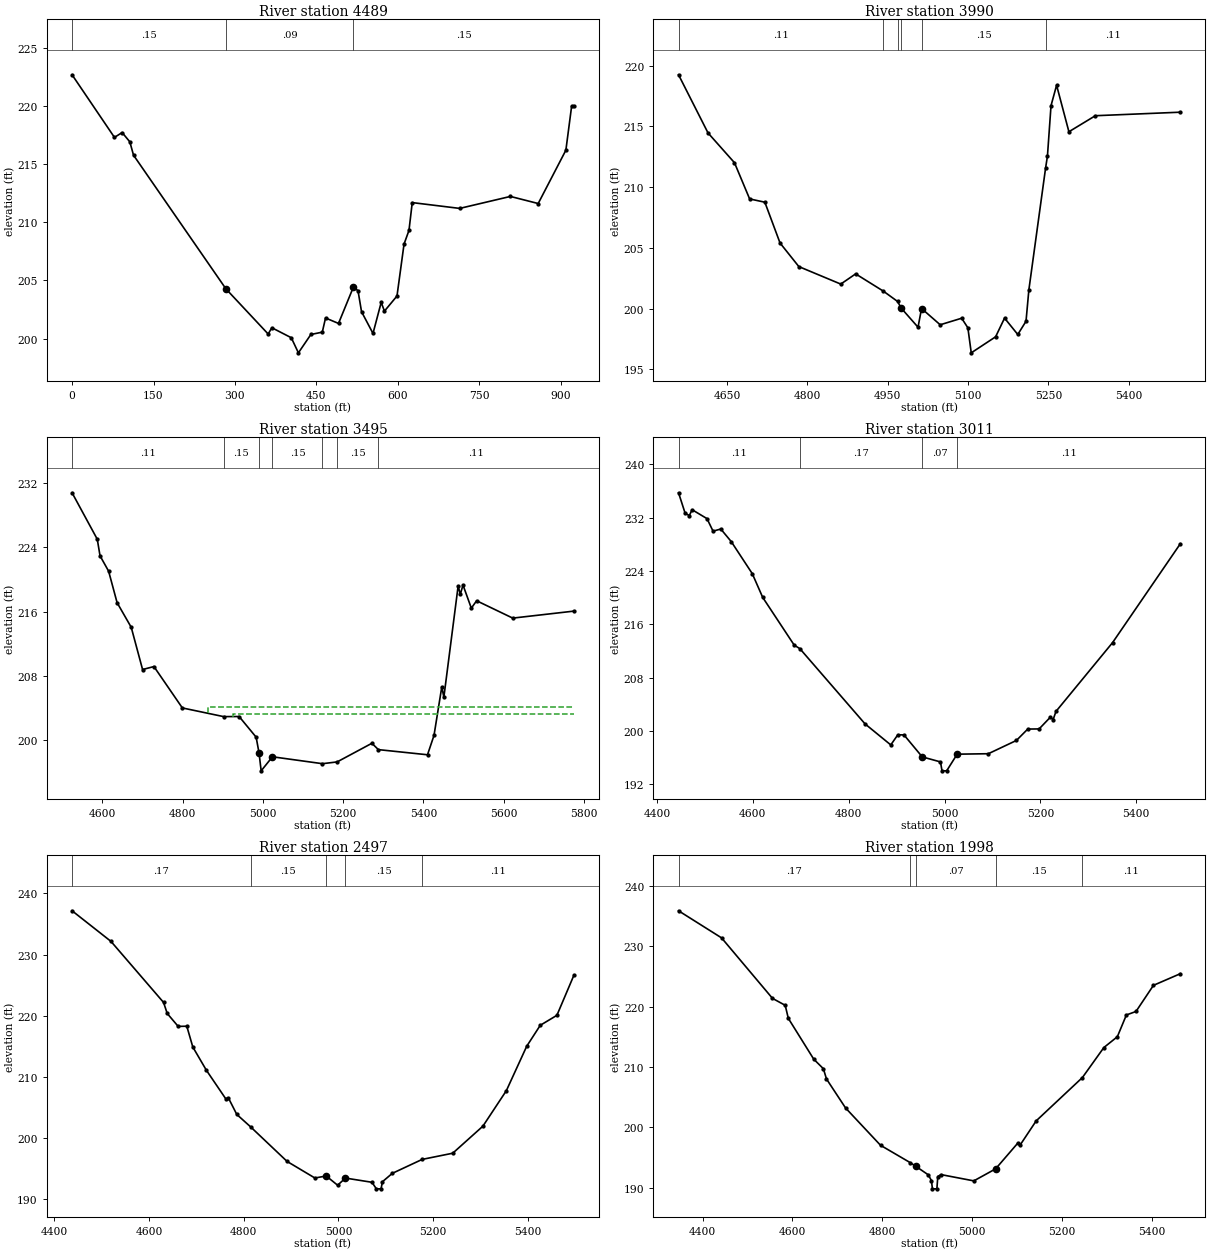
Type RM Length L Ch R = 1 ,4489    ,499,499,499
XS GIS Cut Line= 3
      3817217.85     10127661.07      3816905.46     10127377.57
      3816485.57     10127101.56
#Sta/Elev= 30
       0   222.7    78.1  217.31    92.2  217.73   106.4  216.93   113.2  215.78
   283.5  204.27   361.2  200.39     368  200.93   403.8  200.07   416.9  198.77
   439.9  200.35   460.9  200.55   466.9  201.77   490.8   201.3   518.2  204.43
   526.7  204.12   533.2  202.31   554.3  200.44   569.4  203.11   575.4  202.36
   598.5  203.66   611.5  208.13   620.6  209.31   626.6   211.7     714   211.2
   807.4  212.23   858.6  211.62   909.6  216.21   920.2     220   924.3     220
#Mann= 3 , 0 , 0
       0     .15       0   283.5     .09       0   518.2     .15       0
Bank Sta=283.5,518.2
XS Rating Curve= 0 ,0
Exp/Cntr=0.3,0.1

Type RM Length L Ch R = 1 ,3990    ,495,495,495
BEGIN DESCRIPTION:
WEST FORK OF WHITE OAK CREEK N 8.0
END DESCRIPTION:
XS GIS Cut Line= 3
      3817491.54     10127345.13       3817194.2     10127019.85
      3816714.57     10126891.53
#Sta/Elev= 30
  4559.3  219.25  4614.4  214.46  4663.8  212.01  4692.1  209.03  4720.5  208.76
  4748.9   205.4    4784  203.46  4862.3  202.02  4890.1  202.86  4941.8  201.44
  4968.4  200.59  4975.2  200.04  5006.6  198.47  5013.2  200.01    5048  198.67
  5088.1  199.21  5099.7  198.42    5106  196.36  5151.5  197.68  5168.2  199.22
  5192.9  197.87  5208.3  198.96  5213.6  201.54  5244.8  211.56  5248.3  212.55
    5255  216.71  5265.4  218.39  5288.4  214.56  5337.8  215.88  5496.5  216.17
#Mann= 6 ,-1 , 0
  4559.3     .11       0  4941.8     .15       0  4968.4     .12       0
  4975.2     .09       0  5013.2     .15       0  5244.8     .11       0
Bank Sta=4975.2,5013.2
XS Rating Curve= 0 ,0
Exp/Cntr=0.3,0.1

Type RM Length L Ch R = 1 ,3495    ,484,484,484
BEGIN DESCRIPTION:
WEST FORK OF WHITE OAK CREEK N 7.0
END DESCRIPTION:
XS GIS Cut Line= 3
      3817804.01     10126993.53      3817461.14     10126664.36
      3816710.31     10126856.81
#Sta/Elev= 30
  4524.7   230.8  4587.5  225.02  4594.4  222.95  4615.8  221.04  4636.9  217.12
  4672.1  214.06  4700.4   208.8  4728.7  209.17  4799.5  204.02  4902.3  202.94
    4941  202.95  4983.4  200.38  4990.6  198.42  4995.9  196.19    5024  197.94
  5148.6  197.08  5185.2   197.3  5271.8  199.62    5288  198.83  5410.4  198.19
  5426.6   200.6    5446  206.64  5451.2  205.37  5486.8  219.22    5492  218.15
  5498.9  219.31  5519.6  216.44  5532.8  217.36  5622.8   215.2  5775.1  216.07
#Mann= 7 ,-1 , 0
  4524.7     .11       0  4902.3     .15       0  4990.6     .07       0
    5024     .15       0  5148.6     .11       0  5185.2     .15       0
    5288     .11       0
#XS Ineff= 2 ,-1
  4863.3  4785.3  204.08  4926.8  4863.3  203.21
Permanent Ineff=
       F       F
Bank Sta=4990.6,5024
XS Rating Curve= 0 ,0
Exp/Cntr=0.3,0.1

Type RM Length L Ch R = 1 ,3011    ,514,514,514
BEGIN DESCRIPTION:
WEST FORK OF WHITE OAK CREEK N 6.0
END DESCRIPTION:
XS GIS Cut Line= 3
      3818090.04     10126558.26       3817602.1      10126293.8
      3817148.82     10126102.74
#Sta/Elev= 30
    4445  235.75  4458.9  232.65  4467.6  232.34  4473.3  233.21  4504.4  231.87
    4517  229.99  4533.2  230.31    4555  228.42  4598.8  223.62  4620.6  220.05
  4686.4  212.88  4698.1  212.36  4834.2  201.06  4887.8  197.91  4902.5  199.43
  4915.4  199.41  4953.5  196.11  4991.5  195.36  4994.7  194.02  5004.4  194.02
  5026.3  196.52  5091.4  196.59  5149.9  198.58  5173.6  200.29  5197.3  200.31
    5221  202.09  5226.5   201.7  5232.5  202.94  5350.5  213.26  5491.9   228.1
#Mann= 4 ,-1 , 0
    4445     .11       0  4698.1     .17       0  4953.5     .07       0
  5026.3     .11       0
Bank Sta=4953.5,5026.3
XS Rating Curve= 0 ,0
Exp/Cntr=0.3,0.1

Type RM Length L Ch R = 1 ,2497    ,499,499,499
BEGIN DESCRIPTION:
WEST FORK OF WHITE OAK CREEK N 5.0
END DESCRIPTION:
XS GIS Cut Line= 3
      3818295.24     10126015.25       3817749.6     10125879.37
      3817367.88      10125561.1
#Sta/Elev= 30
  4437.7  237.15  4519.8  232.15  4630.8  222.18  4638.6  220.37  4661.7  218.26
  4679.9  218.29  4692.6  214.89  4721.2   211.1  4762.5  206.39  4767.6  206.59
  4785.4  203.88  4814.4  201.86  4891.6   196.2  4950.3  193.49  4974.2  193.82
  4998.3  192.31  5014.8  193.48  5070.8  192.79  5080.1  191.72    5090  191.72
  5092.9  192.88  5113.7  194.25  5176.8  196.53  5241.3  197.54    5305  201.96
  5354.5  207.76  5397.5  215.02  5426.1  218.44  5461.2  220.07    5497   226.6
#Mann= 5 ,-1 , 0
  4437.7     .17       0  4814.4     .15       0  4974.2     .07       0
  5014.8     .15       0  5176.8     .11       0
Bank Sta=4974.2,5014.8
XS Rating Curve= 0 ,0
Exp/Cntr=0.3,0.1

Type RM Length L Ch R = 1 ,1998    ,499,499,499
BEGIN DESCRIPTION:
WEST FORK OF WHITE OAK CREEK N 4.0
END DESCRIPTION:
XS GIS Cut Line= 4
      3818328.41     10125945.89      3817906.75     10125501.98
      3817869.61     10125484.26      3817408.22     10125448.08
#Sta/Elev= 30
  4346.6  235.89  4442.3   231.4  4555.6  221.37  4583.9  220.22  4590.8  218.06
  4647.4  211.29  4668.8  209.71  4675.7  208.01  4718.2   203.2  4795.9  197.02
  4862.3  194.13  4873.9  193.56  4902.2  192.12  4909.1  191.17  4911.4   189.8
  4921.3   189.8  4923.3  191.84  4930.5  192.16  5003.4  191.12  5051.9  193.11
  5100.9  197.35  5105.9     197  5142.2  201.07    5245  208.25  5292.7  213.22
  5322.7  215.01  5342.8  218.62  5364.2   219.2    5403  223.53  5462.8  225.46
#Mann= 5 ,-1 , 0
  4346.6     .17       0  4862.3     .15       0  4873.9     .07       0
  5051.9     .15       0    5245     .11       0
Bank Sta=4873.9,5051.9
XS Rating Curve= 0 ,0
Exp/Cntr=0.3,0.1

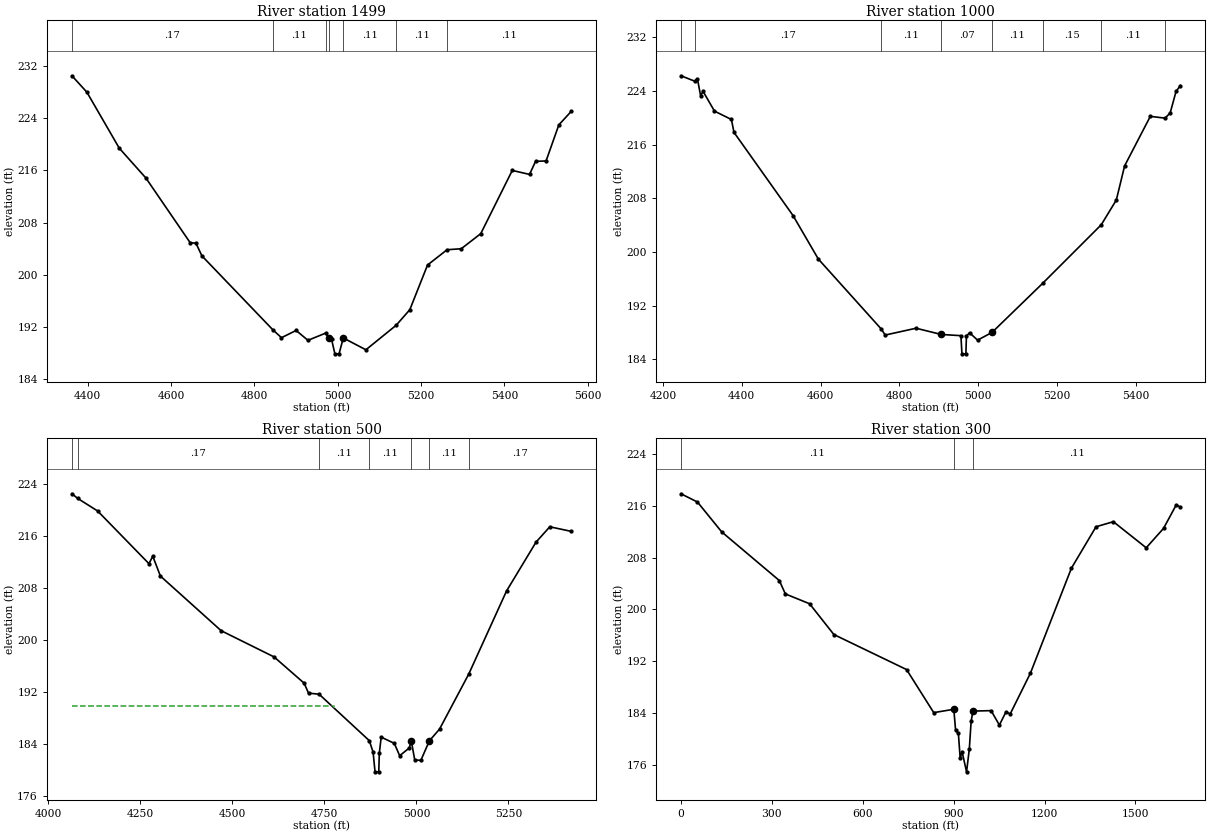
Type RM Length L Ch R = 1 ,1499    ,499,499,499
BEGIN DESCRIPTION:
WEST FORK OF WHITE OAK CREEK N 3.0
END DESCRIPTION:
XS GIS Cut Line= 3
      3818578.77     10125580.81      3818140.46     10125117.76
       3817613.4     10124926.17
#Sta/Elev= 30
  4362.4  230.48  4398.3  227.96    4476  219.39  4539.9  214.82  4645.9  204.94
    4660  204.84  4674.2  202.91    4844  191.62  4865.1  190.38  4900.3  191.49
  4928.6  189.98  4971.1  191.08  4978.4  190.34  4985.3  190.13  4993.3  187.91
  5003.3  187.91  5013.4  190.34  5067.7  188.53  5140.4  192.29    5173  194.66
  5215.6  201.51  5262.5  203.85  5296.5     204  5343.3  206.31  5418.9  215.99
  5460.3  215.38  5474.8  217.38    5500  217.44  5530.6  222.96  5560.8  225.06
#Mann= 7 ,-1 , 0
  4362.4     .17       0    4844     .11       0  4971.1     .11       0
  4978.4     .07       0  5013.4     .11       0  5140.4     .11       0
  5262.5     .11       0
Bank Sta=4978.4,5013.4
XS Rating Curve= 0 ,0
Exp/Cntr=0.3,0.1

Type RM Length L Ch R = 1 ,1000    ,500,500,500
BEGIN DESCRIPTION:
WEST FORK OF WHITE OAK CREEK N 2.0
END DESCRIPTION:
XS GIS Cut Line= 3
      3818786.96     10125291.24      3818310.38     10124706.83
       3817891.9     10124410.97
#Sta/Elev= 30
  4245.9  226.28  4280.5  225.48  4287.7  225.79  4295.6  223.33    4302  223.95
  4330.8  221.01  4373.8  219.76  4380.3  217.84    4530  205.44  4594.3  198.94
  4753.7  188.52  4763.7  187.61    4842  188.63  4905.9   187.7  4955.8  187.52
  4958.4  184.81  4968.4  184.81  4969.8  187.45  4977.7  187.96    4998  186.85
  5034.8  188.01  5162.8  195.31  5311.7  204.06  5349.9  207.75  5370.9  212.84
  5436.1  220.23  5473.7  219.96  5486.6  220.76  5501.4  223.96  5512.5  224.82
#Mann= 8 ,-1 , 0
  4245.9     .11       0  4280.5     .17       0  4753.7     .11       0
  4905.9     .07       0  5034.8     .11       0  5162.8     .15       0
  5311.7     .11       0  5473.7     .17       0
Bank Sta=4905.9,5034.8
XS Rating Curve= 0 ,0
Exp/Cntr=0.3,0.1

Type RM Length L Ch R = 1 ,500     ,200,200,200
BEGIN DESCRIPTION:
WEST FORK OF WHITE OAK CREEK N 1.0
END DESCRIPTION:
XS GIS Cut Line= 3
      3818820.12     10125233.85      3818588.18     10124326.94
      3818224.08     10124115.39
#Sta/Elev= 30
  4063.9  222.47  4079.4  221.76  4133.7  219.82  4273.2  211.71  4283.5  212.87
  4304.2  209.81  4469.3   201.4  4613.3  197.36  4694.9  193.32  4706.7  191.79
  4735.4  191.63  4871.9  184.48  4882.2  182.72  4887.5  179.68  4897.6  179.68
  4899.1  182.52  4904.2  185.02  4939.9  184.06  4954.4  182.16  4980.7  183.36
  4985.9  184.47  4995.3  181.53  5011.9  181.43  5035.1  184.45  5062.7  186.25
    5142  194.71  5244.8  207.51  5325.1  215.04  5362.4  217.39  5421.1  216.68
#Mann= 7 ,-1 , 0
  4063.9     .11       0  4079.4     .17       0  4735.4     .11       0
  4871.9     .11       0  4985.9     .07       0  5035.1     .11       0
    5142     .17       0
#XS Ineff= 2 , 0
       0  4776.6  189.75               0
Permanent Ineff=
       F       F
Bank Sta=4985.9,5035.1
XS Rating Curve= 0 ,0
Exp/Cntr=0.3,0.1

Type RM Length L Ch R = 1 ,300     ,0,0,0
XS GIS Cut Line= 3
      3818835.18     10125165.54      3818850.81     10124337.41
      3818165.04     10123884.29
#Sta/Elev= 30
       0  217.84    54.5  216.56   134.5  211.95   324.5  204.45   344.5  202.38
   424.5  200.86   504.6  196.11   744.6   190.7   834.3  184.05   900.5  184.57
   906.5   181.3   915.6  180.86   921.6  176.99   927.7  178.04   942.6  174.91
   951.7  178.42   957.7   182.7   963.7  184.29  1023.6  184.36    1051  182.13
    1072   184.1  1087.1  183.89  1153.3  190.13  1288.7  206.35    1370  212.75
  1427.2  213.53  1535.6   209.5  1592.7  212.49  1634.9  216.14  1648.6  215.77
#Mann= 3 , 0 , 0
       0     .11       0   900.5     .06       0   963.7     .11       0
Bank Sta=900.5,963.7
XS Rating Curve= 0 ,0
Exp/Cntr=0.3,0.1

Chan Stop Cuts=-1
Use User Specified Reach Order=0
Composite Channel Slope=5