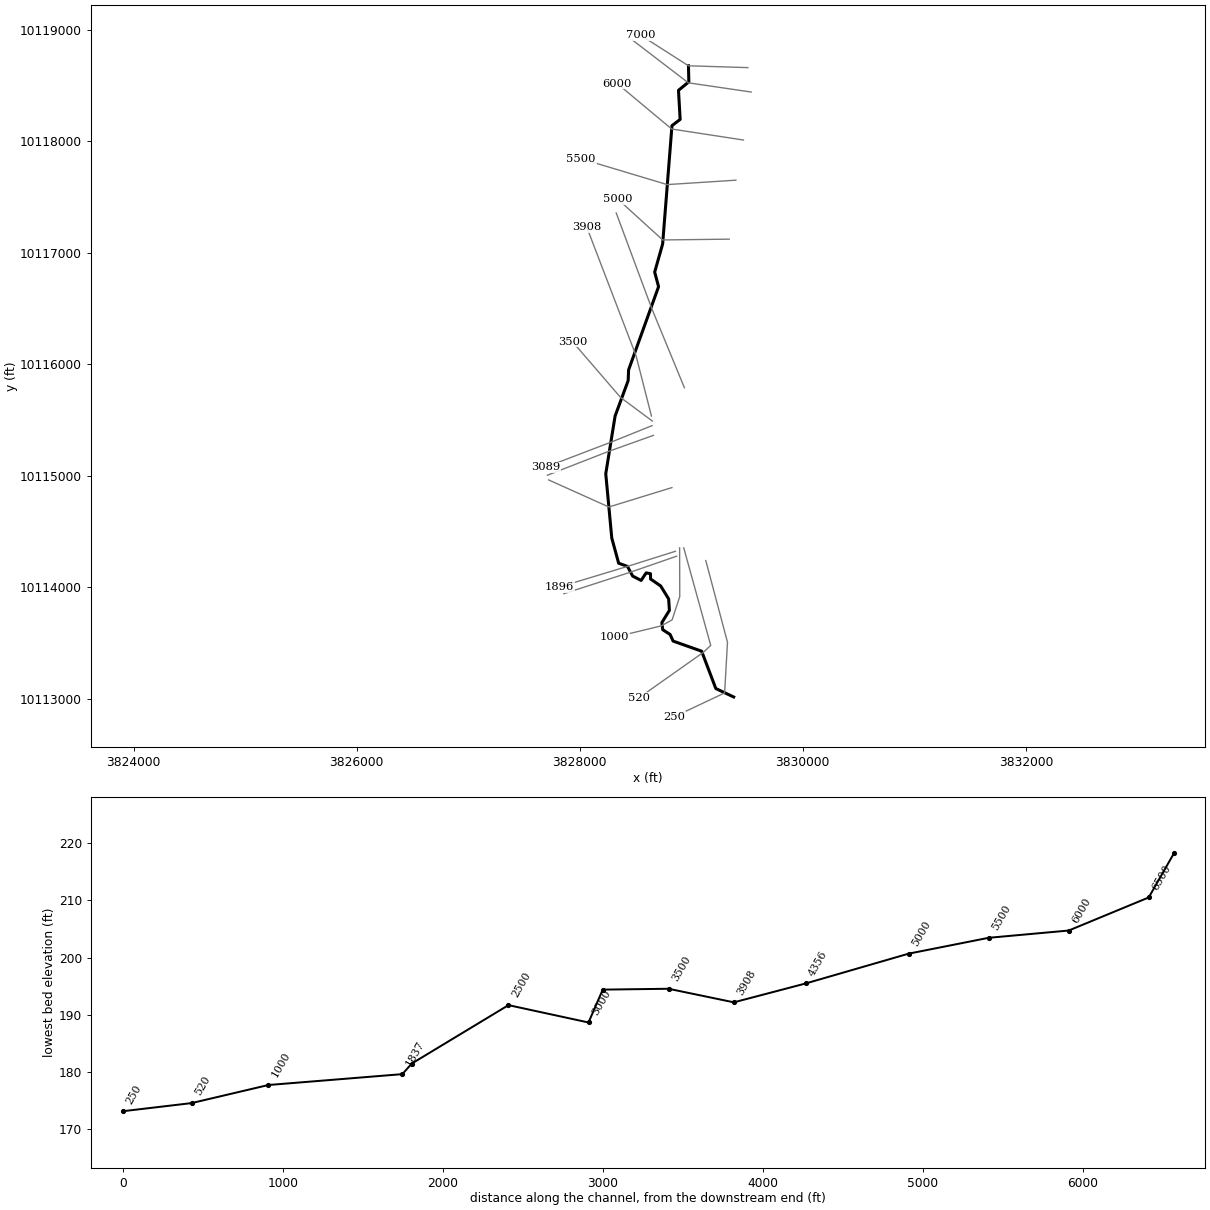
--- WEST FORK W BR ALLIGATOR CRK.prj (project) ---

Proj Title=WEST FORK W BR ALLIGATOR CRK Base Level Engineering
Current Plan=p01
Default Exp/Contr=0.3,0.1
English Units
Geom File=g01
Flow File=f01
Plan File=p01
Y Axis Title=Elevation
X Axis Title(PF)=Main Channel Distance
X Axis Title(XS)=Station
BEGIN DESCRIPTION:
WEST FORK W BR ALLIGATOR CRK
END DESCRIPTION:
DSS Export Rating Curves= 0
DSS Export Rating Curve Sorted= 0
DSS Export Volume Flow Curves= 0
DXF OffsetX= 0
DXF OffsetY= 0
DXF ScaleX= 1
DXF ScaleY= 10

--- WEST FORK W BR ALLIGATOR CRK.p01 (plan) ---

Plan Title=Multiple Run
Short Identifier=Multiple
Geom File=g01
Flow File=f01
Subcritical Flow
K Sum by GR= 0
Std Step Tol= 0.01
Critical Tol= 0.01
Num of Std Step Trials= 20
Max Error Tol= 0.3
Flow Tol Ratio= 0.001
Split Flow NTrial= 30
Split Flow Tol= 0.02
Split Flow Ratio= 0.02
Log Output Level= 0
Friction Slope Method= 1
Unsteady Friction Slope Method= 2
Unsteady Bridges Friction Slope Method= 1
Parabolic Critical Depth
Global Vel Dist=  1 , 1 , 1
Global Log Level= 0
CheckData=True
Encroach Param= -1, 0, 0, 0
BEGIN DESCRIPTION:
Multiple Run
END DESCRIPTION:

--- WEST FORK W BR ALLIGATOR CRK.f01 (steady flow) ---

Flow Title=Multiple
Program Version=4.10
Number of Profiles= 7
Profile Names=10-year,25-year,50-year,1pct_min,100-year,1pct_plu,500-year
River Rch & RM=WEST FORK W BR A,Reach-1         ,7000
     259     332     431     185     560    1691     974
River Rch & RM=WEST FORK W BR A,Reach-1         ,6500
     259     332     431     185     560    1691     974
River Rch & RM=WEST FORK W BR A,Reach-1         ,5500
     774    1067    1462     659    1990    6010    3817
Boundary for River Rch & Prof#=WEST FORK W BR A,Reach-1         , 1
Up Type= 0
Dn Type= 3
Dn Slope=0.01
Boundary for River Rch & Prof#=WEST FORK W BR A,Reach-1         , 2
Up Type= 0
Dn Type= 3
Dn Slope=0.01
Boundary for River Rch & Prof#=WEST FORK W BR A,Reach-1         , 3
Up Type= 0
Dn Type= 3
Dn Slope=0.01
Boundary for River Rch & Prof#=WEST FORK W BR A,Reach-1         , 4
Up Type= 0
Dn Type= 3
Dn Slope=0.01
Boundary for River Rch & Prof#=WEST FORK W BR A,Reach-1         , 5
Up Type= 0
Dn Type= 3
Dn Slope=0.01
Boundary for River Rch & Prof#=WEST FORK W BR A,Reach-1         , 6
Up Type= 0
Dn Type= 3
Dn Slope=0.01
Boundary for River Rch & Prof#=WEST FORK W BR A,Reach-1         , 7
Up Type= 0
Dn Type= 3
Dn Slope=0.01
DSS Import GetInterval= 0
DSS Import GetPeak= 0
DSS Import FillOption= 0

--- WEST FORK W BR ALLIGATOR CRK.g01 (geometry) ---

Geom Title=Existing Conditions
Program Version=4.10

River Reach=WEST FORK W BR A,Reach-1
Reach XY= 30
      3828974.87     10118677.03       3828978.3     10118532.77
      3828885.59     10118456.99      3828900.26     10118195.96
      3828826.97     10118139.79      3828743.36     10117078.98
      3828671.96     10116826.69      3828706.89     10116696.03
      3828438.17      10115950.4      3828434.27     10115854.04
      3828317.08     10115536.33      3828233.33     10115018.57
      3828287.32     10114442.19      3828348.96     10114216.49
      3828427.95     10114187.84      3828474.82     10114101.04
      3828550.34     10114061.98      3828595.48     10114129.69
      3828634.55     10114122.74      3828635.01     10114074.99
      3828725.69      10114012.5      3828797.22     10113896.35
      3828803.99     10113793.75      3828736.28     10113683.85
      3828744.09     10113620.31      3828810.24      10113577.6
      3828837.32     10113518.23      3829093.05      10113427.6
      3829220.14     10113092.71      3829380.36     10113016.99

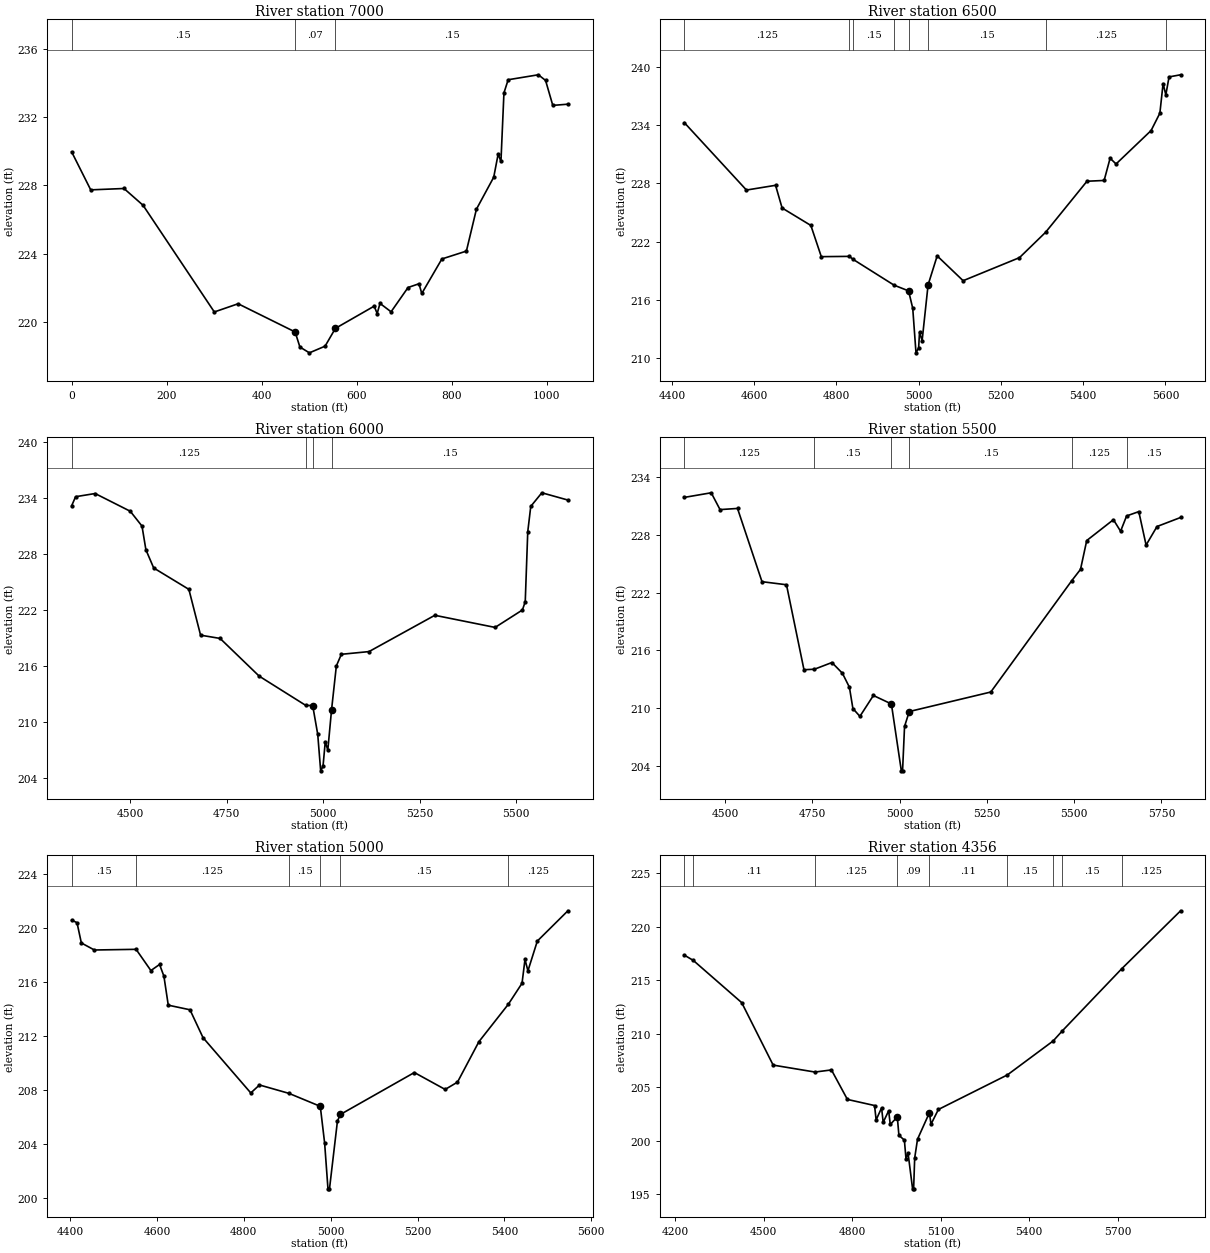
Type RM Length L Ch R = 1 ,7000    ,157,157,157
XS GIS Cut Line= 3
      3829507.94     10118660.25      3828974.89      10118676.8
      3828544.42     10118952.17
#Sta/Elev= 30
       0  229.96    40.1  227.74   110.1  227.82   150.2  226.84   300.2   220.6
   350.3  221.08   470.3  219.43   480.3  218.55   500.3  218.21   533.3   218.6
     555  219.64   636.6  220.94   642.9  220.51   648.9   221.1   672.2  220.61
   707.9  222.03   730.9  222.25   736.8  221.68   779.1   223.7   830.7  224.16
   851.8  226.61   888.2  228.48   897.5  229.83   903.4   229.4   909.7  233.41
   918.6  234.18   982.1  234.47   997.3  234.14  1012.5  232.68  1044.3  232.75
#Mann= 3 , 0 , 0
       0     .15       0   470.3     .07       0     555     .15       0
Bank Sta=470.3,555
XS Rating Curve= 0 ,0
Exp/Cntr=0.3,0.1

Type RM Length L Ch R = 1 ,6500    ,500,500,500
BEGIN DESCRIPTION:
WEST FORK W BR ALLIGATOR CRK 13.0
END DESCRIPTION:
XS GIS Cut Line= 3
      3829537.18     10118441.51       3828973.7     10118524.09
      3828467.85     10118911.07
#Sta/Elev= 30
  4430.5  234.26  4581.4  227.31  4652.2   227.8  4668.1  225.46    4738  223.66
  4763.4  220.44  4831.9  220.47    4840  220.18  4940.3   217.5  4975.6  216.91
  4985.7  215.11  4993.6  210.52    5000  211.02  5002.2  212.63  5008.5  211.78
    5023  217.53  5045.1  220.52  5108.2  217.96  5245.2  220.34  5308.6  222.95
  5409.3  228.22    5451   228.3  5465.5  230.59    5480     230  5565.2  233.45
  5586.5  235.24  5594.3  238.29    5601  237.13  5608.8  238.98  5636.9   239.2
#Mann= 8 ,-1 , 0
  4430.5    .125       0  4831.9     .11       0    4840     .15       0
  4940.3    .125       0  4975.6     .09       0    5023     .15       0
  5308.6    .125       0    5601     .15       0
Bank Sta=4975.6,5023
XS Rating Curve= 0 ,0
Exp/Cntr=0.3,0.1

Type RM Length L Ch R = 1 ,6000    ,500,500,500
BEGIN DESCRIPTION:
WEST FORK W BR ALLIGATOR CRK 12.0
END DESCRIPTION:
XS GIS Cut Line= 3
       3829467.9     10118011.06      3828824.33     10118109.82
      3828337.47     10118516.39
#Sta/Elev= 30
  4348.9  233.15  4359.1  234.12  4409.7  234.46  4500.7  232.56  4531.1  230.97
  4541.2  228.43  4561.4  226.48  4652.5  224.19  4682.8  219.28  4733.4  218.93
  4834.6  214.89  4955.4  211.75  4973.2  211.74  4986.3  208.65  4993.9  204.74
    5000  205.24  5005.8  207.86  5012.4  206.96 5022.13   211.3  5034.5  215.98
  5047.5  217.23  5119.1  217.52  5289.6  221.41  5445.7  220.11  5516.5  221.98
  5523.8  222.87  5530.3  230.36  5538.1  233.08  5566.8  234.54  5634.3  233.76
#Mann= 4 ,-1 , 0
  4348.9    .125       0  4955.4     .15       0  4973.2     .09       0
 5022.13     .15       0
Bank Sta=4973.2,5022.13
XS Rating Curve= 0 ,0
Exp/Cntr=0.3,0.1

Type RM Length L Ch R = 1 ,5500    ,500,500,500
BEGIN DESCRIPTION:
WEST FORK W BR ALLIGATOR CRK 11.0
END DESCRIPTION:
XS GIS Cut Line= 3
      3829399.81     10117650.98      3828783.98     10117611.46
      3828013.14     10117842.78
#Sta/Elev= 30
  4382.9  231.92  4459.8   232.4  4485.1  230.65  4535.2  230.77  4605.3  223.15
  4675.5  222.83  4725.6  213.99  4755.5  214.04  4805.7  214.74  4835.8  213.62
  4855.8  212.17  4865.8  209.95  4885.9  209.14  4924.5  211.31  4976.1  210.43
  5004.6  203.47  5008.1  203.47  5013.8  208.09  5027.3  209.64  5260.9  211.67
  5492.8  223.25    5518  224.43  5535.8  227.43  5612.3   229.6  5632.8   228.4
  5650.1  229.99    5685  230.44  5705.9  226.96  5737.2  228.89  5804.8  229.83
#Mann= 6 ,-1 , 0
  4382.9    .125       0  4755.5     .15       0  4976.1     .09       0
  5027.3     .15       0  5492.8    .125       0  5650.1     .15       0
Bank Sta=4976.1,5027.3
XS Rating Curve= 0 ,0
Exp/Cntr=0.3,0.1

Type RM Length L Ch R = 1 ,5000    ,644,644,644
BEGIN DESCRIPTION:
WEST FORK W BR ALLIGATOR CRK 10.0
END DESCRIPTION:
XS GIS Cut Line= 3
      3829340.19     10117122.24      3828743.83     10117115.16
      3828339.74     10117482.49
#Sta/Elev= 30
  4403.6  220.57  4415.9  220.38  4425.9  218.88  4455.9  218.36  4551.9  218.41
    4586  216.84    4606  217.29    4616  216.42    4626  214.28    4676  213.94
    4706  211.88    4816  207.79    4836  208.38  4903.8  207.76    4976   206.8
    4986  204.09  4993.7   200.7  4997.2   200.7  5015.5  205.71  5022.3   206.2
  5192.6   209.3  5263.5  208.05  5291.9  208.59  5341.2  211.58    5409  214.35
  5440.5   215.9  5447.3  217.66  5454.1  216.82  5475.7  219.02  5546.1  221.26
#Mann= 6 ,-1 , 0
  4403.6     .15       0  4551.9    .125       0  4903.8     .15       0
    4976     .09       0  5022.3     .15       0    5409    .125       0
Bank Sta=4976,5022.3
XS Rating Curve= 0 ,0
Exp/Cntr=0.3,0.1

Type RM Length L Ch R = 1 ,4356    ,448,448,448
BEGIN DESCRIPTION:
WEST FORK W BR ALLIGATOR CRK 9.0
END DESCRIPTION:
XS GIS Cut Line= 3
      3828938.43     10115790.04      3828644.82     10116502.73
      3828327.14     10117357.08
#Sta/Elev= 30
    4231  217.34  4261.2  216.85  4425.4   212.9    4532  207.06  4673.8  206.41
  4729.6  206.61  4783.7  203.85  4875.7  203.28  4881.1  201.94  4899.6  203.06
    4905  201.71  4923.6  202.79    4929  201.51  4952.9  202.21  4958.3   200.5
  4976.9  200.04  4982.3   198.3  4989.2  198.85  5004.7  195.49  5008.2  195.49
  5011.8  198.37  5021.4  200.13  5061.8  202.61  5067.1  201.53  5092.1  202.91
  5325.9  206.14  5481.3  209.32  5511.6  210.24    5713  216.05  5913.3  221.49
#Mann= 9 ,-1 , 0
    4231     .15       0  4261.2     .11       0  4673.8    .125       0
  4952.9     .09       0  5061.8     .11       0  5325.9     .15       0
  5481.3    .125       0  5511.6     .15       0    5713    .125       0
Bank Sta=4952.9,5061.8
XS Rating Curve= 0 ,0
Exp/Cntr=0.3,0.1

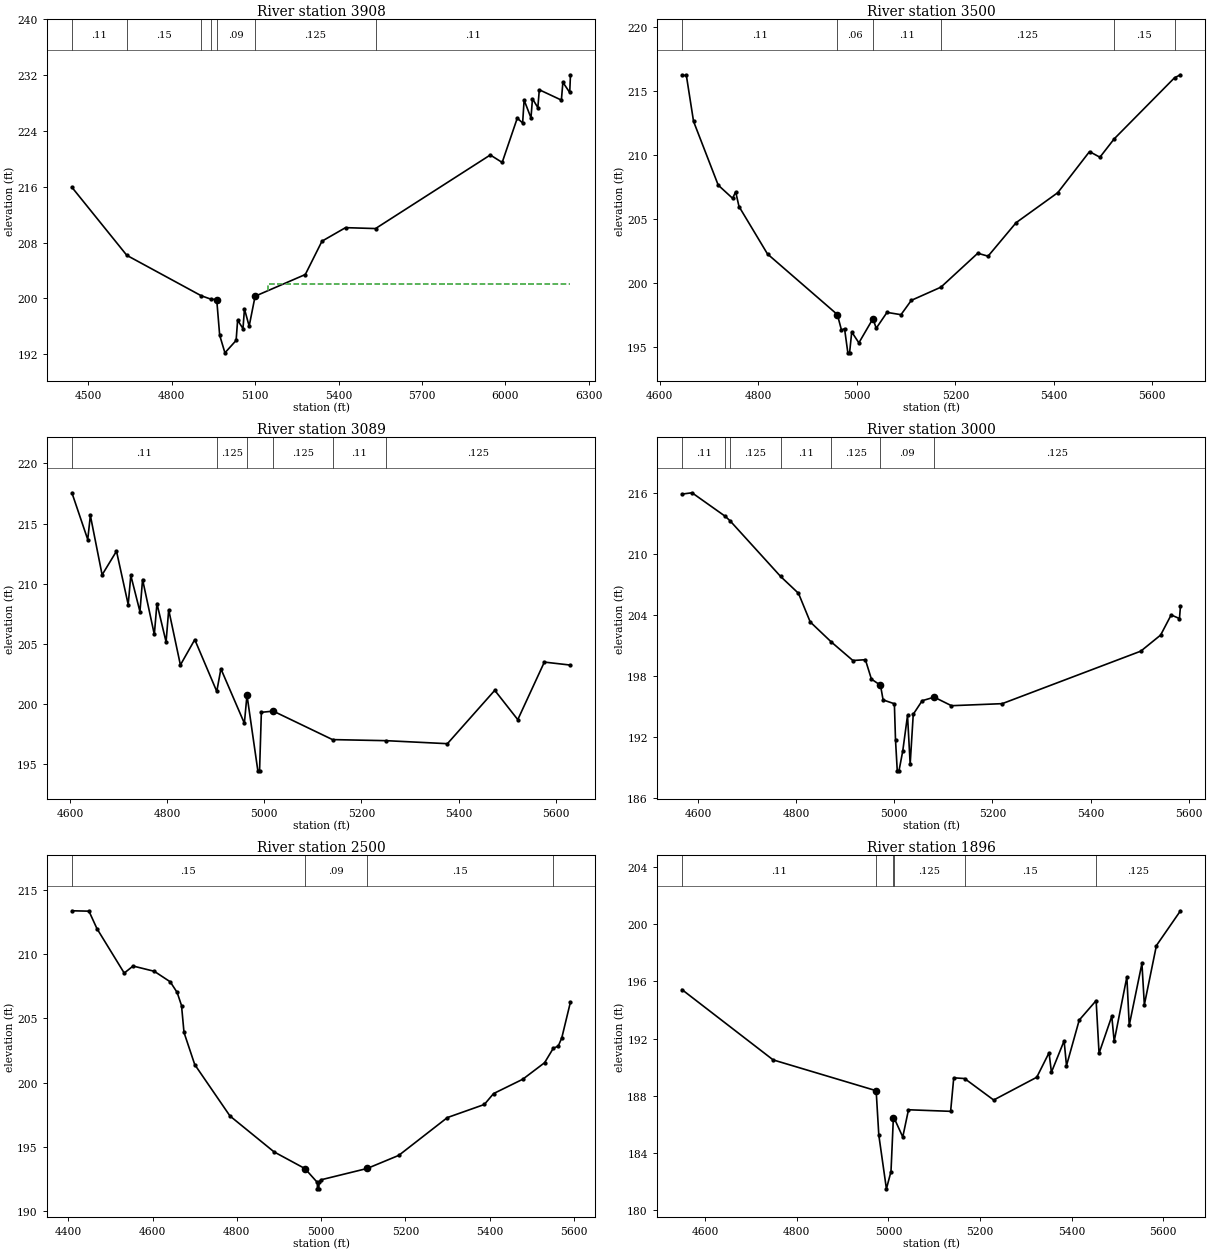
Type RM Length L Ch R = 1 ,3908    ,408,408,408
BEGIN DESCRIPTION:
WEST FORK W BR ALLIGATOR CRK 8.0
END DESCRIPTION:
XS GIS Cut Line= 3
      3828642.97     10115535.99      3828504.58       10116078.
      3828062.63     10117230.47
#Sta/Elev= 30
  4440.6  215.94  4638.2  206.18  4905.7  200.39  4939.6  199.91  4961.6  199.83
  4972.2  194.73  4991.1   192.2  5031.4  193.98  5036.8  196.88  5056.1  195.68
  5061.4  198.49  5078.3  196.03  5099.7  200.32  5280.3  203.43  5340.3  208.21
    5425  210.15    5533  210.02  5945.8  220.57  5988.6   219.5  6042.9  225.85
  6062.2  225.16  6067.5  228.44  6092.2  225.89  6097.6  228.63  6116.9  227.36
  6122.2  229.92  6201.6  228.44    6207  230.99  6231.6  229.53  6234.3  232.07
#Mann= 7 ,-1 , 0
  4440.6     .11       0  4638.2     .15       0  4905.7     .11       0
  4939.6    .125       0  4961.6     .09       0  5099.7    .125       0
    5533     .11       0
#XS Ineff= 2 , 0
       0                  5146.2       0  202.08
Permanent Ineff=
       F       F
Bank Sta=4961.6,5099.7
XS Rating Curve= 0 ,0
Exp/Cntr=0.3,0.1

Type RM Length L Ch R = 1 ,3500    ,411,411,411
BEGIN DESCRIPTION:
WEST FORK W BR ALLIGATOR CRK 7.0
END DESCRIPTION:
XS GIS Cut Line= 3
      3828650.84     10115491.28      3828365.83     10115703.09
      3827936.82     10116200.96
#Sta/Elev= 30
  4644.9  216.24  4653.9  216.24  4668.5  212.65  4718.6  207.67  4747.8  206.64
    4754  207.15  4760.8     206  4818.7  202.29  4960.5  197.56  4968.9  196.34
  4975.1  196.46  4981.8  194.57  4985.3  194.57  4989.7   196.2  5004.2  195.35
  5032.8  197.24  5039.4  196.49  5061.3  197.73  5089.7  197.55  5110.7  198.67
  5170.8   199.7  5245.6  202.35  5266.5  202.12  5323.5  204.74    5408  207.08
  5472.5  210.29  5493.6  209.85  5522.5  211.28  5645.2  216.06  5657.2  216.29
#Mann= 6 ,-1 , 0
  4644.9     .11       0  4960.5     .06       0  5032.8     .11       0
  5170.8    .125       0  5522.5     .15       0  5645.2    .125       0
Bank Sta=4960.5,5032.8
XS Rating Curve= 0 ,0
Exp/Cntr=0.3,0.1

Type RM Length L Ch R = 1 ,3089    ,89,89,89
BEGIN DESCRIPTION:
WEST FORK W BR ALLIGATOR CRK 6.5
END DESCRIPTION:
XS GIS Cut Line= 3
      3828648.63     10115450.04      3828280.94      10115302.2
      3827692.23     10115077.02
#Sta/Elev= 30
  4603.7  217.56  4636.3  213.67  4641.7  215.67  4665.9  210.73  4695.5   212.7
  4719.6  208.26    4725  210.68  4743.8  207.67  4749.2  210.34  4773.4  205.77
  4778.8  208.34  4797.6  205.15    4803  207.82  4827.1  203.23  4856.7  205.34
    4902  201.03  4910.5  202.91  4958.8  198.38  4964.2  200.72  4986.6  194.42
  4990.1  194.42  4993.8  199.29  5018.3  199.39  5140.3  197.02  5251.3  196.93
  5376.9  196.68  5474.4  201.12  5521.8  198.68  5576.5  203.47  5630.3  203.22
#Mann= 6 ,-1 , 0
  4603.7     .11       0    4902    .125       0  4964.2     .09       0
  5018.3    .125       0  5140.3     .11       0  5251.3    .125       0
Bank Sta=4964.2,5018.3
XS Rating Curve= 0 ,0
Exp/Cntr=0.3,0.1

Type RM Length L Ch R = 1 ,3000    ,500,500,500
BEGIN DESCRIPTION:
WEST FORK W BR ALLIGATOR CRK 6.0
END DESCRIPTION:
XS GIS Cut Line= 3
      3828661.66     10115363.24      3828253.75     10115217.41
      3827710.15     10115005.63
#Sta/Elev= 30
  4566.8  215.87  4587.4     216  4655.1  213.69  4664.7  213.26    4768  207.78
  4804.5  206.12  4828.4  203.31  4871.4  201.34  4915.4  199.52  4940.9   199.6
  4953.2  197.69  4971.7  197.09    4977  195.65    5000  195.27  5002.3  191.72
  5005.9  188.68  5009.4  188.68  5017.1  190.63  5026.8  194.12  5032.2  189.34
  5038.5  194.24  5056.7  195.57  5081.2  195.92  5116.4  195.08  5219.8  195.28
  5502.5  200.44  5542.9  202.02  5564.4     204  5581.3  203.64  5583.4  204.89
#Mann= 7 ,-1 , 0
  4566.8     .11       0  4655.1     .15       0  4664.7    .125       0
    4768     .11       0  4871.4    .125       0  4971.7     .09       0
  5081.2    .125       0
Bank Sta=4971.7,5081.2
XS Rating Curve= 0 ,0
Exp/Cntr=0.3,0.1

Type RM Length L Ch R = 1 ,2500    ,604,604,604
BEGIN DESCRIPTION:
WEST FORK W BR ALLIGATOR CRK 5.0
END DESCRIPTION:
XS GIS Cut Line= 3
      3828826.59     10114894.49      3828261.25     10114720.55
       3827721.3     10114963.29
#Sta/Elev= 30
  4408.5   213.4    4449  213.37  4467.9  212.01  4532.7  208.54  4553.7  209.09
    4604  208.68  4641.9  207.86  4658.3  207.03  4668.7  206.01  4674.6  203.91
  4700.1   201.4  4783.8  197.39  4888.5  194.59  4961.7  193.29  4991.1  192.21
  4991.3  191.71  4994.8  191.71  4995.1  192.21  4999.2  192.41  5109.5   193.3
  5184.4  194.32  5299.8  197.27  5387.5  198.29  5409.4  199.14  5478.8  200.26
  5530.6  201.55  5551.3  202.68  5562.9  202.84  5571.4  203.49    5592  206.29
#Mann= 4 ,-1 , 0
  4408.5     .15       0  4961.7     .09       0  5109.5     .15       0
  5551.3    .125       0
Bank Sta=4961.7,5109.5
XS Rating Curve= 0 ,0
Exp/Cntr=0.3,0.1

Type RM Length L Ch R = 1 ,1896    ,59,59,59
BEGIN DESCRIPTION:
WEST FORK W BR ALLIGATOR CRK 3.0
END DESCRIPTION:
XS GIS Cut Line= 3
      3828857.86     10114323.47      3828427.95     10114187.84
      3827817.48     10114003.15
#Sta/Elev= 30
  4549.2  195.42  4748.4  190.51  4973.3  188.36  4979.1  185.26  4995.7  181.51
  5005.7  182.72  5010.9  186.47  5012.6  186.45  5031.4  185.13  5043.9  187.03
  5135.9  186.92  5142.7  189.26  5166.4  189.21  5229.9  187.71    5324   189.3
  5350.8  191.01    5356  189.65  5383.7  191.84  5388.9  190.11  5416.7  193.29
  5453.6  194.65    5460  190.97  5487.8  193.56    5493  191.81  5520.7   196.3
  5525.9  192.93  5553.6  197.24  5558.9  194.36  5585.2  198.49  5637.8  200.92
#Mann= 6 ,-1 , 0
  4549.2     .11       0  4973.3     .07       0  5010.9     .11       0
  5012.6    .125       0  5166.4     .15       0  5453.6    .125       0
Bank Sta=4973.3,5010.9
XS Rating Curve= 0 ,0
Exp/Cntr=0.3,0.1

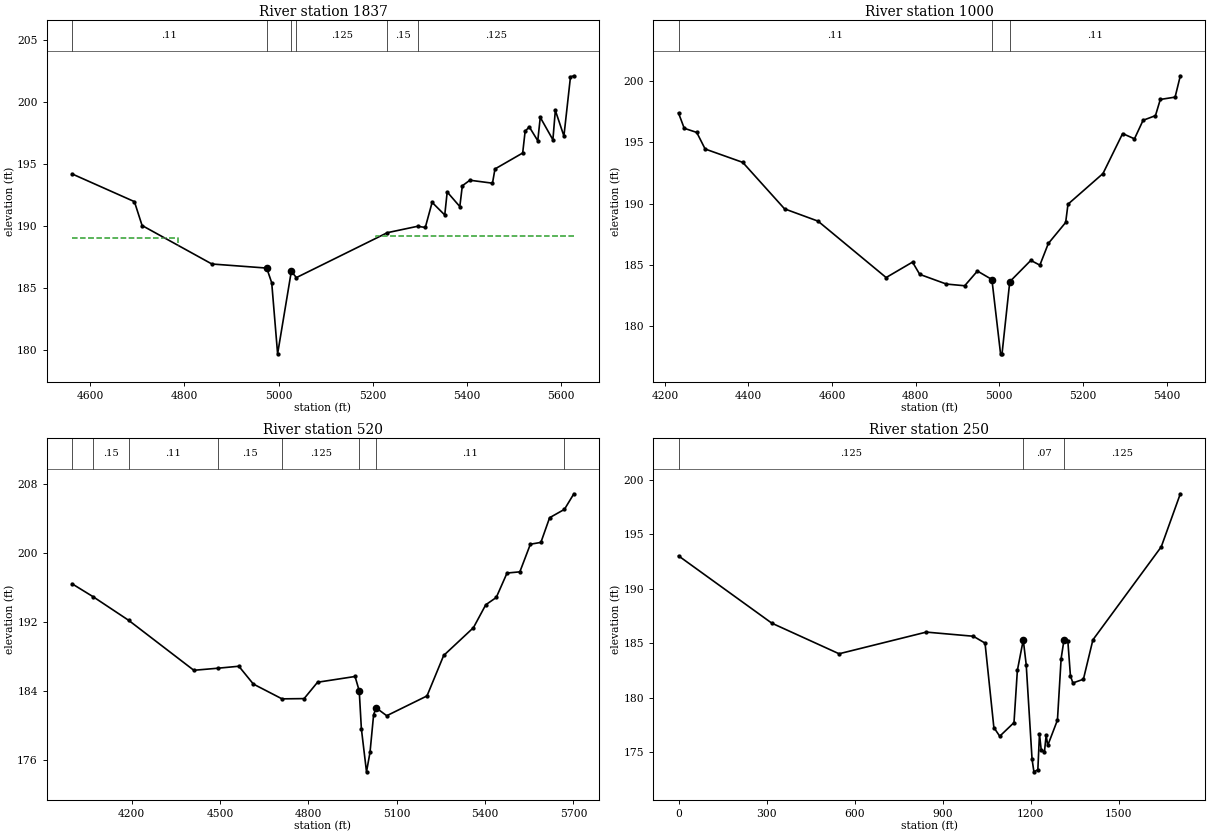
Type RM Length L Ch R = 1 ,1837    ,837,837,837
BEGIN DESCRIPTION:
WEST FORK W BR ALLIGATOR CRK 2.0
END DESCRIPTION:
XS GIS Cut Line= 3
      3828868.26      10114279.2      3828453.99     10114135.76
       3827857.8     10113943.25
#Sta/Elev= 30
  4561.6   194.2  4693.9  191.96  4710.2  190.03  4858.3  186.92  4974.7  186.59
  4985.3   185.4  4997.8  179.66  5026.9  186.33  5037.6  185.82  5230.6  189.45
  5295.2  189.97  5311.2  189.87  5325.7   191.9  5352.5  190.88  5357.7  192.74
  5384.5  191.56  5389.8  193.24  5405.8  193.69  5453.8  193.45  5459.1   194.6
  5517.9  195.89  5523.1  197.65  5531.9     198  5549.9  196.88  5555.2  198.77
    5582  196.96  5587.2  199.33  5605.4  197.26  5619.3  202.04  5626.5  202.13
#Mann= 6 ,-1 , 0
  4561.6     .11       0  4974.7     .07       0  5026.9     .11       0
  5037.6    .125       0  5230.6     .15       0  5295.2    .125       0
#XS Ineff= 2 , 0
       0  4787.3  188.99  5206.1       0   189.2
Permanent Ineff=
       F       F
Bank Sta=4974.7,5026.9
XS Rating Curve= 0 ,0
Exp/Cntr=0.3,0.1

Type RM Length L Ch R = 1 ,1000    ,480,480,480
BEGIN DESCRIPTION:
WEST FORK W BR ALLIGATOR CRK 2.5
END DESCRIPTION:
XS GIS Cut Line= 5
      3828895.58     10114354.71      3828896.78     10113917.76
      3828828.35     10113708.56      3828732.12     10113654.79
      3828311.25     10113553.01
#Sta/Elev= 30
  4232.7  197.39  4246.3  196.15  4276.3  195.81  4296.3  194.46  4386.3  193.37
  4486.3  189.58  4566.3  188.58  4729.3  183.98  4792.4  185.24  4809.6  184.24
  4873.3  183.45  4917.2  183.31  4947.6  184.51  4982.3  183.82    5003  177.76
  5006.5  177.76    5025  183.64  5075.4  185.38    5097  184.99  5117.3  186.76
  5158.7  188.47  5164.3  189.96    5248  192.46    5295  195.72  5323.3  195.29
  5343.9   196.8  5373.5  197.18  5385.1   198.5  5420.5  198.69    5433  200.43
#Mann= 3 , 0 , 0
  4232.7     .11       0  4982.3     .06       0    5025     .11       0
#XS Ineff= 2 , 0
       0                  5075.4       0  185.38
Permanent Ineff=
       F       F
Bank Sta=4982.3,5025
XS Rating Curve= 0 ,0
Exp/Cntr=0.3,0.1

Type RM Length L Ch R = 1 ,520     ,430,430,430
BEGIN DESCRIPTION:
WEST FORK W BR ALLIGATOR CRK 1.0
END DESCRIPTION:
XS GIS Cut Line= 4
      3828932.61     10114354.13      3829174.56     10113479.39
      3829105.55      10113415.1      3828532.49     10113010.85
#Sta/Elev= 30
  3998.1  196.45    4069  194.96    4190  192.21  4411.4   186.4  4492.9  186.64
  4564.2  186.87  4613.4   184.8  4710.7  183.08  4785.7  183.11  4831.3  185.01
  4958.6  185.68  4972.8  184.01  4980.1   179.6  4997.5   174.6  5009.4  176.87
  5021.7  181.26  5030.4  182.03  5066.1  181.12  5202.8  183.42  5259.4  188.12
  5360.4  191.35  5402.2  194.01  5437.9  194.86  5474.5   197.7    5518  197.84
  5553.7  201.05  5589.4  201.26    5619  204.13  5669.3   205.1  5701.3  206.91
#Mann= 8 ,-1 , 0
  3998.1     .11       0    4069     .15       0    4190     .11       0
  4492.9     .15       0  4710.7    .125       0  4972.8     .09       0
  5030.4     .11       0  5669.3    .125       0
Bank Sta=4972.8,5030.4
XS Rating Curve= 0 ,0
Exp/Cntr=0.3,0.1

Type RM Length L Ch R = 1 ,250     ,0,0,0
XS GIS Cut Line= 4
      3829130.39      10114240.1      3829324.84     10113507.46
      3829299.14     10113053.41      3828849.14     10112840.79
#Sta/Elev= 30
       0  193.01     318  186.83   547.3  184.02   844.5  186.01  1004.8  185.63
  1044.8     185  1074.9  177.25  1094.9  176.45  1143.5   177.7    1155  182.49
  1175.1  185.29  1185.1  183.03  1205.1  174.34  1211.4  173.18  1224.8  173.37
  1230.4  176.64  1236.3  175.19  1247.4  175.03  1253.1  176.53  1258.7  175.61
  1291.6  177.93  1304.2  183.58  1313.7  185.25    1327  185.21  1335.9     182
  1344.2  181.34  1380.1  181.68  1412.5   185.3  1645.5  193.84  1710.5  198.71
#Mann= 3 , 0 , 0
       0    .125       0  1175.1     .07       0  1313.7    .125       0
Bank Sta=1175.1,1313.7
XS Rating Curve= 0 ,0
Exp/Cntr=0.3,0.1

Chan Stop Cuts=-1
Use User Specified Reach Order=0
Composite Channel Slope=5