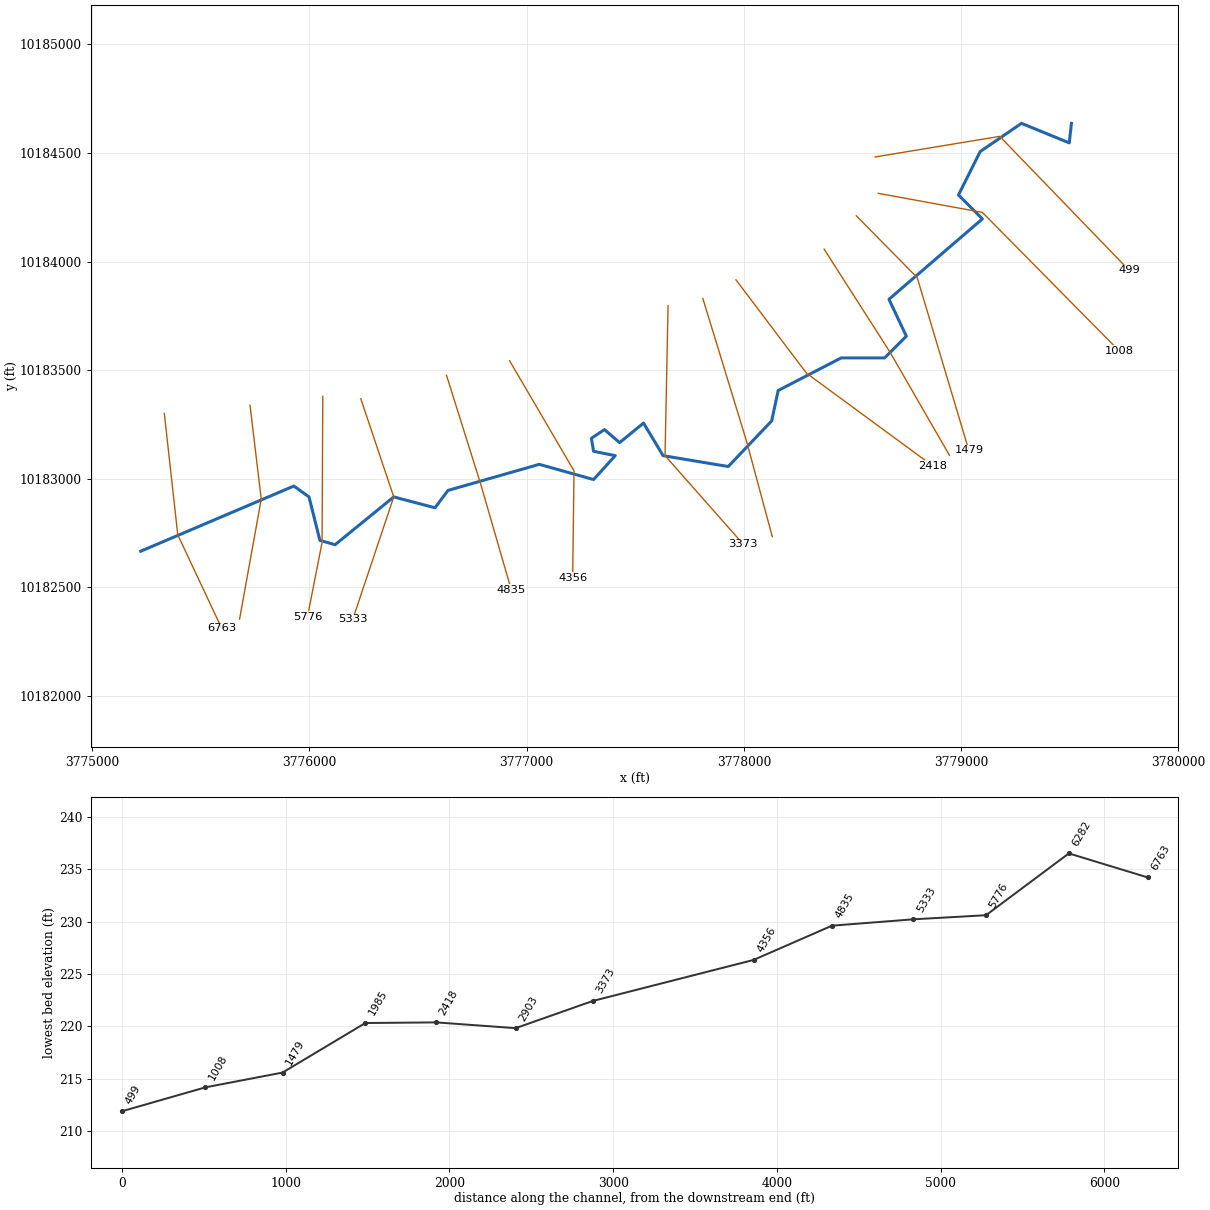
--- WF OF SAN JAC RIVER TRIB NO 1.prj (project) ---

Proj Title=WF OF SAN JAC RIVER TRIB NO 1 Base Level Engineering
Current Plan=p01
Default Exp/Contr=0.3,0.1
English Units
Geom File=g01
Flow File=f01
Plan File=p01
Y Axis Title=Elevation
X Axis Title(PF)=Main Channel Distance
X Axis Title(XS)=Station
BEGIN DESCRIPTION:
WF OF SAN JAC RIVER TRIB NO 1
END DESCRIPTION:
DSS File=dss
DSS Export Rating Curves= 0
DSS Export Rating Curve Sorted= 0
DSS Export Volume Flow Curves= 0
DXF OffsetX= 0
DXF OffsetY= 0
DXF ScaleX= 1
DXF ScaleY= 10

--- WF OF SAN JAC RIVER TRIB NO 1.p01 (plan) ---

Plan Title=Multiple Run
Program Version=4.10
Short Identifier=Multiple Run
Geom File=g01
Flow File=f01
Subcritical Flow
K Sum by GR= 0
Std Step Tol= 0.01
Critical Tol= 0.01
Num of Std Step Trials= 20
Max Error Tol= 0.3
Flow Tol Ratio= 0.001
Split Flow NTrial= 30
Split Flow Tol= 0.02
Split Flow Ratio= 0.02
Log Output Level= 0
Friction Slope Method= 1
Unsteady Friction Slope Method= 2
Unsteady Bridges Friction Slope Method= 1
Parabolic Critical Depth
Global Vel Dist= 1 , 1 , 1
Global Log Level= 0
CheckData=True
Encroach Param=-1 ,0,0, 0
BEGIN DESCRIPTION:
Multiple Run
END DESCRIPTION:
Computation Interval=1HOUR
Output Interval=1HOUR
Run HTab= 0
Run UNet= 0
Run PostProcess= 0
Run WQNet= 0
UNET Theta= 1
UNET Theta Warmup= 1
UNET ZTol= 0.02
UNET ZSATol= 0.05
UNET MxIter= 20
UNET MaxInSteps= 0
UNET DtIC= 0
UNET DtMin= 0
UNET MaxCRTS= 20
UNET WFStab= 2
UNET SFStab= 1
UNET WFX= 1
UNET SFX= 1
UNET DSS MLevel= 4
UNET DZMax Abort= 100
UNET Convert EG Bridges= 0
UNET Use Existing IB Tables=-1
UNET Froude Reduction=False
UNET Froude Limit= 1
UNET Froude Power= 10
UNET Time Slicing=0,0, 5
UNET Junction Losses=0
Instantaneous Interval=1HOUR
DSS File=dss
Write IC File= 0
Write IC File at Sim End=0
Echo Input=False
Echo Parameters=False
Echo Output=False
Write Detailed= 0
WQ AD Non Conservative
WQ ULTIMATE=-1
WQ Max Comp Step=1HOUR
WQ Output Interval=15MIN
WQ Output Selected Increments= 0
WQ Output face flow=0
WQ Output face velocity=0
WQ Output face area=0
WQ Output face dispersion=0
WQ Output cell volume=0
WQ Output cell surface area=0
WQ Output cell continuity=0
WQ Output cumulative cell continuity=0
WQ Output face conc=0
WQ Output face dconc_dx=0
WQ Output face courant=0
WQ Output face peclet=0
WQ Output face adv mass=0
WQ Output face disp mass=0
WQ Output cell mass=0
WQ Output cell source sink temp=0
WQ Output cell source sink nsm=0
WQ Output MaxMinRange=-1
WQ Daily Max Min Mean=-1
WQ Daily Range=0
WQ Daily Time=0
WQ Create Restart=0
WQ Fixed Restart=0
WQ System Summary=0
WQ Use Fixed Temperature=0
Sorting and Armoring Iterations= 10
XS Update Threshold= 0.02
Hydraulics Update Threshold= 0.02
Energy Slope Method= 1
Volume Change Method= 0
XS Weighting Method= 0
Number of US Weighted Cross Sections= 1
Number of DS Weighted Cross Sections= 1
Upstream XS Weight=0.25
Main XS Weight=0.5
Downstream XS Weight=0.25
Number of DS XS's Weighted with US Boundary= 1
Upstream Boundary Weight= 1
Weight of XSs Associated with US Boundary= 0
Number of US XS's Weighted with DS Boundary= 1
Downstream Boundary Weight= 0.5
Weight of XSs Associated with DS Boundary= 0.5
Sediment Output Level= 4
Mass or Volume Output= 0
Output Increment Type= 1
Profile and TS Output Increment= 10
XS Output Flag= 0
XS Output Increment= 10
Disregard all LS=0
Disregard all Conn=0
Disregard all Breaches=0
Disregard all Pumps=0

--- WF OF SAN JAC RIVER TRIB NO 1.f01 (steady flow) ---

Flow Title=Multiple
Program Version=4.10
Number of Profiles= 7
Profile Names=10-year,25-year,50-year,1pct_min,100-year,1pct_plu,500-year
River Rch & RM=WF OF SAN JAC RI,Reach-1         ,6763
     512     689     927     411    1242    3751    2300
River Rch & RM=WF OF SAN JAC RI,Reach-1         ,6282
     641     859    1153     508    1535    4636    2817
River Rch & RM=WF OF SAN JAC RI,Reach-1         ,1985
     731     991    1340     596    1799    5433    3351
Boundary for River Rch & Prof#=WF OF SAN JAC RI,Reach-1         , 1
Up Type= 0
Dn Type= 3
Dn Slope=0.01
Boundary for River Rch & Prof#=WF OF SAN JAC RI,Reach-1         , 2
Up Type= 0
Dn Type= 3
Dn Slope=0.01
Boundary for River Rch & Prof#=WF OF SAN JAC RI,Reach-1         , 3
Up Type= 0
Dn Type= 3
Dn Slope=0.01
Boundary for River Rch & Prof#=WF OF SAN JAC RI,Reach-1         , 4
Up Type= 0
Dn Type= 3
Dn Slope=0.01
Boundary for River Rch & Prof#=WF OF SAN JAC RI,Reach-1         , 5
Up Type= 0
Dn Type= 3
Dn Slope=0.01
Boundary for River Rch & Prof#=WF OF SAN JAC RI,Reach-1         , 6
Up Type= 0
Dn Type= 3
Dn Slope=0.01
Boundary for River Rch & Prof#=WF OF SAN JAC RI,Reach-1         , 7
Up Type= 0
Dn Type= 3
Dn Slope=0.01
DSS Import GetInterval= 0
DSS Import GetPeak= 0
DSS Import FillOption= 0

--- WF OF SAN JAC RIVER TRIB NO 1.g01 (geometry) ---

Geom Title=Existing Conditions
Program Version=4.10

River Reach=WF OF SAN JAC RI,Reach-1
Reach XY= 30
      3775223.23     10182666.84      3775928.23     10182966.84
      3775998.23     10182916.84      3776048.23     10182716.84
      3776118.23     10182696.84      3776388.23     10182916.84
      3776578.23     10182866.84      3776638.23     10182946.84
      3777058.23     10183066.84      3777308.23     10182996.84
      3777408.23     10183106.84      3777308.23     10183126.84
      3777298.23     10183186.84      3777358.23     10183226.84
      3777428.23     10183166.84      3777538.23     10183256.84
      3777628.23     10183106.84      3777928.23     10183056.84
      3778128.23     10183266.84      3778158.23     10183406.84
      3778448.23     10183556.84      3778648.23     10183556.84
      3778748.23     10183656.84      3778668.23     10183826.84
      3779098.23     10184196.84      3778988.23     10184306.84
      3779088.23     10184506.84      3779278.23     10184636.84
      3779498.23     10184546.84      3779508.23     10184636.84

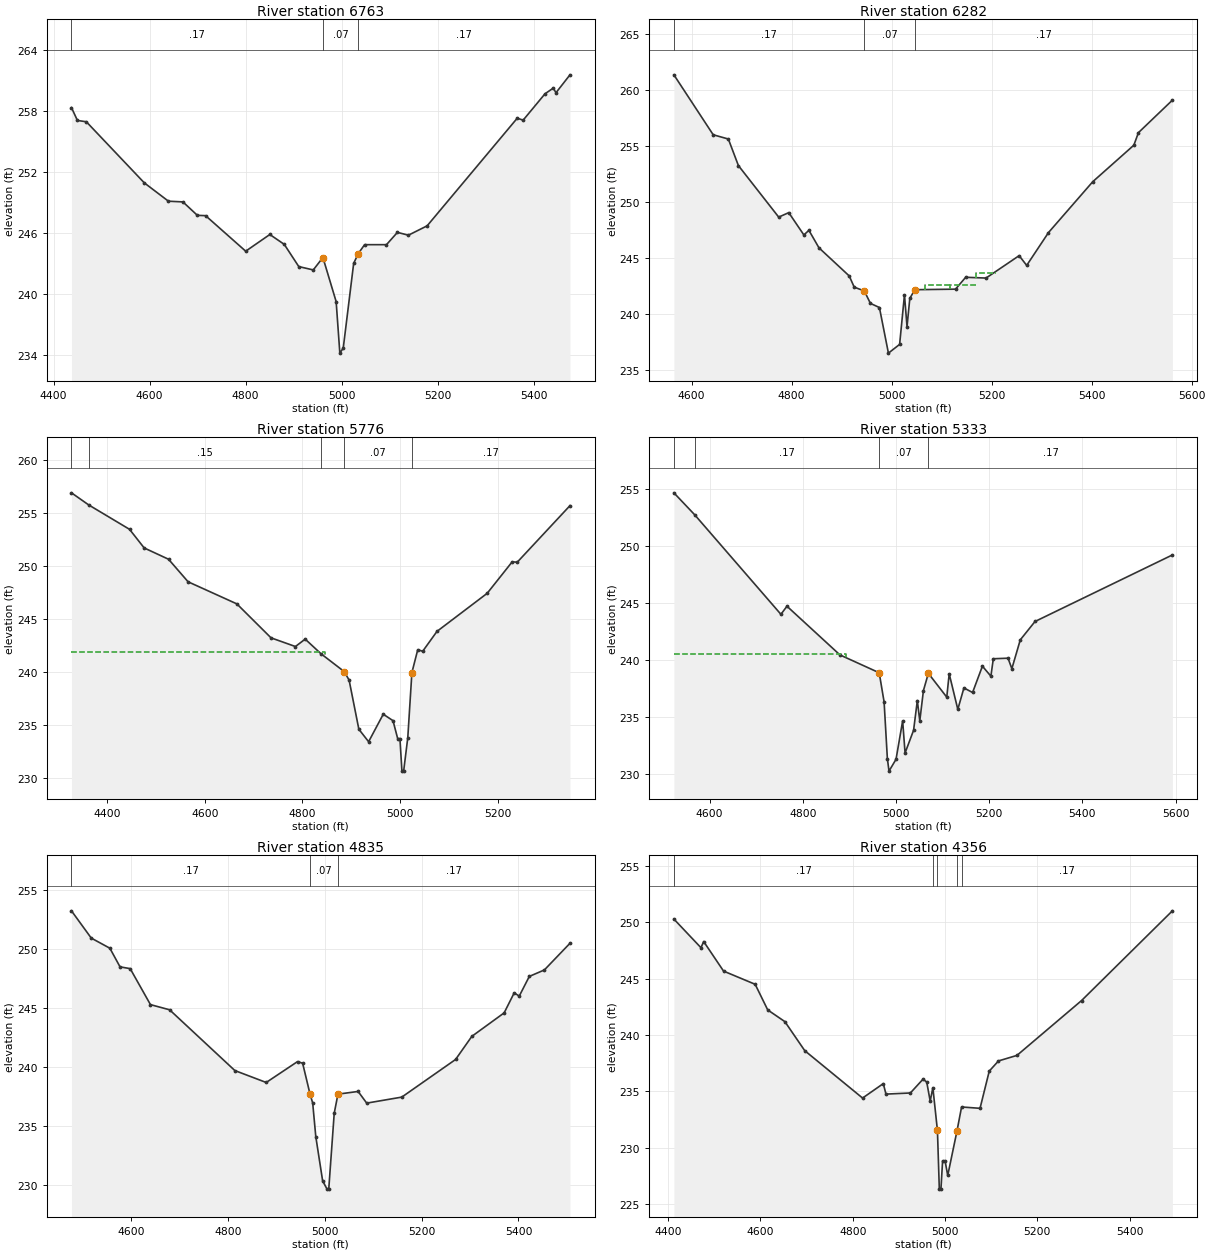
Type RM Length L Ch R = 1 ,6763    ,481,481,481
BEGIN DESCRIPTION:
WF OF SAN JAC RIVER TRIB NO 1 14.0
END DESCRIPTION:
XS GIS Cut Line= 3
      3775331.87     10183301.92      3775393.83     10182742.44
       3775596.2      10182311.6
#Sta/Elev= 30
  4437.1  258.33  4449.5  257.07  4468.1  256.94  4588.9  250.94  4639.2  249.14
  4669.4  249.07  4699.5  247.75  4716.6  247.72  4800.2  244.23  4850.5  245.87
  4880.6   244.9  4910.8  242.72    4941  242.39  4961.1  243.61  4988.7  239.28
  4996.4  234.22  5003.5  234.72  5025.2  243.03  5034.7  243.99    5048  244.87
  5093.6  244.87  5116.4  246.08  5139.2   245.8  5178.3  246.72  5366.1  257.29
  5378.4   257.1    5424  259.69  5441.3  260.25  5446.8  259.79    5476  261.55
#Mann= 3 , 0 , 0
  4437.1     .17       0  4961.1     .07       0  5034.7     .17       0
#XS Ineff= 2 , 0
       0  4850.5  245.87  5116.4       0  246.08
Permanent Ineff=
       F       F
Bank Sta=4961.1,5034.7
XS Rating Curve= 0 ,0
Exp/Cntr=0.3,0.1

Type RM Length L Ch R = 1 ,6282    ,506,506,506
BEGIN DESCRIPTION:
WF OF SAN JAC RIVER TRIB NO 1 13.0
END DESCRIPTION:
XS GIS Cut Line= 3
      3775726.49     10183339.16      3775778.23     10182906.84
      3775678.41     10182354.29
#Sta/Elev= 30
  4564.6  261.35  4643.2     256  4673.5  255.62  4693.6  253.25  4774.2  248.65
  4794.3  249.05  4824.5  247.06  4834.6  247.47  4854.7  245.91  4915.2   243.4
  4925.2   242.4  4945.4  242.06  4957.6  240.95  4975.6  240.58  4993.6  236.51
    5016  237.29  5025.7  241.71  5030.8  238.87  5036.4   241.4  5046.5  242.17
  5127.8  242.22  5148.1  243.28  5188.8  243.21    5255  245.21  5270.1  244.34
  5313.7  247.27  5402.2  251.81  5484.4  255.07  5493.6  256.19  5561.5  259.09
#Mann= 3 , 0 , 0
  4564.6     .17       0  4945.4     .07       0  5046.5     .17       0
#XS Ineff= 3 ,-1
  5066.8  5117.6   242.6  5117.6  5168.5  242.63  5168.5  5209.1  243.64
Permanent Ineff=
       F       F       F
Bank Sta=4945.4,5046.5
XS Rating Curve= 0 ,0
Exp/Cntr=0.3,0.1

Type RM Length L Ch R = 1 ,5776    ,443,443,443
BEGIN DESCRIPTION:
WF OF SAN JAC RIVER TRIB NO 1 12.0
END DESCRIPTION:
XS GIS Cut Line= 3
      3776061.55     10183380.04      3776058.23     10182706.84
      3775991.05     10182364.88
#Sta/Elev= 30
  4326.8  256.92    4362  255.78  4445.8  253.47  4475.8  251.71  4525.8  250.64
  4565.8  248.51  4665.8  246.42  4735.8  243.21  4785.8  242.39  4805.8  243.09
  4838.1  241.71  4885.8  240.02  4895.8  239.22  4915.8  234.57  4935.8  233.39
  4965.8  235.99  4985.8  235.38  4995.4  233.68    5000  233.68  5004.1  230.61
  5007.6  230.61  5016.1  233.78  5024.5  239.92  5036.5  242.09  5046.6  241.94
  5075.9  243.82  5178.8  247.42  5230.1   250.4  5240.4  250.36  5348.5  255.71
#Mann= 5 ,-1 , 0
  4326.8     .17       0    4362     .15       0  4838.1     .17       0
  4885.8     .07       0  5024.5     .17       0
#XS Ineff= 2 , 0
       0  4845.8  241.83               0
Permanent Ineff=
       F       F
Bank Sta=4885.8,5024.5
XS Rating Curve= 0 ,0
Exp/Cntr=0.3,0.1

Type RM Length L Ch R = 1 ,5333    ,498,498,498
BEGIN DESCRIPTION:
WF OF SAN JAC RIVER TRIB NO 1 11.0
END DESCRIPTION:
XS GIS Cut Line= 3
      3776236.54     10183368.87      3776388.23     10182916.84
       3776199.9     10182354.34
#Sta/Elev= 30
  4523.2  254.64  4567.7  252.72  4752.9  243.98  4765.9  244.69  4879.5  240.42
  4963.9  238.85  4974.4  236.29  4981.4  231.32  4984.9  230.22    5000  231.26
  5014.2  234.63  5019.4  231.81  5037.7  233.81  5045.7  236.41    5051  234.63
  5058.8  237.29  5069.4   238.8  5108.9  236.71  5114.1  238.76  5132.6  235.64
  5145.7  237.52  5164.3  237.12  5185.4  239.43  5203.6  238.55  5208.8  240.08
  5240.4  240.13  5248.6  239.21  5266.7  241.74  5298.3  243.35  5593.2  249.19
#Mann= 4 ,-1 , 0
  4523.2     .15       0  4567.7     .17       0  4963.9     .07       0
  5069.4     .17       0
#XS Ineff= 2 , 0
       0  4892.1  240.53               0
Permanent Ineff=
       F       F
Bank Sta=4963.9,5069.4
XS Rating Curve= 0 ,0
Exp/Cntr=0.3,0.1

Type RM Length L Ch R = 1 ,4835    ,479,479,479
BEGIN DESCRIPTION:
WF OF SAN JAC RIVER TRIB NO 1 10.0
END DESCRIPTION:
XS GIS Cut Line= 3
      3776631.16     10183476.85      3776788.23     10182976.84
      3776928.99      10182490.3
#Sta/Elev= 30
  4475.9   253.2  4516.8  250.89  4555.3  250.03  4576.3  248.45  4597.3   248.3
  4639.2  245.25  4678.8  244.81  4813.7  239.66  4878.5  238.65  4943.2  240.42
  4953.8  240.28 4969.08  237.67  4974.6  236.91    4981  234.06  4995.2   230.3
  5004.3  229.61  5007.8  229.61  5019.1  236.04  5026.8  237.66  5068.5  237.89
  5086.3   236.9  5158.8  237.41    5270   240.6  5303.6  242.56  5370.4  244.55
  5391.2  246.25  5401.6  245.97  5422.4  247.64  5453.6  248.19  5506.5  250.45
#Mann= 3 , 0 , 0
  4475.9     .17       0 4969.08     .07       0  5026.8     .17       0
#XS Ineff= 2 , 0
       0  4953.8  240.28               0
Permanent Ineff=
       F       F
Bank Sta=4969.08,5026.8
XS Rating Curve= 0 ,0
Exp/Cntr=0.3,0.1

Type RM Length L Ch R = 1 ,4356    ,983,983,983
BEGIN DESCRIPTION:
WF OF SAN JAC RIVER TRIB NO 1 9.0
END DESCRIPTION:
XS GIS Cut Line= 3
      3776921.52     10183543.91      3777218.23     10183036.84
      3777211.95     10182544.28
#Sta/Elev= 30
  4412.5  250.27  4471.2  247.73    4477  248.28  4520.1  245.66  4588.6  244.49
  4615.8  242.22    4653  241.18    4696  238.61  4821.3  234.41  4866.2  235.69
    4872  234.76  4924.9  234.86  4952.2  236.08  4960.3  235.83  4967.8  234.14
  4973.6  235.33  4983.5  231.54  4987.6  226.34  4991.1  226.34  4994.7  228.85
    5000  228.85  5005.8  227.55  5025.8  231.48  5035.8  233.62  5075.8   233.5
  5095.8   236.8  5115.8   237.7  5155.8  238.19  5295.8  243.05  5492.6     251
#Mann= 5 ,-1 , 0
  4412.5     .17       0  4973.6     .12       0  4983.5     .09       0
  5025.8     .12       0  5035.8     .17       0
Bank Sta=4983.5,5025.8
XS Rating Curve= 0 ,0
Exp/Cntr=0.3,0.1

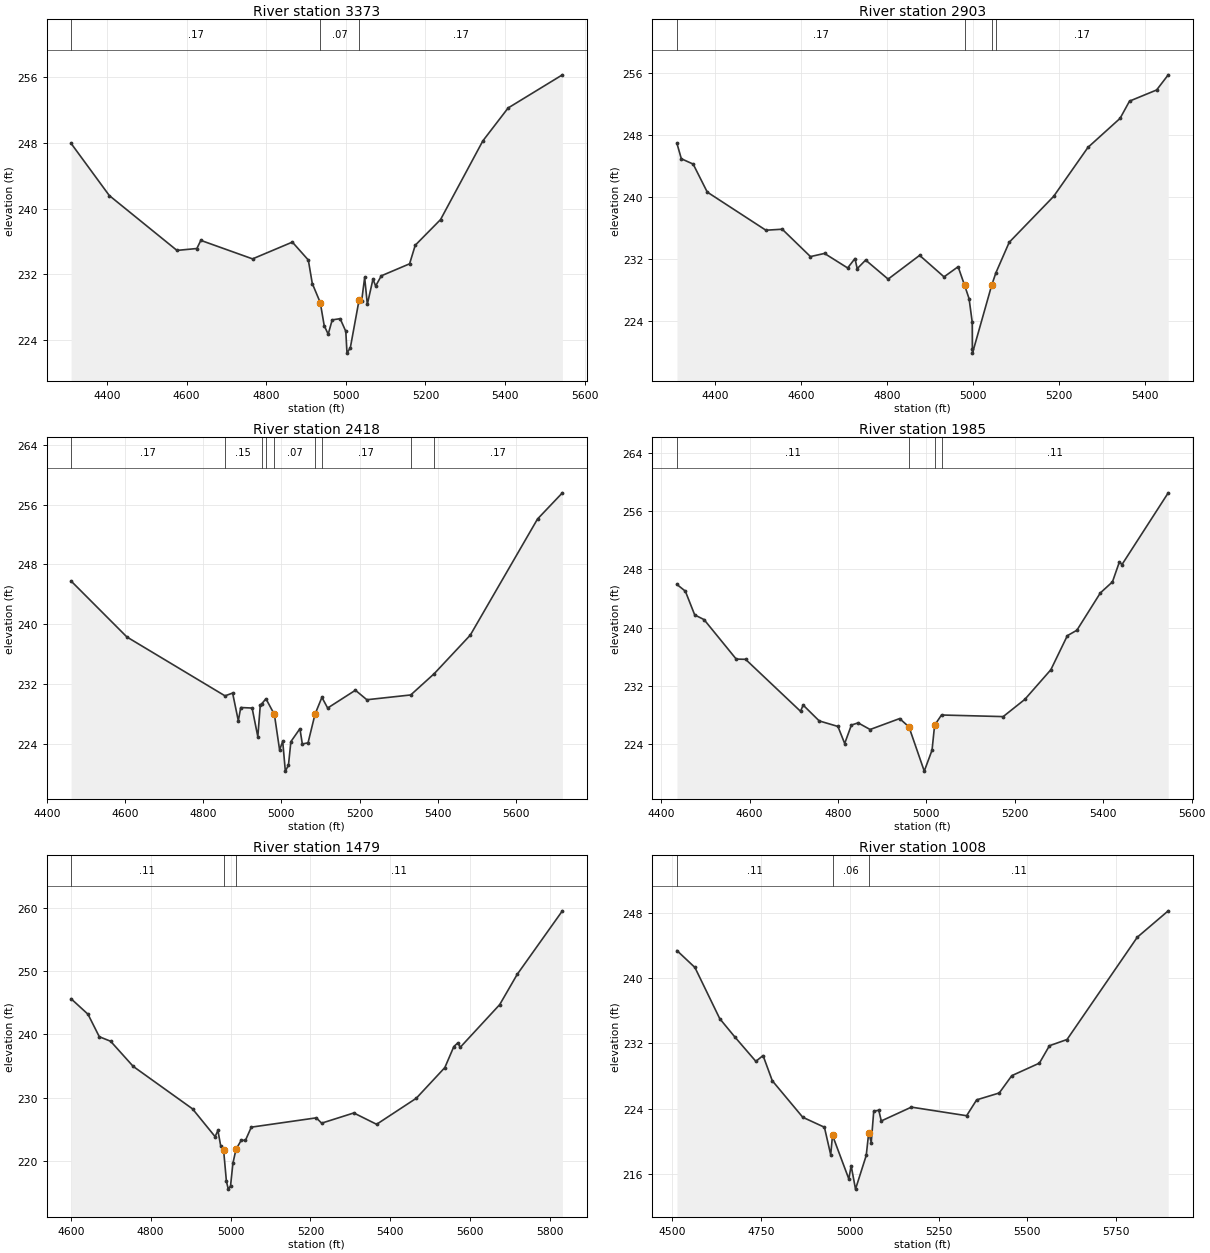
Type RM Length L Ch R = 1 ,3373    ,470,470,470
BEGIN DESCRIPTION:
WF OF SAN JAC RIVER TRIB NO 1 7.0
END DESCRIPTION:
XS GIS Cut Line= 3
      3777651.22       10183797.      3777637.27     10183106.84
      3777997.46     10182698.77
#Sta/Elev= 30
  4309.7  247.92  4405.7  241.58  4575.7  234.91  4625.7  235.14  4635.7  236.13
  4765.7  233.88  4865.7  235.92  4905.8  233.74  4915.8  230.88  4935.8  228.57
  4945.8  225.75  4955.8  224.72  4965.8  226.46  4985.8  226.61    5000  225.07
    5003  222.42  5011.4  223.08  5033.2  228.84  5039.9   228.8  5047.4  231.62
  5054.1  228.35  5068.3  231.42    5075  230.58  5089.2  231.82  5160.3  233.28
  5174.5  235.54  5238.1  238.66  5344.4  248.23  5407.9  252.23  5544.3  256.26
#Mann= 3 , 0 , 0
  4309.7     .17       0  4935.8     .07       0  5033.2     .17       0
Bank Sta=4935.8,5033.2
XS Rating Curve= 0 ,0
Exp/Cntr=0.3,0.1

Type RM Length L Ch R = 1 ,2903    ,485,485,485
BEGIN DESCRIPTION:
WF OF SAN JAC RIVER TRIB NO 1 6.0
END DESCRIPTION:
XS GIS Cut Line= 3
      3777811.31     10183830.54      3778013.01     10183171.62
      3778130.97     10182734.15
#Sta/Elev= 30
  4310.9  246.95  4321.1  244.96  4348.6  244.27  4381.4  240.65  4517.7  235.72
  4555.7  235.85  4621.3  232.31    4654  232.72  4707.8  230.84  4724.8  232.06
    4730  230.75  4749.6  231.86  4801.9   229.4  4875.1  232.47  4931.9  229.69
  4964.6     231  4979.7  228.59  4990.1  226.87  4997.4  223.84  4997.7  220.33
    4998  219.83  5042.5  228.58  5052.4  230.21  5083.4  234.16  5186.6  240.09
  5266.5  246.43  5341.1  250.18  5363.1  252.41  5426.1  253.85  5453.1  255.81
#Mann= 4 ,-1 , 0
  4310.9     .17       0  4979.7     .07       0  5042.5     .11       0
  5052.4     .17       0
Bank Sta=4979.7,5042.5
XS Rating Curve= 0 ,0
Exp/Cntr=0.3,0.1

Type RM Length L Ch R = 1 ,2418    ,433,433,433
BEGIN DESCRIPTION:
WF OF SAN JAC RIVER TRIB NO 1 5.0
END DESCRIPTION:
XS GIS Cut Line= 3
      3777963.97     10183916.14      3778288.23     10183486.84
      3778867.85     10183061.07
#Sta/Elev= 30
    4462  245.78  4604.7  238.31  4855.8  230.44  4875.3  230.81  4889.9   227.1
  4896.1  228.88  4925.2  228.81  4939.8  224.98  4946.1  229.21  4949.4  229.35
  4960.6  230.05  4982.2  227.95  4995.5  223.22  5003.5  224.36  5010.2  220.38
  5018.2  221.17  5024.4  224.32  5047.5  226.05  5053.7  224.01  5068.3  224.16
 5086.14  227.98  5103.8  230.24  5118.5  228.81  5189.5  231.19  5218.8  229.92
  5331.1  230.56  5391.1   233.4  5483.4  238.55  5655.5  254.07  5719.2  257.57
#Mann= 9 ,-1 , 0
    4462     .17       0  4855.8     .15       0  4949.4     .17       0
  4960.6     .11       0  4982.2     .07       0 5086.14     .11       0
  5103.8     .17       0  5331.1     .15       0  5391.1     .17       0
Bank Sta=4982.2,5086.14
XS Rating Curve= 0 ,0
Exp/Cntr=0.3,0.1

Type RM Length L Ch R = 1 ,1985    ,506,506,506
BEGIN DESCRIPTION:
WF OF SAN JAC RIVER TRIB NO 1 4.0
END DESCRIPTION:
XS GIS Cut Line= 3
      3778369.75     10184057.62      3778673.63     10183582.25
      3778946.77     10183108.32
#Sta/Elev= 30
  4435.8  245.93  4454.8  245.01    4476  241.75  4497.1  241.11  4569.9  235.69
    4591  235.66  4715.3  228.53  4721.3  229.38  4757.6  227.21  4799.9  226.45
  4815.2  224.11  4830.4  226.64  4845.6  226.94  4872.7  226.03  4939.5  227.53
  4960.6  226.39  4995.2  220.32  5012.8   223.2  5018.6  226.62  5034.2  228.02
  5173.7   227.8  5222.6  230.16  5281.5  234.23  5318.8   238.9  5340.4  239.65
  5393.5  244.77  5420.8  246.28  5436.6  249.03  5442.4  248.66    5547   258.5
#Mann= 4 ,-1 , 0
  4435.8     .11       0  4960.6     .06       0  5018.6     .11       0
  5034.2     .11       0
#XS Ineff= 2 , 0
       0  4721.3  229.38               0
Permanent Ineff=
       F       F
Bank Sta=4960.6,5018.6
XS Rating Curve= 0 ,0
Exp/Cntr=0.3,0.1

Type RM Length L Ch R = 1 ,1479    ,471,471,471
BEGIN DESCRIPTION:
WF OF SAN JAC RIVER TRIB NO 1 3.0
END DESCRIPTION:
XS GIS Cut Line= 3
      3778517.88     10184211.04      3778798.23     10183926.84
      3779036.14     10183130.63
#Sta/Elev= 30
  4600.8  245.63  4643.1  243.19  4671.4  239.64  4699.7  238.93  4756.3  234.96
  4904.8  228.26  4961.4  223.87  4968.4  224.85  4975.5  222.37  4982.6  221.79
  4989.7  216.82  4994.4  215.59    5000  216.09    5006  219.68  5013.7  221.88
  5026.9  223.31  5037.3  223.28    5052  225.37  5214.8  226.84  5228.1     226
  5308.7  227.61  5365.8  225.82  5465.1  229.93  5536.6  234.77  5559.2  238.09
  5569.6  238.69  5574.9  237.95    5674  244.71  5717.8  249.48    5831  259.51
#Mann= 3 , 0 , 0
  4600.8     .11       0  4982.6     .06       0  5013.7     .11       0
Bank Sta=4982.6,5013.7
XS Rating Curve= 0 ,0
Exp/Cntr=0.3,0.1

Type RM Length L Ch R = 1 ,1008    ,509,509,509
BEGIN DESCRIPTION:
WF OF SAN JAC RIVER TRIB NO 1 2.0
END DESCRIPTION:
XS GIS Cut Line= 3
      3778619.19     10184314.51      3779098.23     10184226.84
       3779728.6     10183588.55
#Sta/Elev= 30
    4513  243.36  4563.7  241.29  4633.6  235.03  4675.2  232.84  4735.3  229.81
  4755.6  230.52  4781.6  227.44  4867.5  222.97  4928.5  221.75  4946.2  218.38
  4951.3  220.76  4997.3  215.42  5003.8  217.05  5016.1  214.18  5046.3   218.3
  5053.3  221.09  5060.4  219.88  5067.4   223.7  5081.6  223.83  5088.7  222.52
  5173.5  224.21  5329.1  223.16  5357.4   225.1    5421  225.94  5456.4  228.06
  5534.1  229.59  5562.4  231.72    5612  232.48  5809.9  244.99  5897.1  248.22
#Mann= 3 , 0 , 0
    4513     .11       0  4951.3     .06       0  5053.3     .11       0
#XS Ineff= 2 , 0
       0                  5067.4       0   223.7
Permanent Ineff=
       F       F
Bank Sta=4951.3,5053.3
XS Rating Curve= 0 ,0
Exp/Cntr=0.3,0.1

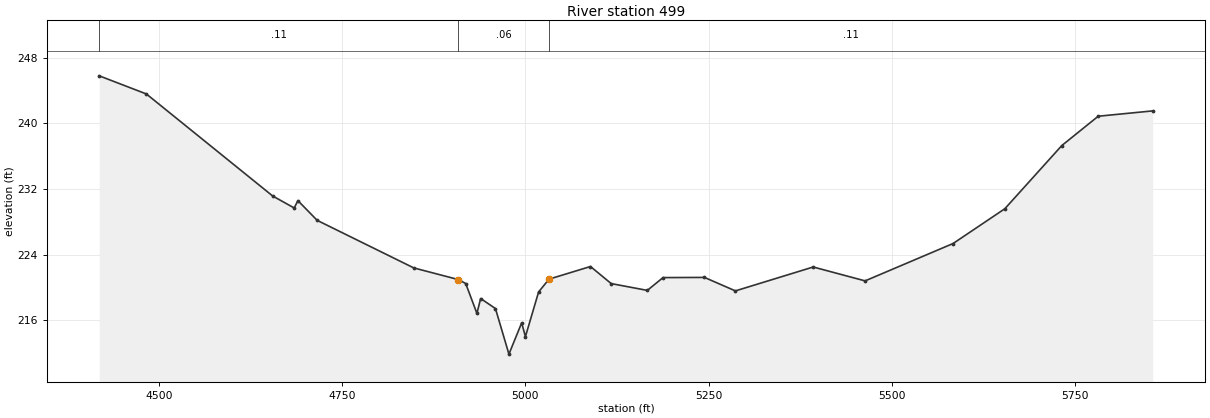
Type RM Length L Ch R = 1 ,499     ,0,0,0
BEGIN DESCRIPTION:
WF OF SAN JAC RIVER TRIB NO 1 1.0
END DESCRIPTION:
XS GIS Cut Line= 3
      3778604.31     10184482.05      3779178.23     10184576.84
      3779773.08     10183961.03
#Sta/Elev= 30
  4418.3  245.79  4482.7  243.58    4655  231.16  4684.4   229.7  4689.5  230.59
  4715.8  228.19  4847.6   222.4  4908.4  220.98  4918.5   220.5  4933.8  216.86
  4938.9  218.67  4959.1  217.45  4977.5   211.9  4994.9  215.71    5000  214.03
    5018  219.47  5032.2  221.03  5088.8  222.57  5117.1  220.49  5166.4  219.66
  5187.8  221.22  5244.4  221.24  5286.6   219.6  5392.8  222.51  5463.6  220.82
  5583.7  225.37  5654.4  229.61  5732.1   237.3  5781.8  240.87  5856.2  241.52
#Mann= 3 , 0 , 0
  4418.3     .11       0  4908.4     .06       0  5032.2     .11       0
Bank Sta=4908.4,5032.2
XS Rating Curve= 0 ,0
Exp/Cntr=0.3,0.1

Chan Stop Cuts=-1
Use User Specified Reach Order=0
Composite Channel Slope=5