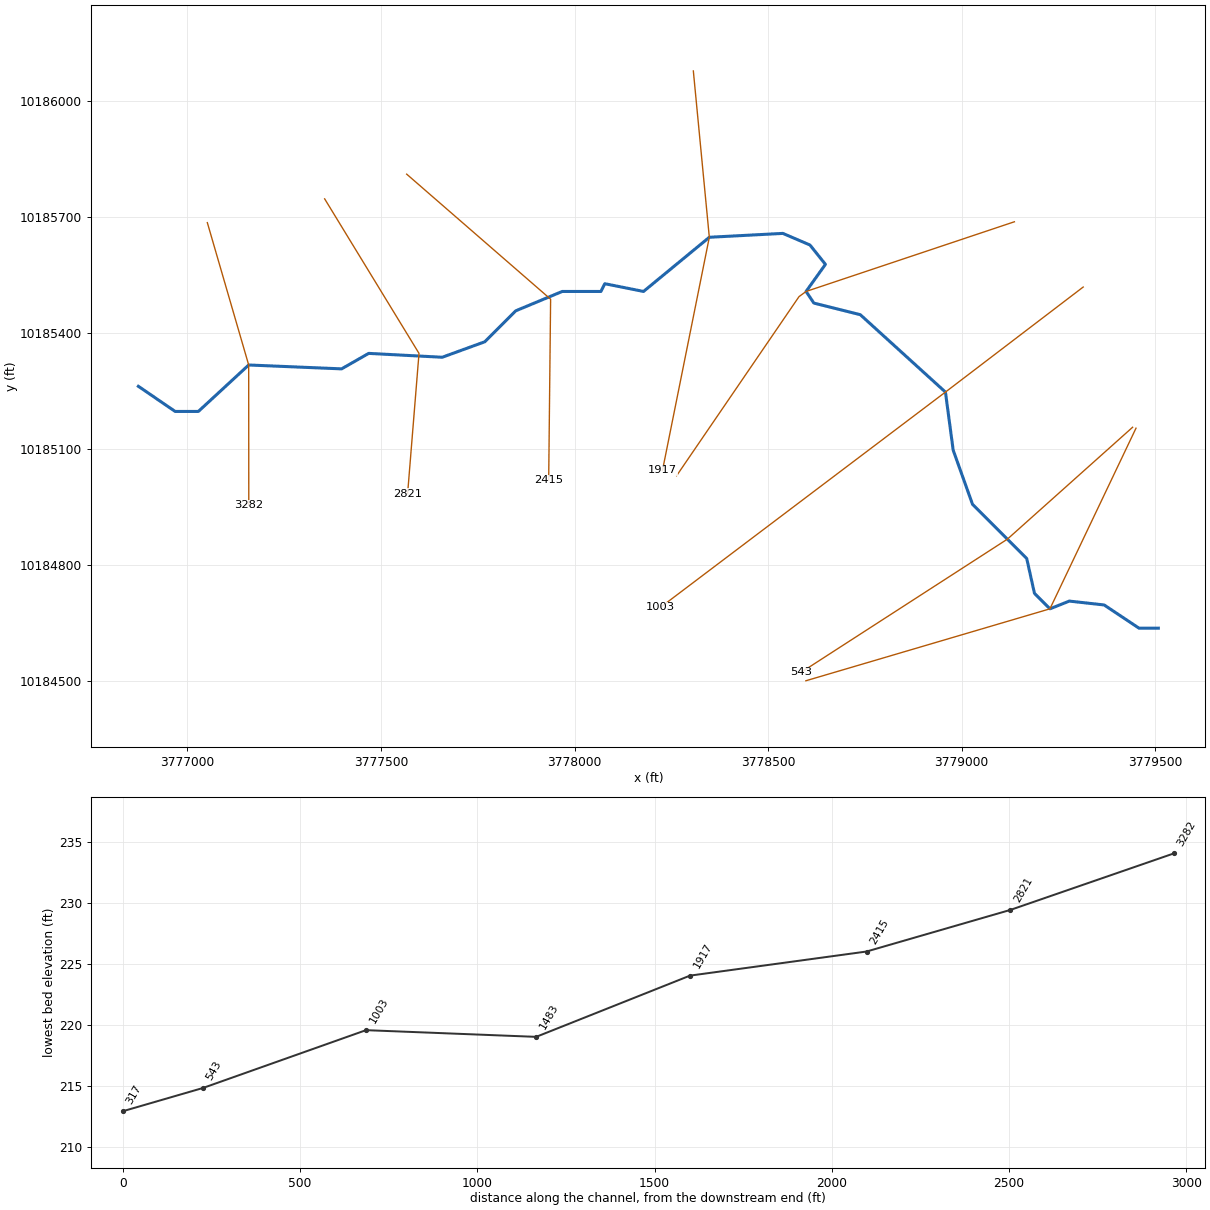
--- WF OF SAN JAC RIVER TRIB NO 1_1.prj (project) ---

Proj Title=WF OF SAN JAC RIVER TRIB NO 1_1 Base Level Engineering
Current Plan=p01
Default Exp/Contr=0.3,0.1
English Units
Geom File=g01
Flow File=f01
Plan File=p01
Y Axis Title=Elevation
X Axis Title(PF)=Main Channel Distance
X Axis Title(XS)=Station
BEGIN DESCRIPTION:
WF OF SAN JAC RIVER TRIB NO 1_1
END DESCRIPTION:
DSS Export Rating Curves= 0
DSS Export Rating Curve Sorted= 0
DSS Export Volume Flow Curves= 0
DXF OffsetX= 0
DXF OffsetY= 0
DXF ScaleX= 1
DXF ScaleY= 10

--- WF OF SAN JAC RIVER TRIB NO 1_1.p01 (plan) ---

Plan Title=Multiple Run
Short Identifier=Multiple
Geom File=g01
Flow File=f01
Subcritical Flow
K Sum by GR= 0
Std Step Tol= 0.01
Critical Tol= 0.01
Num of Std Step Trials= 20
Max Error Tol= 0.3
Flow Tol Ratio= 0.001
Split Flow NTrial= 30
Split Flow Tol= 0.02
Split Flow Ratio= 0.02
Log Output Level= 0
Friction Slope Method= 1
Unsteady Friction Slope Method= 2
Unsteady Bridges Friction Slope Method= 1
Parabolic Critical Depth
Global Vel Dist=  1 , 1 , 1
Global Log Level= 0
CheckData=True
Encroach Param= -1, 0, 0, 0
BEGIN DESCRIPTION:
Multiple Run
END DESCRIPTION:

--- WF OF SAN JAC RIVER TRIB NO 1_1.f01 (steady flow) ---

Flow Title=Multiple
Program Version=4.10
Number of Profiles= 7
Profile Names=10-year,25-year,50-year,1pct_min,100-year,1pct_plu,500-year
River Rch & RM=WF OF SAN JAC RI,Reach-1         ,3282
     533     711     951     419    1264    3817    2310
Boundary for River Rch & Prof#=WF OF SAN JAC RI,Reach-1         , 1
Up Type= 0
Dn Type= 3
Dn Slope=0.01
Boundary for River Rch & Prof#=WF OF SAN JAC RI,Reach-1         , 2
Up Type= 0
Dn Type= 3
Dn Slope=0.01
Boundary for River Rch & Prof#=WF OF SAN JAC RI,Reach-1         , 3
Up Type= 0
Dn Type= 3
Dn Slope=0.01
Boundary for River Rch & Prof#=WF OF SAN JAC RI,Reach-1         , 4
Up Type= 0
Dn Type= 3
Dn Slope=0.01
Boundary for River Rch & Prof#=WF OF SAN JAC RI,Reach-1         , 5
Up Type= 0
Dn Type= 3
Dn Slope=0.01
Boundary for River Rch & Prof#=WF OF SAN JAC RI,Reach-1         , 6
Up Type= 0
Dn Type= 3
Dn Slope=0.01
Boundary for River Rch & Prof#=WF OF SAN JAC RI,Reach-1         , 7
Up Type= 0
Dn Type= 3
Dn Slope=0.01
DSS Import GetInterval= 0
DSS Import GetPeak= 0
DSS Import FillOption= 0

--- WF OF SAN JAC RIVER TRIB NO 1_1.g01 (geometry) ---

Geom Title=Existing Conditions
Program Version=4.10

River Reach=WF OF SAN JAC RI,Reach-1
Reach XY= 30
      3776873.23     10185261.84      3776968.23     10185196.84
      3777028.23     10185196.84      3777158.23     10185316.84
      3777398.23     10185306.84      3777468.23     10185346.84
      3777658.23     10185336.84      3777768.23     10185376.84
      3777848.23     10185456.84      3777968.23     10185506.84
      3778068.23     10185506.84      3778078.23     10185526.84
      3778178.23     10185506.84      3778348.23     10185646.84
      3778538.23     10185656.84      3778608.23     10185626.84
      3778648.23     10185576.84      3778598.23     10185506.84
      3778618.23     10185476.84      3778738.23     10185446.84
      3778958.23     10185246.84      3778978.23     10185096.84
      3779028.23     10184956.84      3779168.23     10184816.84
      3779188.23     10184726.84      3779228.23     10184686.84
      3779278.23     10184706.84      3779368.23     10184696.84
      3779458.23     10184636.84      3779508.23     10184636.84

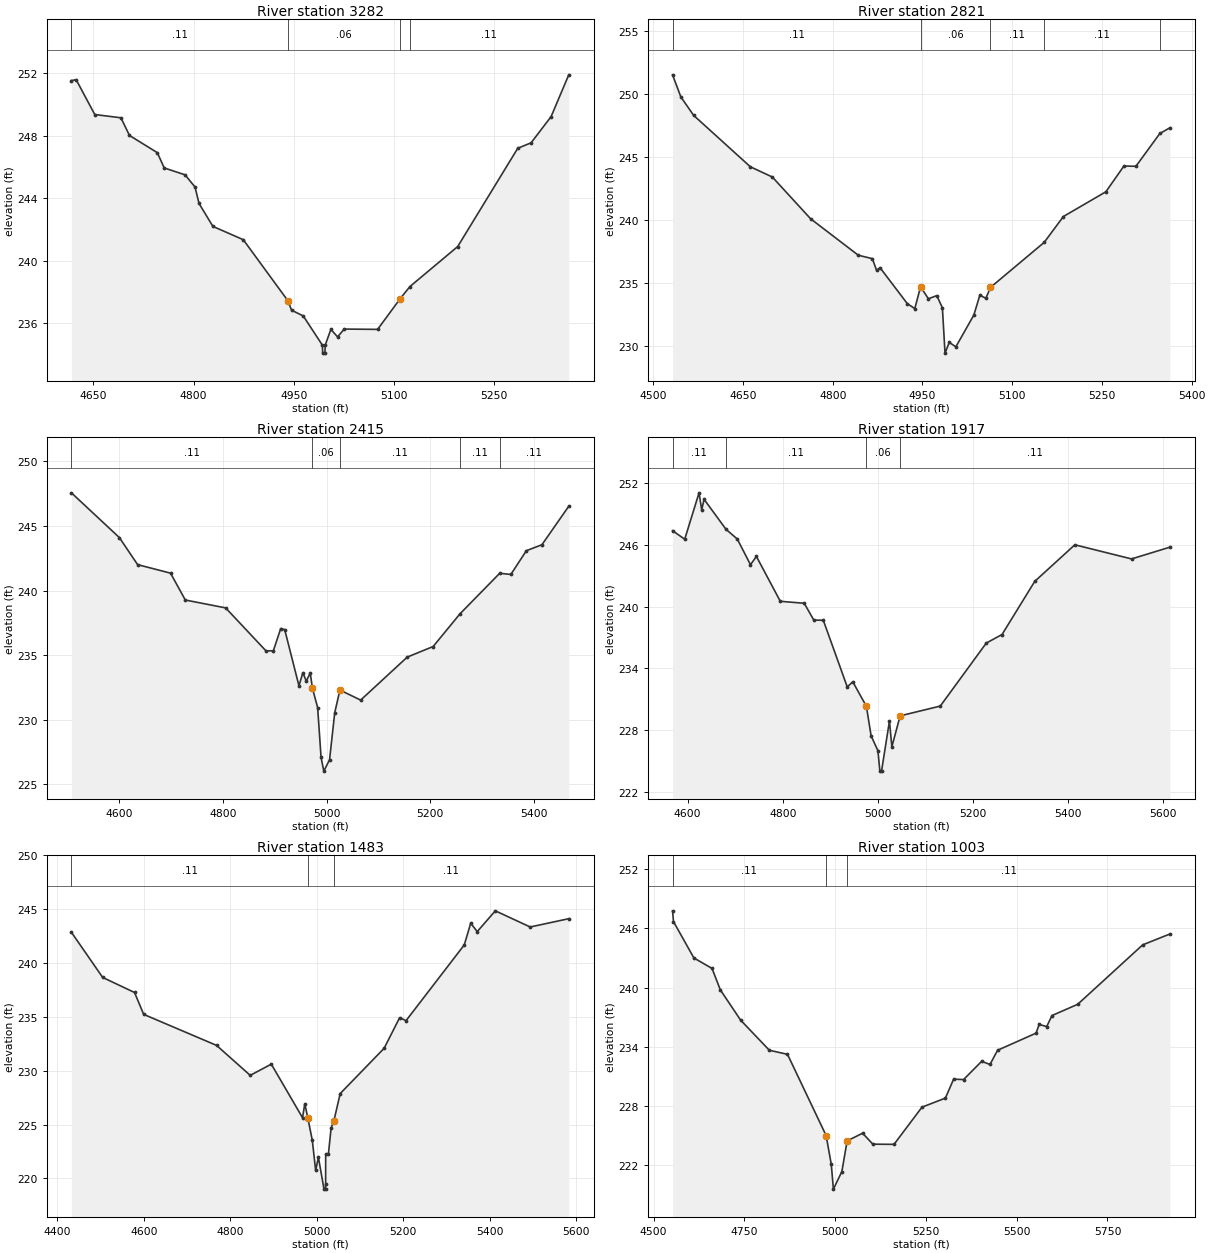
Type RM Length L Ch R = 1 ,3282    ,461,461,461
BEGIN DESCRIPTION:
WF OF SAN JAC RIVER TRIB NO 1_1 7.0
END DESCRIPTION:
XS GIS Cut Line= 3
      3777051.38     10185684.64      3777158.23     10185316.84
      3777158.48     10184954.64
#Sta/Elev= 30
    4617  251.52  4624.1  251.58    4652  249.35  4691.2  249.14    4704  248.01
  4745.7  246.91  4756.1  245.93  4787.3  245.49  4802.2  244.71  4808.2  243.66
    4829  242.19  4874.5  241.34  4941.6  237.42  4946.8  236.83  4964.4  236.46
  4993.2  234.58  4993.4  234.08  4996.9  234.08  4997.2  234.58  5005.8   235.6
  5015.8  235.12  5025.8  235.62  5075.8   235.6  5109.7  237.57  5124.2  238.34
  5195.8   240.9  5285.8  247.19  5305.8  247.54  5335.8  249.22  5362.2  251.89
#Mann= 4 ,-1 , 0
    4617     .11       0  4941.6     .06       0  5109.7     .11       0
  5124.2     .11       0
Bank Sta=4941.6,5109.7
XS Rating Curve= 0 ,0
Exp/Cntr=0.3,0.1

Type RM Length L Ch R = 1 ,2821    ,406,406,406
BEGIN DESCRIPTION:
WF OF SAN JAC RIVER TRIB NO 1_1 6.0
END DESCRIPTION:
XS GIS Cut Line= 3
      3777354.47     10185746.11      3777598.23     10185346.84
      3777568.78     10184984.44
#Sta/Elev= 30
  4532.2   251.5  4546.1  249.75  4567.4  248.29  4662.3  244.21    4699   243.4
    4763  240.09  4842.7   237.2  4866.2  236.93  4873.3     236  4879.1  236.21
  4924.7  233.36  4937.2  232.97  4946.8   234.7  4959.9  233.75    4974     234
  4983.3  233.03  4987.7  229.44  4994.8  230.29  5005.8  229.94  5035.9  232.46
  5045.9  234.03    5056  233.79  5063.7  234.65  5153.5  238.22  5185.6  240.27
  5256.6  242.23  5286.7  244.27  5306.8  244.25  5346.8  246.85  5363.6   247.3
#Mann= 5 ,-1 , 0
  4532.2     .11       0  4946.8     .06       0  5063.7     .11       0
  5153.5     .11       0  5346.8     .11       0
Bank Sta=4946.8,5063.7
XS Rating Curve= 0 ,0
Exp/Cntr=0.3,0.1

Type RM Length L Ch R = 1 ,2415    ,498,498,498
BEGIN DESCRIPTION:
WF OF SAN JAC RIVER TRIB NO 1_1 5.0
END DESCRIPTION:
XS GIS Cut Line= 3
      3777566.38     10185809.93      3777938.23     10185486.84
      3777933.24     10185019.27
#Sta/Elev= 30
  4507.4  247.57  4600.1   244.1  4635.2  242.01  4698.8  241.35  4727.3  239.27
  4805.2  238.66  4883.1  235.33  4897.3  235.34  4911.5  237.06  4919.2  236.98
  4946.7  232.63  4954.3  233.64  4960.9  232.99  4968.5  233.62 4972.84  232.42
  4982.8  230.94  4989.4  227.08  4994.7  226.02  5005.8   226.9  5015.8  230.55
  5025.8   232.3  5065.8  231.52  5155.8  234.85  5205.8  235.67  5257.6   238.2
  5334.3  241.34  5355.8  241.25  5385.8  243.09  5415.8  243.55  5467.6  246.53
#Mann= 5 ,-1 , 0
  4507.4     .11       0 4972.84     .06       0  5025.8     .11       0
  5257.6     .11       0  5334.3     .11       0
#XS Ineff= 2 , 0
       0  4911.5  237.06               0
Permanent Ineff=
       F       F
Bank Sta=4972.84,5025.8
XS Rating Curve= 0 ,0
Exp/Cntr=0.3,0.1

Type RM Length L Ch R = 1 ,1917    ,434,434,434
BEGIN DESCRIPTION:
WF OF SAN JAC RIVER TRIB NO 1_1 4.0
END DESCRIPTION:
XS GIS Cut Line= 3
      3778306.94     10186076.57      3778348.23     10185646.84
      3778227.36     10185045.16
#Sta/Elev= 30
  4568.3  247.36  4593.9  246.53    4624  251.03  4629.6  249.38  4634.6   250.4
  4680.7  247.49  4704.4  246.55  4732.1  244.06  4744.6  244.86  4794.8  240.51
  4845.1  240.32  4865.2  238.69  4885.2  238.67  4935.5  232.21  4947.2   232.7
  4975.7  230.33  4985.7  227.46    5000  226.02  5004.1  224.04  5007.6  224.04
  5024.2  228.89  5029.3   226.4  5046.7   229.4  5131.1  230.35  5227.8  236.46
  5260.9  237.29  5329.6  242.44  5413.9  245.99  5533.1  244.62  5613.7  245.76
#Mann= 4 ,-1 , 0
  4568.3     .11       0  4680.7     .11       0  4975.7     .06       0
  5046.7     .11       0
Bank Sta=4975.7,5046.7
XS Rating Curve= 0 ,0
Exp/Cntr=0.3,0.1

Type RM Length L Ch R = 1 ,1483    ,480,480,480
BEGIN DESCRIPTION:
WF OF SAN JAC RIVER TRIB NO 1_1 3.0
END DESCRIPTION:
XS GIS Cut Line= 4
      3779136.41      10185686.9      3778598.23     10185506.84
      3778579.96     10185493.49      3778263.67     10185030.67
#Sta/Elev= 30
  4432.5  242.85  4504.8  238.66  4578.6  237.26  4599.7  235.23  4768.4  232.35
  4846.2  229.57    4895  230.61  4967.2  225.64  4972.5  226.93  4979.3  225.65
  4989.9  223.53  4997.6  220.74    5004  221.96  5016.9  219.01  5020.4  219.01
  5020.7  219.51  5020.8  222.26  5027.1  222.26  5033.4  224.69  5039.5   225.3
  5054.4  227.88    5156  232.08  5191.9  234.92  5206.8  234.65  5341.5  241.68
  5356.4  243.69  5371.4  242.91  5413.3  244.84    5494  243.34  5583.2  244.11
#Mann= 3 , 0 , 0
  4432.5     .11       0  4979.3     .06       0  5039.5     .11       0
Bank Sta=4979.3,5039.5
XS Rating Curve= 0 ,0
Exp/Cntr=0.3,0.1

Type RM Length L Ch R = 1 ,1003    ,460,460,460
BEGIN DESCRIPTION:
WF OF SAN JAC RIVER TRIB NO 1_1 2.0
END DESCRIPTION:
XS GIS Cut Line= 3
      3779314.14     10185518.28      3778958.23     10185246.84
      3778222.73     10184691.18
#Sta/Elev= 30
  4552.4  247.78    4555  246.69  4611.2     243  4661.1  241.94  4683.9  239.77
    4740  236.69    4819  233.64  4868.9  233.23  4975.3  224.99  4989.5  222.06
  4995.3  219.56  5018.6  221.34  5033.1  224.45  5075.7  225.23  5103.9  224.12
  5162.2   224.1  5239.2  227.87  5303.7  228.79  5326.3  230.71  5353.7  230.67
  5403.6  232.52  5426.5   232.2  5447.3  233.64  5553.5  235.38  5561.8  236.26
  5582.6  236.04  5597.1  237.16  5667.9   238.3  5846.9  244.33  5921.8  245.43
#Mann= 3 , 0 , 0
  4552.4     .11       0  4975.3     .06       0  5033.1     .11       0
Bank Sta=4975.3,5033.1
XS Rating Curve= 0 ,0
Exp/Cntr=0.3,0.1

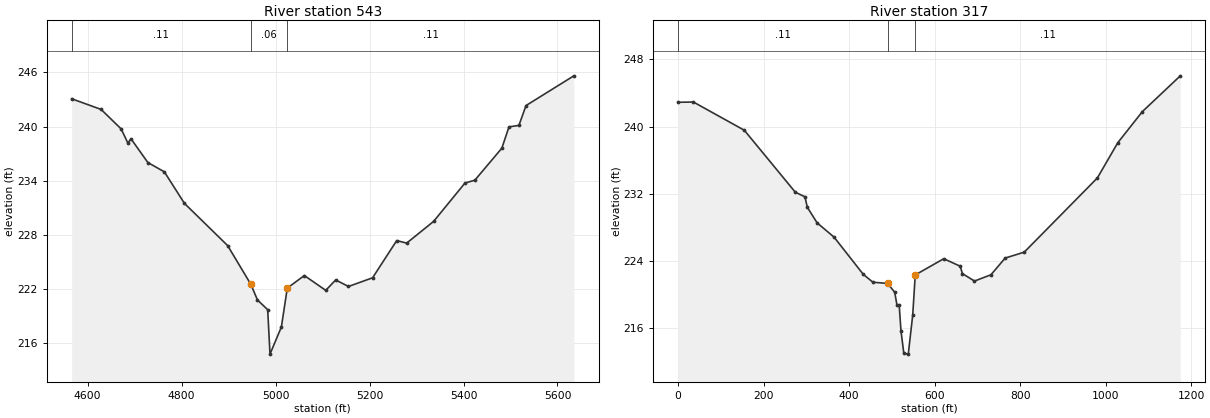
Type RM Length L Ch R = 1 ,543     ,226,226,226
BEGIN DESCRIPTION:
WF OF SAN JAC RIVER TRIB NO 1_1 1.0
END DESCRIPTION:
XS GIS Cut Line= 3
      3779441.76     10185155.98      3779118.23     10184866.84
      3778584.95     10184522.49
#Sta/Elev= 30
  4566.1  243.08  4628.8   241.9  4671.5  239.74  4685.7  238.18  4692.4  238.65
  4728.3  236.02  4763.4  234.99  4806.1   231.5    4898  226.83  4947.4  222.54
  4961.6   220.8  4983.3  219.73  4988.2  214.81  5012.4  217.81    5025  222.12
  5061.3  223.51  5106.8  221.87    5128  223.02  5155.2   222.3  5206.5  223.26
  5257.9  227.38  5279.1   227.1  5336.5  229.51  5403.1  233.75  5424.2  234.07
  5481.6  237.61  5496.8  239.97  5517.9  240.13  5533.1  242.33  5634.8  245.62
#Mann= 3 , 0 , 0
  4566.1     .11       0  4947.4     .06       0    5025     .11       0
Bank Sta=4947.4,5025
XS Rating Curve= 0 ,0
Exp/Cntr=0.3,0.1

Type RM Length L Ch R = 1 ,317     ,0,0,0
XS GIS Cut Line= 3
      3779450.54     10185153.57      3779228.23     10184686.84
      3778597.71     10184500.98
#Sta/Elev= 30
       0  242.89    35.8  242.92   154.8  239.56   273.9  232.19   296.6  231.63
   302.1  230.39   324.9  228.54   364.7  226.83   432.8  222.41   455.5  221.46
   490.1  221.32   506.5  220.26   511.9   218.7     517   218.7   521.1   215.7
   527.8  212.98   538.2   212.9   548.6  217.56   554.5  222.33   621.1  224.26
   659.6  223.37   664.8  222.49     693   221.6   731.5  222.35   764.8  224.34
   809.3  225.04   980.4  233.88  1028.2  238.08  1085.6  241.78  1174.3  246.04
#Mann= 3 , 0 , 0
       0     .11       0   490.1     .06       0   554.5     .11       0
Bank Sta=490.1,554.5
XS Rating Curve= 0 ,0
Exp/Cntr=0.3,0.1

Chan Stop Cuts=-1
Use User Specified Reach Order=0
Composite Channel Slope=5