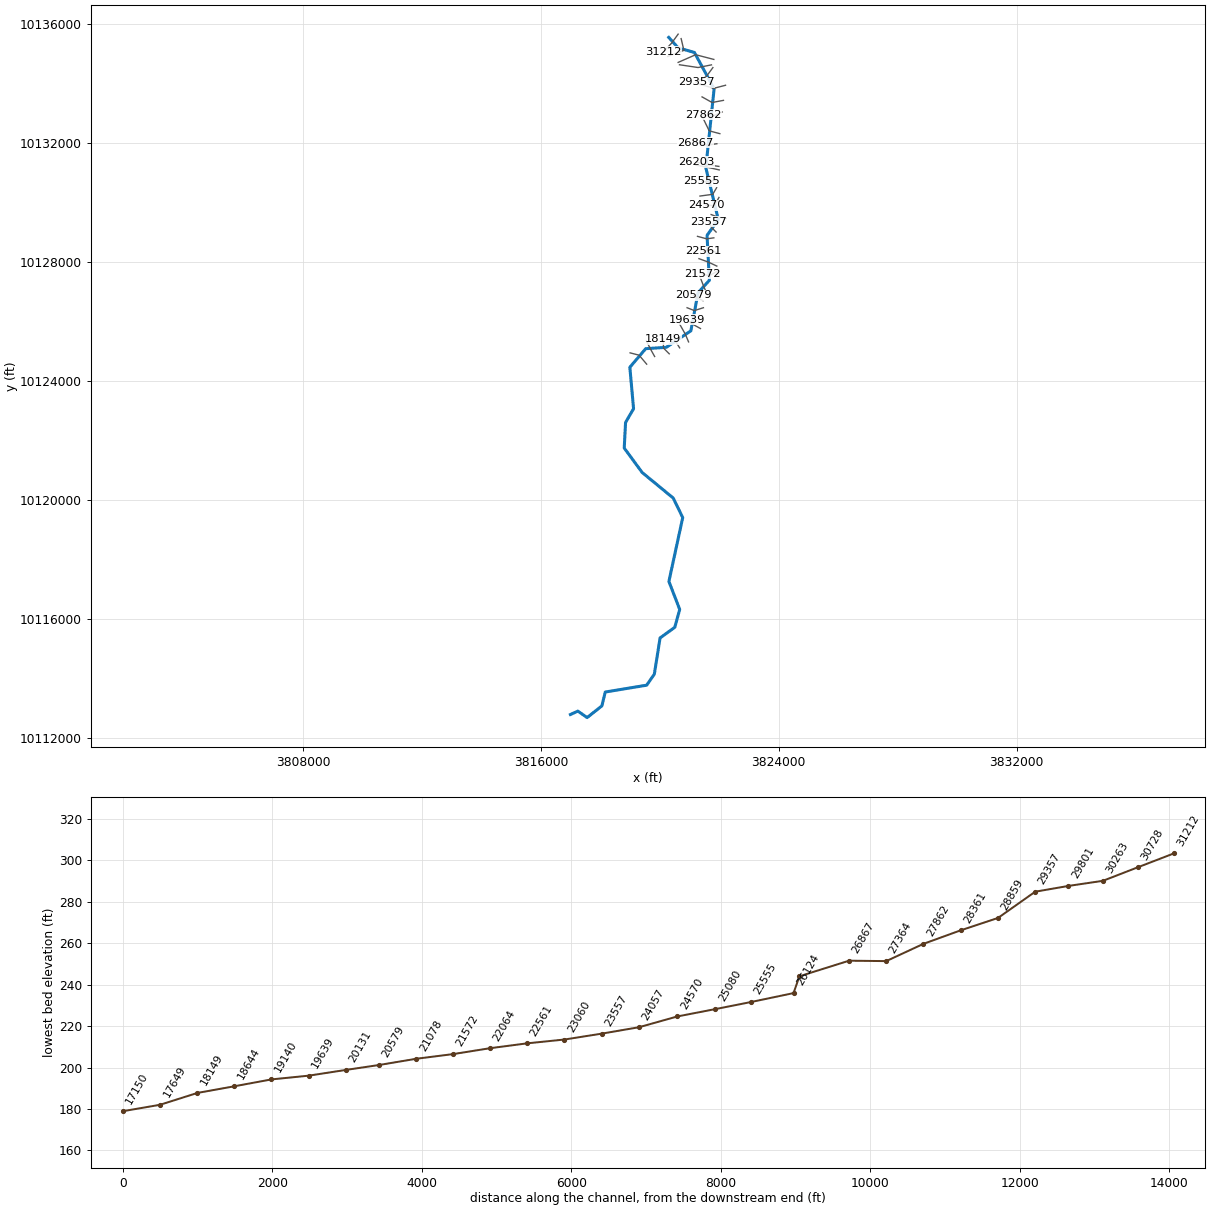
--- WHITE OAK CREEK NORTH.prj (project) ---

Proj Title=WHITE OAK CREEK NORTH Base Level Engineering
Current Plan=p01
Default Exp/Contr=0.3,0.1
English Units
Geom File=g01
Flow File=f01
Plan File=p01
Y Axis Title=Elevation
X Axis Title(PF)=Main Channel Distance
X Axis Title(XS)=Station
BEGIN DESCRIPTION:
WHITE OAK CREEK NORTH
END DESCRIPTION:
DSS Export Rating Curves= 0
DSS Export Rating Curve Sorted= 0
DSS Export Volume Flow Curves= 0
DXF OffsetX= 0
DXF OffsetY= 0
DXF ScaleX= 1
DXF ScaleY= 10

--- WHITE OAK CREEK NORTH.p01 (plan) ---

Plan Title=Multiple Run
Short Identifier=Multiple
Geom File=g01
Flow File=f01
Subcritical Flow
K Sum by GR= 0
Std Step Tol= 0.01
Critical Tol= 0.01
Num of Std Step Trials= 20
Max Error Tol= 0.3
Flow Tol Ratio= 0.001
Split Flow NTrial= 30
Split Flow Tol= 0.02
Split Flow Ratio= 0.02
Log Output Level= 0
Friction Slope Method= 1
Unsteady Friction Slope Method= 2
Unsteady Bridges Friction Slope Method= 1
Parabolic Critical Depth
Global Vel Dist=  1 , 1 , 1
Global Log Level= 0
CheckData=True
Encroach Param= -1, 0, 0, 0
BEGIN DESCRIPTION:
Multiple Run
END DESCRIPTION:

--- WHITE OAK CREEK NORTH.f01 (steady flow) ---

Flow Title=Multiple
Program Version=4.10
Number of Profiles= 7
Profile Names=10-year,25-year,50-year,1pct_min,100-year,1pct_plu,500-year
River Rch & RM=WHITE OAK CREEK,Reach-1         ,31212
     311     404     531     231     698    2108    1240
River Rch & RM=WHITE OAK CREEK,Reach-1         ,29801
     943    1314    1810     821    2479    7486    4806
River Rch & RM=WHITE OAK CREEK,Reach-1         ,22561
    1256    1768    2452    1118    3375   10192    6612
River Rch & RM=WHITE OAK CREEK,Reach-1         ,16000
    3016    4407    6269    2920    8819   26633   18063
River Rch & RM=WHITE OAK CREEK,Reach-1         ,11000
    3247    4735    6725    3126    9441   28511   19255
River Rch & RM=WHITE OAK CREEK,Reach-1         ,7439
    3412    4987    7094    3303    9975   30124   20408
River Rch & RM=WHITE OAK CREEK,Reach-1         ,1880
    3428    5008    7123    3315   10011   30233   20466
Boundary for River Rch & Prof#=WHITE OAK CREEK,Reach-1         , 1
Up Type= 0
Dn Type= 3
Dn Slope=0.005
Boundary for River Rch & Prof#=WHITE OAK CREEK,Reach-1         , 2
Up Type= 0
Dn Type= 3
Dn Slope=0.005
Boundary for River Rch & Prof#=WHITE OAK CREEK,Reach-1         , 3
Up Type= 0
Dn Type= 3
Dn Slope=0.005
Boundary for River Rch & Prof#=WHITE OAK CREEK,Reach-1         , 4
Up Type= 0
Dn Type= 3
Dn Slope=0.005
Boundary for River Rch & Prof#=WHITE OAK CREEK,Reach-1         , 5
Up Type= 0
Dn Type= 3
Dn Slope=0.005
Boundary for River Rch & Prof#=WHITE OAK CREEK,Reach-1         , 6
Up Type= 0
Dn Type= 3
Dn Slope=0.005
Boundary for River Rch & Prof#=WHITE OAK CREEK,Reach-1         , 7
Up Type= 0
Dn Type= 3
Dn Slope=0.005
DSS Import GetInterval= 0
DSS Import GetPeak= 0
DSS Import FillOption= 0

--- WHITE OAK CREEK NORTH.g01 (geometry) ---

Geom Title=Existing Conditions
Program Version=4.10

River Reach=WHITE OAK CREEK ,Reach-1
Reach XY= 30
      3820301.46     10135552.96      3820615.04     10135201.28
      3821163.06     10135045.96      3821827.08      10133823.5
      3821548.12     10131170.29      3821968.16     10129425.81
      3821589.28     10128893.52      3821667.78     10127382.78
      3821288.04     10126965.87      3821044.45     10125683.56
      3820218.28     10125129.06      3819526.58     10125083.98
      3818992.96     10124459.42      3819118.17     10123064.93
      3818848.86     10122601.74      3818804.06     10121741.71
       3819407.5     10120919.96      3820451.56     10120060.69
      3820771.66     10119403.81      3820306.56     10117256.02
      3820670.15     10116314.13      3820504.18     10115713.66
      3820010.24       10115356.       3819816.5     10114138.46
      3819558.47     10113766.81      3818166.11     10113537.62
      3818053.71     10113072.82      3817557.02     10112678.52
      3817244.93     10112894.98      3816994.15     10112780.92

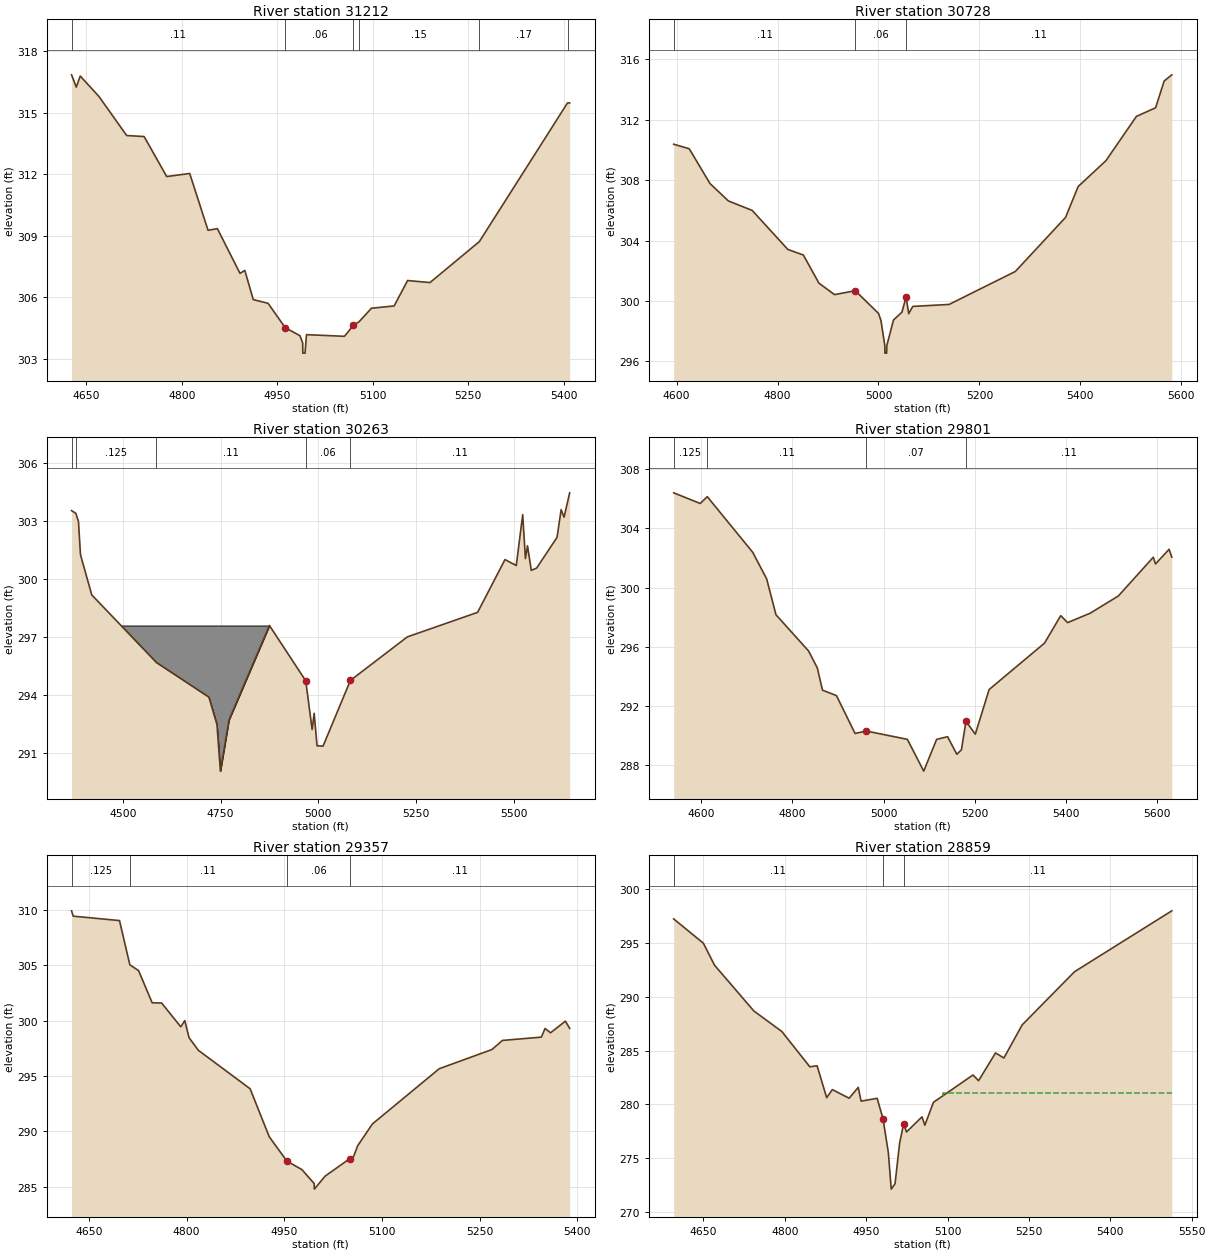
Type RM Length L Ch R = 1 ,31212   ,484,484,484
BEGIN DESCRIPTION:
WHITE OAK CREEK NORTH 63.0
END DESCRIPTION:
XS GIS Cut Line= 3
      3820617.87     10135661.09      3820398.17     10135359.54
      3820117.83     10135061.05
#Sta/Elev= 30
  4626.9  316.84  4634.3  316.24  4640.5  316.78  4669.8  315.79  4713.5  313.88
  4740.9  313.83  4776.4  311.88  4812.5  312.03  4841.3  309.26    4856  309.34
  4891.5  307.16  4899.1   307.3  4912.4  305.88  4935.6   305.7  4962.6  304.51
  4985.7  304.12    4990  303.77  4990.2  303.27  4993.7  303.27    4996  304.17
  5055.6  304.09  5069.8  304.63  5078.6   304.8  5098.1  305.46  5133.7  305.57
  5154.8  306.81    5190  306.71  5267.6  308.71  5406.1  315.47  5409.5  315.47
#Mann= 6 ,-1 , 0
  4626.9     .11       0  4962.6     .06       0  5069.8     .11       0
  5078.6     .15       0  5267.6     .17       0  5406.1     .11       0
Bank Sta=4962.6,5069.8
XS Rating Curve= 0 ,0
Exp/Cntr=0.3,0.1

Type RM Length L Ch R = 1 ,30728   ,465,465,465
BEGIN DESCRIPTION:
WHITE OAK CREEK NORTH 62.0
END DESCRIPTION:
XS GIS Cut Line= 3
      3820717.85     10135511.07      3820811.39      10135116.3
      3820267.84     10134911.07
#Sta/Elev= 30
  4594.3  310.37  4625.1  310.07  4666.2  307.77  4702.5  306.62  4749.8  305.99
  4820.4  303.41  4851.2  303.04    4882  301.18  4912.9  300.42    4954  300.68
    5000  299.18  5004.9  298.71  5012.5  297.05  5012.7  296.55  5016.2  296.55
  5016.5  297.05  5029.7  298.74  5046.5  299.26  5054.6  300.26  5059.9  299.16
  5067.9  299.64  5139.8  299.77    5271  301.95  5370.6  305.53  5395.5  307.57
  5450.5  309.28  5510.9  312.21  5548.9  312.78  5565.9  314.55    5581  314.96
#Mann= 3 , 0 , 0
  4594.3     .11       0    4954     .06       0  5054.6     .11       0
Bank Sta=4954,5054.6
XS Rating Curve= 0 ,0
Exp/Cntr=0.3,0.1

Type RM Length L Ch R = 1 ,30263   ,462,462,462
BEGIN DESCRIPTION:
WHITE OAK CREEK NORTH 61.0
END DESCRIPTION:
XS GIS Cut Line= 3
      3821817.84     10134811.07      3821207.02     10134969.77
      3820617.82     10134711.06
#Sta/Elev= 30
  4368.9  303.52  4379.9  303.38  4386.6  302.95  4391.7  301.24  4420.6  299.16
  4585.9  295.67  4720.2  293.88  4740.8  292.47  4749.8  290.05  4771.8   292.7
  4875.2  297.58  4968.1  294.72  4984.5   292.2  4989.6  293.04    4997  291.36
  5012.3  291.34  5082.4  294.74    5228  296.99  5407.9  298.26    5478  300.99
  5506.8  300.68  5523.3  303.31  5530.2  301.04  5535.6   301.7  5545.2  300.43
    5559  300.55  5611.2  302.14  5621.6  303.57  5629.1  303.18  5643.5  304.44
#Mann= 5 ,-1 , 0
  4368.9     .11       0  4379.9    .125       0  4585.9     .11       0
  4968.1     .06       0  5082.4     .11       0
#Block Obstruct= 2 , 0
       0  4875.2  297.58               0
Bank Sta=4968.1,5082.4
XS Rating Curve= 0 ,0
Exp/Cntr=0.3,0.1

Type RM Length L Ch R = 1 ,29801   ,444,444,444
BEGIN DESCRIPTION:
WHITE OAK CREEK NORTH 60.0
END DESCRIPTION:
XS GIS Cut Line= 3
      3821737.72     10134627.74      3821286.63      10134538.7
      3820662.05     10134631.98
#Sta/Elev= 30
  4540.2  306.41  4598.3  305.69  4613.8  306.15  4713.3  302.39  4743.9  300.59
  4764.3  298.16  4835.7  295.71  4854.8  294.57  4866.2  293.06  4896.8  292.69
  4937.6  290.13  4962.5  290.29  5052.2  289.73    5088  287.58  5116.3  289.73
  5140.3  289.91  5160.5  288.72  5170.6  289.02  5180.5  290.95    5201  290.08
  5231.3   293.1  5352.6  296.24  5388.2   298.1  5403.2  297.63  5452.4  298.26
  5514.4  299.43  5590.9  302.05  5595.9   301.6  5625.6  302.59  5631.5  302.06
#Mann= 4 ,-1 , 0
  4540.2    .125       0  4613.8     .11       0  4962.5     .07       0
  5180.5     .11       0
Bank Sta=4962.5,5180.5
XS Rating Curve= 0 ,0
Exp/Cntr=0.3,0.1

Type RM Length L Ch R = 1 ,29357   ,498,498,498
BEGIN DESCRIPTION:
WHITE OAK CREEK NORTH 59.0
END DESCRIPTION:
XS GIS Cut Line= 3
      3821785.46     10134536.58      3821562.81     10134232.85
      3821222.09     10134046.61
#Sta/Elev= 30
  4623.4   309.9  4625.9  309.42    4697  309.02  4712.9  305.03  4726.3  304.51
  4747.1  301.61  4761.8  301.58  4791.1  299.44  4797.3     300  4803.8  298.46
  4818.1  297.32  4897.6  293.85  4926.9  289.53    4954  287.33  4977.1  286.56
    4996   285.3  4996.2   284.8  5012.7  285.97  5050.7  287.55  5056.4  287.73
  5062.6   288.7  5085.4  290.68    5188  295.66  5268.9  297.39    5285  298.21
  5344.8  298.51  5350.5  299.29  5358.9   298.9  5381.7  299.95  5388.3   299.3
#Mann= 4 ,-1 , 0
  4623.4    .125       0  4712.9     .11       0    4954     .06       0
  5050.7     .11       0
Bank Sta=4954,5050.7
XS Rating Curve= 0 ,0
Exp/Cntr=0.3,0.1

Type RM Length L Ch R = 1 ,28859   ,498,498,498
BEGIN DESCRIPTION:
WHITE OAK CREEK NORTH 58.0
END DESCRIPTION:
XS GIS Cut Line= 3
      3822210.82     10133941.98      3821819.13     10133840.19
      3821325.43     10133981.03
#Sta/Elev= 30
  4595.3  297.25    4650  294.99  4670.7  292.94  4743.1  288.69  4794.7  286.78
  4846.3   283.5  4859.6   283.6  4877.3  280.63  4887.7  281.38  4918.7  280.58
  4935.5  281.59  4940.7  280.31  4970.3  280.57  4981.2  278.66    4991  275.51
  4996.3  272.13  5003.3  272.63  5011.7  276.39  5019.2  278.23  5024.4  277.44
    5053  278.85  5058.2  278.07  5074.1   280.2  5146.9  282.74  5157.3  282.21
  5188.5  284.79  5203.9  284.32  5237.7   287.4  5334.1  292.34  5513.4     298
#Mann= 3 , 0 , 0
  4595.3     .11       0  4981.2     .06       0  5019.2     .11       0
#XS Ineff= 2 , 0
       0  4935.5  281.59    5092       0  281.07
Permanent Ineff=
       F       F
Bank Sta=4981.2,5019.2
XS Rating Curve= 0 ,0
Exp/Cntr=0.3,0.1

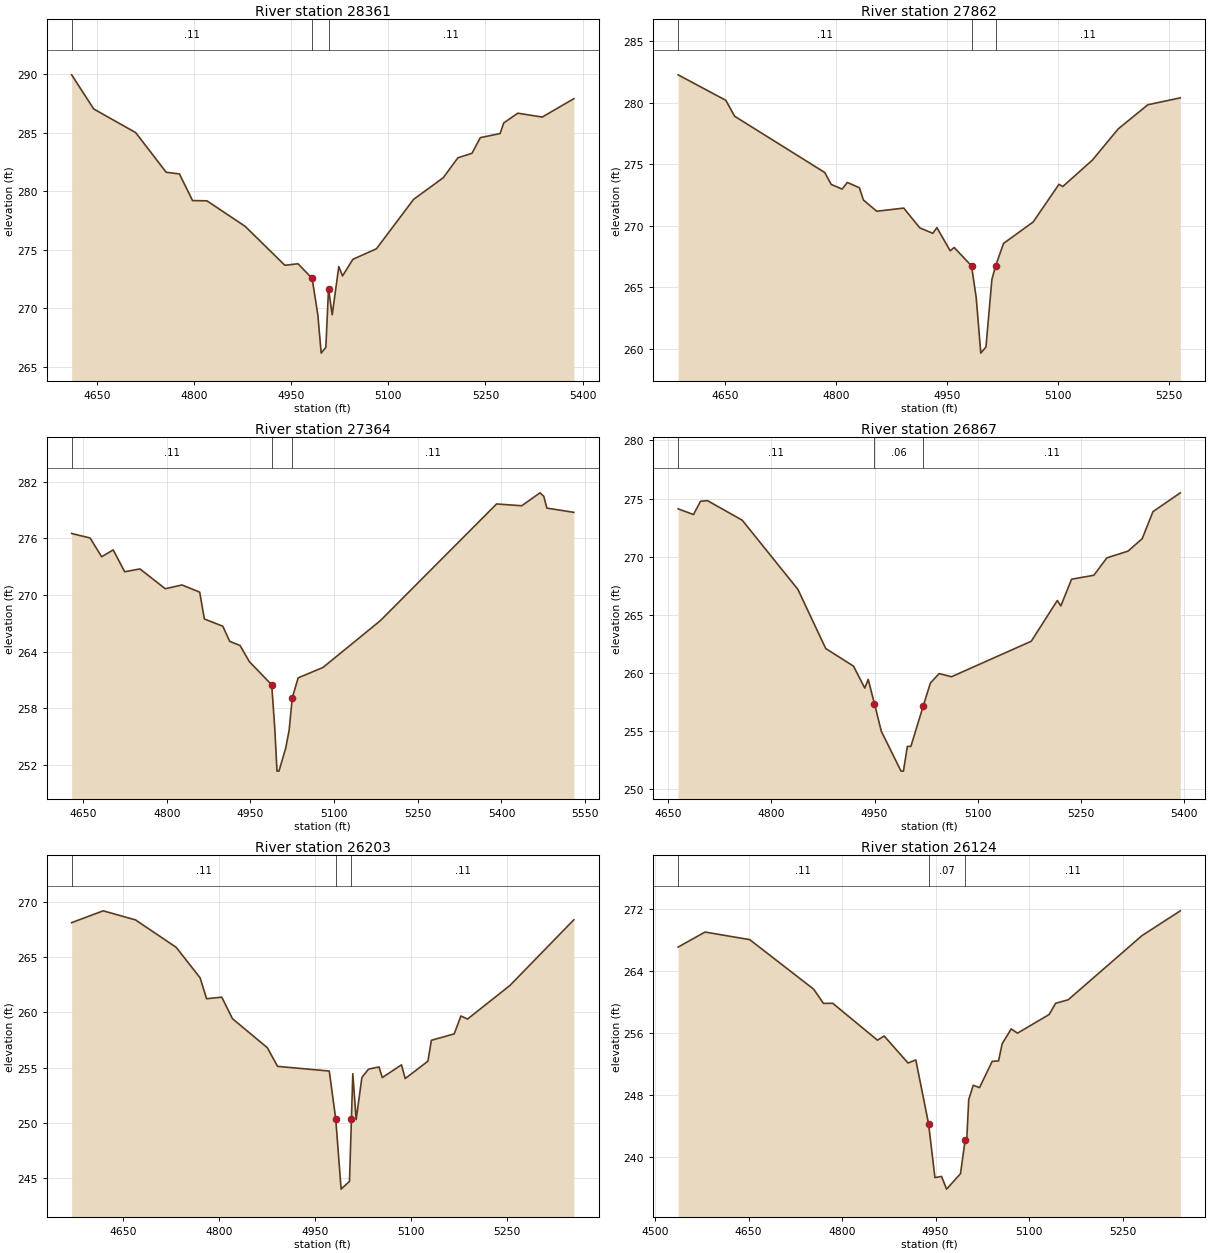
Type RM Length L Ch R = 1 ,28361   ,499,499,499
BEGIN DESCRIPTION:
WHITE OAK CREEK NORTH 57.0
END DESCRIPTION:
XS GIS Cut Line= 3
      3822141.33     10133434.16      3821759.16     10133362.12
      3821421.85     10133550.82
#Sta/Elev= 30
  4611.1  289.97  4645.2  287.05    4710  285.03  4757.1  281.64  4777.5   281.5
  4797.8  279.22    4820   279.2  4879.2  277.01  4940.3  273.69  4960.6  273.82
  4982.4  272.57  4991.2  269.47  4996.4  266.18  5003.6  266.68  5007.7  271.67
  5013.4  269.46  5023.6  273.58  5029.4  272.78  5045.3   274.2  5081.7   275.1
    5139  279.32  5184.8  281.17  5207.5  282.88  5229.2  283.26  5242.1   284.6
  5272.6  284.95  5278.3  285.86    5300  286.69  5337.7  286.36  5386.5  287.93
#Mann= 3 , 0 , 0
  4611.1     .11       0  4982.4     .06       0  5007.7     .11       0
Bank Sta=4982.4,5007.7
XS Rating Curve= 0 ,0
Exp/Cntr=0.3,0.1

Type RM Length L Ch R = 1 ,27862   ,498,498,498
BEGIN DESCRIPTION:
WHITE OAK CREEK NORTH 56.0
END DESCRIPTION:
XS GIS Cut Line= 3
        3822098.     10133043.55      3821718.27     10132879.13
      3821461.45     10132947.66
#Sta/Elev= 30
  4586.2  282.25  4650.8  280.18  4662.6  278.89  4784.6  274.32  4793.4  273.35
  4808.1  272.97  4815.2  273.51  4831.5  273.08    4837  272.08    4855  271.17
  4891.5  271.43  4913.3  269.82  4930.9  269.38  4936.4  269.84  4954.4  267.96
  4959.8  268.23  4983.3  266.73  4989.6  264.16  4995.8  259.65  5002.8  260.15
  5010.8  265.63  5015.9  266.74  5026.6  268.56  5066.7   270.3  5101.6  273.36
  5106.8  273.18  5146.9  275.33  5181.8  277.86  5221.9  279.82  5265.8  280.38
#Mann= 3 , 0 , 0
  4586.2     .11       0  4983.3     .06       0  5015.9     .11       0
#XS Ineff= 2 ,-1
  4936.4  4891.5  269.84  4959.8  4936.4  268.23
Permanent Ineff=
       T       T
Bank Sta=4983.3,5015.9
XS Rating Curve= 0 ,0
Exp/Cntr=0.3,0.1

Type RM Length L Ch R = 1 ,27364   ,497,497,497
BEGIN DESCRIPTION:
WHITE OAK CREEK NORTH 55.0
END DESCRIPTION:
XS GIS Cut Line= 3
      3822019.83     10132314.38      3821661.56     10132409.17
      3821429.83      10132885.6
#Sta/Elev= 30
  4629.4  276.52  4662.5  276.04  4683.2  274.05  4703.9  274.78  4724.5  272.46
  4751.9  272.76  4797.3  270.66  4827.2  271.06    4859   270.3  4867.4  267.45
  4900.4  266.69  4912.8  265.08  4931.4  264.64  4947.9  262.94  4988.1  260.47
  4993.5  255.95  4997.6  251.32  5001.1  251.32  5013.2  253.76  5019.4  255.67
  5024.9  259.07  5035.5  261.21    5080  262.31  5182.8  267.27  5391.3  279.65
  5436.4  279.46  5469.2  280.83  5475.9  280.46  5481.5  279.21  5529.8  278.76
#Mann= 3 , 0 , 0
  4629.4     .11       0  4988.1     .06       0  5024.9     .11       0
Bank Sta=4988.1,5024.9
XS Rating Curve= 0 ,0
Exp/Cntr=0.3,0.1

Type RM Length L Ch R = 1 ,26867   ,664,664,664
BEGIN DESCRIPTION:
WHITE OAK CREEK NORTH 54.0
END DESCRIPTION:
XS GIS Cut Line= 3
      3821920.03     10131975.84      3821588.23     10131926.84
      3821203.89     10132014.89
#Sta/Elev= 30
  4664.6  274.11    4687  273.62  4697.1  274.76  4707.2  274.82  4757.8  273.13
  4838.6  267.18  4879.1  262.08  4919.5  260.56  4935.8  258.67  4940.8  259.42
  4949.8  257.34  4959.9  254.95  4988.5  251.52    4992  251.52  4997.7  253.65
  5002.8  253.65  5020.9  257.16  5031.2  259.11  5043.9  259.92  5061.9  259.65
  5177.8  262.71  5215.6  266.22  5220.7  265.75  5236.3  268.05  5268.7  268.39
  5287.6  269.89  5318.4  270.47  5338.9  271.54  5354.6  273.87  5394.3  275.49
#Mann= 3 , 0 , 0
  4664.6     .11       0  4949.8     .06       0  5020.9     .11       0
#XS Ineff= 2 , 0
       0  4940.8  259.42               0
Permanent Ineff=
       F       F
Bank Sta=4949.8,5020.9
XS Rating Curve= 0 ,0
Exp/Cntr=0.3,0.1

Type RM Length L Ch R = 1 ,26203   ,79,79,79
BEGIN DESCRIPTION:
WHITE OAK CREEK NORTH 53.0
END DESCRIPTION:
XS GIS Cut Line= 3
      3821986.67     10131213.63      3821560.55     10131273.49
      3821216.79     10131360.91
#Sta/Elev= 30
  4569.7  268.11    4619  269.18  4669.5  268.36  4733.1  265.88  4770.5  263.12
  4780.6  261.23  4804.4  261.37    4821  259.43  4875.6   256.8  4891.6  255.11
  4972.4  254.69  4982.5  250.36  4990.9  244.01    5004  244.71 5007.04  250.38
  5009.2  254.45  5014.4   250.3  5023.4  254.11  5033.7  254.86  5050.1  255.06
  5055.3   254.1  5085.3  255.25  5091.1  254.01  5126.6  255.58    5132  257.47
  5167.7  258.05  5178.2  259.67  5188.5  259.39  5254.8  262.43  5354.7  268.37
#Mann= 3 , 0 , 0
  4569.7     .11       0  4982.5     .07       0 5007.04     .11       0
#XS Ineff= 2 , 0
       0                  5009.2       0  254.45
Permanent Ineff=
       F       F
Bank Sta=4982.5,5007.04
XS Rating Curve= 0 ,0
Exp/Cntr=0.3,0.1

Type RM Length L Ch R = 1 ,26124   ,569,569,569
BEGIN DESCRIPTION:
WHITE OAK CREEK NORTH 52.0
END DESCRIPTION:
XS GIS Cut Line= 3
      3822000.02     10131095.36      3821548.06     10131195.86
      3821210.92     10131256.79
#Sta/Elev= 30
    4537  267.14  4580.2  269.08  4651.9   268.1  4754.4  261.71  4770.2  259.87
  4785.1  259.88  4856.8  255.12  4867.5  255.66  4905.9  252.17  4918.3  252.57
  4938.7  244.36    4949  237.38  4959.6  237.53  4967.7  235.89    4990  237.89
  4997.5  242.26    5000  242.26  5003.2  247.45  5010.4   249.3  5020.5     249
  5040.9  252.39    5051  252.44  5056.8  254.65  5071.3  256.57  5081.5  256.03
  5132.3  258.44  5142.5  259.88  5162.8  260.34    5281  268.61  5342.6  271.82
#Mann= 3 , 0 , 0
    4537     .11       0  4938.7     .07       0  4997.5     .11       0
Bank Sta=4938.7,4997.5
XS Rating Curve= 0 ,0
Exp/Cntr=0.3,0.1

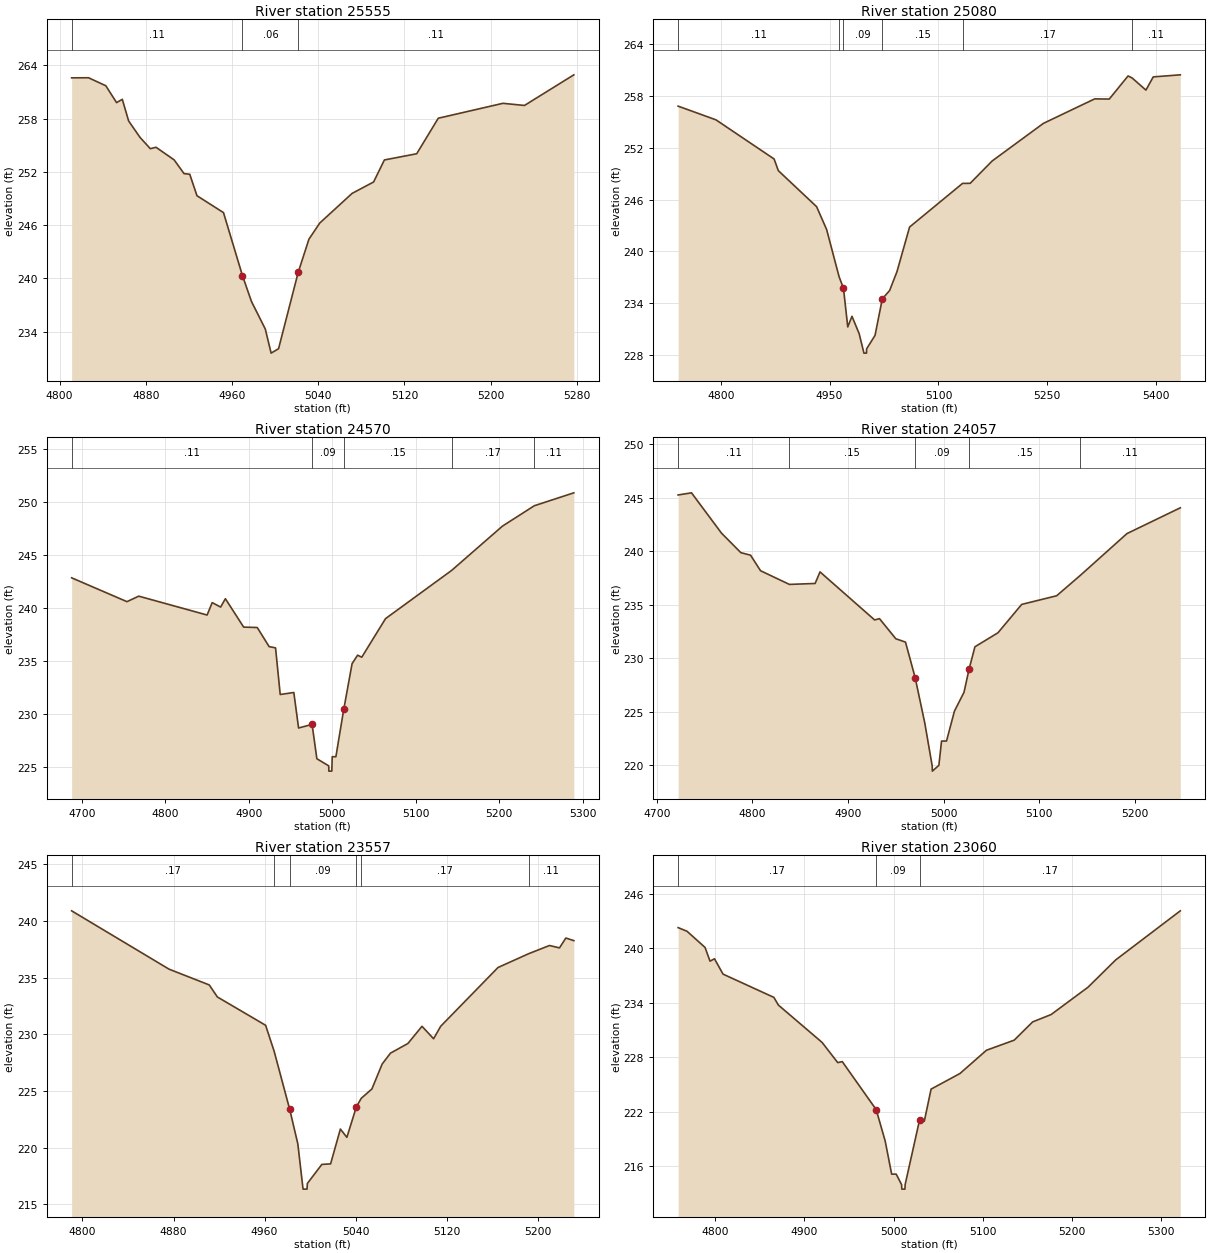
Type RM Length L Ch R = 1 ,25555   ,475,475,475
BEGIN DESCRIPTION:
WHITE OAK CREEK NORTH 51.0
END DESCRIPTION:
XS GIS Cut Line= 3
      3821867.86     10130761.08      3821689.23     10130699.96
      3821412.09     10130705.84
#Sta/Elev= 30
  4811.2  262.59  4826.9   262.6  4842.9   261.7  4852.9   259.8  4858.2  260.17
  4864.1  257.73  4874.6  255.89  4884.2  254.61  4889.5  254.77  4906.3  253.35
  4915.5   251.8  4920.8  251.73  4927.5  249.31  4952.1  247.41  4969.7  240.31
  4978.1  237.39  4990.9  234.29  4996.3  231.58  5003.2  232.08  5021.4  240.67
  5031.4  244.42  5041.4  246.23  5071.4  249.57  5091.4  250.86  5101.4  253.34
  5131.4  254.04  5151.4  258.04  5211.4  259.72  5231.4  259.48  5277.2  262.93
#Mann= 3 , 0 , 0
  4811.2     .11       0  4969.7     .06       0  5021.4     .11       0
Bank Sta=4969.7,5021.4
XS Rating Curve= 0 ,0
Exp/Cntr=0.3,0.1

Type RM Length L Ch R = 1 ,25080   ,510,510,510
BEGIN DESCRIPTION:
WHITE OAK CREEK NORTH 50.0
END DESCRIPTION:
XS GIS Cut Line= 3
       3821911.4     10130497.54      3821780.29      10130274.4
      3821350.88     10130216.54
#Sta/Elev= 30
  4741.2  256.83  4793.4  255.24  4873.5   250.7  4879.3  249.35  4932.1  245.17
  4945.9  242.52    4963  237.06  4969.1  235.71    4975  231.23  4980.8  232.46
  4990.7  230.45  4997.3  228.19  5000.8  228.19    5001  228.69  5012.6  230.25
  5022.6  234.48  5032.7  235.45  5042.8  237.63  5060.2  242.81  5133.2  247.87
  5143.7  247.88    5174  250.47  5244.6  254.83  5315.3  257.67  5335.4  257.65
  5361.3  260.33    5367  260.09  5385.9  258.69    5396  260.22  5433.3  260.46
#Mann= 6 ,-1 , 0
  4741.2     .11       0    4963     .15       0  4969.1     .09       0
  5022.6     .15       0  5133.2     .17       0    5367     .11       0
Bank Sta=4969.1,5022.6
XS Rating Curve= 0 ,0
Exp/Cntr=0.3,0.1

Type RM Length L Ch R = 1 ,24570   ,513,513,513
BEGIN DESCRIPTION:
WHITE OAK CREEK NORTH 49.0
END DESCRIPTION:
XS GIS Cut Line= 3
      3821989.53     10130169.42      3821841.62     10129894.48
      3821552.48     10129908.95
#Sta/Elev= 30
  4687.8  242.87  4754.1  240.62  4768.2  241.14  4850.1  239.36  4856.2  240.53
  4866.3  240.11    4872   240.9  4893.9  238.22  4910.2  238.18  4924.4  236.38
  4932.1  236.26  4937.7  231.86    4954  232.05  4959.7   228.7  4975.9  229.04
  4981.6   225.8  4995.8  225.13    4996  224.63  4999.5  224.63    5000  225.99
  5004.4  225.99  5013.8  230.45  5023.8  234.77  5030.4  235.57  5035.4  235.38
  5063.9  239.02  5143.1  243.57    5204  247.75  5242.1  249.67  5289.5  250.89
#Mann= 5 ,-1 , 0
  4687.8     .11       0  4975.9     .09       0  5013.8     .15       0
  5143.1     .17       0  5242.1     .11       0
Bank Sta=4975.9,5013.8
XS Rating Curve= 0 ,0
Exp/Cntr=0.3,0.1

Type RM Length L Ch R = 1 ,24057   ,500,500,500
BEGIN DESCRIPTION:
WHITE OAK CREEK NORTH 48.0
END DESCRIPTION:
XS GIS Cut Line= 3
      3822232.68     10129463.25      3821958.44     10129506.93
       3821726.9     10129594.37
#Sta/Elev= 30
  4722.3  245.24  4736.3  245.44  4767.7  241.67  4787.9  239.85  4798.1  239.61
  4808.5  238.16  4838.7  236.88  4865.6  236.97  4870.7  238.05  4927.8  233.56
  4932.9  233.68    4950   231.8  4960.1  231.49  4970.2  228.17  4980.3  223.91
    4988  219.93  4988.2  219.43    4995  219.97  4997.8  222.24    5003  222.24
  5011.3  225.04  5021.3   226.8  5026.6  228.96  5032.7  231.05  5056.8  232.36
  5081.6  235.01  5118.2  235.82    5143  237.73  5191.7  241.63  5247.5  244.04
#Mann= 5 ,-1 , 0
  4722.3     .11       0  4838.7     .15       0  4970.2     .09       0
  5026.6     .15       0    5143     .11       0
Bank Sta=4970.2,5026.6
XS Rating Curve= 0 ,0
Exp/Cntr=0.3,0.1

Type RM Length L Ch R = 1 ,23557   ,497,497,497
BEGIN DESCRIPTION:
WHITE OAK CREEK NORTH 47.0
END DESCRIPTION:
XS GIS Cut Line= 3
       3821893.6     10129005.81      3821746.66     10129155.14
      3821638.38     10129359.98
#Sta/Elev= 30
  4790.5  240.89  4876.1  235.74  4911.4  234.35  4918.5  233.29  4960.9  230.79
  4968.4   228.5  4982.1  223.36  4989.2  220.33  4993.8  216.33  4997.3  216.33
  4997.6  216.83  5010.3  218.51    5018  218.56  5026.6  221.63  5032.3   220.9
  5040.6  223.58  5044.9  224.34  5054.3  225.17  5063.3  227.37  5070.6  228.33
  5085.9  229.18  5098.3   230.7  5108.5   229.6  5114.7   230.7  5165.1  235.89
  5192.1  237.11  5210.3  237.83  5219.1  237.62  5224.7  238.49  5231.7  238.26
#Mann= 6 ,-1 , 0
  4790.5     .17       0  4968.4     .15       0  4982.1     .09       0
  5040.6     .15       0  5044.9     .17       0  5192.1     .11       0
#XS Ineff= 2 , 0
       0                  5098.3       0   230.7
Permanent Ineff=
       F       F
Bank Sta=4982.1,5040.6
XS Rating Curve= 0 ,0
Exp/Cntr=0.3,0.1

Type RM Length L Ch R = 1 ,23060   ,499,499,499
BEGIN DESCRIPTION:
WHITE OAK CREEK NORTH 46.0
END DESCRIPTION:
XS GIS Cut Line= 3
       3821817.8     10128811.07      3821578.41     10128777.77
      3821267.88     10128861.06
#Sta/Elev= 30
  4758.3  242.29  4768.3  241.89  4788.5  240.11  4794.1   238.6  4799.1  238.86
  4808.7  237.17  4865.7  234.61  4870.8  233.76  4919.8  229.65  4937.3  227.43
  4942.4  227.54  4980.4  222.26  4990.5  218.81  4997.8  215.15  5002.9  215.15
  5008.9     214  5009.2   213.5  5012.7   213.5  5012.9     214  5029.2  221.16
  5034.4  220.97    5042  224.51  5074.4  226.23  5104.1  228.79  5135.2   229.9
  5155.9  231.91  5176.6  232.72    5218  235.73  5249.1  238.74  5321.5  244.14
#Mann= 3 , 0 , 0
  4758.3     .17       0  4980.4     .09       0  5029.2     .17       0
Bank Sta=4980.4,5029.2
XS Rating Curve= 0 ,0
Exp/Cntr=0.3,0.1

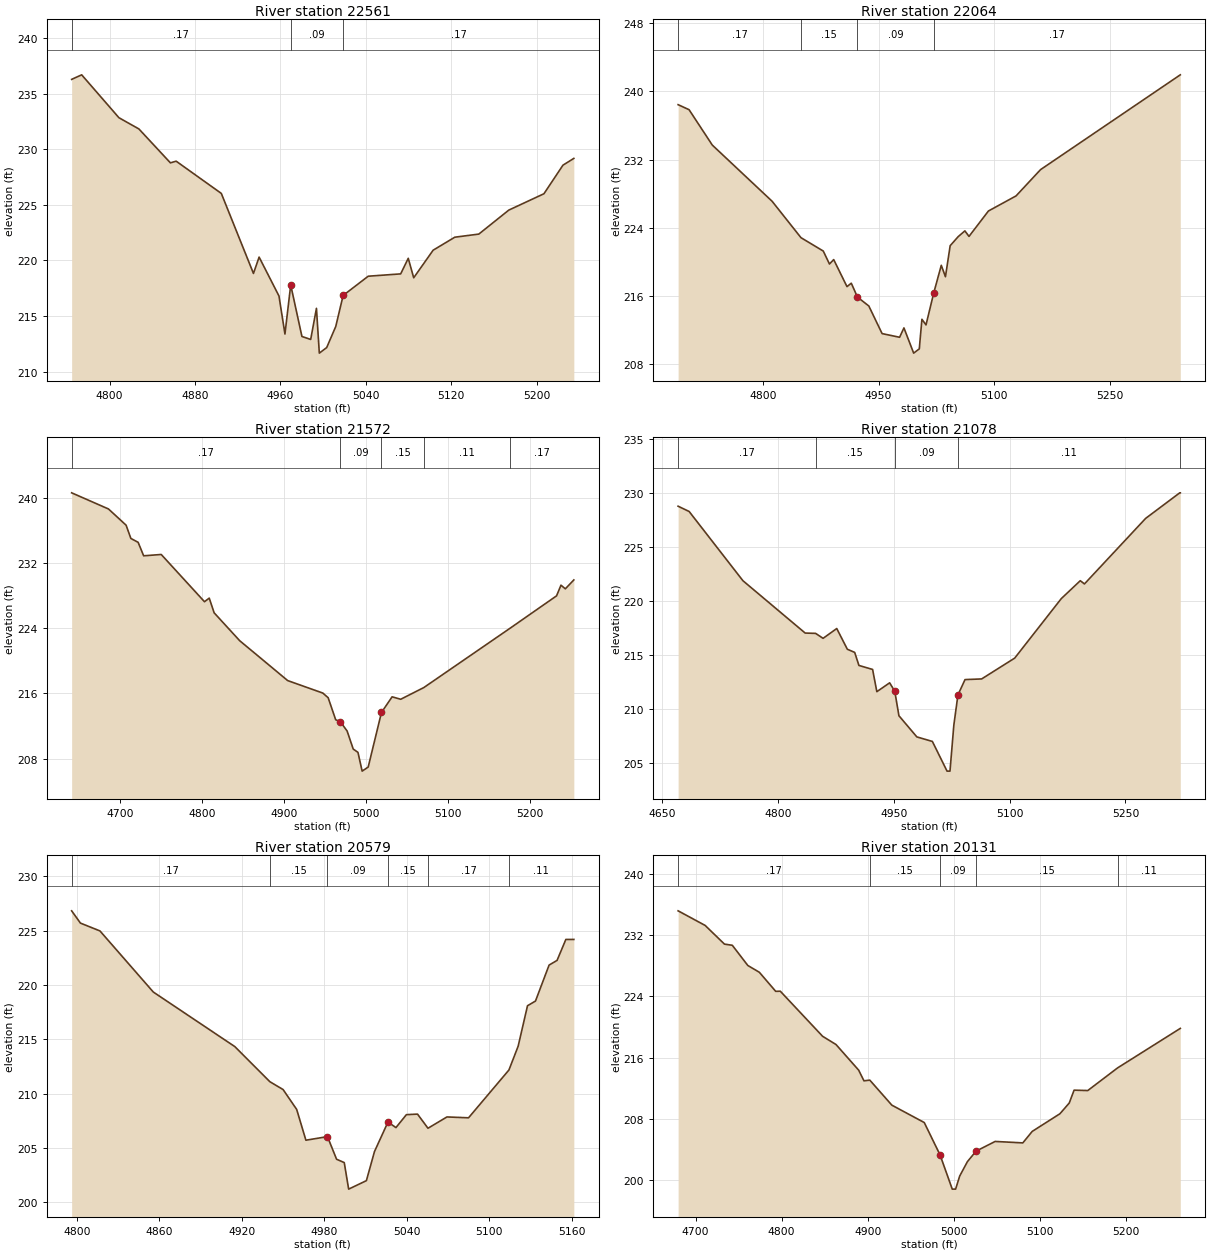
Type RM Length L Ch R = 1 ,22561   ,497,497,497
BEGIN DESCRIPTION:
WHITE OAK CREEK NORTH 45.0
END DESCRIPTION:
XS GIS Cut Line= 3
      3821917.85     10128311.07      3821699.45     10128399.43
       3821467.8     10128361.06
#Sta/Elev= 30
  4764.4  236.29  4773.8   236.7  4808.7  232.84  4827.4  231.83  4856.9  228.78
  4862.3  228.93  4904.6  226.03  4934.7  218.83    4940   220.3  4958.6   216.8
  4964.2  213.38  4969.6  217.79  4980.1  213.16  4988.3  212.89  4993.7  215.69
  4996.4  211.66  5003.3  212.16  5011.8  214.06  5018.7  216.85  5042.2  218.58
  5072.6  218.79  5079.7  220.19  5084.8  218.44    5103  220.92  5123.3  222.09
  5145.8  222.37  5173.9  224.53  5206.8     226  5224.6  228.57  5234.8  229.18
#Mann= 3 , 0 , 0
  4764.4     .17       0  4969.6     .09       0  5018.7     .17       0
Bank Sta=4969.6,5018.7
XS Rating Curve= 0 ,0
Exp/Cntr=0.3,0.1

Type RM Length L Ch R = 1 ,22064   ,492,492,492
BEGIN DESCRIPTION:
WHITE OAK CREEK NORTH 44.0
END DESCRIPTION:
XS GIS Cut Line= 3
      3821917.87     10127861.06      3821637.92     10127993.75
      3821317.85     10128111.07
#Sta/Elev= 30
  4690.2  238.45  4704.4  237.86  4734.5  233.71    4812  227.12  4849.4  222.85
  4878.3  221.28  4886.3  219.76  4891.8  220.28    4909  217.11  4914.6  217.51
  4922.6  215.88  4937.3  214.84  4954.5   211.6  4977.2  211.17  4982.8  212.27
  4995.4  209.31  5002.7  209.81  5006.1  213.28  5011.4  212.62  5021.4  216.36
  5031.2  219.61  5036.6  218.27  5042.7  221.91  5053.3  222.99  5061.8  223.65
  5067.1     223  5092.3  225.98  5128.1  227.75  5159.8  230.83  5340.9  241.95
#Mann= 4 ,-1 , 0
  4690.2     .17       0  4849.4     .15       0  4922.6     .09       0
  5021.4     .17       0
Bank Sta=4922.6,5021.4
XS Rating Curve= 0 ,0
Exp/Cntr=0.3,0.1

Type RM Length L Ch R = 1 ,21572   ,494,494,494
BEGIN DESCRIPTION:
WHITE OAK CREEK NORTH 43.0
END DESCRIPTION:
XS GIS Cut Line= 3
      3821967.88     10127711.09      3821658.01     10127529.02
      3821417.84     10127611.07
#Sta/Elev= 30
  4640.6   240.6  4685.6  238.62  4707.1  236.63  4712.9  235.01  4721.8  234.53
  4728.5  232.88    4750  233.04  4802.8  227.25  4808.6  227.69  4814.6  225.89
  4845.8  222.47  4904.4  217.58  4947.3  216.05  4953.8  215.48    4963  212.78
  4968.8  212.53    4977  211.39  4984.4  209.19  4990.2  208.78  4995.3  206.48
  5002.7  206.98  5018.9  213.67  5031.9  215.59  5042.4  215.29  5070.7  216.73
  5176.4  224.03  5232.7  227.97  5238.1  229.28  5243.4  228.83  5253.8  229.92
#Mann= 5 ,-1 , 0
  4640.6     .17       0  4968.8     .09       0  5018.9     .15       0
  5070.7     .11       0  5176.4     .17       0
Bank Sta=4968.8,5018.9
XS Rating Curve= 0 ,0
Exp/Cntr=0.3,0.1

Type RM Length L Ch R = 1 ,21078   ,499,499,499
BEGIN DESCRIPTION:
WHITE OAK CREEK NORTH 42.0
END DESCRIPTION:
XS GIS Cut Line= 3
      3821617.85     10126861.08       3821483.4     10127161.58
      3821367.86     10127461.06
#Sta/Elev= 30
  4670.8  228.76  4685.1  228.27  4754.7  221.86  4835.3  217.01  4848.8  216.98
  4858.5  216.52  4876.2  217.43  4889.9  215.51  4899.4  215.22  4904.9  214.01
  4922.6  213.64  4928.1  211.58  4944.7   212.4  4951.3  211.62  4956.7  209.35
  4979.9  207.39    5000  206.97    5019  204.22  5022.8  204.22  5027.8  208.49
  5033.1  211.28  5042.3   212.7  5063.8  212.76  5106.6  214.69  5166.9   220.2
  5191.5  221.86  5196.9  221.56  5276.1  227.63  5320.3     230    5321     230
#Mann= 5 ,-1 , 0
  4670.8     .17       0  4848.8     .15       0  4951.3     .09       0
  5033.1     .11       0  5320.3     .17       0
Bank Sta=4951.3,5033.1
XS Rating Curve= 0 ,0
Exp/Cntr=0.3,0.1

Type RM Length L Ch R = 1 ,20579   ,448,448,448
BEGIN DESCRIPTION:
WHITE OAK CREEK NORTH 41.0
END DESCRIPTION:
XS GIS Cut Line= 3
      3821453.56     10126697.94      3821272.02     10126790.77
      3821132.92     10126872.63
#Sta/Elev= 30
  4796.1  226.81  4802.5  225.68  4816.7  224.96  4855.5  219.34  4914.8  214.32
  4940.3  211.09  4949.9  210.37  4959.8  208.54  4966.5  205.71  4982.2  206.04
  4988.8  203.96  4994.4  203.65  4997.6  201.21  5010.5  201.99  5016.4  204.67
  5026.2  207.38    5032  206.87  5039.6  208.06  5047.7  208.11  5055.3  206.81
  5069.1  207.85  5084.8  207.77  5114.2  212.17  5120.9  214.36  5127.7  218.08
  5133.5  218.51  5143.4  221.82  5149.2  222.25  5155.6  224.18  5161.4  224.18
#Mann= 6 ,-1 , 0
  4796.1     .17       0  4940.3     .15       0  4982.2     .09       0
  5026.2     .15       0  5055.3     .17       0  5114.2     .11       0
Bank Sta=4982.2,5026.2
XS Rating Curve= 0 ,0
Exp/Cntr=0.3,0.1

Type RM Length L Ch R = 1 ,20131   ,492,492,492
BEGIN DESCRIPTION:
WHITE OAK CREEK NORTH 40.0
END DESCRIPTION:
XS GIS Cut Line= 3
      3821467.82     10126461.06      3821162.37     10126364.98
      3820917.88     10126461.06
#Sta/Elev= 30
  4679.8  235.17  4711.2  233.26  4733.6  230.82  4742.7  230.67  4760.7  228.03
  4774.1  227.14  4793.1  224.65  4798.4  224.67  4847.5  218.78  4863.1   217.7
  4889.4  214.35  4895.5  212.96  4902.3  213.05  4927.9  209.78  4965.5  207.51
  4983.8  203.29    4998  198.81  5001.9  198.81  5006.6  200.51  5015.6   202.4
  5025.6  203.77  5047.8  205.04  5079.9  204.85  5090.8  206.35    5123  208.66
  5133.8  210.06  5139.4  211.74  5155.3  211.69  5189.8  214.64  5262.7  219.81
#Mann= 5 ,-1 , 0
  4679.8     .17       0  4902.3     .15       0  4983.8     .09       0
  5025.6     .15       0  5189.8     .11       0
Bank Sta=4983.8,5025.6
XS Rating Curve= 0 ,0
Exp/Cntr=0.3,0.1

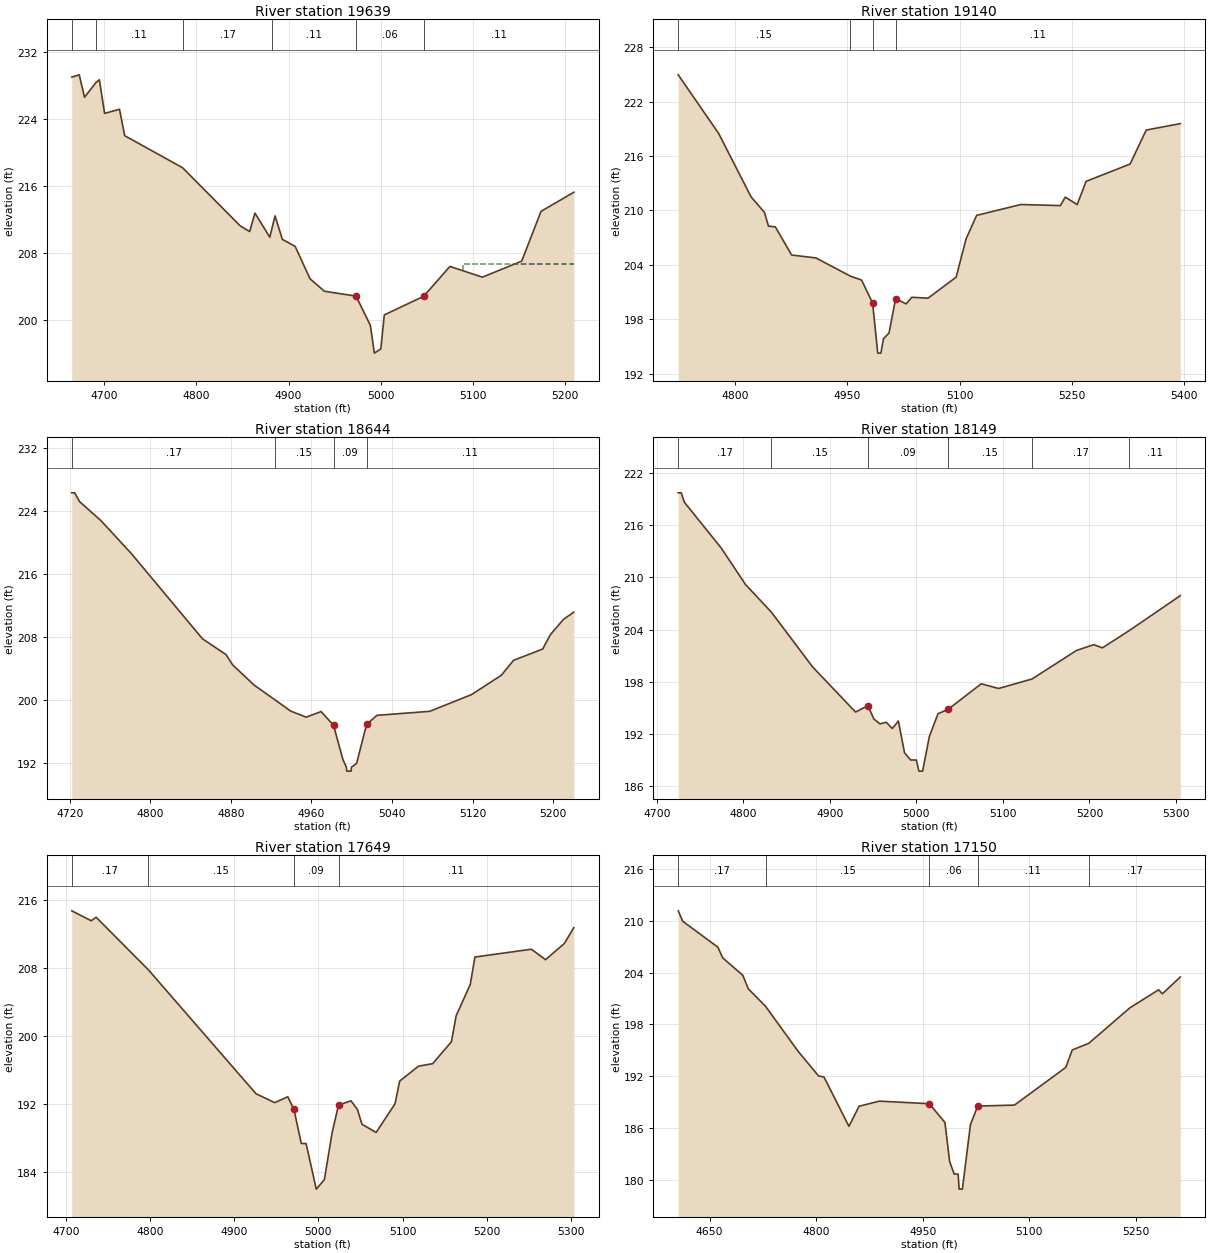
Type RM Length L Ch R = 1 ,19639   ,499,499,499
BEGIN DESCRIPTION:
WHITE OAK CREEK NORTH 39.0
END DESCRIPTION:
XS GIS Cut Line= 3
      3821367.87     10125761.06      3821074.32     10125922.27
      3820917.82      10126061.1
#Sta/Elev= 30
  4665.1  228.99  4673.2  229.26  4678.9  226.59  4691.5  228.36    4695  228.67
  4700.7  224.66  4716.8  225.15  4722.5     222  4785.2  218.18  4847.7  211.24
  4857.9  210.57  4863.6  212.77  4879.7   209.9  4882.4   211.1  4885.4  212.44
  4893.3  209.64  4907.2   208.8  4923.3  204.94  4938.9  203.45  4973.2  202.87
  4988.7  199.38    4993  196.07    5000  196.57  5003.8  200.63  5046.5  202.85
  5074.9  206.41  5110.1  205.13  5152.7  207.04  5173.6  212.97  5209.2  215.26
#Mann= 6 ,-1 , 0
  4665.1     .17       0  4691.5     .11       0  4785.2     .17       0
  4882.4     .11       0  4973.2     .06       0  5046.5     .11       0
#XS Ineff= 2 , 0
       0                  5088.9       0  206.66
Permanent Ineff=
       F       F
Bank Sta=4973.2,5046.5
XS Rating Curve= 0 ,0
Exp/Cntr=0.3,0.1

Type RM Length L Ch R = 1 ,19140   ,496,496,496
BEGIN DESCRIPTION:
WHITE OAK CREEK NORTH 38.0
END DESCRIPTION:
XS GIS Cut Line= 3
      3820967.86     10125311.06      3820861.47     10125566.16
      3820667.87     10125911.04
#Sta/Elev= 30
  4723.6  224.95  4777.8  218.47  4821.1  211.49    4839  209.78  4844.4  208.26
  4853.6  208.18  4875.3  205.08  4907.8  204.76    4954  202.75  4968.9  202.32
  4983.7   199.8  4990.6  194.26  4994.8  194.26  4998.2  195.84  5005.7  196.48
  5014.5  200.26  5028.6  199.69  5036.2  200.42  5057.9  200.32  5095.5  202.64
  5108.8  206.85  5122.9  209.45  5182.2  210.65    5235  210.53  5241.5  211.46
  5257.5  210.64  5269.4   213.2  5328.3  215.11  5349.9  218.86  5395.5  219.57
#Mann= 4 ,-1 , 0
  4723.6     .15       0    4954     .11       0  4983.7     .07       0
  5014.5     .11       0
Bank Sta=4983.7,5014.5
XS Rating Curve= 0 ,0
Exp/Cntr=0.3,0.1

Type RM Length L Ch R = 1 ,18644   ,495,495,495
BEGIN DESCRIPTION:
WHITE OAK CREEK NORTH 37.0
END DESCRIPTION:
XS GIS Cut Line= 3
      3820667.85     10125111.07      3820520.34     10125346.83
      3820467.85     10125561.09
#Sta/Elev= 30
  4721.9  226.27  4724.8  226.27  4729.6  225.16  4750.8  222.75  4780.9  218.59
  4851.7  207.75  4875.2  205.73  4881.6  204.45  4902.9  201.88  4923.8  199.99
  4939.4  198.57  4954.7   197.8  4969.6  198.51  4981.9  196.77  4991.3  192.39
  4994.7  191.45    4995  190.95  4999.3  190.95  4999.7  191.45  5004.8  191.92
  5014.7  196.87    5025  198.03  5077.5  198.54  5119.1  200.67  5148.5  203.11
  5160.7  205.01  5189.7  206.45  5197.2  208.25  5210.3  210.21  5220.6  211.13
#Mann= 4 ,-1 , 0
  4721.9     .17       0  4923.8     .15       0  4981.9     .09       0
  5014.7     .11       0
Bank Sta=4981.9,5014.7
XS Rating Curve= 0 ,0
Exp/Cntr=0.3,0.1

Type RM Length L Ch R = 1 ,18149   ,500,500,500
BEGIN DESCRIPTION:
WHITE OAK CREEK NORTH 36.0
END DESCRIPTION:
XS GIS Cut Line= 3
      3820317.83     10124911.09      3820123.46     10125106.05
      3820117.85      10125411.1
#Sta/Elev= 30
  4724.7  219.72  4728.2  219.72  4731.7  218.65  4774.2   213.4  4802.5  209.18
  4832.5  205.99  4880.2  199.69  4929.7  194.52  4943.9  195.25  4950.9  193.72
    4958  193.16  4965.1  193.35  4972.2  192.63  4979.2  193.49  4986.3  189.84
  4993.3  189.01    5000  189.01  5002.9  187.73  5007.2  187.73    5015  191.71
    5025  194.33  5036.5  194.82    5075  197.77    5095  197.23  5133.7  198.32
  5185.1   201.6  5205.1  202.27  5215.1   201.9  5246.3   203.9  5305.1   207.9
#Mann= 6 ,-1 , 0
  4724.7     .17       0  4832.5     .15       0  4943.9     .09       0
  5036.5     .15       0  5133.7     .17       0  5246.3     .11       0
#XS Ineff= 2 , 0
       0                    5075       0  197.77
Permanent Ineff=
       F       F
Bank Sta=4943.9,5036.5
XS Rating Curve= 0 ,0
Exp/Cntr=0.3,0.1

Type RM Length L Ch R = 1 ,17649   ,499,499,499
BEGIN DESCRIPTION:
WHITE OAK CREEK NORTH 35.0
END DESCRIPTION:
XS GIS Cut Line= 3
      3819826.71     10124820.41      3819684.42     10125076.43
      3819548.57     10125347.72
#Sta/Elev= 30
  4707.1  214.72  4730.3  213.55    4736  213.97  4798.1  207.79  4925.9  193.23
  4948.1  192.18  4963.7  192.87    4971  191.38  4979.7  187.39  4985.4  187.37
  4997.5  182.02  5007.1  183.13  5016.4   188.7  5023.9  191.89  5038.7   192.4
  5046.3  191.39  5051.8  189.64  5068.6  188.68    5091  192.04  5096.5  194.71
  5118.9  196.47  5135.7  196.76    5158  199.33  5163.6  202.38  5180.4  206.07
  5185.9  209.29    5253  210.21  5269.8  208.98  5292.1  210.88  5303.4  212.74
#Mann= 4 ,-1 , 0
  4707.1     .17       0  4798.1     .15       0    4971     .09       0
  5023.9     .11       0
Bank Sta=4971,5023.9
XS Rating Curve= 0 ,0
Exp/Cntr=0.3,0.1

Type RM Length L Ch R = 1 ,17150   ,497,497,497
BEGIN DESCRIPTION:
WHITE OAK CREEK NORTH 34.0
END DESCRIPTION:
XS GIS Cut Line= 3
      3819558.58      10124563.2      3819304.59     10124864.67
      3819001.74     10124943.33
#Sta/Elev= 30
  4605.8  211.17  4612.1  209.96  4661.6  206.96  4668.4  205.72  4696.7   203.7
  4704.4  202.14    4729  200.08  4774.7  194.88  4803.3  192.04  4811.1   191.9
  4846.2  186.19  4860.5  188.52  4889.1  189.11  4959.4  188.81  4981.4  186.64
    4988  182.13  4994.4  180.66    5000  180.66  5001.4  178.91    5006  178.91
  5017.3  186.38  5027.6  188.54  5079.3  188.65  5151.6  193.02  5160.7  195.04
    5184  195.81  5241.8  199.92  5282.4  202.02  5287.6  201.55  5312.9   203.5
#Mann= 5 ,-1 , 0
  4605.8     .17       0    4729     .15       0  4959.4     .06       0
  5027.6     .11       0    5184     .17       0
Bank Sta=4959.4,5027.6
XS Rating Curve= 0 ,0
Exp/Cntr=0.3,0.1