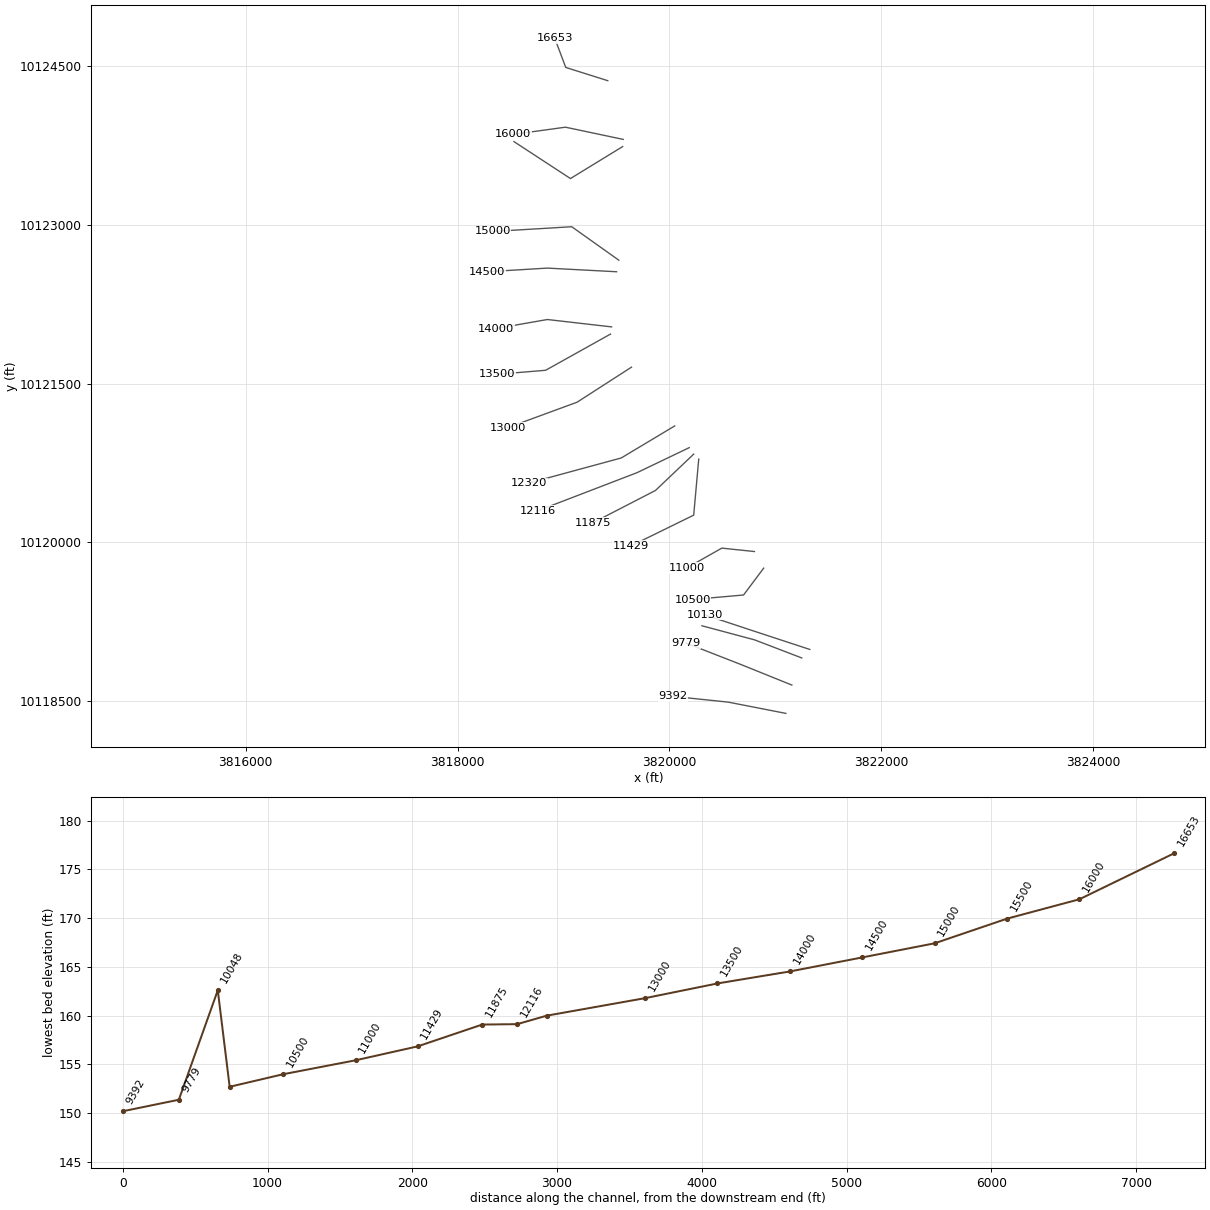
HEC-RAS study WHITE OAK CREEK NORTH.prj: WHITE OAK CREEK NORTH Base Level Engineering

--- WHITE OAK CREEK NORTH.g01 (geometry) --- (continued)

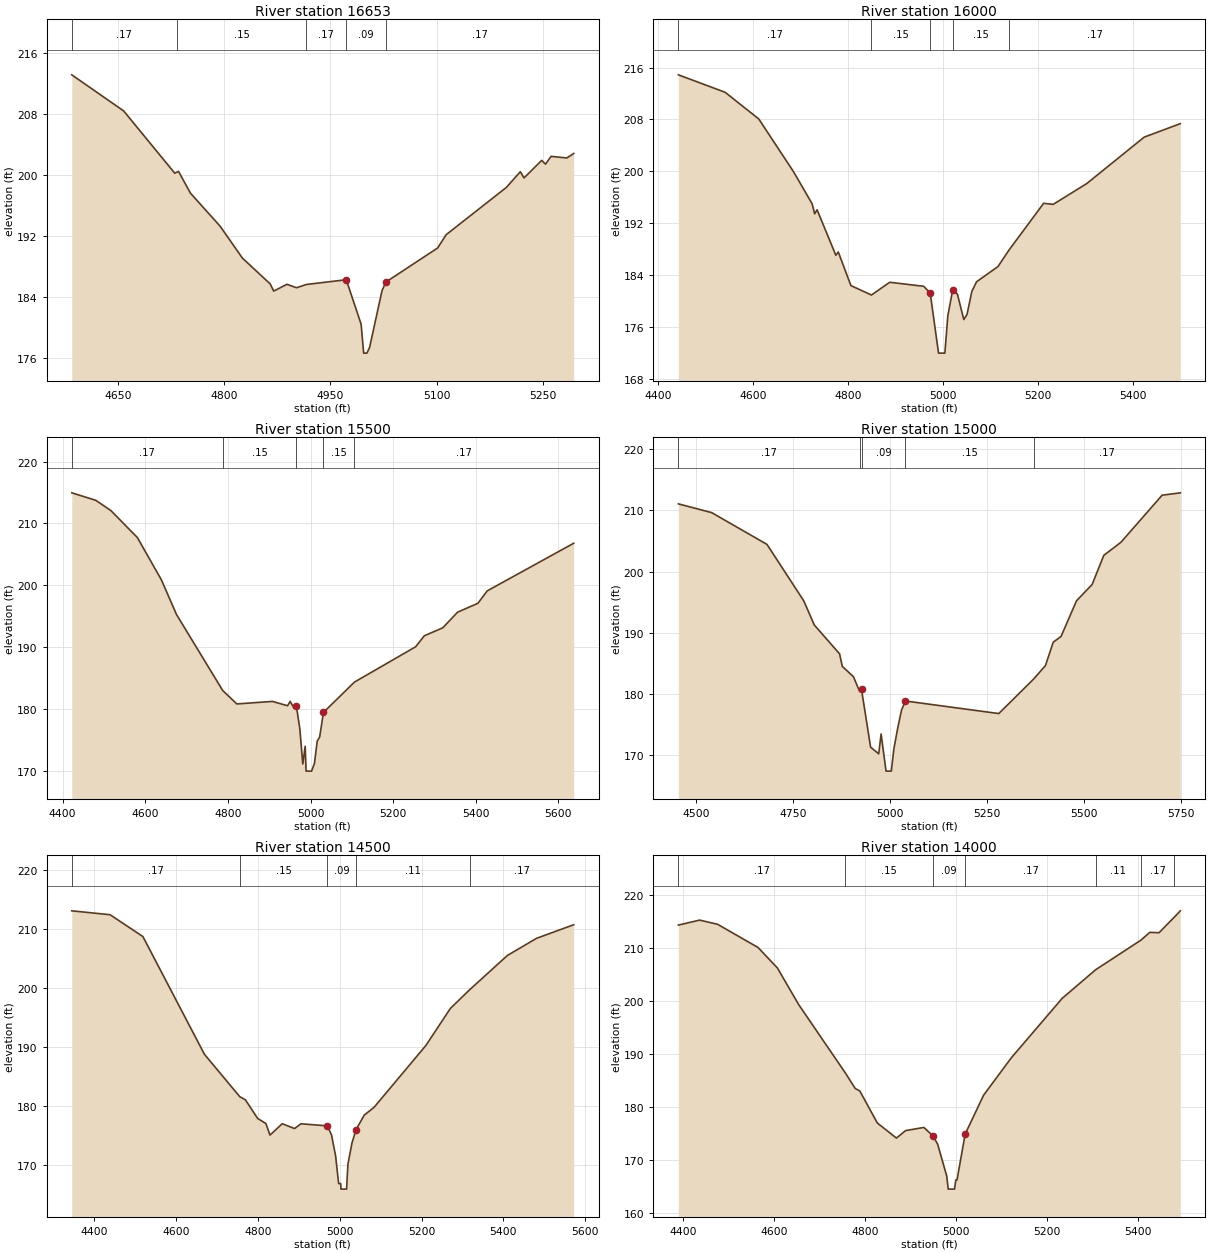
Type RM Length L Ch R = 1 ,16653   ,653,653,653
BEGIN DESCRIPTION:
WHITE OAK CREEK NORTH 33.0
END DESCRIPTION:
XS GIS Cut Line= 3
      3819417.88     10124361.06      3819021.44     10124486.11
      3818917.86     10124761.05
#Sta/Elev= 30
  4584.3  213.17  4657.7  208.43  4729.9  200.26  4732.9   200.4  4735.2   200.5
  4752.1  197.64    4794  193.31  4825.5  189.12  4864.6  185.75  4869.8  184.79
  4888.4  185.68  4902.1  185.23    4916  185.66  4972.3  186.28  4993.3  180.45
  4996.9  176.65  5001.5  176.65  5005.3   177.4  5022.8  184.83  5028.2  185.97
  5101.5  190.45  5113.5  192.19  5198.8  198.41  5218.3  200.46  5223.6  199.64
  5248.5  201.94  5253.9  201.45  5261.8  202.47  5284.1  202.26  5293.8  202.85
#Mann= 5 ,-1 , 0
  4584.3     .17       0  4732.9     .15       0    4916     .17       0
  4972.3     .09       0  5028.2     .17       0
Bank Sta=4972.3,5028.2
XS Rating Curve= 0 ,0
Exp/Cntr=0.3,0.1

Type RM Length L Ch R = 1 ,16000   ,500,500,500
BEGIN DESCRIPTION:
WHITE OAK CREEK NORTH 32.0
END DESCRIPTION:
XS GIS Cut Line= 3
      3819563.69     10123806.57      3819018.35     10123921.89
      3818522.45     10123853.49
#Sta/Elev= 30
  4442.6  214.87  4541.3  212.17  4612.1  208.06  4685.3  199.93  4724.5  194.98
  4729.9  193.43    4735  194.05  4774.5  187.04  4779.7  187.54  4806.3  182.36
  4849.6   180.9  4888.1  182.87  4959.6  182.25  4973.4  181.22    4991  171.94
  5004.3  171.94  5010.6  177.72  5020.7  181.65  5030.8  181.03  5044.2  177.12
    5051  177.89  5061.1  181.44  5071.2  182.95  5116.2  185.29  5140.3  187.92
  5212.5  195.05  5232.7  194.89  5303.3  198.09  5424.5  205.26  5500.6  207.34
#Mann= 5 ,-1 , 0
  4442.6     .17       0  4849.6     .15       0  4973.4     .09       0
  5020.7     .15       0  5140.3     .17       0
#XS Ineff= 2 , 0
       0  4779.7  187.54               0
Permanent Ineff=
       F       F
Bank Sta=4973.4,5020.7
XS Rating Curve= 0 ,0
Exp/Cntr=0.3,0.1

Type RM Length L Ch R = 1 ,15500   ,500,500,500
BEGIN DESCRIPTION:
WHITE OAK CREEK NORTH 31.0
END DESCRIPTION:
XS GIS Cut Line= 3
      3819558.57     10123738.88      3819065.74     10123436.87
      3818532.68      10123785.6
#Sta/Elev= 30
    4422  214.94  4480.2  213.73  4516.7  212.07  4580.8  207.71  4638.9  200.88
  4675.6  195.26  4787.4  182.98  4821.6  180.81  4907.7  181.22  4944.4  180.52
  4950.6  181.23  4959.9  180.13  4965.7  180.46  4974.1  176.78  4981.2  171.09
    4987  173.97  4989.2  169.95  5002.5  169.95  5009.4   171.2  5016.1  174.79
  5022.1  175.47  5031.2  179.44  5106.2  184.34  5254.3  190.05  5275.4  191.83
  5320.1  193.12    5356  195.65  5405.1  197.08  5427.7  199.09    5637  206.79
#Mann= 5 ,-1 , 0
    4422     .17       0  4787.4     .15       0  4965.7     .09       0
  5031.2     .15       0  5106.2     .17       0
Bank Sta=4965.7,5031.2
XS Rating Curve= 0 ,0
Exp/Cntr=0.3,0.1

Type RM Length L Ch R = 1 ,15000   ,500,500,500
BEGIN DESCRIPTION:
WHITE OAK CREEK NORTH 30.0
END DESCRIPTION:
XS GIS Cut Line= 3
      3819522.04     10122665.95      3819078.03     10122981.65
      3818331.07     10122936.87
#Sta/Elev= 30
  4455.2  211.06  4540.9  209.63  4683.5  204.44  4778.3  195.22  4805.3  191.29
  4870.5  186.57  4877.5  184.52  4906.1  182.85  4922.4   180.4    4927  180.77
  4950.4  171.34  4971.3  170.25  4977.5  173.49  4990.2  167.42  5003.8  167.42
  5010.2  170.99  5020.2  174.41  5030.2  177.42  5040.3  178.87  5280.7  176.82
    5371  182.49  5400.9  184.66  5420.9  188.47    5441  189.41    5481  195.24
  5521.1  197.89  5551.2  202.65  5595.4  204.79  5701.4  212.47  5748.3  212.86
#Mann= 5 ,-1 , 0
  4455.2     .17       0  4922.4     .15       0    4927     .09       0
  5040.3     .15       0    5371     .17       0
Bank Sta=4927,5040.3
XS Rating Curve= 0 ,0
Exp/Cntr=0.3,0.1

Type RM Length L Ch R = 1 ,14500   ,500,500,500
BEGIN DESCRIPTION:
WHITE OAK CREEK NORTH 29.0
END DESCRIPTION:
XS GIS Cut Line= 3
      3819501.27     10122556.56      3818847.98     10122591.04
      3818277.32     10122556.56
#Sta/Elev= 30
  4345.8  213.04  4439.4  212.38  4519.5  208.69  4669.7  188.79  4756.2   181.6
  4769.8  181.08  4799.9  177.92  4819.9  177.07  4829.9  175.11  4859.9  177.03
    4890  176.21  4905.3  177.02  4970.1  176.67  4980.1  175.15  4990.1  171.63
  4997.6  166.91  5002.6  166.91  5003.2  165.97    5017  165.97  5020.2  170.17
  5030.2  173.78  5040.2  176.05  5060.2  178.49  5083.9  179.79  5210.5  190.25
  5270.6  196.54  5317.5  199.69  5409.9   205.5    5481  208.39  5571.7  210.69
#Mann= 5 ,-1 , 0
  4345.8     .17       0  4756.2     .15       0  4970.1     .09       0
  5040.2     .11       0  5317.5     .17       0
Bank Sta=4970.1,5040.2
XS Rating Curve= 0 ,0
Exp/Cntr=0.3,0.1

Type RM Length L Ch R = 1 ,14000   ,500,500,500
BEGIN DESCRIPTION:
WHITE OAK CREEK NORTH 28.0
END DESCRIPTION:
XS GIS Cut Line= 3
      3819454.32     10122035.73      3818848.11     10122105.43
      3818361.71     10122020.29
#Sta/Elev= 30
  4389.8  214.35  4436.6  215.29  4476.1   214.5  4565.1  210.12  4607.7  206.25
  4654.2  199.38  4756.9  186.47  4778.8  183.52  4788.9  183.05  4827.3  177.02
  4869.4  174.16  4889.5  175.57  4929.8  176.17  4949.9  174.56    4960  173.03
  4980.1  166.99  4983.3  164.53  4997.1  164.53    5000  166.27  5002.7  166.27
  5020.6  174.92  5061.2  182.26  5122.1  189.31  5233.8  200.51  5307.7  205.93
  5407.2  211.51  5426.7  212.98    5447  212.91  5480.7  215.86  5493.8  217.04
#Mann= 7 ,-1 , 0
  4389.8     .17       0  4756.9     .15       0  4949.9     .09       0
  5020.6     .17       0  5307.7     .11       0  5407.2     .17       0
  5480.7     .11       0
Bank Sta=4949.9,5020.6
XS Rating Curve= 0 ,0
Exp/Cntr=0.3,0.1

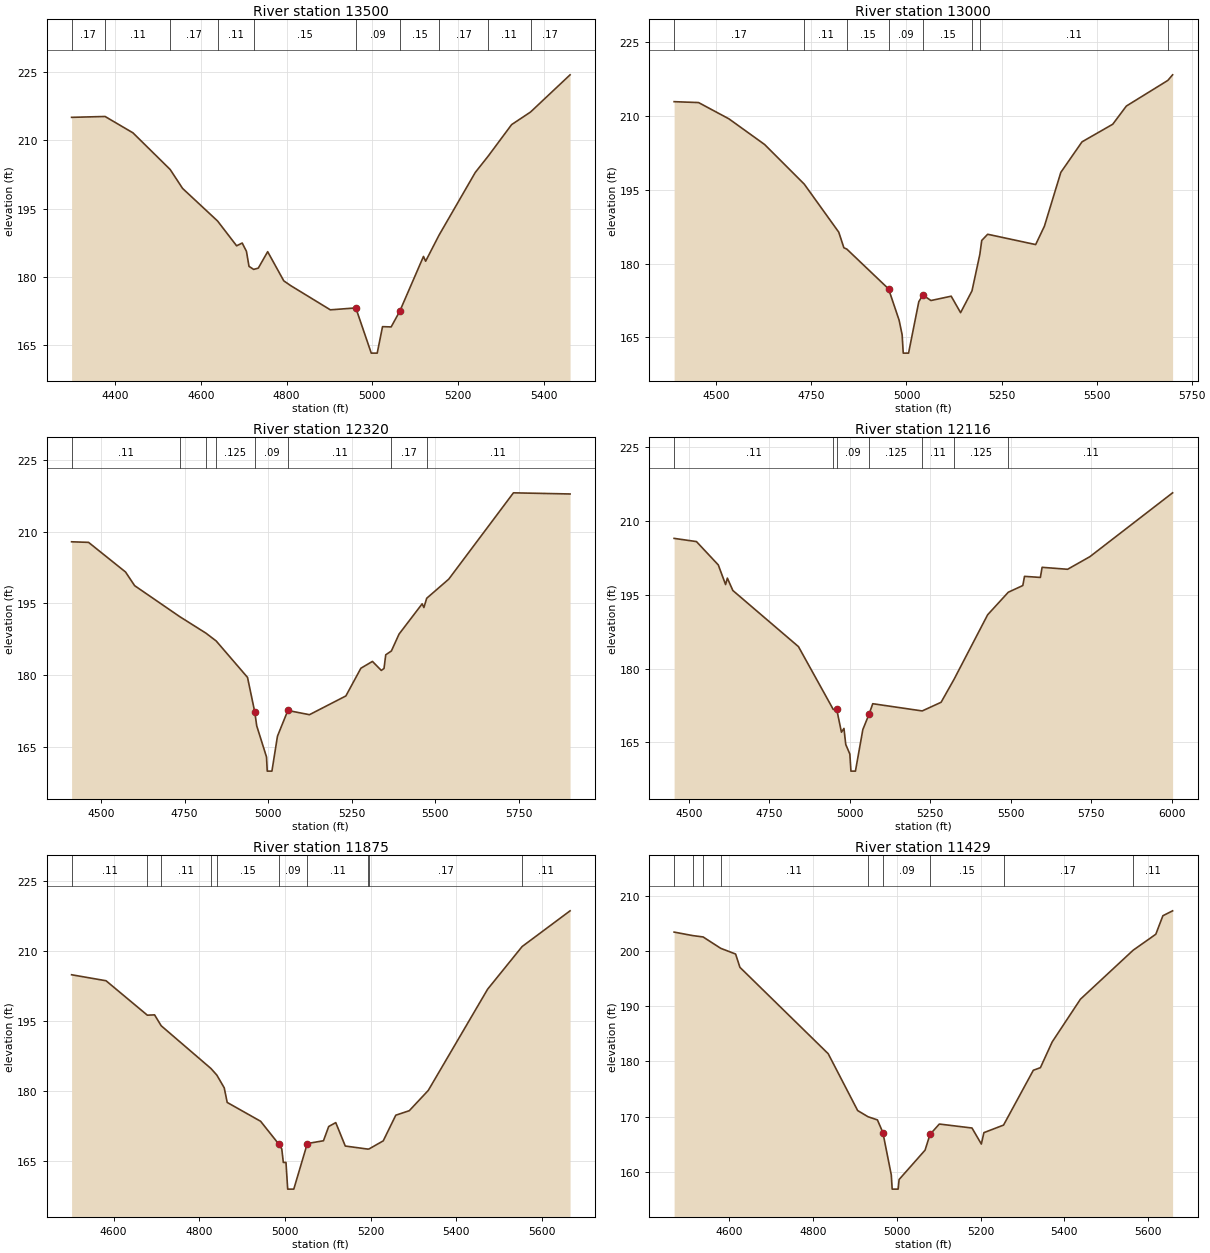
Type RM Length L Ch R = 1 ,13500   ,500,500,500
BEGIN DESCRIPTION:
WHITE OAK CREEK NORTH 27.0
END DESCRIPTION:
XS GIS Cut Line= 3
      3819443.91       10121968.      3818831.36     10121625.91
      3818371.93     10121587.88
#Sta/Elev= 30
  4298.4  215.04  4376.5  215.23  4441.5  211.64  4528.3   203.6  4557.3  199.44
  4638.9  192.29  4683.3  186.85  4696.3  187.46  4706.2  185.64  4712.2  182.34
  4723.1  181.67  4733.9  181.96  4755.7  185.56  4793.3  179.16  4809.3  178.12
  4901.9   172.8  4961.3  173.22  4997.3   163.3  5011.2   163.3  5023.6  169.11
  5043.7  169.05  5063.7  172.48  5119.1  184.52  5124.1  183.47  5155.4  189.19
  5239.9  202.95  5270.1  206.54  5324.6  213.44  5368.8  216.21    5461  224.37
#Mann= 10 ,-1 , 0
  4298.4     .17       0  4376.5     .11       0  4528.3     .17       0
  4638.9     .11       0  4723.1     .15       0  4961.3     .09       0
  5063.7     .15       0  5155.4     .17       0  5270.1     .11       0
  5368.8     .17       0
#XS Ineff= 2 , 0
       0  4755.7  185.56               0
Permanent Ineff=
       F       F
Bank Sta=4961.3,5063.7
XS Rating Curve= 0 ,0
Exp/Cntr=0.3,0.1

Type RM Length L Ch R = 1 ,13000   ,680,680,680
BEGIN DESCRIPTION:
WHITE OAK CREEK NORTH 26.0
END DESCRIPTION:
XS GIS Cut Line= 3
      3819641.82     10121655.49      3819128.35     10121324.51
       3818471.4     10121083.12
#Sta/Elev= 30
  4389.1  212.94  4453.3  212.76  4533.2  209.45  4626.9  204.24  4731.3  196.17
  4822.1  186.39  4835.5  183.22  4843.1  182.96    4953  174.86  4980.7   168.5
  4988.7  165.52  4991.6  161.79  5005.6  161.79  5032.5  172.25  5043.1  173.61
  5064.5  172.49  5117.7  173.37  5142.4  170.02  5172.4  174.46  5193.1  181.91
    5198  184.71  5213.6  185.97  5339.8  183.87  5362.8  187.61    5406  198.56
  5461.7  204.77  5542.5  208.35  5578.3  212.05  5687.3  217.26  5699.9   218.4
#Mann= 8 ,-1 , 0
  4389.1     .17       0  4731.3     .11       0  4843.1     .15       0
    4953     .09       0  5043.1     .15       0  5172.4     .17       0
  5193.1     .11       0  5687.3     .17       0
Bank Sta=4953,5043.1
XS Rating Curve= 0 ,0
Exp/Cntr=0.3,0.1

Type RM Length L Ch R = 1 ,12320   ,204,204,204
BEGIN DESCRIPTION:
WHITE OAK CREEK NORTH 25.0
END DESCRIPTION:
XS GIS Cut Line= 3
      3820049.55     10121100.31      3819545.15     10120797.92
      3818672.41     10120560.74
#Sta/Elev= 30
  4411.9  207.86  4462.7  207.74  4573.5  201.55  4600.7   198.7  4735.8  192.23
  4813.9   188.8  4844.8  187.16  4938.6  179.56  4960.4  172.32  4966.2  169.44
  4995.5  162.95  4997.7  159.99  5011.7  159.99  5028.3  167.28  5059.4  172.65
  5124.1  171.77  5233.1  175.68  5278.1  181.47  5312.7  182.89  5339.2  181.01
  5347.3  181.42  5352.5  184.27  5369.4  185.07  5392.3  188.59  5461.5  194.91
  5466.7  194.14  5475.1  196.07  5541.1  200.06  5734.8  218.08  5904.4  217.84
#Mann= 8 ,-1 , 0
  4411.9     .11       0  4735.8     .17       0  4813.9     .11       0
  4844.8    .125       0  4960.4     .09       0  5059.4     .11       0
  5369.4     .17       0  5475.1     .11       0
Bank Sta=4960.4,5059.4
XS Rating Curve= 0 ,0
Exp/Cntr=0.3,0.1

Type RM Length L Ch R = 1 ,12116   ,241,241,241
BEGIN DESCRIPTION:
WHITE OAK CREEK NORTH 23.0
END DESCRIPTION:
XS GIS Cut Line= 3
      3820186.76     10120895.41       3819694.3     10120659.17
      3818757.97     10120299.01
#Sta/Elev= 30
  4453.8  206.49  4523.2  205.84  4591.1  201.09  4613.8  197.09  4619.3   198.4
  4636.4  195.88  4840.3  184.46  4948.4  171.68  4959.1  171.73  4973.9  167.04
  4981.7  167.81  4987.3  164.54    5000   162.6  5003.4  159.12  5017.4  159.12
  5040.4  167.58  5059.7  170.71  5071.2  172.84  5224.9  171.37  5283.6  173.13
  5323.9  177.81  5428.3  190.94  5492.5  195.53  5537.6  196.89  5542.9  198.76
  5592.2  198.54  5597.6   200.6  5676.8   200.2  5746.2  202.77  6003.2  215.76
#Mann= 7 ,-1 , 0
  4453.8     .11       0  4948.4    .125       0  4959.1     .09       0
  5059.7    .125       0  5224.9     .11       0  5323.9    .125       0
  5492.5     .11       0
Bank Sta=4959.1,5059.7
XS Rating Curve= 0 ,0
Exp/Cntr=0.3,0.1

Type RM Length L Ch R = 1 ,11875   ,446,446,446
BEGIN DESCRIPTION:
Mapping XS ad3a689e
END DESCRIPTION:
XS GIS Cut Line= 3
      3820228.57     10120833.96      3819868.35     10120491.09
      3819276.42     10120185.44
#Sta/Elev= 30
  4501.8  204.95  4582.2  203.67  4678.6   196.3  4695.5  196.37  4710.9  194.04
  4827.1  184.89  4840.9  183.47  4858.1  180.75    4865  177.63    4943   173.6
  4985.5   168.7  4992.4  167.68    4996  164.79  5002.2  164.79  5006.2  159.08
  5020.4  159.08    5052  168.84  5089.7  169.43  5101.9  172.48  5118.4  173.31
  5140.6   168.3  5192.9  167.65  5195.9  167.67  5229.2  169.41  5258.5   174.9
    5290  175.86  5334.3   180.2  5472.9  201.87  5553.3  210.98  5665.3  218.63
#Mann= 10 ,-1 , 0
  4501.8     .11       0  4678.6     .17       0  4710.9     .11       0
  4827.1     .17       0  4840.9     .15       0  4985.5     .09       0
    5052     .11       0  5192.9     .15       0  5195.9     .17       0
  5553.3     .11       0
Bank Sta=4985.5,5052
XS Rating Curve= 0 ,0
Exp/Cntr=0.3,0.1

Type RM Length L Ch R = 1 ,11429   ,429,429,429
BEGIN DESCRIPTION:
WHITE OAK CREEK NORTH 21.0
END DESCRIPTION:
XS GIS Cut Line= 3
      3820276.41      10120787.5      3820228.89     10120257.82
      3819637.89     10119967.85
#Sta/Elev= 30
  4468.2  203.48  4513.1  202.84  4537.4   202.6  4579.4  200.54    4615   199.5
  4625.3  197.09  4836.1  181.41  4906.4   171.1    4931  169.98  4953.6   169.4
  4966.6  167.11  4986.7  159.41  4988.8  156.84    5003  156.84  5005.4  158.59
  5067.3  163.91  5079.1  166.76  5101.4  168.65  5179.4  167.93  5201.7  165.02
  5207.8  167.09  5254.7  168.46  5325.8  178.41  5342.7  178.88  5370.8  183.55
  5438.2   191.3  5563.9  200.18  5618.2  203.09  5635.1  206.45  5658.3  207.34
#Mann= 9 ,-1 , 0
  4468.2     .17       0  4513.1     .11       0  4537.4     .17       0
  4579.4     .11       0    4931     .15       0  4966.6     .09       0
  5079.1     .15       0  5254.7     .17       0  5563.9     .11       0
Bank Sta=4966.6,5079.1
XS Rating Curve= 0 ,0
Exp/Cntr=0.3,0.1

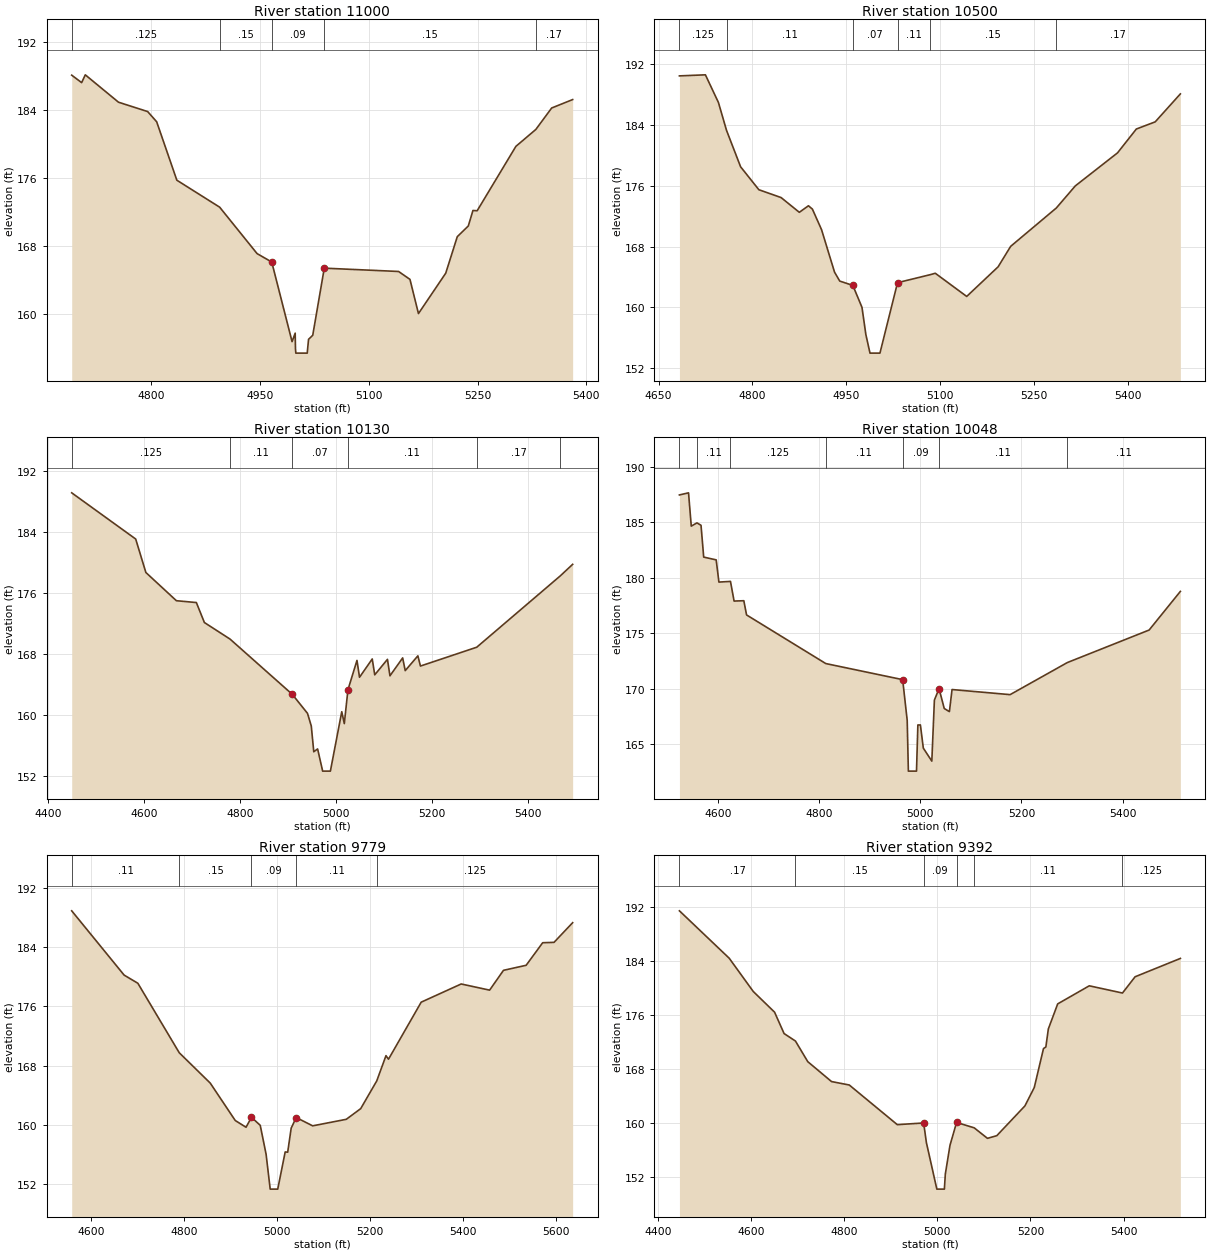
Type RM Length L Ch R = 1 ,11000   ,500,500,500
BEGIN DESCRIPTION:
WHITE OAK CREEK NORTH 22.0
END DESCRIPTION:
XS GIS Cut Line= 3
      3820802.01     10119914.18      3820494.29     10119946.37
      3820162.68     10119758.76
#Sta/Elev= 30
  4690.6  188.09  4704.3  187.21  4709.3  188.13  4755.1  184.91  4795.3  183.81
  4807.7  182.61  4835.5  175.74  4894.5  172.57  4946.1  167.11  4966.3  166.12
  4994.3  156.76  4998.6  157.76    4999  155.91  4999.5  155.41  5015.2  155.41
    5017  157.03  5022.8  157.51  5038.7   165.4  5141.1  165.01  5156.8  164.08
  5168.5  160.06  5206.1  164.81    5222   169.1  5237.2  170.36  5243.6  172.18
  5249.4  172.15  5302.8  179.72  5330.3  181.71  5352.1  184.23    5381  185.22
#Mann= 5 ,-1 , 0
  4690.6    .125       0  4894.5     .15       0  4966.3     .09       0
  5038.7     .15       0  5330.3     .17       0
Bank Sta=4966.3,5038.7
XS Rating Curve= 0 ,0
Exp/Cntr=0.3,0.1

Type RM Length L Ch R = 1 ,10500   ,370,370,370
BEGIN DESCRIPTION:
WHITE OAK CREEK NORTH 21.5
END DESCRIPTION:
XS GIS Cut Line= 3
      3820889.27     10119757.21      3820699.47     10119503.69
      3820217.85     10119461.07
#Sta/Elev= 30
  4683.3  190.46  4724.8   190.6  4745.6  186.96  4758.5   183.3    4781   178.5
  4810.2  175.48  4845.7  174.45  4874.8  172.51  4889.4  173.37  4895.7  172.93
  4910.3  170.23  4931.1  164.63  4939.4  163.46  4960.3  162.89  4974.9  160.01
  4981.1  156.43  4987.7  153.98  5003.6  153.98  5031.7  163.25  5083.8   164.3
    5092  164.49  5142.2  161.44  5192.4  165.34  5212.4  168.03  5285.4  173.08
  5315.6  175.98  5383.1  180.33  5413.2  183.47  5443.3  184.41  5483.5  188.09
#Mann= 6 ,-1 , 0
  4683.3    .125       0  4758.5     .11       0  4960.3     .07       0
  5031.7     .11       0  5083.8     .15       0  5285.4     .17       0
#XS Ineff= 2 , 0
       0  4889.4  173.37               0
Permanent Ineff=
       F       F
Bank Sta=4960.3,5031.7
XS Rating Curve= 0 ,0
Exp/Cntr=0.3,0.1

Type RM Length L Ch R = 1 ,10130   ,82,82,82
BEGIN DESCRIPTION:
WHITE OAK CREEK NORTH 19.0
END DESCRIPTION:
XS GIS Cut Line= 3
      3821324.54     10118989.48      3820801.93      10119161.2
      3820333.41     10119316.24
#Sta/Elev= 30
  4449.9  189.19  4583.2  183.13  4604.4  178.74    4668  175.04  4709.6   174.8
  4726.3  172.18  4779.7  170.01  4909.6  162.75  4941.1  160.27    4949  158.61
  4954.2  155.23  4962.2   155.6  4972.7  152.69  4988.8  152.69  5012.5  160.48
  5017.8  158.92  5025.4  163.36  5044.2  167.21  5049.5     165    5076   167.4
  5081.2  165.32  5107.7  167.35  5112.9  165.19  5139.4  167.54  5144.7  165.87
  5171.1  167.81  5176.4  166.47  5293.7  168.94  5467.8   178.3  5493.5  179.81
#Mann= 6 ,-1 , 0
  4449.9    .125       0  4779.7     .11       0  4909.6     .07       0
  5025.4     .11       0  5293.7     .17       0  5467.8     .11       0
Bank Sta=4909.6,5025.4
XS Rating Curve= 0 ,0
Exp/Cntr=0.3,0.1

Type RM Length L Ch R = 1 ,10048   ,269,269,269
BEGIN DESCRIPTION:
WHITE OAK CREEK NORTH 18.0
END DESCRIPTION:
XS GIS Cut Line= 3
      3821248.54     10118909.19      3820803.46     10119079.91
      3820306.68     10119213.02
#Sta/Elev= 30
  4523.3  187.48  4541.3  187.67  4546.7  184.67  4557.9  184.96    4566  184.75
  4571.3  181.88    4596  181.63  4601.4  179.63  4624.3  179.69  4631.4  177.92
  4650.7  177.95  4656.1  176.67  4812.8  172.29  4964.9  170.84  4973.9  167.17
  4976.2   162.6  4992.3   162.6    4995  166.76    5000  166.76  5005.8  164.67
  5022.6   163.5  5027.7     169  5036.9  170.03  5047.2  168.24  5057.4  167.96
  5062.6  169.95  5177.5  169.49  5290.7  172.38  5452.5  175.31  5514.3  178.79
#Mann= 7 ,-1 , 0
  4523.3    .125       0  4557.9     .11       0  4624.3    .125       0
  4812.8     .11       0  4964.9     .09       0  5036.9     .11       0
  5290.7     .11       0
Bank Sta=4964.9,5036.9
XS Rating Curve= 0 ,0
Exp/Cntr=0.3,0.1

Type RM Length L Ch R = 1 ,9779    ,387,387,387
BEGIN DESCRIPTION:
Mapping XS b7ad5950
END DESCRIPTION:
XS GIS Cut Line= 3
       3821155.2     10118653.13      3820668.39     10118849.63
      3820154.76     10119050.27
#Sta/Elev= 30
  4558.7  188.87  4671.3  180.21  4700.8  179.11  4789.8  169.74  4856.4  165.65
  4910.1  160.61  4933.3   159.7    4945  161.04  4963.8  159.96  4976.4  156.06
  4985.2  151.36  5001.4  151.36  5017.4  156.37  5022.8  156.34  5030.3  159.58
  5041.1  161.01  5076.5  159.89  5148.7  160.77  5179.7  162.21  5214.2  165.95
    5234  169.35  5239.4  168.87  5309.7  176.56  5395.6  179.01  5456.7  178.18
  5486.5  180.85  5535.2  181.53  5570.7  184.57  5595.1  184.62  5635.1  187.27
#Mann= 5 ,-1 , 0
  4558.7     .11       0  4789.8     .15       0    4945     .09       0
  5041.1     .11       0  5214.2    .125       0
Bank Sta=4945,5041.1
XS Rating Curve= 0 ,0
Exp/Cntr=0.3,0.1

Type RM Length L Ch R = 1 ,9392    ,607,607,607
BEGIN DESCRIPTION:
WHITE OAK CREEK NORTH 17.0
END DESCRIPTION:
XS GIS Cut Line= 3
      3821098.35     10118385.67      3820555.03     10118491.84
      3820035.86     10118546.16
#Sta/Elev= 30
  4446.4  191.45  4553.3  184.42  4604.9  179.49  4650.7  176.42  4671.1  173.25
  4695.5  172.14    4722  169.08    4773  166.13  4811.1  165.62  4914.2  159.74
  4970.8  159.99  4976.7  157.07  4999.1  150.18  5015.3  150.18  5017.3   152.4
  5027.3  156.67  5041.5  160.07  5079.3  159.27  5107.8  157.71  5127.9  158.11
  5188.2  162.52  5208.3  165.25  5228.1  171.02  5233.2  171.26  5238.5  173.93
  5258.6  177.65  5326.4  180.33  5397.7  179.26  5424.8  181.67    5522  184.39
#Mann= 6 ,-1 , 0
  4446.4     .17       0  4695.5     .15       0  4970.8     .09       0
  5041.5     .15       0  5079.3     .11       0  5397.7    .125       0
Bank Sta=4970.8,5041.5
XS Rating Curve= 0 ,0
Exp/Cntr=0.3,0.1