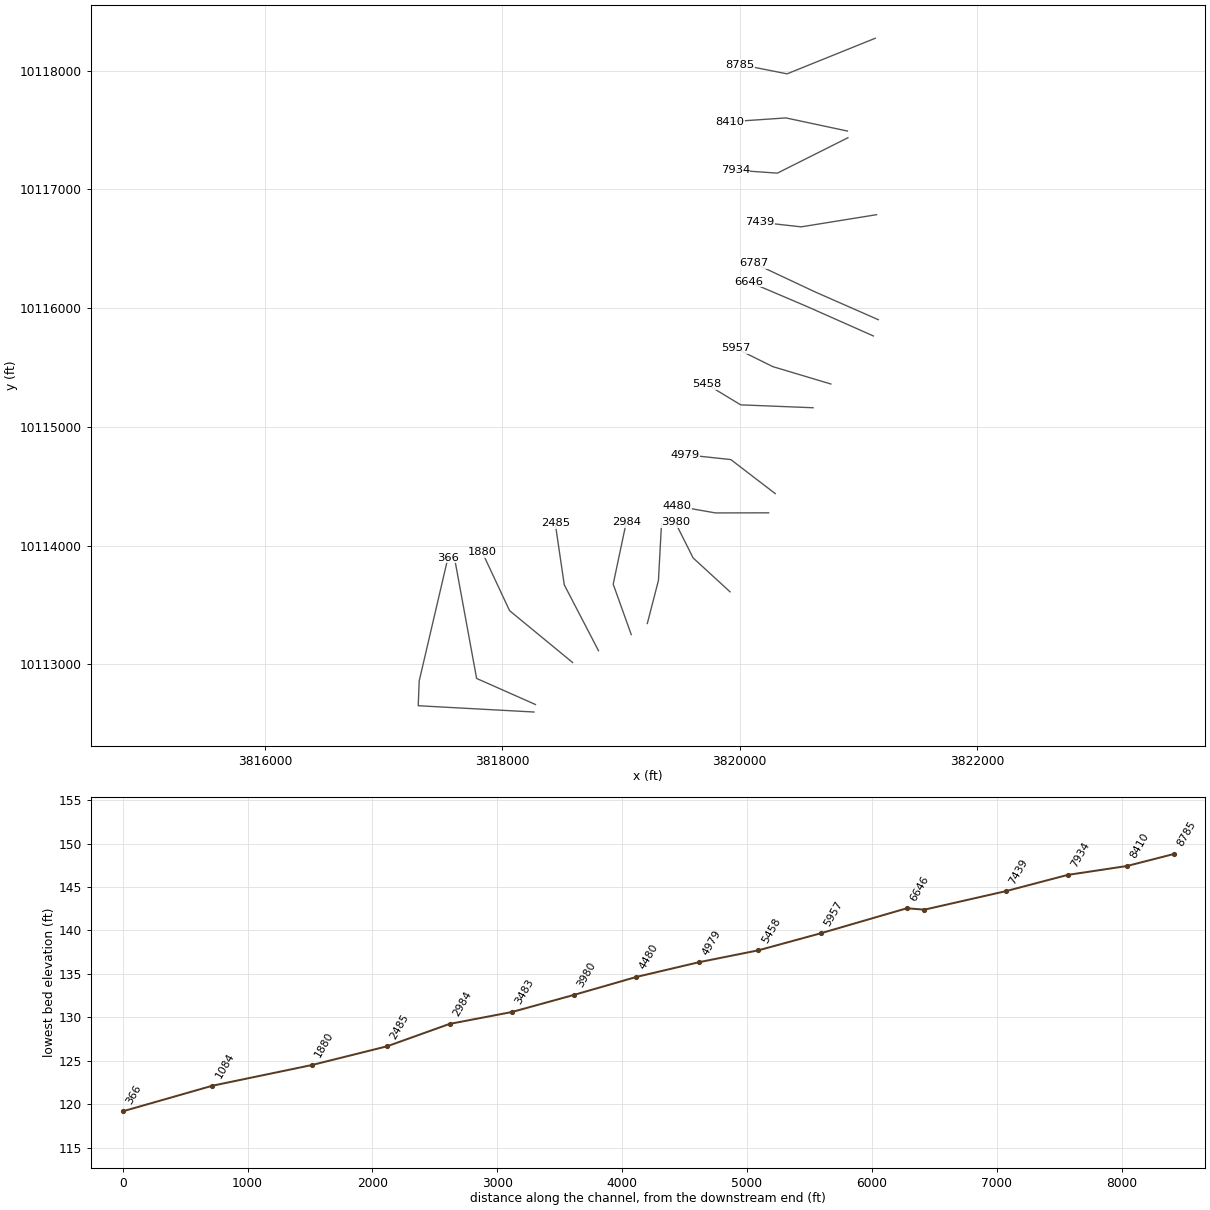
HEC-RAS study WHITE OAK CREEK NORTH.prj: WHITE OAK CREEK NORTH Base Level Engineering

--- WHITE OAK CREEK NORTH.g01 (geometry) --- (continued)

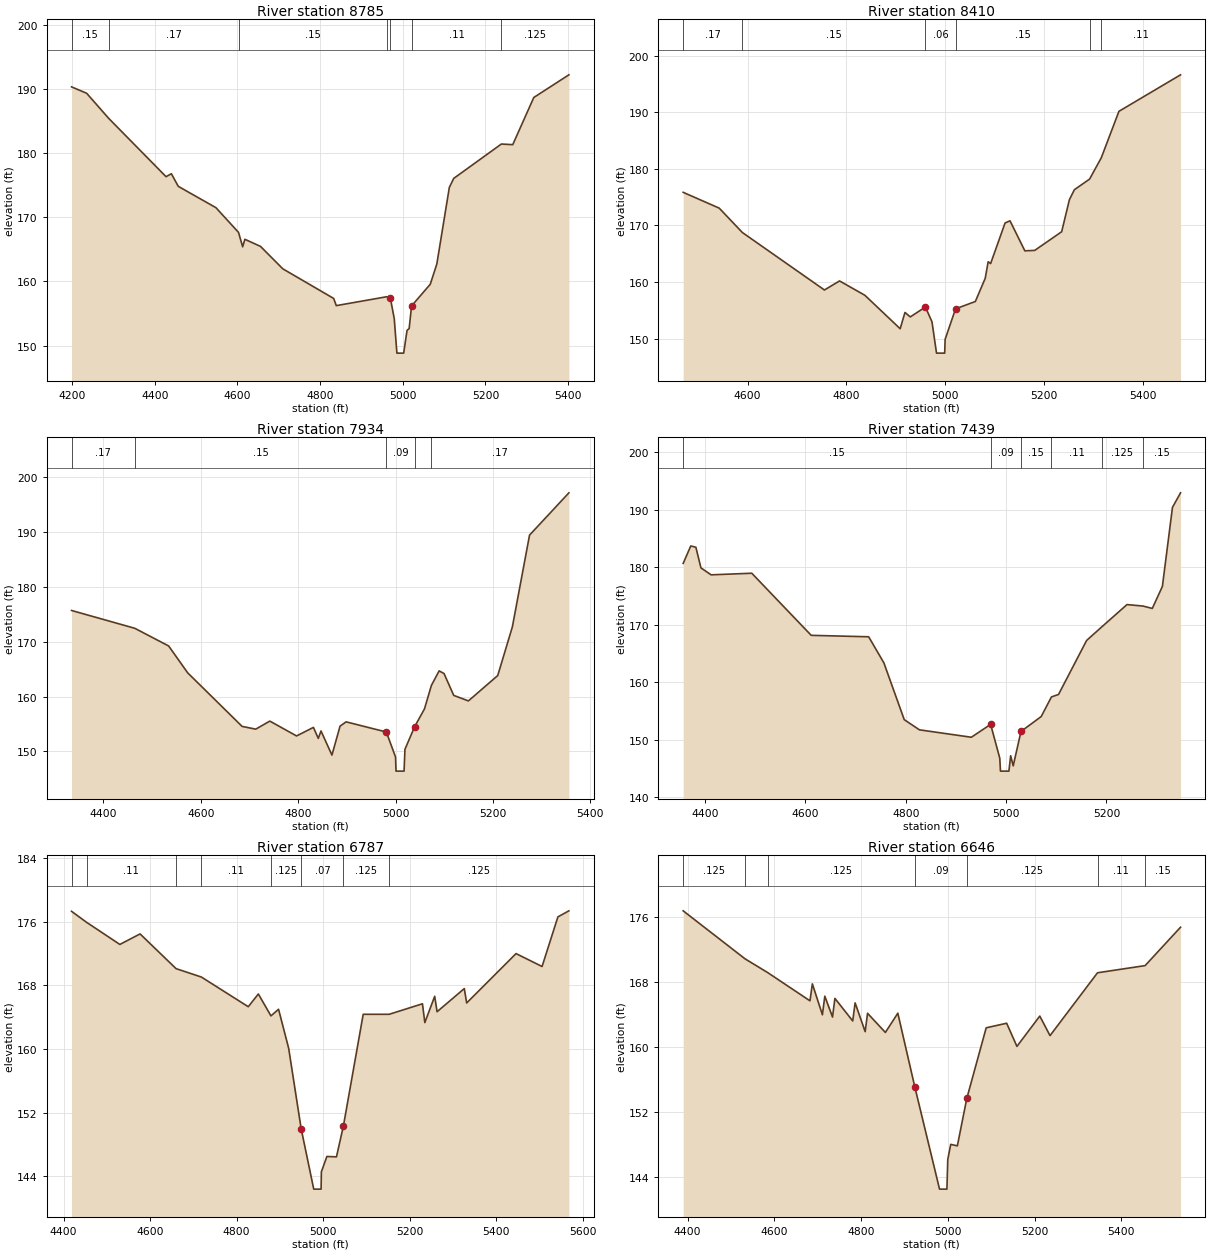
Type RM Length L Ch R = 1 ,8785    ,375,375,375
BEGIN DESCRIPTION:
WHITE OAK CREEK NORTH 18.5
END DESCRIPTION:
XS GIS Cut Line= 3
       3821141.8     10118272.82      3820398.71     10117973.23
       3820004.6     10118051.47
#Sta/Elev= 30
  4198.8   190.4  4235.4   189.4  4288.4   185.5  4427.4  176.37  4440.3  176.83
    4457  174.86  4548.1  171.53  4602.7  167.67  4612.7  165.42  4618.1  166.59
  4655.9  165.48  4709.8  161.98  4832.9  157.35  4839.2  156.23  4961.4  157.62
  4969.8  157.46  4979.4  154.19  4985.8  148.81  5002.2  148.81  5010.3  152.37
  5015.4  152.64  5021.3  156.18  5066.5  159.57  5082.4  162.74  5112.6  174.69
  5123.2   176.1  5238.5  181.47    5266  181.37  5316.9  188.74  5401.8  192.28
#Mann= 7 ,-1 , 0
  4198.8     .15       0  4288.4     .17       0  4602.7     .15       0
  4961.4     .11       0  4969.8     .06       0  5021.3     .11       0
  5238.5    .125       0
Bank Sta=4969.8,5021.3
XS Rating Curve= 0 ,0
Exp/Cntr=0.3,0.1

Type RM Length L Ch R = 1 ,8410    ,476,476,476
BEGIN DESCRIPTION:
WHITE OAK CREEK NORTH 15.0
END DESCRIPTION:
XS GIS Cut Line= 3
      3820907.43     10117491.56      3820388.87     10117602.05
      3819913.47     10117569.69
#Sta/Elev= 30
  4469.8  175.85  4542.7  173.06  4589.6  168.75  4755.7  158.59  4786.3  160.19
  4837.5  157.66    4909  151.74  4918.7  154.62  4929.5  153.83  4960.1  155.58
  4973.4  152.96  4982.6  147.43  4999.1  147.43    5000  149.87  5021.1  155.25
  5061.2  156.56  5081.2  160.67  5087.1  163.58  5092.1  163.26  5121.3  170.43
  5131.3  170.82  5161.4  165.51  5181.4  165.59  5235.9  168.89  5251.6  174.56
  5261.6  176.31  5292.4  178.19  5316.1  181.96  5351.8  190.17  5476.5  196.62
#Mann= 6 ,-1 , 0
  4469.8     .17       0  4589.6     .15       0  4960.1     .06       0
  5021.1     .15       0  5292.4     .17       0  5316.1     .11       0
Bank Sta=4960.1,5021.1
XS Rating Curve= 0 ,0
Exp/Cntr=0.3,0.1

Type RM Length L Ch R = 1 ,7934    ,495,495,495
BEGIN DESCRIPTION:
WHITE OAK CREEK NORTH 14.0
END DESCRIPTION:
XS GIS Cut Line= 3
      3820911.76     10117435.14       3820317.1     10117137.02
      3819962.06     10117161.65
#Sta/Elev= 30
  4334.8  175.68  4464.7  172.43  4534.2  169.21  4573.3  164.31    4685  154.55
    4713  154.05  4741.9  155.52  4796.8  152.81  4831.4  154.37  4841.4  152.37
    4847  153.72  4869.4  149.32  4886.1   154.6  4898.5  155.38  4981.1  153.53
    5000  148.97    5001   146.4  5017.5   146.4  5019.3  150.37  5039.3  154.51
  5059.4  157.74  5073.6  162.02  5089.5  164.67  5099.5  164.19  5119.5   160.2
  5149.6   159.2  5209.8  163.82  5239.8  172.67  5275.1  189.41  5355.9  197.12
#Mann= 5 ,-1 , 0
  4334.8     .17       0  4464.7     .15       0  4981.1     .09       0
  5039.3     .15       0  5073.6     .17       0
#XS Ineff= 2 , 0
       0                  5089.5       0  164.67
Permanent Ineff=
       F       F
Bank Sta=4981.1,5039.3
XS Rating Curve= 0 ,0
Exp/Cntr=0.3,0.1

Type RM Length L Ch R = 1 ,7439    ,652,652,652
BEGIN DESCRIPTION:
WHITE OAK CREEK NORTH 13.0
END DESCRIPTION:
XS GIS Cut Line= 3
      3821152.79     10116787.03       3820517.4     10116684.55
      3820171.85     10116723.16
#Sta/Elev= 30
  4356.4  180.65  4371.5  183.68  4381.7  183.46  4391.8  179.87    4412  178.66
  4493.1  178.94  4611.6  168.14  4726.1  167.89  4756.4  163.36    4797  153.48
  4827.3  151.71  4930.7  150.42  4969.2  152.66  4987.4  146.78  4988.8  144.53
  5005.6  144.53  5009.1   147.2  5014.2  145.45  5029.7  151.43    5070  154.02
  5090.4  157.43  5104.5  157.86  5160.5  167.25  5190.7  169.61    5241  173.49
  5272.9  173.23  5291.4  172.82  5311.5  176.64  5331.6  190.39  5347.7  192.92
#Mann= 6 ,-1 , 0
  4356.4     .15       0  4969.2     .09       0  5029.7     .15       0
  5090.4     .11       0  5190.7    .125       0  5272.9     .15       0
Bank Sta=4969.2,5029.7
XS Rating Curve= 0 ,0
Exp/Cntr=0.3,0.1

Type RM Length L Ch R = 1 ,6787    ,141,141,141
BEGIN DESCRIPTION:
WHITE OAK CREEK NORTH 12.0
END DESCRIPTION:
XS GIS Cut Line= 3
      3821168.08     10115902.49      3820635.64     10116136.25
      3820121.77     10116377.78
#Sta/Elev= 30
  4418.5  177.28  4453.2   175.9  4530.2  173.12  4576.9  174.44  4660.1  170.08
  4718.5  169.03  4826.9   165.3  4850.2   166.9  4879.3  164.15  4896.9  164.98
  4920.3  160.07  4949.1  149.99  4978.2   142.4  4995.2   142.4  4995.8  144.57
  5008.6   146.5  5030.7  146.45  5046.9  150.37  5092.5  164.35  5152.6  164.35
  5229.4  165.67  5234.9  163.31  5257.7  166.61  5263.2  164.67  5326.1  167.58
  5331.6  165.77  5445.7  171.97  5505.8  170.35  5542.4  176.58  5567.8  177.34
#Mann= 8 ,-1 , 0
  4418.5    .125       0  4453.2     .11       0  4660.1    .125       0
  4718.5     .11       0  4879.3    .125       0  4949.1     .07       0
  5046.9    .125       0  5152.6    .125       0
Bank Sta=4949.1,5046.9
XS Rating Curve= 0 ,0
Exp/Cntr=0.3,0.1

Type RM Length L Ch R = 1 ,6646    ,689,689,689
BEGIN DESCRIPTION:
WHITE OAK CREEK NORTH 11.0
END DESCRIPTION:
XS GIS Cut Line= 3
      3821126.08     10115765.78      3820568.21     10116013.02
      3820074.31      10116223.3
#Sta/Elev= 30
  4389.8   176.7  4532.5  170.81  4584.8  169.12  4682.2  165.66  4687.7  167.74
  4710.9  163.95  4716.4  166.23  4734.2  163.67  4739.7  165.96  4780.8  163.19
  4786.3  165.41  4809.5  161.88    4815  164.13  4856.1  161.78  4884.8  164.14
  4923.8  155.14    4981  142.56    4998  142.56    5000  146.19  5006.8  148.05
  5022.1  147.87  5043.9  153.69  5088.6  162.35  5135.8  162.91  5159.5  160.07
  5212.2  163.79  5235.8  161.39  5345.3   169.1  5455.1  169.98  5536.8  174.69
#Mann= 7 ,-1 , 0
  4389.8    .125       0  4532.5     .11       0  4584.8    .125       0
  4923.8     .09       0  5043.9    .125       0  5345.3     .11       0
  5455.1     .15       0
Bank Sta=4923.8,5043.9
XS Rating Curve= 0 ,0
Exp/Cntr=0.3,0.1

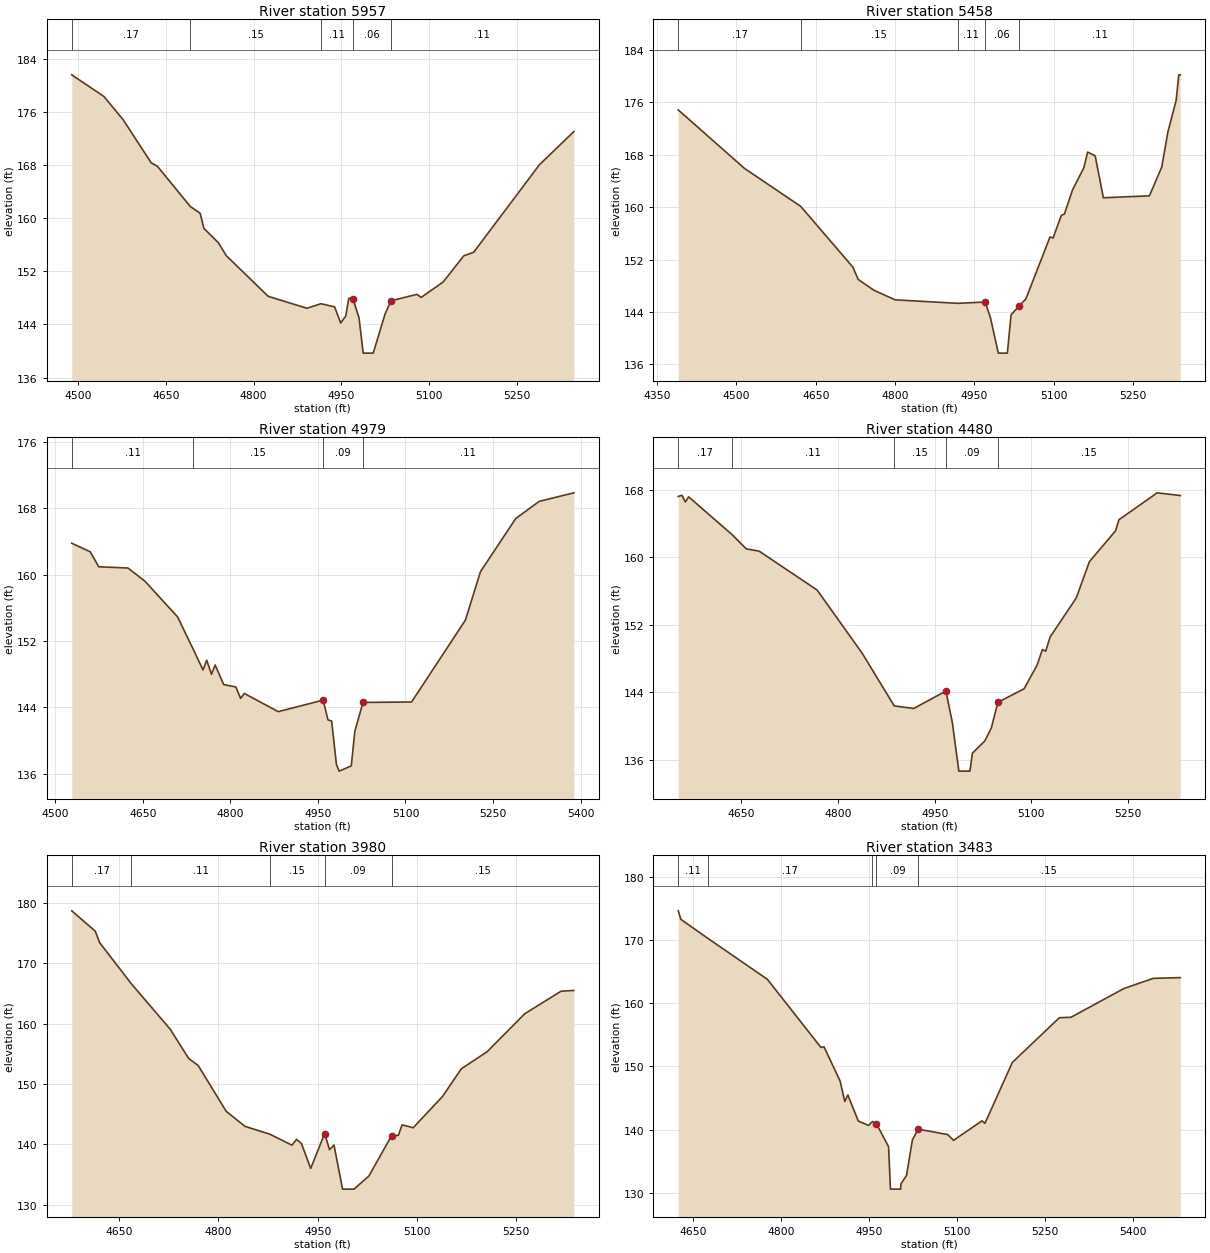
Type RM Length L Ch R = 1 ,5957    ,499,499,499
BEGIN DESCRIPTION:
WHITE OAK CREEK NORTH 10.0
END DESCRIPTION:
XS GIS Cut Line= 3
      3820767.83     10115361.08      3820278.83     10115507.31
      3819967.87     10115661.06
#Sta/Elev= 30
  4489.6  181.62  4544.5  178.36  4577.6  174.82  4625.3  168.35  4635.7  167.85
  4692.2  161.76  4708.8  160.76  4715.2  158.48  4740.1   156.3  4753.5  154.36
    4825  148.24  4891.2  146.44    4915  147.13  4938.4  146.65  4948.8  144.22
  4957.4  145.27  4962.6  147.94  4969.7  147.89  4980.1  144.99  4987.2  139.68
  5004.3  139.68  5024.4  145.53  5034.6  147.57  5079.2  148.54  5086.1  148.07
  5123.8   150.4    5159  154.35  5175.9  154.88    5288  168.06  5346.9  173.07
#Mann= 5 ,-1 , 0
  4489.6     .17       0  4692.2     .15       0    4915     .11       0
  4969.7     .06       0  5034.6     .11       0
Bank Sta=4969.7,5034.6
XS Rating Curve= 0 ,0
Exp/Cntr=0.3,0.1

Type RM Length L Ch R = 1 ,5458    ,479,479,479
BEGIN DESCRIPTION:
WHITE OAK CREEK NORTH 9.0
END DESCRIPTION:
XS GIS Cut Line= 3
      3820617.86     10115161.07      3820008.25     10115185.42
      3819717.84     10115361.08
#Sta/Elev= 30
  4389.9  174.83  4515.1  165.91  4621.4  160.12  4720.2  150.84  4730.2  148.97
  4760.2   147.3  4800.2  145.85  4918.1  145.32  4970.4  145.51  4980.4  143.09
  4995.2  137.72  5012.3  137.72  5019.3  143.56  5034.8  144.93  5047.2  145.97
    5093  155.44  5098.8  155.28  5114.3  158.73  5120.2  158.94  5135.7  162.64
    5157  166.01  5164.1  168.39  5178.4  167.83  5193.9  161.42    5281  161.72
  5304.3  166.11  5316.1  171.52  5331.6  176.31  5336.5  180.18  5339.4  180.18
#Mann= 5 ,-1 , 0
  4389.9     .17       0  4621.4     .15       0  4918.1     .11       0
  4970.4     .06       0  5034.8     .11       0
#Block Obstruct= 2 , 0
       0                  5172.5       0  168.53
Bank Sta=4970.4,5034.8
XS Rating Curve= 0 ,0
Exp/Cntr=0.3,0.1

Type RM Length L Ch R = 1 ,4979    ,499,499,499
BEGIN DESCRIPTION:
WHITE OAK CREEK NORTH 8.0
END DESCRIPTION:
XS GIS Cut Line= 3
      3820299.29     10114437.79      3819925.01     10114724.54
      3819538.83     10114765.92
#Sta/Elev= 30
  4528.5  163.77  4560.2  162.74  4574.7  160.94  4624.6  160.79  4653.6  159.22
  4709.8   154.9  4736.4  151.02  4753.3  148.52  4759.6  149.69  4767.8     148
  4774.1  149.12  4788.7  146.76  4809.5  146.47  4817.7   145.1    4824  145.69
  4882.1   143.5  4959.1  144.89  4967.3  142.51  4973.6  142.37  4981.8  137.14
  4986.5  136.34  5007.2  136.97  5013.3  141.14  5027.3  144.61  5110.5  144.66
  5202.7  154.52  5228.5  160.35  5288.8  166.74    5329  168.81  5388.4  169.84
#Mann= 4 ,-1 , 0
  4528.5     .11       0  4736.4     .15       0  4959.1     .09       0
  5027.3     .11       0
Bank Sta=4959.1,5027.3
XS Rating Curve= 0 ,0
Exp/Cntr=0.3,0.1

Type RM Length L Ch R = 1 ,4480    ,500,500,500
BEGIN DESCRIPTION:
WHITE OAK CREEK NORTH 7.0
END DESCRIPTION:
XS GIS Cut Line= 3
      3820243.51     10114276.09      3819795.31     10114275.29
      3819468.79     10114332.51
#Sta/Elev= 30
  4551.8  167.23  4557.5  167.37  4562.9  166.57  4567.9  167.19  4635.5   162.7
  4657.5  161.01  4677.5  160.74  4767.5  156.13  4837.5  148.63  4887.2  142.39
  4917.5  142.08  4967.5  144.15  4977.5   140.4  4987.6  134.65  5004.8  134.65
  5008.6  136.78  5027.9  138.23    5038  139.77  5048.2  142.81  5088.8  144.41
  5109.1  147.22  5117.3  149.08  5122.4  148.87  5129.4  150.57    5170   155.2
  5190.3  159.49  5230.9  163.15  5236.1  164.46  5295.6  167.66  5331.5  167.34
#Mann= 5 ,-1 , 0
  4551.8     .17       0  4635.5     .11       0  4887.2     .15       0
  4967.5     .09       0  5048.2     .15       0
Bank Sta=4967.5,5048.2
XS Rating Curve= 0 ,0
Exp/Cntr=0.3,0.1

Type RM Length L Ch R = 1 ,3980    ,497,497,497
BEGIN DESCRIPTION:
WHITE OAK CREEK NORTH 6.0
END DESCRIPTION:
XS GIS Cut Line= 3
      3819917.86     10113611.07      3819607.18     10113896.07
      3819456.06     10114197.17
#Sta/Elev= 30
  4578.4  178.67  4613.9   175.3  4620.6  173.39  4668.5  166.58  4727.3  159.04
  4755.1  154.21  4769.3  153.07  4811.8  145.46  4840.2  142.97  4877.4  141.69
  4911.1  139.86  4917.9  140.82  4925.2  140.17  4939.4  136.01  4960.4  141.79
  4967.8  139.12  4974.6  139.87  4987.5  132.58  5004.8  132.58  5027.2  134.74
  5061.5  141.42  5071.8  141.49  5077.4  143.22  5094.2  142.75  5138.8  147.96
  5166.8   152.5  5205.8  155.33  5262.9  161.64  5317.5  165.35  5336.9  165.49
#Mann= 5 ,-1 , 0
  4578.4     .17       0  4668.5     .11       0  4877.4     .15       0
  4960.4     .09       0  5061.5     .15       0
Bank Sta=4960.4,5061.5
XS Rating Curve= 0 ,0
Exp/Cntr=0.3,0.1

Type RM Length L Ch R = 1 ,3483    ,499,499,499
BEGIN DESCRIPTION:
WHITE OAK CREEK NORTH 5.0
END DESCRIPTION:
XS GIS Cut Line= 3
      3819221.16     10113344.02      3819314.97      10113707.1
      3819340.91      10114186.9
#Sta/Elev= 30
    4625  174.58  4629.4  173.24  4675.2  170.25  4776.9  163.76  4868.1     153
  4873.3  153.11  4900.8  147.69  4908.8  144.46    4914  145.49  4931.8  141.37
  4949.4  140.68  4955.9  141.29  4962.8  140.92  4983.4  137.31  4986.6  130.61
  5003.9  130.61  5004.5  131.45    5014  132.77    5024  138.39    5034  140.09
  5084.1  139.23  5094.1  138.32  5142.6   141.4  5147.6     141  5194.3  150.63
  5274.4  157.69  5294.4  157.77  5384.5  162.31  5434.6  163.91  5480.5  164.03
#Mann= 5 ,-1 , 0
    4625     .11       0  4675.2     .17       0  4955.9     .15       0
  4962.8     .09       0    5034     .15       0
Bank Sta=4962.8,5034
XS Rating Curve= 0 ,0
Exp/Cntr=0.3,0.1

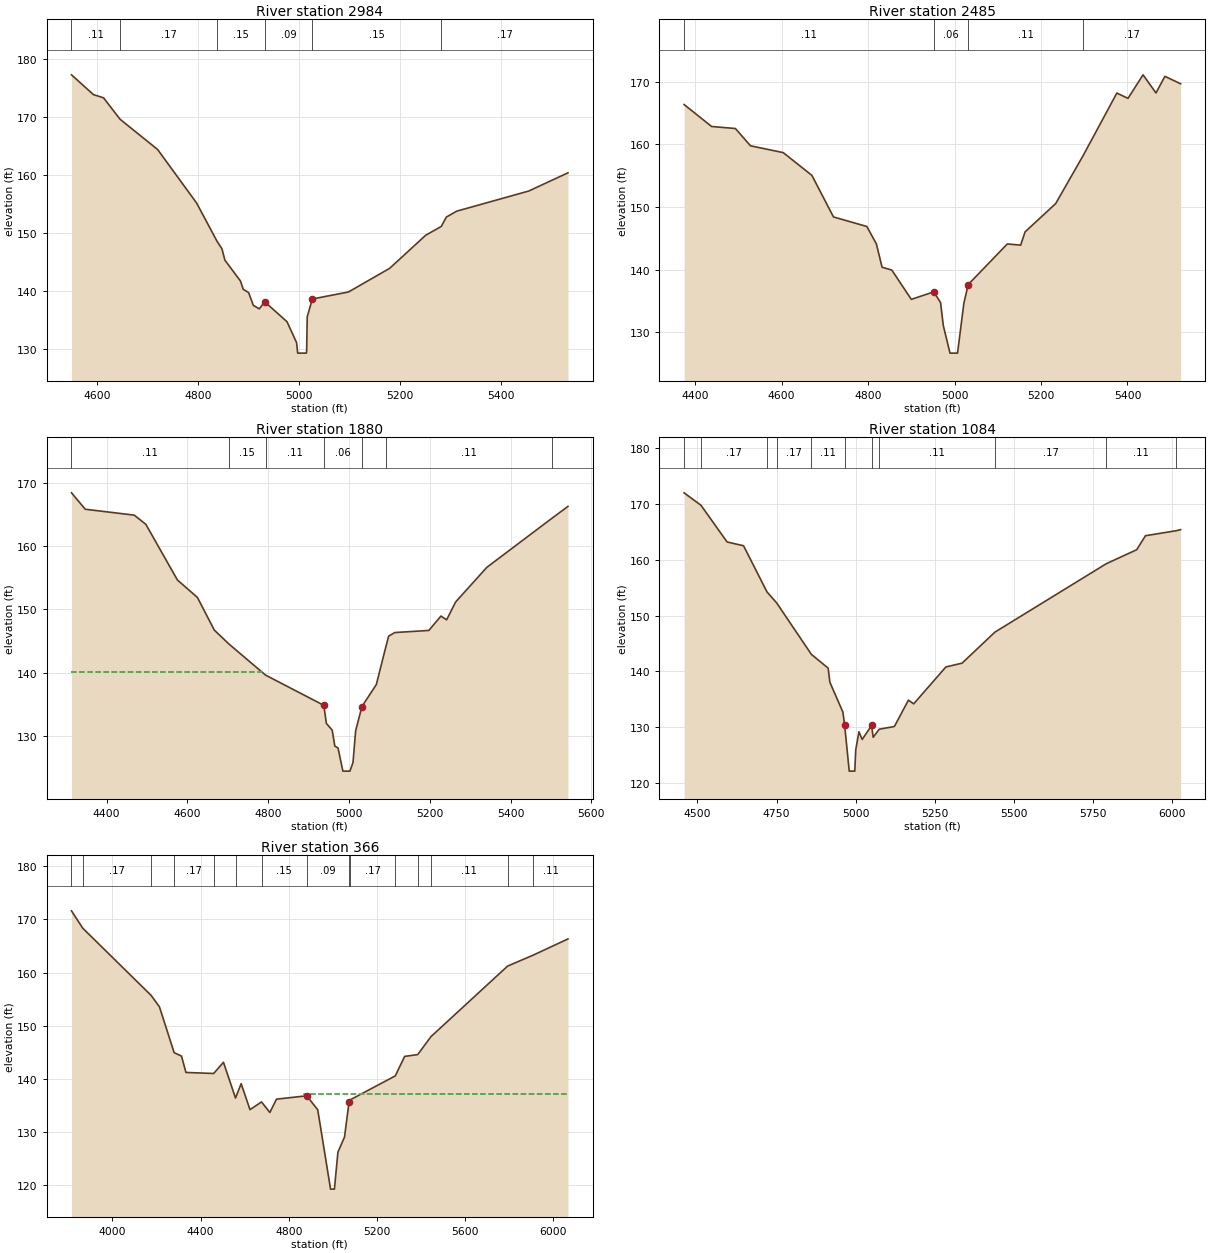
Type RM Length L Ch R = 1 ,2984    ,499,499,499
BEGIN DESCRIPTION:
WHITE OAK CREEK NORTH 4.0
END DESCRIPTION:
XS GIS Cut Line= 3
      3819085.76     10113250.27      3818933.62     10113675.26
      3819043.86     10114197.14
#Sta/Elev= 30
  4548.6  177.26  4592.1  173.85  4612.2  173.29    4645  169.59  4719.4  164.38
  4796.8  155.14  4837.5  148.51  4846.9  147.27    4853  145.27  4883.8  141.68
  4889.3  140.25    4900  139.68  4909.3  137.48  4921.2  136.88  4931.8   138.1
  4976.1  134.66  4995.1  131.05  4997.3  129.24  5014.6  129.24  5015.1  129.74
  5016.2  135.51  5026.4  138.58    5098  139.79  5179.7  143.87  5251.2  149.58
  5282.1   151.1  5292.1  152.71  5312.6  153.73  5455.6  157.21  5533.4  160.35
#Mann= 6 ,-1 , 0
  4548.6     .11       0    4645     .17       0  4837.5     .15       0
  4931.8     .09       0  5026.4     .15       0  5282.1     .17       0
Bank Sta=4931.8,5026.4
XS Rating Curve= 0 ,0
Exp/Cntr=0.3,0.1

Type RM Length L Ch R = 1 ,2485    ,605,605,605
BEGIN DESCRIPTION:
WHITE OAK CREEK NORTH 3.0
END DESCRIPTION:
XS GIS Cut Line= 3
      3818809.69      10113114.9      3818521.26     10113669.71
      3818445.25     10114186.95
#Sta/Elev= 30
  4374.7  166.36  4438.3  162.85  4493.3  162.53  4528.2  159.77  4603.9  158.68
  4670.2  155.05  4720.1  148.41  4797.2  146.89  4819.3  144.11  4832.5  140.38
    4855  139.93  4900.1  135.25    4952  136.45  4967.7  134.75  4974.1  131.07
  4989.6  126.67    5007  126.67  5021.6  134.63  5031.7  137.62  5122.1   144.1
    5153  143.91  5163.1  146.02  5233.9  150.54  5297.8  158.25  5375.4  168.19
  5401.2  167.34    5436   171.1  5465.9   168.2  5486.5  170.86  5522.8  169.67
#Mann= 4 ,-1 , 0
  4374.7     .11       0    4952     .06       0  5031.7     .11       0
  5297.8     .17       0
#XS Ineff= 2 , 0
       0                  5122.1       0   144.1
Permanent Ineff=
       F       F
Bank Sta=4952,5031.7
XS Rating Curve= 0 ,0
Exp/Cntr=0.3,0.1

Type RM Length L Ch R = 1 ,1880    ,796,796,796
BEGIN DESCRIPTION:
WHITE OAK CREEK NORTH 2.0
END DESCRIPTION:
XS GIS Cut Line= 3
      3818590.95     10113015.92       3818060.4     10113452.04
      3817830.54       10113943.
#Sta/Elev= 30
  4313.2   168.4  4347.3  165.81  4468.5  164.88  4497.2  163.44  4575.4  154.65
  4624.9   151.9  4666.7  146.75  4702.4  144.58  4793.5  139.65  4937.7  134.88
  4944.2  132.02  4958.5  130.97    4965  128.45  4972.9  128.15    4985   124.5
  5002.5   124.5    5010  125.87  5016.6  130.87  5032.1  134.69  5067.8  138.16
  5090.6  143.93  5098.3   145.8  5113.5  146.36  5197.7  146.69  5227.7  148.96
  5241.8  148.37  5263.9  151.17  5341.2  156.64  5501.5  164.34  5542.1  166.26
#Mann= 7 ,-1 , 0
  4313.2     .11       0  4702.4     .15       0  4793.5     .11       0
  4937.7     .06       0  5032.1     .15       0  5090.6     .11       0
  5501.5     .17       0
#XS Ineff= 2 , 0
       0  4787.8  140.08               0
Permanent Ineff=
       F       F
Bank Sta=4937.7,5032.1
XS Rating Curve= 0 ,0
Exp/Cntr=0.3,0.1

Type RM Length L Ch R = 1 ,1084    ,718,718,718
BEGIN DESCRIPTION:
WHITE OAK CREEK NORTH 2.5
END DESCRIPTION:
XS GIS Cut Line= 3
      3818278.43     10112661.76      3817782.62      10112881.2
      3817597.39     10113890.14
#Sta/Elev= 30
  4457.8     172  4511.2  169.76  4593.6  163.19  4645.6  162.51  4719.5  154.24
    4750  152.28  4859.7  143.05  4912.7  140.58  4918.2  138.04  4959.3   132.7
  4964.8  130.35  4979.3  122.12  4996.8  122.12  4999.9  125.95    5010  129.18
  5020.2   127.8  5049.9   130.3  5054.9  128.19    5074  129.63  5121.9  130.12
  5166.2  134.84  5182.9  134.18  5284.5  140.79  5335.7  141.47  5439.3  147.03
  5791.3   159.3  5887.1   161.8  5914.9  164.31  6012.1  165.21  6025.8   165.4
#Mann= 11 ,-1 , 0
  4457.8     .11       0  4511.2     .17       0  4719.5     .11       0
    4750     .17       0  4859.7     .11       0  4964.8     .09       0
  5049.9     .15       0    5074     .11       0  5439.3     .17       0
  5791.3     .11       0  6012.1     .17       0
Bank Sta=4964.8,5049.9
XS Rating Curve= 0 ,0
Exp/Cntr=0.3,0.1

Type RM Length L Ch R = 1 ,366     ,0,0,0
BEGIN DESCRIPTION:
WHITE OAK CREEK NORTH 1.0
END DESCRIPTION:
XS GIS Cut Line= 4
      3818266.11     10112598.44      3817290.65     10112651.39
      3817298.62     10112859.74      3817541.16     10113897.78
#Sta/Elev= 30
  3814.6  171.63  3865.4  168.37  4175.5   155.7  4213.4  153.54  4280.1   144.9
  4313.6  144.24  4333.6  141.16  4459.4  140.97  4503.8  143.08  4558.4  136.34
    4584  139.05  4624.1  134.15  4676.3  135.61  4714.2  133.62  4744.2  136.13
  4881.2  136.76  4931.3  134.13  4989.4  119.17  5006.9  119.17  5022.8  126.14
  5052.7  128.99  5073.3  135.59    5079  136.01  5282.8  140.51  5325.5  144.19
  5384.7  144.53  5444.3   147.9  5792.2  161.21  5908.5  163.28    6066  166.33
#Mann= 15 ,-1 , 0
  3814.6     .11       0  3865.4     .17       0  4175.5     .11       0
  4280.1     .17       0  4459.4     .11       0  4558.4     .17       0
  4676.3     .15       0  4881.2     .09       0  5073.3     .15       0
    5079     .17       0  5282.8     .11       0  5384.7     .17       0
  5444.3     .11       0  5792.2     .17       0  5908.5     .11       0
#XS Ineff= 2 ,-1
    4584  4503.8  139.05  4871.2    4584  137.13
Permanent Ineff=
       F       F
Bank Sta=4881.2,5073.3
XS Rating Curve= 0 ,0
Exp/Cntr=0.3,0.1

Chan Stop Cuts=-1
Use User Specified Reach Order=0
Composite Channel Slope=5