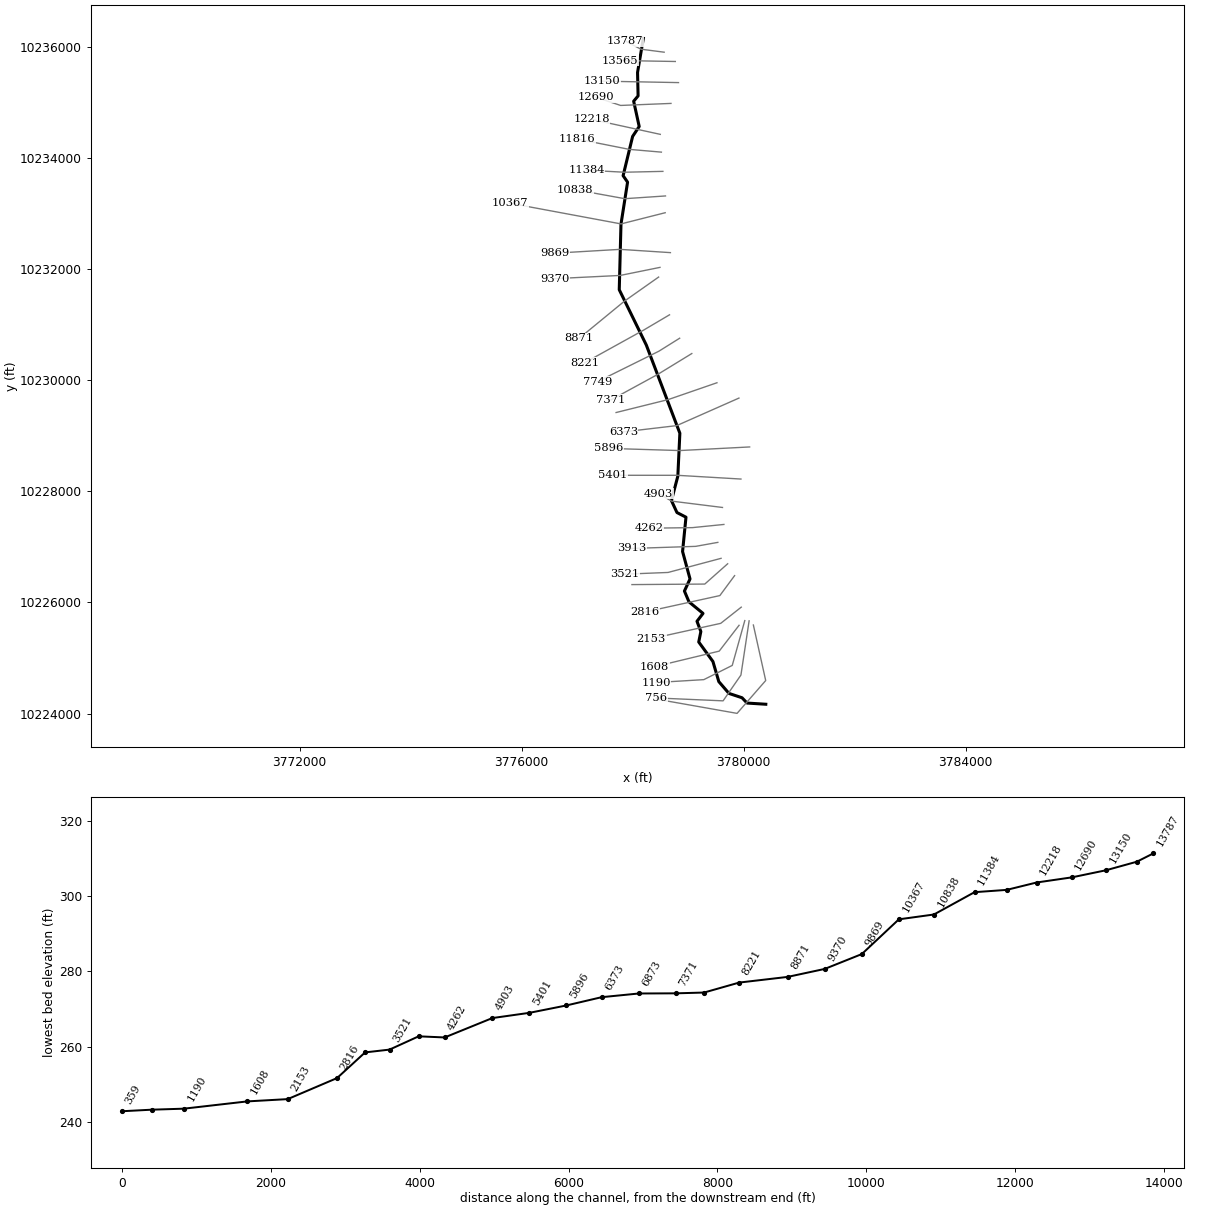
--- BLACK BRANCH.prj (project) ---

Proj Title=BLACK BRANCH Base Level Engineering
Current Plan=p01
Default Exp/Contr=0.3,0.1
English Units
Geom File=g01
Flow File=f01
Plan File=p01
Y Axis Title=Elevation
X Axis Title(PF)=Main Channel Distance
X Axis Title(XS)=Station
BEGIN DESCRIPTION:
BLACK BRANCH
END DESCRIPTION:
DSS Export Rating Curves= 0
DSS Export Rating Curve Sorted= 0
DSS Export Volume Flow Curves= 0
DXF OffsetX= 0
DXF OffsetY= 0
DXF ScaleX= 1
DXF ScaleY= 10

--- BLACK BRANCH.p01 (plan) ---

Plan Title=Multiple Run
Program Version=4.10
Short Identifier=Multiple
Geom File=g01
Flow File=f01
Subcritical Flow
K Sum by GR= 0
Std Step Tol= 0.01
Critical Tol= 0.01
Num of Std Step Trials= 20
Max Error Tol= 0.3
Flow Tol Ratio= 0.001
Split Flow NTrial= 30
Split Flow Tol= 0.02
Split Flow Ratio= 0.02
Log Output Level= 0
Friction Slope Method= 1
Unsteady Friction Slope Method= 2
Unsteady Bridges Friction Slope Method= 1
Parabolic Critical Depth
Global Vel Dist= 1 , 1 , 1
Global Log Level= 0
CheckData=True
Encroach Param=-1 ,0,0, 0
BEGIN DESCRIPTION:
Multiple Run
END DESCRIPTION:
Computation Interval=1HOUR
Output Interval=1HOUR
Run HTab= 0
Run UNet= 0
Run PostProcess= 0
Run WQNet= 0
UNET Theta= 1
UNET Theta Warmup= 1
UNET ZTol= 0.02
UNET ZSATol= 0.05
UNET MxIter= 20
UNET MaxInSteps= 0
UNET DtIC= 0
UNET DtMin= 0
UNET MaxCRTS= 20
UNET WFStab= 2
UNET SFStab= 1
UNET WFX= 1
UNET SFX= 1
UNET DSS MLevel= 4
UNET DZMax Abort= 100
UNET Convert EG Bridges= 0
UNET Use Existing IB Tables=-1
UNET Froude Reduction=False
UNET Froude Limit= 1
UNET Froude Power= 10
UNET Time Slicing=0,0, 5
UNET Junction Losses=0
Instantaneous Interval=1HOUR
Write IC File= 0
Write IC File at Sim End=0
Echo Input=False
Echo Parameters=False
Echo Output=False
Write Detailed= 0
WQ AD Non Conservative
WQ ULTIMATE=-1
WQ Max Comp Step=1HOUR
WQ Output Interval=15MIN
WQ Output Selected Increments= 0
WQ Output face flow=0
WQ Output face velocity=0
WQ Output face area=0
WQ Output face dispersion=0
WQ Output cell volume=0
WQ Output cell surface area=0
WQ Output cell continuity=0
WQ Output cumulative cell continuity=0
WQ Output face conc=0
WQ Output face dconc_dx=0
WQ Output face courant=0
WQ Output face peclet=0
WQ Output face adv mass=0
WQ Output face disp mass=0
WQ Output cell mass=0
WQ Output cell source sink temp=0
WQ Output cell source sink nsm=0
WQ Output MaxMinRange=-1
WQ Daily Max Min Mean=-1
WQ Daily Range=0
WQ Daily Time=0
WQ Create Restart=0
WQ Fixed Restart=0
WQ System Summary=0
WQ Use Fixed Temperature=0
Sorting and Armoring Iterations= 10
XS Update Threshold= 0.02
Hydraulics Update Threshold= 0.02
Energy Slope Method= 1
Volume Change Method= 0
XS Weighting Method= 0
Number of US Weighted Cross Sections= 1
Number of DS Weighted Cross Sections= 1
Upstream XS Weight=0.25
Main XS Weight=0.5
Downstream XS Weight=0.25
Number of DS XS's Weighted with US Boundary= 1
Upstream Boundary Weight= 1
Weight of XSs Associated with US Boundary= 0
Number of US XS's Weighted with DS Boundary= 1
Downstream Boundary Weight= 0.5
Weight of XSs Associated with DS Boundary= 0.5
Sediment Output Level= 4
Mass or Volume Output= 0
Output Increment Type= 1
Profile and TS Output Increment= 10
XS Output Flag= 0
XS Output Increment= 10
Disregard all LS=0
Disregard all Conn=0
Disregard all Breaches=0
Disregard all Pumps=0

--- BLACK BRANCH.f01 (steady flow) ---

Flow Title=Multiple
Program Version=4.10
Number of Profiles= 7
Profile Names=10-year,25-year,50-year,1pct_min,100-year,1pct_plu,500-year
River Rch & RM=BLACK BRANCH,Reach-1         ,13787
    1197    1676    2315    1050    3172    9579    6161
Boundary for River Rch & Prof#=BLACK BRANCH,Reach-1         , 1
Up Type= 0
Dn Type= 3
Dn Slope=0.001
Boundary for River Rch & Prof#=BLACK BRANCH,Reach-1         , 2
Up Type= 0
Dn Type= 3
Dn Slope=0.001
Boundary for River Rch & Prof#=BLACK BRANCH,Reach-1         , 3
Up Type= 0
Dn Type= 3
Dn Slope=0.001
Boundary for River Rch & Prof#=BLACK BRANCH,Reach-1         , 4
Up Type= 0
Dn Type= 3
Dn Slope=0.001
Boundary for River Rch & Prof#=BLACK BRANCH,Reach-1         , 5
Up Type= 0
Dn Type= 3
Dn Slope=0.001
Boundary for River Rch & Prof#=BLACK BRANCH,Reach-1         , 6
Up Type= 0
Dn Type= 3
Dn Slope=0.001
Boundary for River Rch & Prof#=BLACK BRANCH,Reach-1         , 7
Up Type= 0
Dn Type= 3
Dn Slope=0.001
DSS Import GetInterval= 0
DSS Import GetPeak= 0
DSS Import FillOption= 0

--- BLACK BRANCH.g01 (geometry) ---

Geom Title=Existing Conditions
Program Version=4.10

River Reach=BLACK BRANCH    ,Reach-1
Reach XY= 30
      3778192.74     10236160.72      3778088.34     10235546.58
      3778097.95     10235123.88      3778018.33      10235028.2
      3778117.96     10234573.02       3777999.6      10234394.4
      3777828.35     10233686.61      3777908.53     10233570.58
      3777789.75     10232812.69      3777758.61     10231632.96
       3778246.2     10230635.99      3778850.25     10229048.34
      3778813.81     10228275.09      3778698.57      10227834.9
      3778797.91     10227619.82      3778960.45     10227535.89
      3778899.16     10226917.73      3779033.42     10226423.45
      3778932.49     10226205.73      3779014.71     10226010.63
      3779267.55     10225803.21      3779158.77     10225660.72
       3779228.4     10225476.41      3779190.31     10225287.69
      3779445.73     10224936.76      3779551.81     10224574.47
      3779734.96     10224361.72      3779969.81     10224283.93
      3780060.69     10224188.16      3780398.23     10224166.84

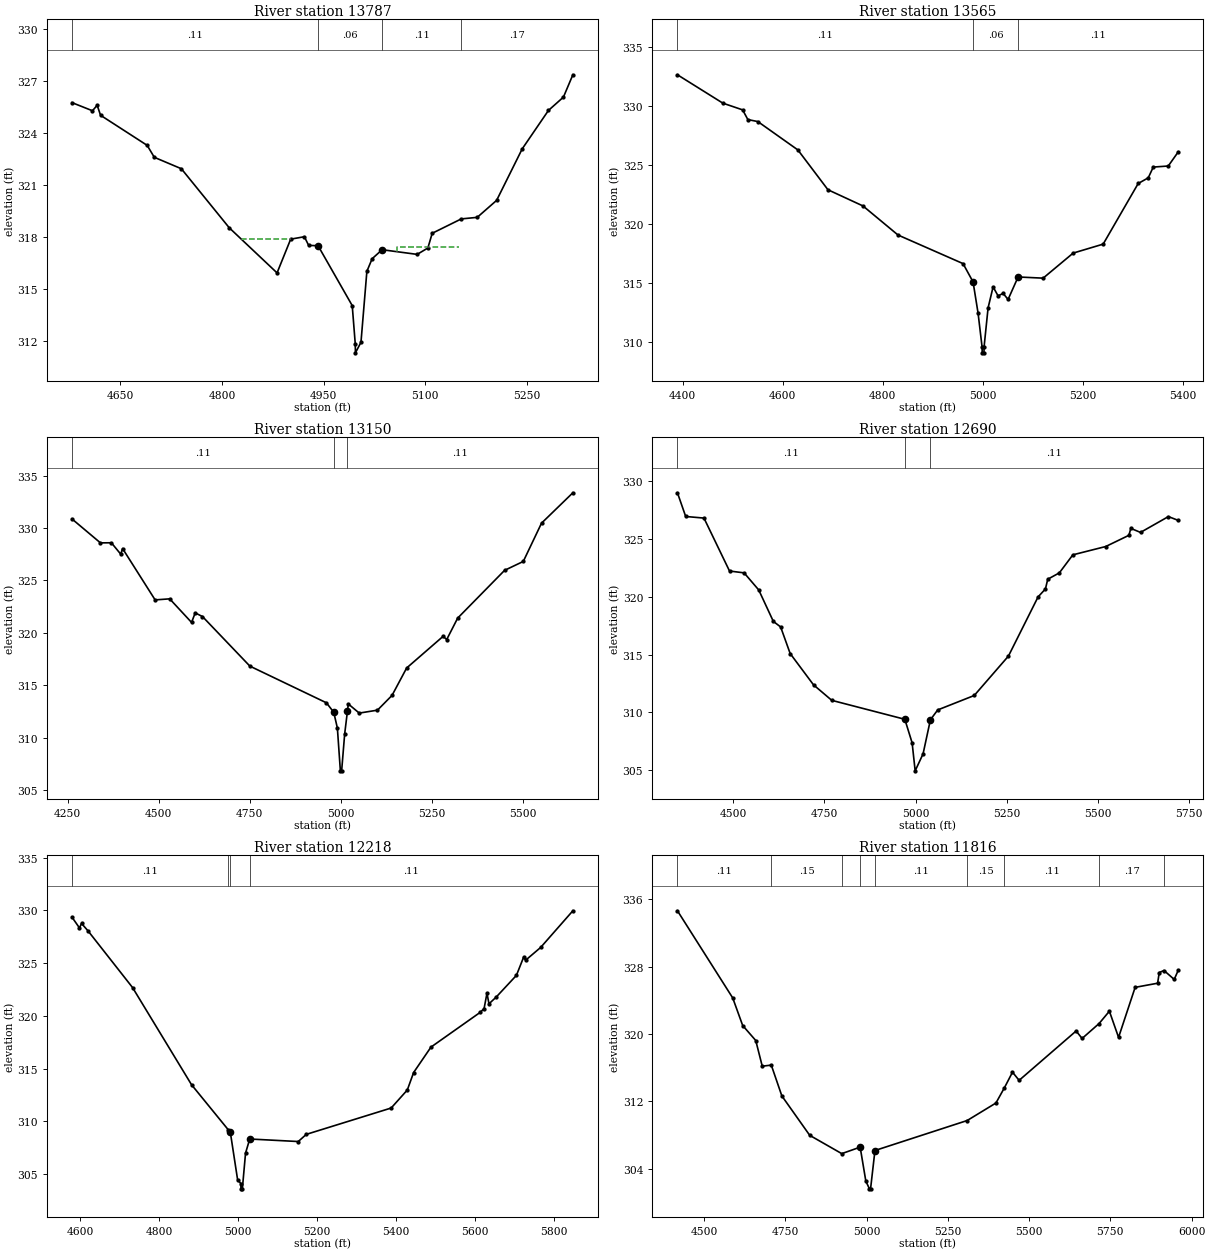
Type RM Length L Ch R = 1 ,13787   ,222,222,222
BEGIN DESCRIPTION:
BLACK BRANCH 26.0
END DESCRIPTION:
XS GIS Cut Line= 3
      3778567.81     10235911.08        3778150.     10235965.17
      3777867.88     10236111.05
#Sta/Elev= 30
  4578.7  325.77  4608.9   325.3  4615.8  325.62  4620.8  325.04  4689.6   323.3
  4700.1  322.61    4740  321.95  4810.6  318.54  4881.2  315.93  4901.3  317.88
  4921.5  318.02  4927.8  317.52  4941.7   317.5  4992.1  314.04  4996.6  311.81
  4996.8  311.31    5005  311.92  5013.7  316.02  5021.5  316.75  5036.2  317.27
  5087.9     317  5103.7  317.37  5110.1  318.22    5153  319.05  5176.5  319.14
  5205.1  320.12  5242.9   323.1  5281.6  325.32  5303.7  326.09  5317.6  327.38
#Mann= 4 ,-1 , 0
  4578.7     .11       0  4941.7     .06       0  5036.2     .11       0
    5153     .17       0
#XS Ineff= 2 ,-1
    4830  4901.3  317.88  5058.7    5150  317.43
Permanent Ineff=
       F       F
Bank Sta=4941.7,5036.2
XS Rating Curve= 0 ,0
Exp/Cntr=0.3,0.1

Type RM Length L Ch R = 1 ,13565   ,415,415,415
BEGIN DESCRIPTION:
BLACK BRANCH 25.0
END DESCRIPTION:
XS GIS Cut Line= 2
      3778768.56     10235743.73      3777767.81     10235761.07
#Sta/Elev= 30
  4389.8  332.63  4480.5  330.23  4520.1  329.66  4530.5  328.84  4550.5  328.67
  4630.5  326.27  4690.6   322.9  4760.6  321.53  4830.6  319.07  4960.6  316.65
  4980.6   315.1  4990.6  312.46  4998.6   309.6  4998.9   309.1  5002.4   309.1
  5002.6   309.6  5010.6   312.9  5020.6  314.68  5030.6  313.92  5040.6  314.13
  5050.6  313.62  5070.6  315.52  5120.6  315.42  5180.6  317.54  5240.6   318.3
  5310.6  323.43  5330.7  323.91  5340.7  324.82  5370.7  324.91  5390.7  326.11
#Mann= 3 , 0 , 0
  4389.8     .11       0  4980.6     .06       0  5070.6     .11       0
Bank Sta=4980.6,5070.6
XS Rating Curve= 0 ,0
Exp/Cntr=0.3,0.1

Type RM Length L Ch R = 1 ,13150   ,460,460,460
BEGIN DESCRIPTION:
Mapping XS 192d6fbc
END DESCRIPTION:
XS GIS Cut Line= 2
      3778825.81     10235363.53      3777451.86     10235389.55
#Sta/Elev= 30
  4262.2  330.86  4340.2  328.58  4370.2  328.59  4395.9   327.5  4400.9  328.04
  4490.2  323.14  4530.2  323.24  4590.2  320.99  4600.2   321.9  4620.2  321.55
  4750.2  316.82  4960.3  313.32  4980.3  312.42  4990.3  310.91  4998.5  306.83
    5002  306.83  5010.3  310.35    5018 312.552  5020.3  313.21  5050.3  312.34
  5100.3  312.62  5140.3  314.03  5180.3  316.64  5280.3  319.66  5290.3  319.36
  5320.3   321.4  5449.1  325.96  5500.4  326.81  5550.4  330.46  5636.4  333.36
#Mann= 3 , 0 , 0
  4262.2     .11       0  4980.3     .06       0    5018     .11       0
Bank Sta=4980.3,5018
XS Rating Curve= 0 ,0
Exp/Cntr=0.3,0.1

Type RM Length L Ch R = 1 ,12690   ,472,472,472
BEGIN DESCRIPTION:
BLACK BRANCH 24.0
END DESCRIPTION:
XS GIS Cut Line= 3
      3778690.45     10234988.53      3777784.15     10234952.07
      3777342.14     10235097.67
#Sta/Elev= 30
  4347.3     329  4369.9  326.95    4420  326.81    4490  322.23    4530  322.07
  4570.1  320.59  4610.1  317.87  4630.1  317.39  4656.2  315.09  4720.2  312.38
  4770.2  311.04  4970.4   309.4  4990.4  307.36  4998.7  304.94  5020.4  306.41
  5040.5  309.36  5060.5  310.21  5160.6  311.46  5254.3  314.87  5335.5  319.99
  5355.7  320.68    5362  321.52  5393.8  322.07  5430.8  323.63  5520.9  324.35
  5584.4  325.32  5589.7  325.92  5616.2  325.57  5692.6  326.94  5719.7  326.61
#Mann= 3 , 0 , 0
  4347.3     .11       0  4970.4     .06       0  5040.5     .11       0
Bank Sta=4970.4,5040.5
XS Rating Curve= 0 ,0
Exp/Cntr=0.3,0.1

Type RM Length L Ch R = 1 ,12218   ,402,402,402
BEGIN DESCRIPTION:
BLACK BRANCH 23.0
END DESCRIPTION:
XS GIS Cut Line= 2
      3778497.71     10234431.23      3777258.16     10234702.06
#Sta/Elev= 30
  4579.6  329.36  4598.5  328.34  4603.7  328.77  4620.4  328.05    4733  322.68
  4882.4  313.46  4975.3  309.19  4980.4  309.01  4999.1  304.44  5007.4  304.08
  5007.6  303.58  5011.1  303.58  5019.2  306.97  5029.8  308.31  5152.7  308.07
  5173.1  308.75  5388.1  311.25    5429  312.96    5445  314.62  5488.9  317.03
  5613.3  320.32  5623.5  320.69  5630.8  322.14  5635.9  321.14  5654.2  321.78
  5705.4  323.84  5723.7  325.57  5728.8  325.28  5766.8  326.49  5848.4  329.97
#Mann= 4 ,-1 , 0
  4579.6     .11       0  4975.3     .09       0  4980.4     .06       0
  5029.8     .11       0
Bank Sta=4980.4,5029.8
XS Rating Curve= 0 ,0
Exp/Cntr=0.3,0.1

Type RM Length L Ch R = 1 ,11816   ,432,432,432
BEGIN DESCRIPTION:
BLACK BRANCH 22.0
END DESCRIPTION:
XS GIS Cut Line= 3
      3778517.83     10234111.07      3777938.18     10234161.04
      3776997.66     10234347.91
#Sta/Elev= 30
  4418.2  334.63  4588.3  324.28  4618.9  321.01  4659.1  319.23  4679.1  316.18
  4706.9  316.31  4739.4  312.65  4825.2  307.97  4923.7   305.8  4980.3  306.57
  4997.7  302.55  5008.8  301.62  5012.3  301.62  5025.8  306.17  5309.5  309.73
    5398  311.81  5424.2  313.63  5448.9  315.47  5469.3   314.5  5644.7  320.36
    5663  319.47  5715.2  321.24    5747  322.71  5775.2   319.6  5826.2  325.54
  5895.3  326.03  5900.4   327.3    5915  327.54  5946.4  326.48  5958.9  327.58
#Mann= 9 ,-1 , 0
  4418.2     .11       0  4706.9     .15       0  4923.7     .11       0
  4980.3     .06       0  5025.8     .11       0  5309.5     .15       0
  5424.2     .11       0  5715.2     .17       0    5915     .11       0
Bank Sta=4980.3,5025.8
XS Rating Curve= 0 ,0
Exp/Cntr=0.3,0.1

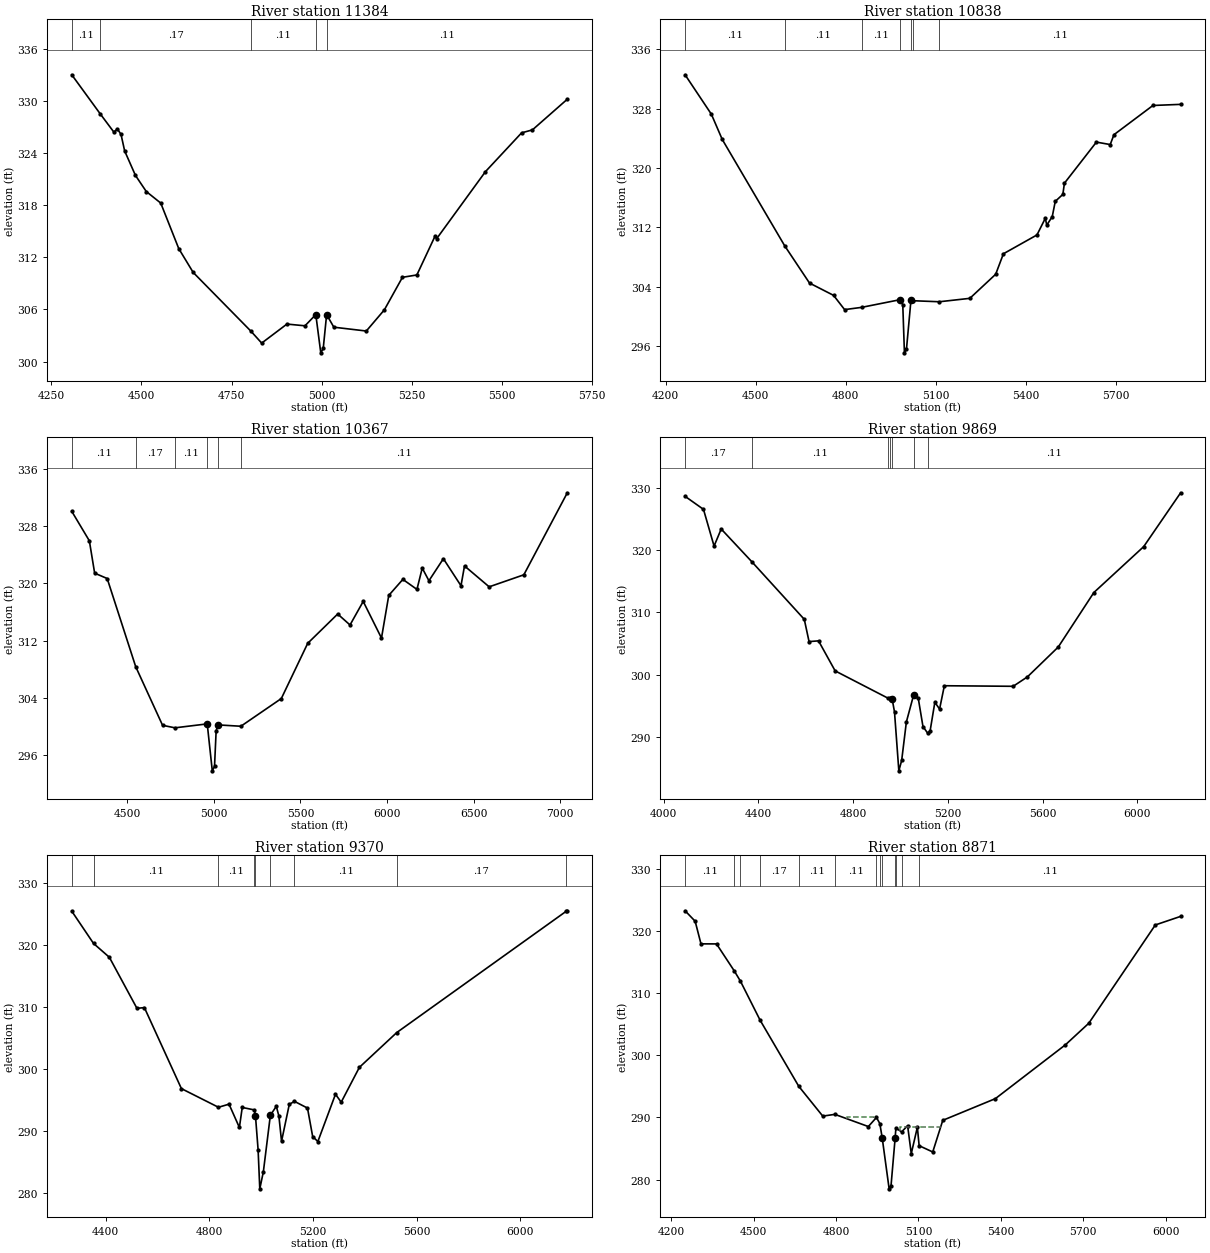
Type RM Length L Ch R = 1 ,11384   ,546,546,546
BEGIN DESCRIPTION:
BLACK BRANCH 21.0
END DESCRIPTION:
XS GIS Cut Line= 3
      3778544.55     10233764.57      3777851.62     10233749.13
      3777171.18     10233785.31
#Sta/Elev= 30
  4306.9     333  4386.1  328.49  4423.6  326.41  4433.6  326.77  4443.6  326.13
  4453.6  324.24  4483.6  321.42  4513.6  319.57  4553.7  318.24  4603.7     313
  4643.7  310.26  4804.1  303.49  4833.7  302.13  4903.7  304.32  4953.8  304.12
  4983.8  305.41  4997.6  301.01  5004.4  301.51  5013.8  305.41  5033.8  303.96
  5123.9  303.52    5174  305.96  5224.1   309.7  5264.1  309.97  5314.1   314.4
  5319.1  314.15  5454.4  321.86  5554.6  326.32  5584.6  326.66  5681.4  330.19
#Mann= 5 ,-1 , 0
  4306.9     .11       0  4386.1     .17       0  4804.1     .11       0
  4983.8     .06       0  5013.8     .11       0
Bank Sta=4983.8,5013.8
XS Rating Curve= 0 ,0
Exp/Cntr=0.3,0.1

Type RM Length L Ch R = 1 ,10838   ,471,471,471
BEGIN DESCRIPTION:
BLACK BRANCH 20.0
END DESCRIPTION:
XS GIS Cut Line= 3
      3778591.39     10233321.86      3777858.25     10233272.53
        3776957.     10233436.26
#Sta/Elev= 30
  4265.2  332.58  4352.7  327.27    4389  323.86  4596.8  309.53  4679.7  304.49
  4759.9  302.83  4796.6  300.91  4852.9  301.21  4980.4  302.24  4990.4  301.57
  4995.9  295.08  5002.7  295.58  5017.7   302.2  5022.8  302.11  5112.2  301.97
  5213.8  302.43  5299.9  305.68  5325.6  308.44  5437.4  310.98  5465.1  313.22
  5470.2  312.31  5488.3  313.45  5498.4  315.51  5523.6  316.45  5528.9  317.96
  5635.4   323.5  5681.4  323.17  5693.9   324.5  5823.7  328.44    5916  328.59
#Mann= 7 ,-1 , 0
  4265.2     .11       0  4596.8     .11       0  4852.9     .11       0
  4980.4     .06       0  5017.7     .09       0  5022.8     .11       0
  5112.2     .11       0
Bank Sta=4980.4,5017.7
XS Rating Curve= 0 ,0
Exp/Cntr=0.3,0.1

Type RM Length L Ch R = 1 ,10367   ,498,498,498
BEGIN DESCRIPTION:
BLACK BRANCH 19.0
END DESCRIPTION:
XS GIS Cut Line= 3
      3778586.22     10233019.77      3777791.15      10232818.3
      3775784.18     10233191.65
#Sta/Elev= 30
  4179.8  330.06  4281.4  325.94    4312  321.42  4384.4  320.67  4549.1  308.35
  4704.2  300.16  4775.9  299.81  4962.1  300.36  4991.3   293.8  5004.2  294.42
  5013.5  299.36  5023.7  300.22  5156.4  300.03  5389.9   303.9  5542.4  311.62
  5715.4  315.71  5786.6  314.18  5862.8  317.47  5968.3  312.35  6010.3  318.31
  6091.7  320.55  6173.1  319.15  6203.6  322.13  6242.3  320.36  6325.7  323.44
  6427.4  319.66  6447.7  322.43  6590.1  319.51  6790.3  321.19  7041.4  332.65
#Mann= 6 ,-1 , 0
  4179.8     .11       0  4549.1     .17       0  4775.9     .11       0
  4962.1     .06       0  5023.7     .11       0  5156.4     .11       0
Bank Sta=4962.1,5023.7
XS Rating Curve= 0 ,0
Exp/Cntr=0.3,0.1

Type RM Length L Ch R = 1 ,9869    ,499,499,499
BEGIN DESCRIPTION:
BLACK BRANCH 18.0
END DESCRIPTION:
XS GIS Cut Line= 3
      3778680.01     10232301.02      3777772.31     10232359.89
      3776592.14     10232290.65
#Sta/Elev= 30
  4090.4   328.6  4168.1  326.51  4212.8  320.62  4242.9  323.36  4372.4   318.1
  4593.6  308.87  4613.7   305.3  4653.7  305.42  4723.9   300.6  4945.2  296.26
  4954.4  296.27  4964.4  296.11  4974.4  294.02  4992.7  284.57  5004.7  286.25
  5024.5  292.41  5054.6  296.66  5074.6  296.23  5094.6  291.67  5114.7   290.6
  5124.7  290.97  5144.7  295.57  5164.7  294.48  5184.8  298.22  5475.3  298.13
  5535.4  299.64  5665.6  304.43  5815.9  313.17  6026.2  320.53  6182.2  329.17
#Mann= 7 ,-1 , 0
  4090.4     .17       0  4372.4     .11       0  4945.2     .11       0
  4954.4     .09       0  4964.4     .06       0  5054.6     .11       0
  5114.7     .11       0
#XS Ineff= 1 ,-1
  5074.6    5175  296.23
Permanent Ineff=
       F
Bank Sta=4964.4,5054.6
XS Rating Curve= 0 ,0
Exp/Cntr=0.3,0.1

Type RM Length L Ch R = 1 ,9370    ,499,499,499
BEGIN DESCRIPTION:
BLACK BRANCH 17.0
END DESCRIPTION:
XS GIS Cut Line= 3
      3778492.46      10232035.4      3777776.81     10231890.33
      3776596.64     10231832.28
#Sta/Elev= 30
  4269.8  325.42  4353.8  320.21  4414.8  317.98  4521.3  309.74    4550  309.86
  4692.8  296.79  4835.7  293.78  4876.5  294.28  4916.5  290.52  4927.5  293.75
  4974.5  293.35  4978.5  292.41  4988.7  286.92  4995.2  280.62    5009  283.38
    5036 292.491    5059  293.94    5069  292.33  5079.1  288.29  5109.1  294.26
  5129.1  294.73  5179.2  293.65  5199.2  289.06  5219.2  288.25  5287.2  295.88
  5309.3   294.6  5379.4  300.22  5523.5  305.83  6177.3   325.4  6181.6  325.48
#Mann= 9 ,-1 , 0
  4269.8     .17       0  4353.8     .11       0  4835.7     .11       0
  4974.5     .11       0  4978.5     .06       0    5036     .11       0
  5129.1     .11       0  5523.5     .17       0  6177.3     .11       0
#XS Ineff= 2 ,-1
    4878  4927.5  293.75    5059    5270  293.94
Permanent Ineff=
       F       F
Bank Sta=4978.5,5036
XS Rating Curve= 0 ,0
Exp/Cntr=0.3,0.1

Type RM Length L Ch R = 1 ,8871    ,650,650,650
BEGIN DESCRIPTION:
BLACK BRANCH 16.0
END DESCRIPTION:
XS GIS Cut Line= 3
      3778467.82     10231861.05      3777854.53       10231429.
       3777039.4     10230759.39
#Sta/Elev= 30
  4249.8  323.23  4286.5  321.55  4307.7  317.91  4364.3   317.9  4428.8  313.57
  4451.3  311.92  4523.2  305.62    4664  294.99  4751.3   290.2  4795.4  290.48
  4917.3  288.52  4946.9  289.98  4959.2     289  4967.9  286.68  4993.1   278.5
    5000     279 5014.98286.6798  5017.7  288.27  5038.6  287.66  5060.4  288.66
  5073.7  284.16  5095.9  288.41  5102.4  285.44  5151.9  284.43  5188.5  289.52
  5380.1  293.01  5635.5  301.68  5720.4  305.14  5962.7  320.95  6054.9  322.33
#Mann= 13 ,-1 , 0
  4249.8     .11       0  4428.8     .17       0  4451.3     .11       0
  4523.2     .17       0    4664     .11       0  4795.4     .11       0
  4946.9     .11       0  4959.2     .11       0  4967.9     .06       0
 5014.98     .09       0  5017.7     .11       0  5038.6     .11       0
  5102.4     .11       0
#XS Ineff= 2 ,-1
    4840  4938.3     290  5032.1    5182   288.4
Permanent Ineff=
       F       F
Bank Sta=4967.9,5014.98
XS Rating Curve= 0 ,0
Exp/Cntr=0.3,0.1

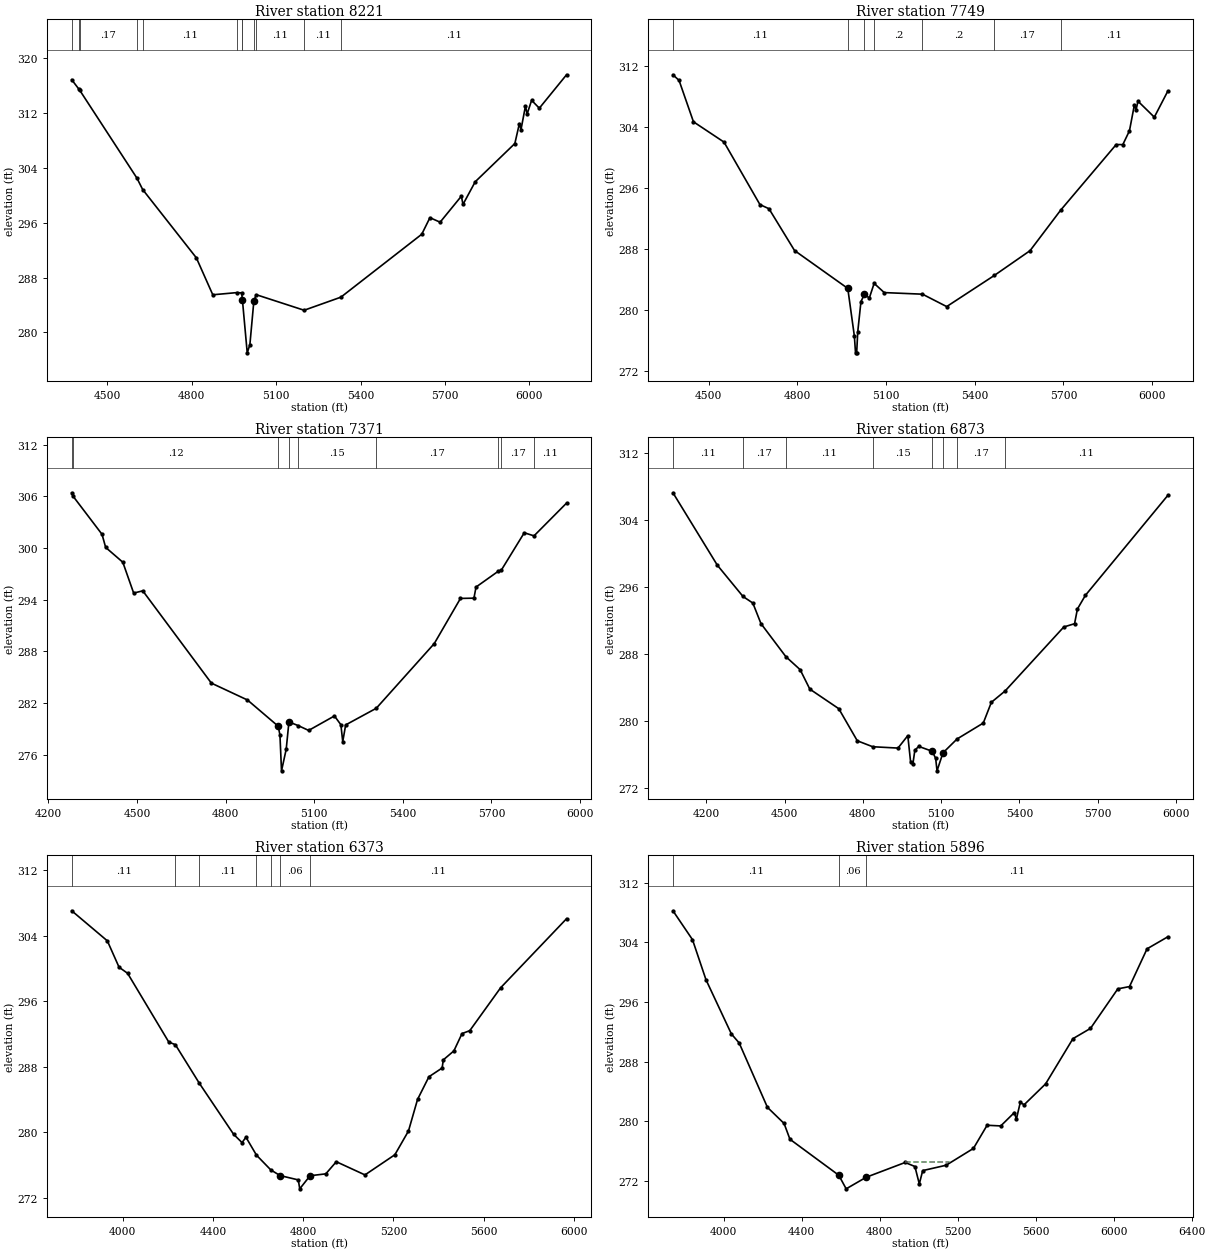
Type RM Length L Ch R = 1 ,8221    ,472,472,472
BEGIN DESCRIPTION:
BLACK BRANCH 15.0
END DESCRIPTION:
XS GIS Cut Line= 3
      3778664.38     10231181.25      3778206.03      10230910.4
      3777133.07     10230316.63
#Sta/Elev= 30
  4373.5  316.89  4398.5  315.54  4401.5  315.38  4605.1  302.53  4625.7  300.85
  4816.4  290.88  4874.9  285.48  4961.3   285.8  4977.5  285.75  4980.4 284.645
  4997.3     277  5006.7  278.18    5021  284.63  5029.5  285.49  5199.6  283.22
  5330.2  285.13  5617.6  294.32  5646.7  296.74  5682.9  296.08  5758.4  299.88
  5764.2  298.68  5807.7  301.99  5948.5  307.57  5964.6  310.48  5970.3  309.59
  5986.3  313.06    5992  311.87  6008.1  313.88  6035.5  312.73  6132.2  317.61
#Mann= 12 ,-1 , 0
  4373.5     .11       0  4398.5     .15       0  4401.5     .17       0
  4605.1     .11       0  4625.7     .11       0  4961.3     .11       0
  4977.5     .09       0  4980.4     .06       0    5021     .09       0
  5029.5     .11       0  5199.6     .11       0  5330.2     .11       0
Bank Sta=4980.4,5021
XS Rating Curve= 0 ,0
Exp/Cntr=0.3,0.1

Type RM Length L Ch R = 1 ,7749    ,378,378,378
BEGIN DESCRIPTION:
BLACK BRANCH 14.0
END DESCRIPTION:
XS GIS Cut Line= 3
      3778846.68     10230759.38      3778471.65     10230524.98
      3777367.51     10229978.12
#Sta/Elev= 30
  4378.8   310.9  4399.5  310.16  4448.2  304.72  4551.6  302.05  4673.1  293.84
  4703.8  293.29  4790.2   287.8  4970.4  282.82  4992.7  276.56  4996.6  274.35
  5000.5  274.35  5004.1   277.1    5015  281.09  5026.6  282.03  5043.4  281.57
  5059.6  283.48  5093.8  282.27  5223.2  282.06  5305.1  280.43  5466.2  284.52
  5587.2  287.78  5690.5  293.09  5878.7  301.73  5901.1  301.72  5923.6  303.54
  5940.4  306.97    5946  306.29  5952.4  307.43  6007.7  305.33  6053.2  308.74
#Mann= 7 ,-1 , 0
  4378.8     .11       0  4970.4     .06       0  5026.6     .11       0
  5059.6      .2       0  5223.2      .2       0  5466.2     .17       0
  5690.5     .11       0
Bank Sta=4970.4,5026.6
XS Rating Curve= 0 ,0
Exp/Cntr=0.3,0.1

Type RM Length L Ch R = 1 ,7371    ,498,498,498
BEGIN DESCRIPTION:
BLACK BRANCH 13.0
END DESCRIPTION:
XS GIS Cut Line= 3
       3779065.4     10230483.32      3778450.37     10230106.86
      3777612.57     10229650.14
#Sta/Elev= 30
  4278.9  306.41  4283.5  306.01  4381.5  301.59  4393.8  300.07  4451.9  298.35
  4488.6  294.77  4519.5  295.03  4751.7  284.32    4874  282.36    4978  279.32
  4983.9  278.29  4989.2  274.14  5005.1  276.65  5014.3  279.82  5046.3  279.38
  5081.1  278.83  5168.4  280.51  5190.2  279.49  5196.5  277.53  5206.4  279.47
    5310   281.4  5506.4  288.91  5595.1  294.15  5640.7  294.18  5647.8  295.47
  5722.1  297.28  5733.9  297.46  5811.1  301.77  5844.1  301.41  5954.2  305.21
#Mann= 9 ,-1 , 0
  4278.9     .15       0  4283.5     .12       0    4978     .07       0
  5014.3     .12       0  5046.3     .15       0    5310     .17       0
  5722.1     .11       0  5733.9     .17       0  5844.1     .11       0
Bank Sta=4978,5014.3
XS Rating Curve= 0 ,0
Exp/Cntr=0.3,0.1

Type RM Length L Ch R = 1 ,6873    ,500,500,500
BEGIN DESCRIPTION:
BLACK BRANCH 12.0
END DESCRIPTION:
XS GIS Cut Line= 3
       3779518.5     10229957.27      3778641.77     10229654.59
      3777701.85     10229421.07
#Sta/Elev= 30
  4072.5  307.21  4242.5  298.59    4341  294.86  4378.6  294.08  4409.8  291.63
  4505.3  287.69  4559.8  286.15    4597  283.83  4707.9   281.5  4778.8  277.68
  4837.9  276.97  4934.8  276.81  4972.4  278.29    4983  275.19  4991.9  274.93
  4999.4  276.55  5014.3  277.01  5065.9  276.43  5079.1  275.59  5084.4   274.1
  5107.1  276.24    5161  277.89  5261.6  279.79  5292.6  282.26  5345.3  283.61
  5570.1  291.23  5611.4  291.62  5622.3  293.37  5652.7  294.99  5968.5  306.89
#Mann= 8 ,-1 , 0
  4072.5     .11       0    4341     .17       0  4505.3     .11       0
  4837.9     .15       0  5065.9     .09       0  5107.1     .15       0
    5161     .17       0  5345.3     .11       0
#XS Ineff= 1 ,-1
    4760  4972.4  278.29
Permanent Ineff=
       F
Bank Sta=5065.9,5107.1
XS Rating Curve= 0 ,0
Exp/Cntr=0.3,0.1

Type RM Length L Ch R = 1 ,6373    ,477,477,477
BEGIN DESCRIPTION:
BLACK BRANCH 11.0
END DESCRIPTION:
XS GIS Cut Line= 3
      3779914.34     10229681.23      3778792.77     10229185.11
      3777831.91     10229071.96
#Sta/Elev= 30
  3773.6  307.06  3931.5  303.39  3983.5  300.17  4021.3  299.43  4204.1  291.03
    4233  290.72  4339.1  286.02  4491.4  279.78  4528.8  278.76  4546.1  279.42
  4592.8  277.23  4656.3  275.43  4697.4  274.74  4778.2  274.21  4784.6  273.12
  4830.4  274.72  4900.1  274.95  4946.7  276.43  5073.8  274.82  5206.3  277.28
  5266.7  280.18    5307  284.04  5357.4   286.8    5416  287.87  5421.1  288.86
  5468.1  289.96  5504.1  292.07  5538.6  292.43  5675.2  297.66  5967.5  306.09
#Mann= 7 ,-1 , 0
  3773.6     .11       0    4233     .17       0  4339.1     .11       0
  4592.8     .17       0  4656.3     .11       0  4697.4     .06       0
  4830.4     .11       0
#XS Ineff= 1 ,-1
  4946.7  5172.7  276.43
Permanent Ineff=
       F
Bank Sta=4697.4,4830.4
XS Rating Curve= 0 ,0
Exp/Cntr=0.3,0.1

Type RM Length L Ch R = 1 ,5896    ,495,495,495
BEGIN DESCRIPTION:
BLACK BRANCH 10.0
END DESCRIPTION:
XS GIS Cut Line= 3
      3780107.08     10228801.03      3778848.25     10228736.06
      3777571.74     10228774.95
#Sta/Elev= 30
  3739.5  308.26  3839.7  304.38  3908.9     299  4039.1  291.72  4079.2   290.5
    4224  281.86  4309.5  279.69  4339.5  277.57  4589.9  272.74  4627.8  270.91
    4730  272.46  4930.3  274.45  4980.4  273.91  5002.9  271.57  5020.4  273.36
  5140.5  274.08  5280.5  276.34  5350.6  279.45  5420.6  279.36  5490.6  281.16
  5500.6  280.25  5520.6  282.51  5540.7  282.21  5650.7  285.01  5790.8  291.08
  5880.8  292.46  6020.9  297.77  6080.9  298.08  6170.9  303.15  6277.1  304.76
#Mann= 3 , 0 , 0
  3739.5     .11       0  4589.9     .06       0    4730     .11       0
#XS Ineff= 1 ,-1
  4930.3    5155  274.45
Permanent Ineff=
       F
Bank Sta=4589.9,4730
XS Rating Curve= 0 ,0
Exp/Cntr=0.3,0.1

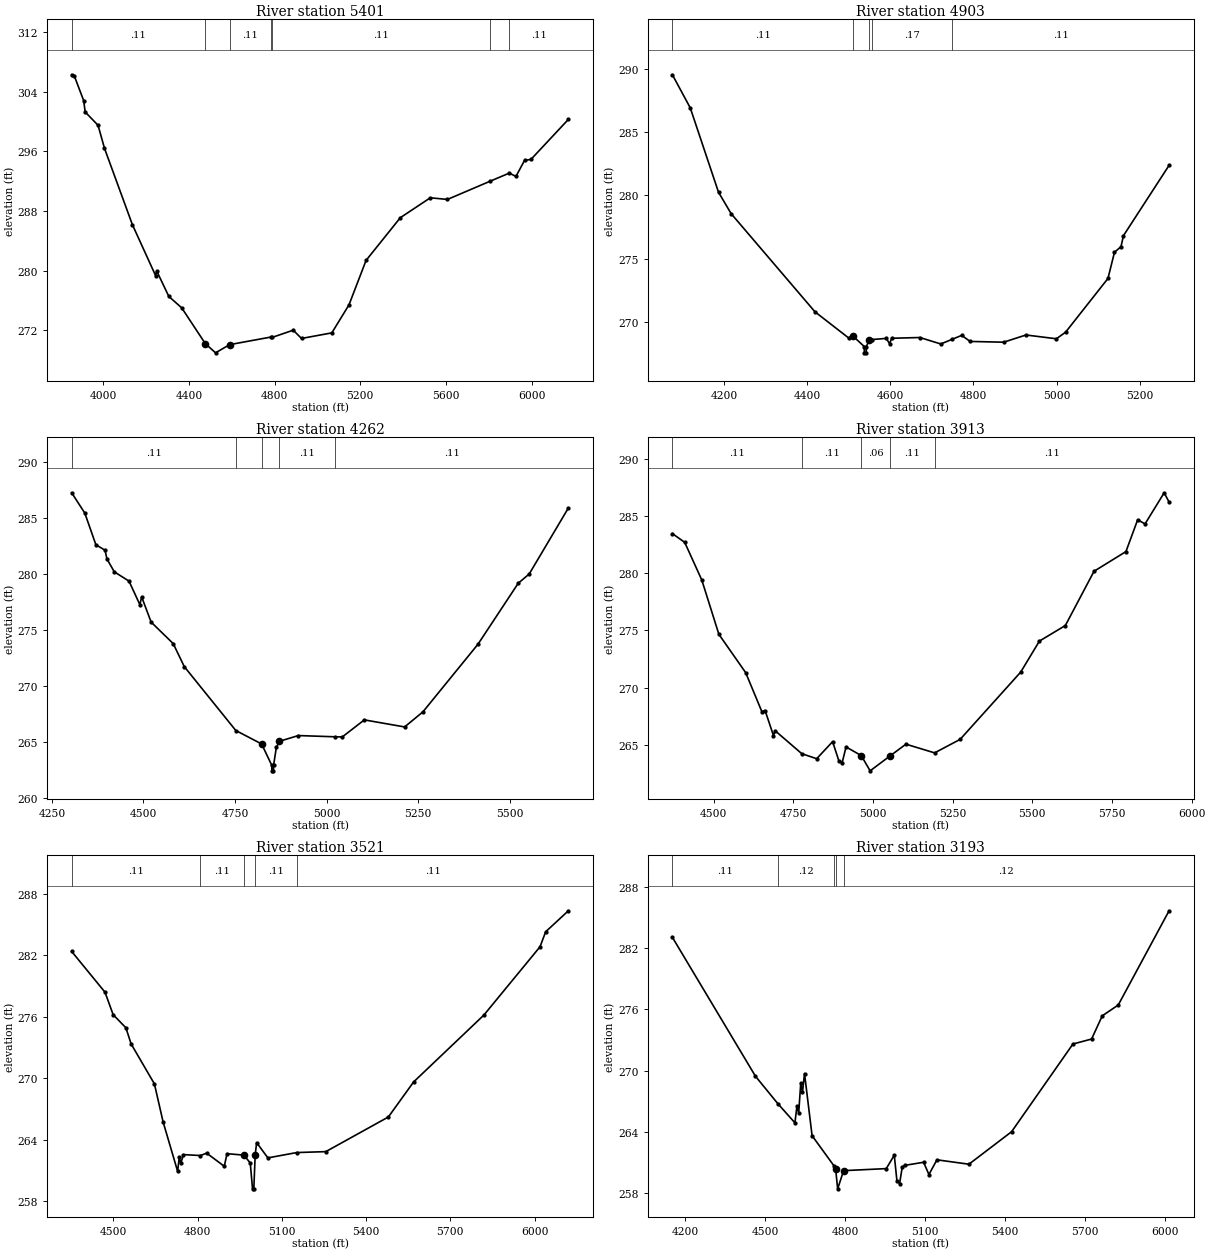
Type RM Length L Ch R = 1 ,5401    ,498,498,498
BEGIN DESCRIPTION:
BLACK BRANCH 9.0
END DESCRIPTION:
XS GIS Cut Line= 3
      3779950.78      10228222.9      3778804.95     10228290.23
      3777633.15     10228290.61
#Sta/Elev= 30
  3852.2  306.28  3865.1  306.08  3908.2  302.81  3915.2  301.29  3975.3   299.5
  4005.4  296.41  4135.6  286.17    4244  279.33    4249  279.96  4305.9  276.53
    4366     275  4476.2   270.2  4524.1  268.96  4589.8  270.06  4784.7  271.09
  4789.2  271.04  4886.9     272  4925.5  270.89  5067.1  271.64  5147.1  275.39
  5227.1  281.37  5387.1   287.1  5527.1  289.77  5607.1  289.55  5806.9     292
  5895.8  293.08  5927.1  292.64  5967.1  294.79  5997.1  294.92  6171.8  300.29
#Mann= 7 ,-1 , 0
  3852.2     .11       0  4476.2     .06       0  4589.8     .11       0
  4784.7     .15       0  4789.2     .11       0  5806.9     .17       0
  5895.8     .11       0
#XS Ineff= 1 ,-1
  4886.9    5080     272
Permanent Ineff=
       F
Bank Sta=4476.2,4589.8
XS Rating Curve= 0 ,0
Exp/Cntr=0.3,0.1

Type RM Length L Ch R = 1 ,4903    ,641,641,641
BEGIN DESCRIPTION:
BLACK BRANCH 8.0
END DESCRIPTION:
XS GIS Cut Line= 3
      3779617.85     10227711.07      3778701.36     10227825.45
      3778467.88     10227961.05
#Sta/Elev= 30
  4076.4  289.52  4119.3  286.91  4187.2  280.25  4217.5  278.56    4419  270.81
  4499.7  268.75  4509.7  268.91  4537.4  268.07  4537.8  267.57  4542.1  267.57
  4542.5  268.07    4550  268.62  4555.9  268.62  4590.4  268.71  4598.3  268.29
  4603.4  268.72    4671  268.78  4721.4  268.27  4748.8  268.64  4771.7  268.95
  4791.9  268.47  4872.5  268.41  4926.1  268.98  4999.2  268.68  5021.3   269.2
  5123.1  273.44  5138.8  275.51  5154.4  275.95  5160.4  276.82    5270  282.37
#Mann= 5 ,-1 , 0
  4076.4     .11       0  4509.7     .06       0    4550     .11       0
  4555.9     .17       0  4748.8     .11       0
Bank Sta=4509.7,4550
XS Rating Curve= 0 ,0
Exp/Cntr=0.3,0.1

Type RM Length L Ch R = 1 ,4262    ,349,349,349
BEGIN DESCRIPTION:
BLACK BRANCH 7.0
END DESCRIPTION:
XS GIS Cut Line= 3
      3779643.54     10227405.19      3779075.82      10227347.9
      3778291.09     10227337.51
#Sta/Elev= 30
  4304.1  287.25    4340  285.43  4370.1  282.61  4395.1  282.12  4400.3  281.34
  4420.4  280.19  4460.6  279.36  4490.1  277.26  4495.1  277.95  4520.9   275.7
  4581.2  273.78  4611.3  271.73    4752  266.02  4822.4  264.82    4850  262.92
  4850.4  262.42  4854.8  262.42  4855.1  262.92  4862.6  264.51  4871.2  265.06
  4922.7  265.57  5022.7  265.46  5042.7  265.45  5102.7  266.97  5212.7  266.34
  5262.7  267.69  5412.7  273.72  5522.7  279.17  5552.7     280  5659.5  285.89
#Mann= 5 ,-1 , 0
  4304.1     .11       0    4752     .11       0  4822.4     .06       0
  4871.2     .11       0  5022.7     .11       0
Bank Sta=4822.4,4871.2
XS Rating Curve= 0 ,0
Exp/Cntr=0.3,0.1

Type RM Length L Ch R = 1 ,3913    ,392,392,392
BEGIN DESCRIPTION:
BLACK BRANCH 6.0
END DESCRIPTION:
XS GIS Cut Line= 3
      3779534.18     10227082.28       3779134.6     10227010.52
      3777982.49     10226972.91
#Sta/Elev= 30
  4370.4  283.45    4409  282.69  4462.6   279.4  4516.3  274.65  4600.4   271.3
  4651.2  267.89  4661.3  267.99  4687.6   265.8  4692.6  266.23  4776.4  264.22
  4823.2  263.78  4873.2  265.27  4893.2  263.56  4903.2  263.44  4915.4  264.81
  4963.2  264.05  4990.9  262.72  5053.3  264.02  5103.3  265.05  5193.3  264.29
  5273.4  265.47  5463.5  271.35  5522.2  274.06  5603.6  275.42  5693.6  280.16
  5793.7  281.88  5830.5  284.66  5853.7   284.3  5913.7  287.02  5929.1  286.21
#Mann= 5 ,-1 , 0
  4370.4     .11       0  4776.4     .11       0  4963.2     .06       0
  5053.3     .11       0  5193.3     .11       0
Bank Sta=4963.2,5053.3
XS Rating Curve= 0 ,0
Exp/Cntr=0.3,0.1

Type RM Length L Ch R = 1 ,3521    ,328,328,328
BEGIN DESCRIPTION:
BLACK BRANCH 5.0
END DESCRIPTION:
XS GIS Cut Line= 3
      3779592.61     10226794.88      3778638.32     10226540.61
      3777857.02     10226509.36
#Sta/Elev= 30
  4351.1  282.35  4469.9  278.37  4498.8  276.18  4544.1  274.91    4563  273.32
  4645.8  269.43  4676.8  265.72  4728.6  260.89  4734.3  262.29  4739.5  261.67
  4749.3  262.53  4809.4  262.44  4832.1  262.67  4894.8  261.39  4904.5  262.62
  4964.7  262.48  4987.3  261.71  4995.4  259.19    5000  259.19  5004.8  262.48
    5010   263.7  5050.1  262.21  5152.9  262.73  5256.4  262.82  5479.3   266.2
  5569.3  269.62  5819.5  276.14  6019.7  282.81  6039.7  284.27  6120.6  286.32
#Mann= 5 ,-1 , 0
  4351.1     .11       0  4809.4     .11       0  4964.7     .06       0
  5004.8     .11       0  5152.9     .11       0
Bank Sta=4964.7,5004.8
XS Rating Curve= 0 ,0
Exp/Cntr=0.3,0.1

Type RM Length L Ch R = 1 ,3193    ,377,377,377
BEGIN DESCRIPTION:
BLACK BRANCH 4.0
END DESCRIPTION:
XS GIS Cut Line= 3
      3779711.25     10226696.87      3779299.23     10226331.42
      3777987.31     10226321.86
#Sta/Elev= 30
  4151.8  283.06  4463.3  269.47  4547.7  266.77  4611.3  264.91  4618.8  266.52
  4625.5   265.9  4633.1  268.76  4639.7  267.92  4647.3  269.73  4675.7  263.65
  4758.6  260.67  4763.9   260.4  4771.6  258.45  4793.9  260.23  4953.9  260.43
  4983.9  261.74  4993.9  259.23  5003.9  258.97  5013.9   260.6  5023.9  260.75
  5093.9  261.05  5113.9  259.85  5143.9  261.29  5263.9  260.86  5423.9  264.04
  5653.9  272.62  5723.9  273.11  5763.9  275.38  5823.9  276.44  6014.5  285.66
#Mann= 5 ,-1 , 0
  4151.8     .11       0  4547.7     .12       0  4758.6     .12       0
  4763.9     .07       0  4793.9     .12       0
Bank Sta=4763.9,4793.9
XS Rating Curve= 0 ,0
Exp/Cntr=0.3,0.1

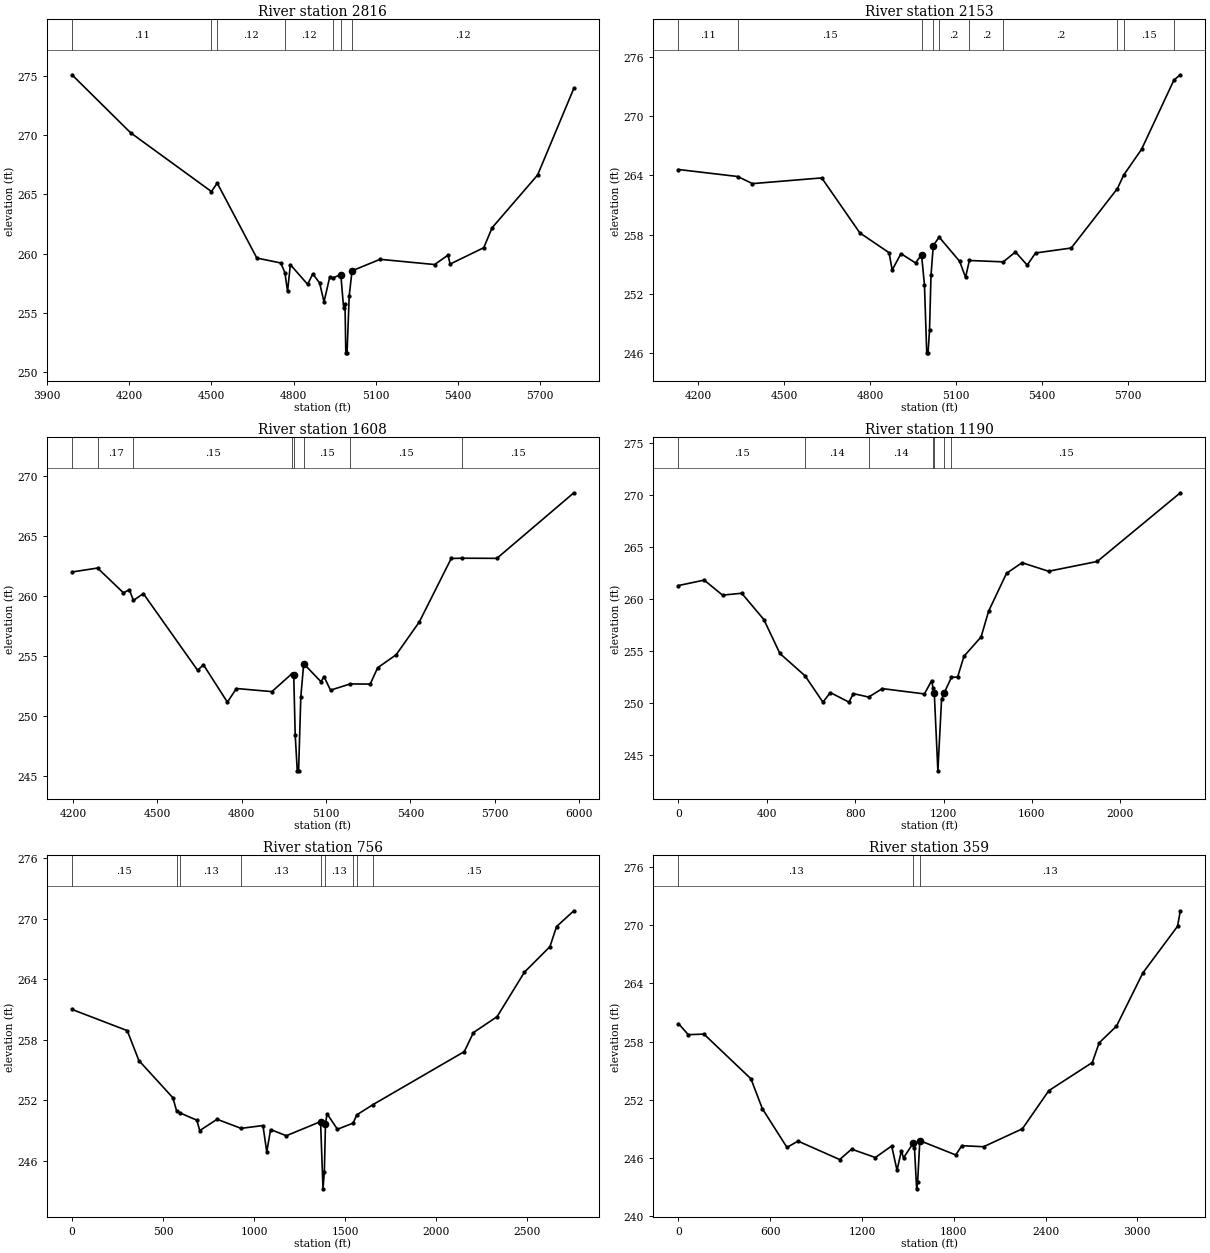
Type RM Length L Ch R = 1 ,2816    ,663,663,663
BEGIN DESCRIPTION:
BLACK BRANCH 3.0
END DESCRIPTION:
XS GIS Cut Line= 3
      3779836.26     10226483.36      3779570.61     10226123.94
      3778216.41     10225827.06
#Sta/Elev= 30
  3990.7  275.09  4204.9   270.2  4500.1  265.24  4521.4  265.95    4666  259.63
  4753.6  259.21  4768.4   258.4  4778.3  256.82  4788.5  259.07  4851.5  257.41
  4870.4  258.29  4895.3  257.53  4911.4  255.93  4931.9  257.99  4945.8  257.97
  4972.8  258.23    4983  255.42  4988.1  255.71    4991  251.63  4995.6  251.63
  5003.5  256.45  5013.8  258.55  5116.1  259.52  5315.4  259.08  5364.3  259.87
  5372.1  259.12  5494.9   260.5  5525.6  262.19  5691.5  266.63    5824  273.95
#Mann= 7 ,-1 , 0
  3990.7     .11       0  4500.1     .15       0  4521.4     .12       0
  4768.4     .12       0  4945.8     .12       0  4972.8     .08       0
  5013.8     .12       0
Bank Sta=4972.8,5013.8
XS Rating Curve= 0 ,0
Exp/Cntr=0.3,0.1

Type RM Length L Ch R = 1 ,2153    ,545,545,545
BEGIN DESCRIPTION:
BLACK BRANCH 2.0
END DESCRIPTION:
XS GIS Cut Line= 3
        3779956.     10225915.59      3779586.23     10225623.94
       3778336.2     10225347.89
#Sta/Elev= 30
  4130.6   264.6  4337.7  263.89  4388.8  263.17  4630.6  263.75  4763.7  258.18
  4865.5  256.18  4876.4  254.43  4907.1  256.08  4957.9  255.14  4978.8  255.97
    4989  252.94  4996.9  246.04  5001.6  246.04  5006.7  248.35  5011.8  253.87
  5019.8   256.9  5040.2  257.76  5111.9   255.3  5132.4  253.68  5145.7  255.39
  5263.9  255.25  5306.5  256.25  5347.5  254.92  5376.6  256.15  5501.1  256.65
  5662.2  262.67  5684.4  264.05  5746.4  266.64  5859.5  273.66  5881.7  274.19
#Mann= 10 ,-1 , 0
  4130.6     .11       0  4337.7     .15       0  4978.8     .09       0
  5019.8     .15       0  5040.2      .2       0  5145.7      .2       0
  5263.9      .2       0  5662.2     .11       0  5684.4     .15       0
  5859.5     .11       0
Bank Sta=4978.8,5019.8
XS Rating Curve= 0 ,0
Exp/Cntr=0.3,0.1

Type RM Length L Ch R = 1 ,1608    ,851,851,851
BEGIN DESCRIPTION:
BLACK BRANCH 1.0
END DESCRIPTION:
XS GIS Cut Line= 3
      3779916.62     10225588.73      3779559.01     10225123.61
      3778393.49     10224842.68
#Sta/Elev= 30
  4196.1  262.02  4287.2  262.35  4379.4  260.28  4400.2  260.54  4414.9  259.65
  4450.1  260.22  4643.1  253.82  4663.9  254.28  4749.1  251.16  4781.2   252.3
  4907.4  252.04  4979.4  253.55  4985.1  253.44  4990.3  248.45  4997.7  245.43
  5002.4  245.43  5010.3  251.59  5020.6  254.37  5082.3  252.86  5092.6   253.3
    5116  252.16  5185.9  252.68  5257.2  252.67  5283.7  254.03  5349.7  255.12
    5432  257.86  5545.4  263.15  5582.7  263.17  5707.9  263.16  5981.7  268.63
#Mann= 8 ,-1 , 0
  4196.1     .11       0  4287.2     .17       0  4414.9     .15       0
  4979.4     .12       0  4985.1     .09       0  5020.6     .15       0
  5185.9     .15       0  5582.7     .15       0
Bank Sta=4985.1,5020.6
XS Rating Curve= 0 ,0
Exp/Cntr=0.3,0.1

Type RM Length L Ch R = 1 ,1190    ,433,433,433
XS GIS Cut Line= 4
      3780019.67     10225673.36      3779793.97     10224866.07
      3779281.82       10224610.      3778422.44     10224557.91
#Sta/Elev= 30
       0  261.28   116.6   261.8   199.7  260.36   286.6  260.54   386.6  258.02
   459.3  254.76   573.5  252.61     654  250.09   687.7  251.01     772  250.09
   791.5  250.91   861.2  250.58   922.7  251.39  1113.4  250.88  1146.3  252.16
  1151.9  251.49  1158.1  250.93  1174.3   243.5  1191.1  250.38  1202.9  250.97
  1235.8  252.48  1263.7   252.5  1292.3  254.49  1369.9  256.35  1404.1  258.83
    1485  262.45  1555.1  263.47  1675.3  262.65  1895.7  263.59  2271.6  270.18
#Mann= 7 ,-1 , 0
       0     .15       0   573.5     .14       0   861.2     .14       0
  1151.9     .12       0  1158.1     .09       0  1202.9     .14       0
  1235.8     .15       0
Bank Sta=1158.1,1202.9
XS Rating Curve= 0 ,0
Exp/Cntr=0.3,0.1

Type RM Length L Ch R = 1 ,756     ,397,397,397
XS GIS Cut Line= 4
      3780097.79     10225669.02      3779950.22     10224692.46
      3779629.04     10224228.05      3778426.78     10224280.14
#Sta/Elev= 30
       0     261   303.6   258.9   367.4  255.94   554.2  252.25   574.4  250.96
   594.6  250.74   685.6  250.03   701.6     249   796.9  250.12   928.4  249.22
  1048.7   249.5  1069.6  246.88  1090.6   249.1  1177.1  248.49    1365  249.89
  1378.4  243.23  1385.9  244.93    1392  249.68  1400.8  250.66  1457.6  249.13
  1544.1  249.74  1563.5  250.55  1653.6  251.58  2154.1  256.82  2204.4  258.71
  2334.2  260.28  2484.4  264.69  2624.5  267.22  2660.7  269.21  2755.7  270.77
#Mann= 9 ,-1 , 0
       0     .15       0   574.4     .14       0   594.6     .13       0
   928.4     .13       0    1365     .08       0    1392     .13       0
  1544.1     .13       0  1563.5     .14       0  1653.6     .15       0
Bank Sta=1365,1392
XS Rating Curve= 0 ,0
Exp/Cntr=0.3,0.1

Type RM Length L Ch R = 1 ,359     ,0,0,0
XS GIS Cut Line= 4
      3780174.27     10225593.95      3780396.49     10224593.95
      3779880.78     10224002.36      3778429.47     10224258.88
#Sta/Elev= 30
       0  259.86    64.4  258.71   166.9  258.77   474.2  254.16   548.8  251.08
   709.8  247.09   781.9  247.74  1054.2  245.84  1132.1  246.91  1287.8  246.05
  1394.1  247.24  1429.2  244.73  1457.7  246.73  1471.9  246.01  1535.5  247.55
  1543.2  247.04  1557.4  242.82    1564  243.55  1578.3  247.79  1813.2  246.31
  1852.8  247.27    1995  247.16  2248.8  249.01  2421.5  252.94  2705.8  255.84
  2750.7  257.87    2864  259.59  3036.5  265.08  3263.1  269.88  3281.3  271.48
#Mann= 3 , 0 , 0
       0     .13       0  1535.5     .08       0  1578.3     .13       0
Bank Sta=1535.5,1578.3
XS Rating Curve= 0 ,0
Exp/Cntr=0.3,0.1

Chan Stop Cuts=-1
Use User Specified Reach Order=0
Composite Channel Slope=5