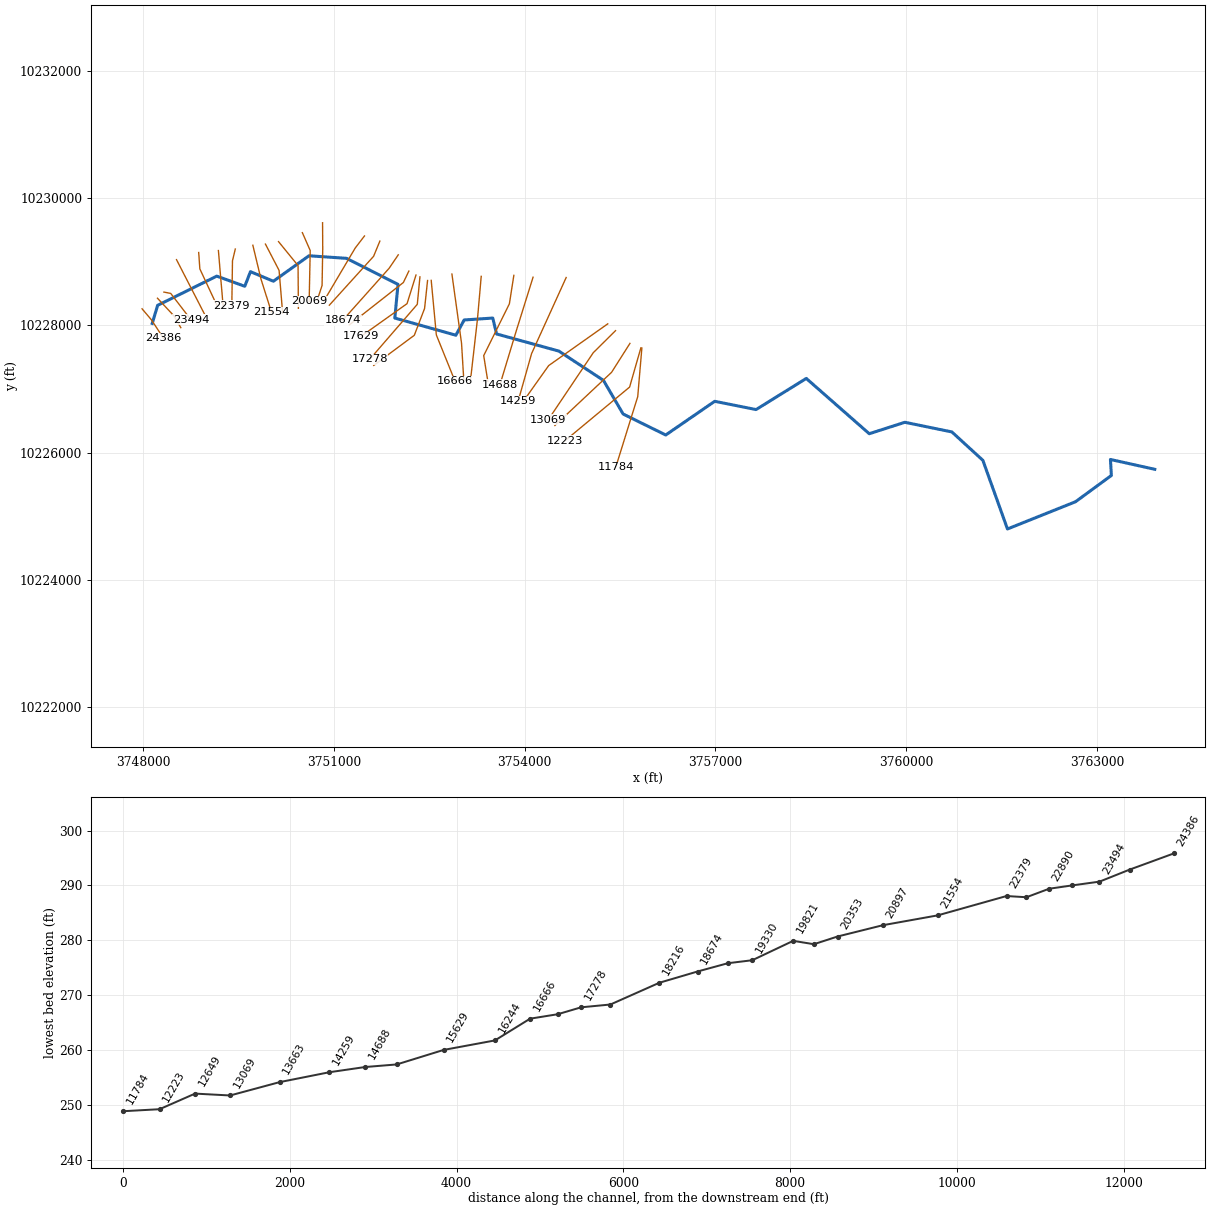
--- CASIDY BRANCH.prj (project) ---

Proj Title=CASIDY BRANCH Base Level Engineering
Current Plan=p01
Default Exp/Contr=0.3,0.1
English Units
Geom File=g01
Flow File=f01
Plan File=p01
Y Axis Title=Elevation
X Axis Title(PF)=Main Channel Distance
X Axis Title(XS)=Station
BEGIN DESCRIPTION:
CASIDY BRANCH
END DESCRIPTION:
DSS Export Rating Curves= 0
DSS Export Rating Curve Sorted= 0
DSS Export Volume Flow Curves= 0
DXF OffsetX= 0
DXF OffsetY= 0
DXF ScaleX= 1
DXF ScaleY= 10

--- CASIDY BRANCH.p01 (plan) ---

Plan Title=Multiple Run
Program Version=4.10
Short Identifier=Multiple
Geom File=g01
Flow File=f01
Subcritical Flow
K Sum by GR= 0
Std Step Tol= 0.01
Critical Tol= 0.01
Num of Std Step Trials= 20
Max Error Tol= 0.3
Flow Tol Ratio= 0.001
Split Flow NTrial= 30
Split Flow Tol= 0.02
Split Flow Ratio= 0.02
Log Output Level= 0
Friction Slope Method= 1
Unsteady Friction Slope Method= 2
Unsteady Bridges Friction Slope Method= 1
Parabolic Critical Depth
Global Vel Dist= 1 , 1 , 1
Global Log Level= 0
CheckData=True
Encroach Param=-1 ,0,0, 0
BEGIN DESCRIPTION:
Multiple Run
END DESCRIPTION:
Computation Interval=1HOUR
Output Interval=1HOUR
Run HTab= 0
Run UNet= 0
Run PostProcess= 0
Run WQNet= 0
UNET Theta= 1
UNET Theta Warmup= 1
UNET ZTol= 0.02
UNET ZSATol= 0.05
UNET MxIter= 20
UNET MaxInSteps= 0
UNET DtIC= 0
UNET DtMin= 0
UNET MaxCRTS= 20
UNET WFStab= 2
UNET SFStab= 1
UNET WFX= 1
UNET SFX= 1
UNET DSS MLevel= 4
UNET DZMax Abort= 100
UNET Convert EG Bridges= 0
UNET Use Existing IB Tables=-1
UNET Froude Reduction=False
UNET Froude Limit= 1
UNET Froude Power= 10
UNET Time Slicing=0,0, 5
UNET Junction Losses=0
Instantaneous Interval=1HOUR
Write IC File= 0
Write IC File at Sim End=0
Echo Input=False
Echo Parameters=False
Echo Output=False
Write Detailed= 0
WQ AD Non Conservative
WQ ULTIMATE=-1
WQ Max Comp Step=1HOUR
WQ Output Interval=15MIN
WQ Output Selected Increments= 0
WQ Output face flow=0
WQ Output face velocity=0
WQ Output face area=0
WQ Output face dispersion=0
WQ Output cell volume=0
WQ Output cell surface area=0
WQ Output cell continuity=0
WQ Output cumulative cell continuity=0
WQ Output face conc=0
WQ Output face dconc_dx=0
WQ Output face courant=0
WQ Output face peclet=0
WQ Output face adv mass=0
WQ Output face disp mass=0
WQ Output cell mass=0
WQ Output cell source sink temp=0
WQ Output cell source sink nsm=0
WQ Output MaxMinRange=-1
WQ Daily Max Min Mean=-1
WQ Daily Range=0
WQ Daily Time=0
WQ Create Restart=0
WQ Fixed Restart=0
WQ System Summary=0
WQ Use Fixed Temperature=0
Sorting and Armoring Iterations= 10
XS Update Threshold= 0.02
Hydraulics Update Threshold= 0.02
Energy Slope Method= 1
Volume Change Method= 0
XS Weighting Method= 0
Number of US Weighted Cross Sections= 1
Number of DS Weighted Cross Sections= 1
Upstream XS Weight=0.25
Main XS Weight=0.5
Downstream XS Weight=0.25
Number of DS XS's Weighted with US Boundary= 1
Upstream Boundary Weight= 1
Weight of XSs Associated with US Boundary= 0
Number of US XS's Weighted with DS Boundary= 1
Downstream Boundary Weight= 0.5
Weight of XSs Associated with DS Boundary= 0.5
Sediment Output Level= 4
Mass or Volume Output= 0
Output Increment Type= 1
Profile and TS Output Increment= 10
XS Output Flag= 0
XS Output Increment= 10
Disregard all LS=0
Disregard all Conn=0
Disregard all Breaches=0
Disregard all Pumps=0

--- CASIDY BRANCH.f01 (steady flow) ---

Flow Title=Multiple
Program Version=4.10
Number of Profiles= 7
Profile Names=10-year,25-year,50-year,1pct_min,100-year,1pct_plu,500-year
River Rch & RM=CASIDY BRANCH,Reach-1         ,24386
     884    1215    1658     743    2244    6777    4254
River Rch & RM=CASIDY BRANCH,Reach-1         ,16244
     978    1346    1839     824    2488    7514    4715
River Rch & RM=CASIDY BRANCH,Reach-1         ,9597
    1040    1434    1961     879    2656    8021    5041
River Rch & RM=CASIDY BRANCH,Reach-1         ,6975
    1545    2172    3007    1364    4120   12442    8007
River Rch & RM=CASIDY BRANCH,Reach-1         ,6479
    1545    2172    3007    1364    4120   12442    8007
River Rch & RM=CASIDY BRANCH,Reach-1         ,5667
    2427    3485    4896    2251    6798   20530   13569
River Rch & RM=CASIDY BRANCH,Reach-1         ,5406
    2427    3485    4896    2251    6798   20530   13569
Boundary for River Rch & Prof#=CASIDY BRANCH,Reach-1         , 1
Up Type= 0
Dn Type= 3
Dn Slope=0.002
Boundary for River Rch & Prof#=CASIDY BRANCH,Reach-1         , 2
Up Type= 0
Dn Type= 3
Dn Slope=0.002
Boundary for River Rch & Prof#=CASIDY BRANCH,Reach-1         , 3
Up Type= 0
Dn Type= 3
Dn Slope=0.002
Boundary for River Rch & Prof#=CASIDY BRANCH,Reach-1         , 4
Up Type= 0
Dn Type= 3
Dn Slope=0.002
Boundary for River Rch & Prof#=CASIDY BRANCH,Reach-1         , 5
Up Type= 0
Dn Type= 3
Dn Slope=0.002
Boundary for River Rch & Prof#=CASIDY BRANCH,Reach-1         , 6
Up Type= 0
Dn Type= 3
Dn Slope=0.002
Boundary for River Rch & Prof#=CASIDY BRANCH,Reach-1         , 7
Up Type= 0
Dn Type= 3
Dn Slope=0.002
DSS Import GetInterval= 0
DSS Import GetPeak= 0
DSS Import FillOption= 0

--- CASIDY BRANCH.g01 (geometry) ---

Geom Title=Existing Conditions
Program Version=4.10

River Reach=CASIDY BRANCH   ,Reach-1
Reach XY= 30
      3748143.23     10228031.84      3748228.23     10228316.84
      3749158.23     10228776.84      3749598.23     10228616.84
      3749688.23     10228846.84      3750048.23     10228696.84
      3750608.23     10229096.84      3751198.23     10229056.84
      3752008.23     10228646.84      3751958.23     10228116.84
      3752918.23     10227846.84      3753048.23     10228086.84
      3753498.23     10228116.84      3753558.23     10227866.84
      3754538.23     10227596.84      3755238.23     10227136.84
      3755548.23     10226606.84      3756218.23     10226276.84
      3756988.23     10226806.84      3757638.23     10226676.84
      3758428.23     10227166.84      3759418.23     10226296.84
      3759978.23     10226476.84      3760717.42     10226324.99
      3761204.98     10225878.39      3761591.62     10224798.07
       3762662.4     10225226.88      3763225.63     10225640.14
      3763211.05     10225891.45      3763908.23     10225736.84

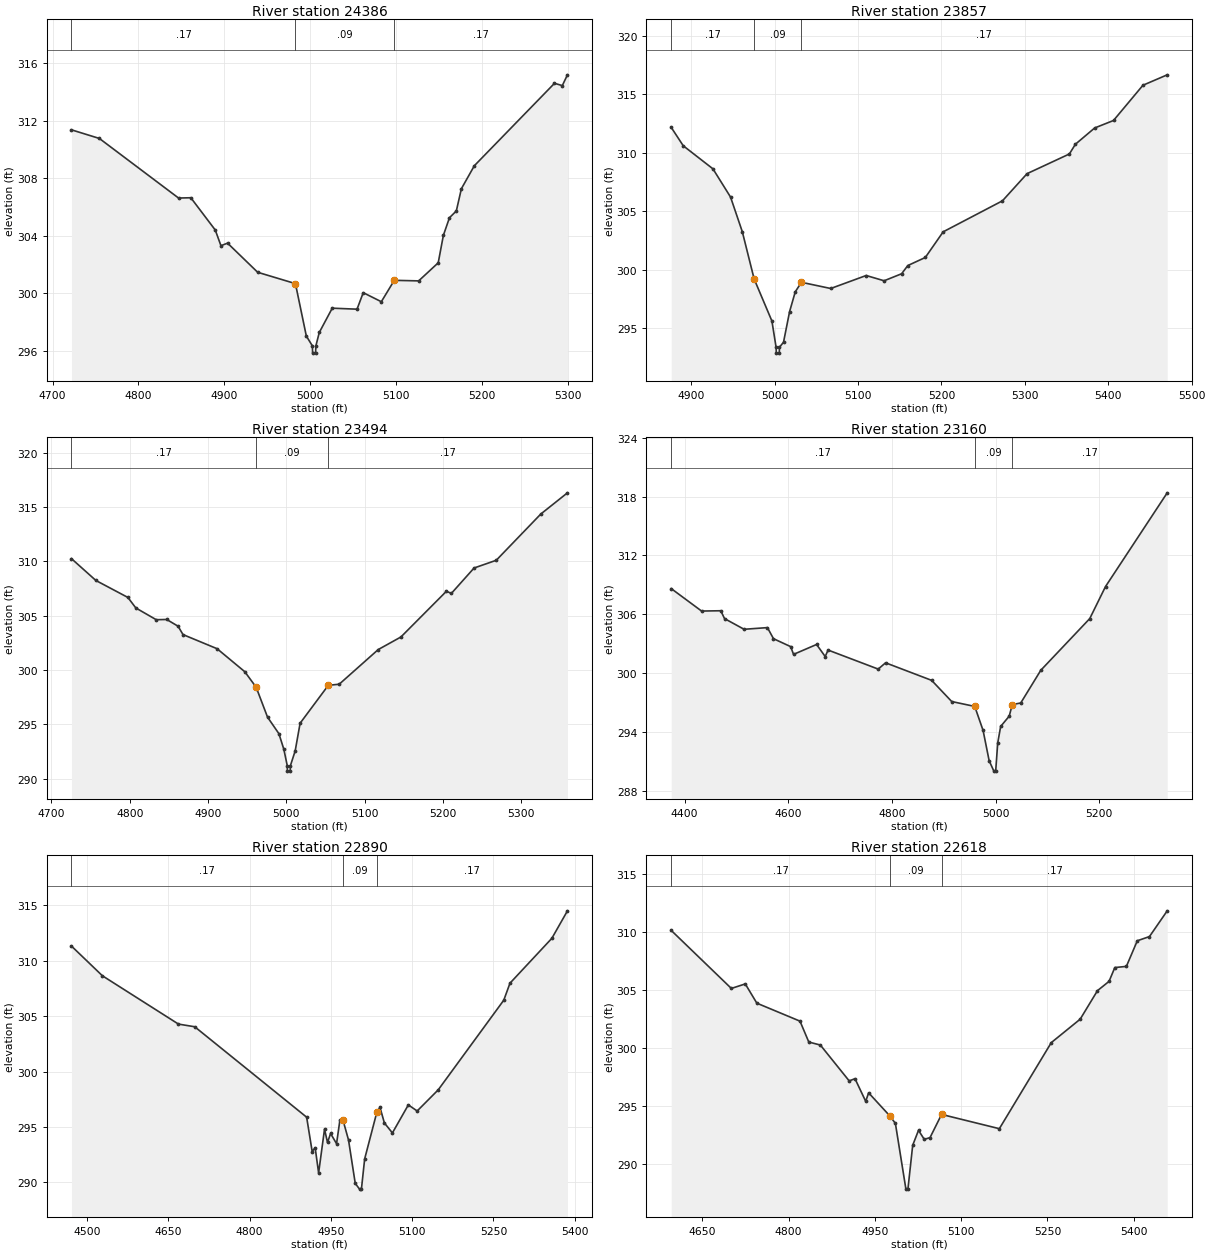
Type RM Length L Ch R = 1 ,24386   ,529,529,529
BEGIN DESCRIPTION:
CASIDY BRANCH 44.0
END DESCRIPTION:
XS GIS Cut Line= 3
      3747983.37     10228262.68      3748129.23     10228090.77
        3748323.     10227796.24
#Sta/Elev= 30
  4721.9  311.38  4754.4  310.78  4846.7  306.63    4861  306.65  4889.5   304.4
  4896.1  303.31  4903.8  303.49  4938.9  301.46  4982.9  300.67  4995.6  297.02
  5002.7  296.33  5002.9  295.83  5006.4  295.83  5006.7  296.33  5010.7  297.27
  5025.8  298.96  5054.7  298.89  5061.9  300.04    5083  299.41  5098.1   300.9
  5126.5  300.86  5149.3  302.12  5155.3  304.03  5162.4  305.26  5170.4  305.73
  5176.3  307.28  5191.4  308.88  5284.8  314.62  5293.9  314.46  5299.9  315.21
#Mann= 3 , 0 , 0
  4721.9     .17       0  4982.9     .09       0  5098.1     .17       0
Bank Sta=4982.9,5098.1
XS Rating Curve= 0 ,0
Exp/Cntr=0.3,0.1

Type RM Length L Ch R = 1 ,23857   ,363,363,363
BEGIN DESCRIPTION:
CASIDY BRANCH 43.0
END DESCRIPTION:
XS GIS Cut Line= 3
      3748225.58     10228429.32       3748483.4     10228153.27
      3748592.68     10227965.93
#Sta/Elev= 30
  4876.1  312.17  4890.5   310.6  4926.1  308.63  4947.2  306.22  4961.3  303.26
  4975.5  299.22  4996.8  295.63  5001.8  293.39  5002.1  292.89  5005.6  292.89
  5005.8  293.39  5010.7  293.82    5018  296.44  5024.8  298.13  5032.2  298.94
  5067.3  298.41  5109.8  299.52  5131.3  299.07  5152.3  299.67  5159.7  300.37
  5180.7  301.06  5202.1  303.25  5273.2   305.9  5302.7  308.22  5353.4   309.9
  5360.6  310.73  5383.7  312.12  5406.3  312.76  5441.6  315.77  5470.7  316.66
#Mann= 3 , 0 , 0
  4876.1     .17       0  4975.5     .09       0  5032.2     .17       0
Bank Sta=4975.5,5032.2
XS Rating Curve= 0 ,0
Exp/Cntr=0.3,0.1

Type RM Length L Ch R = 1 ,23494   ,334,334,334
BEGIN DESCRIPTION:
CASIDY BRANCH 42.0
END DESCRIPTION:
XS GIS Cut Line= 3
      3748327.19     10228525.66      3748433.92     10228504.83
      3748753.56     10228089.04
#Sta/Elev= 30
  4725.6  310.25  4756.8  308.24  4797.6  306.68  4807.8  305.71  4833.8  304.63
  4847.2  304.65  4861.7  304.03    4868  303.26  4911.5  301.96  4946.9  299.84
  4961.4  298.41  4975.9  295.66  4990.4  294.14  4996.7  292.71  5001.1  291.19
  5001.3  290.69  5004.8  290.69  5005.1  291.19  5011.2  292.55  5017.5   295.1
  5053.5  298.59  5067.4  298.69  5117.2  301.88  5146.2  303.04  5204.3  307.25
  5210.6  307.05  5239.6  309.39  5267.9   310.1  5324.8  314.36  5358.8  316.31
#Mann= 3 ,-1 , 0
  4725.6     .17       0  4961.4     .09       0  5053.5     .17       0
Bank Sta=4961.4,5053.5
XS Rating Curve= 0 ,0
Exp/Cntr=0.3,0.1

Type RM Length L Ch R = 1 ,23160   ,270,270,270
BEGIN DESCRIPTION:
Mapping XS 0675b960
END DESCRIPTION:
XS GIS Cut Line= 2
      3748525.08     10229036.04      3748962.19     10228185.26
#Sta/Elev= 30
  4374.4  308.61  4432.9  306.32  4469.9  306.35  4477.2  305.55  4514.9  304.46
  4559.9  304.63  4571.6   303.5  4604.7  302.69  4610.3   301.9  4654.7  302.91
  4671.3  301.68  4676.9  302.34  4773.5   300.4  4787.8  301.04  4876.6  299.25
  4915.3  297.09  4959.7  296.59  4975.8  294.14  4987.5  291.05  4996.6  289.99
  5000.1  289.99    5004  292.86  5009.7  294.55  5026.2   295.6  5032.1  296.78
  5048.4  296.94  5087.1  300.28  5181.5  305.55  5211.9  308.82  5330.9  318.38
#Mann= 3 , 0 , 0
  4374.4     .17       0  4959.7     .09       0  5032.1     .17       0
Bank Sta=4959.7,5032.1
XS Rating Curve= 0 ,0
Exp/Cntr=0.3,0.1

Type RM Length L Ch R = 1 ,22890   ,272,272,272
BEGIN DESCRIPTION:
CASIDY BRANCH 41.0
END DESCRIPTION:
XS GIS Cut Line= 3
      3748874.02     10229148.05      3748892.25     10228890.25
      3749170.39     10228294.97
#Sta/Elev= 30
  4471.2  311.33  4528.3  308.65  4668.7  304.29  4698.7  304.05  4905.3  295.89
  4915.5  292.79    4921  293.14  4927.4  290.86  4938.3  294.81  4943.8  293.61
  4949.5  294.42  4960.5   293.5  4966.7  295.63  4972.2  295.66  4982.6  293.83
    4995  289.92  5002.9   289.4  5006.4   289.4  5012.4  292.13  5035.2   296.4
  5040.7  296.77  5048.8  295.37  5063.6  294.47    5093     297  5109.3  296.45
  5148.2  298.36  5269.2  306.45  5280.6  307.98  5357.9  312.03  5386.7  314.51
#Mann= 3 , 0 , 0
  4471.2     .17       0  4972.2     .09       0  5035.2     .17       0
Bank Sta=4972.2,5035.2
XS Rating Curve= 0 ,0
Exp/Cntr=0.3,0.1

Type RM Length L Ch R = 1 ,22618   ,239,239,239
BEGIN DESCRIPTION:
CASIDY BRANCH 40.0
END DESCRIPTION:
XS GIS Cut Line= 2
      3749183.92     10229179.29      3749256.93     10228320.29
#Sta/Elev= 30
  4596.1  310.15  4700.6  305.15  4724.8  305.54  4744.9  303.88  4819.9  302.33
  4835.2  300.53  4855.3  300.27  4905.4  297.18  4915.5  297.37  4934.1  295.42
  4939.2  296.15  4975.7  294.18  4985.7  293.52    5004  287.85  5007.5  287.85
  5015.8  291.63  5025.9  292.92  5035.9  292.14  5045.9  292.29    5066  294.29
  5166.4  293.06  5256.7  300.48  5306.9   302.5    5337  304.96  5357.1  305.76
  5367.1  306.95  5387.2  307.05  5406.2  309.26  5427.3  309.62  5458.2  311.84
#Mann= 3 ,-1 , 0
  4596.1     .17       0  4975.7     .09       0    5066     .17       0
Bank Sta=4975.7,5066
XS Rating Curve= 0 ,0
Exp/Cntr=0.3,0.1

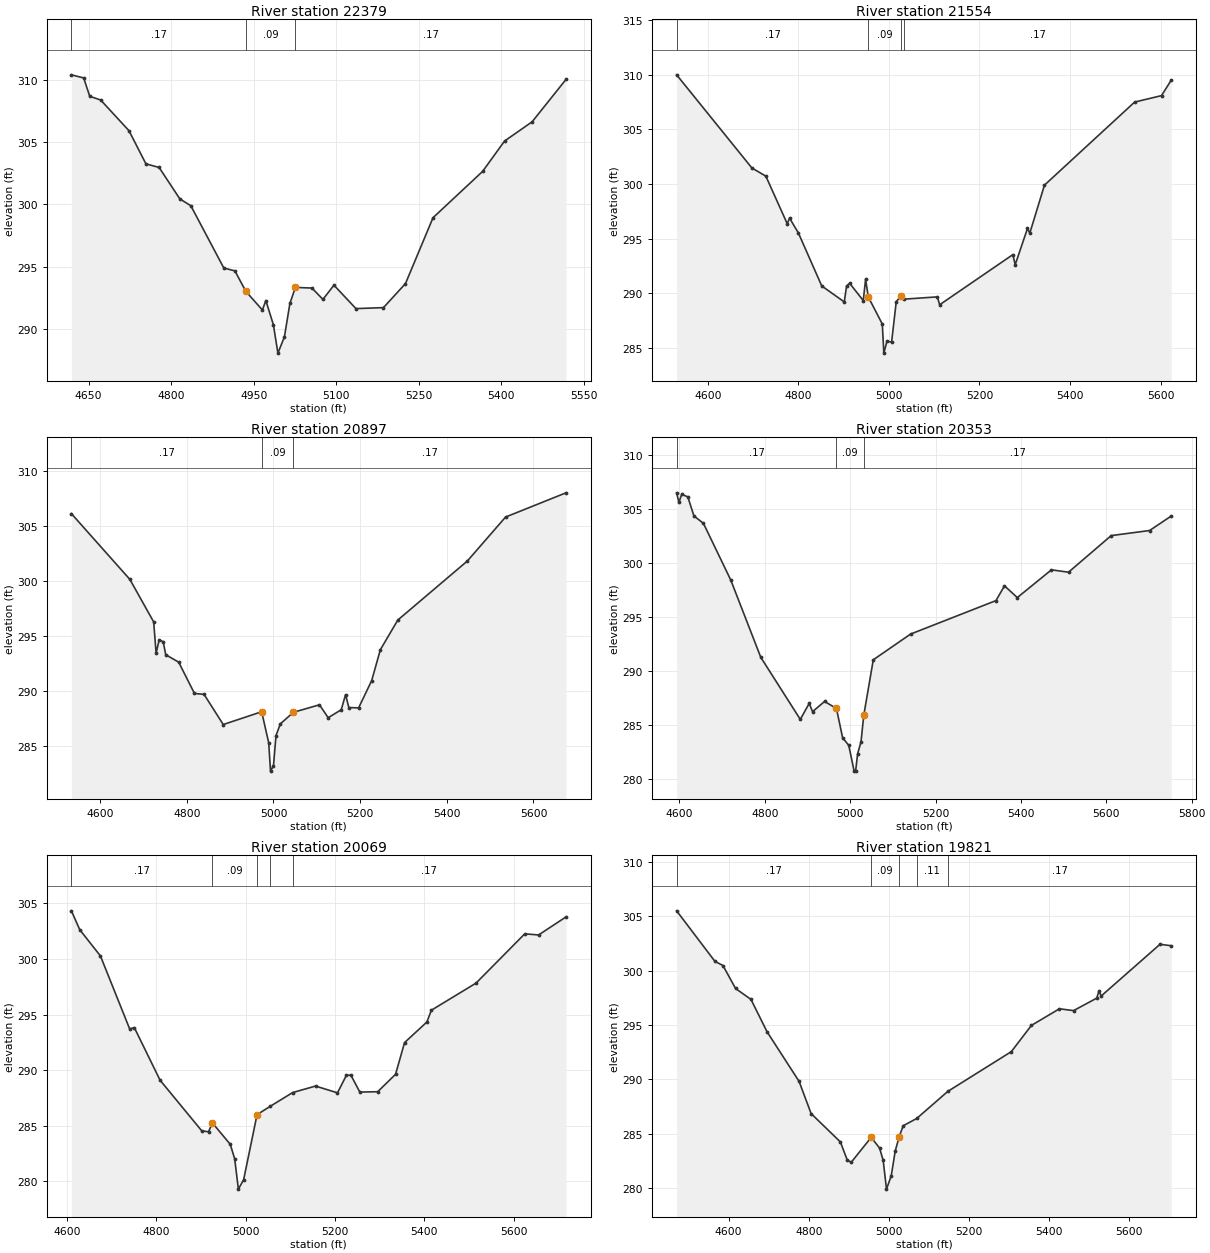
Type RM Length L Ch R = 1 ,22379   ,825,825,825
BEGIN DESCRIPTION:
Mapping XS f758a63a
END DESCRIPTION:
XS GIS Cut Line= 3
      3749449.55      10229202.8      3749405.27     10229017.85
      3749394.85      10228309.5
#Sta/Elev= 30
  4618.8  310.39  4641.1  310.14  4652.1  308.67    4672  308.37  4723.4  305.91
  4754.2  303.25  4778.2  302.96  4815.8  300.44  4835.8  299.89  4895.8  294.89
  4915.8  294.67  4935.8  293.02  4965.8  291.53  4972.1  292.29  4985.8  290.34
    4994  288.07  5005.8  289.37  5015.8  292.06  5025.8  293.34  5055.8  293.29
  5075.8  292.38  5095.8  293.52  5135.8  291.64  5185.8  291.72  5225.8  293.65
  5275.8  298.93  5365.8  302.64  5405.8  305.08  5455.8  306.62  5517.4  310.02
#Mann= 3 , 0 , 0
  4618.8     .17       0  4935.8     .09       0  5025.8     .17       0
Bank Sta=4935.8,5025.8
XS Rating Curve= 0 ,0
Exp/Cntr=0.3,0.1

Type RM Length L Ch R = 1 ,21554   ,657,657,657
BEGIN DESCRIPTION:
CASIDY BRANCH 39.0
END DESCRIPTION:
XS GIS Cut Line= 3
      3749725.58     10229262.68      3749853.19      10228731.4
      3750017.87     10228211.03
#Sta/Elev= 30
  4531.2  309.98  4697.4  301.47  4728.3  300.72  4775.5  296.37  4780.6  296.89
  4800.2  295.52  4851.7  290.69  4901.4  289.23  4906.6  290.69  4913.4  290.93
  4943.4  289.35  4948.5   291.3  4954.5  289.68  4985.4  287.21  4988.8  284.55
  4995.7  285.64  5005.9  285.55  5016.2  289.24  5026.5  289.78  5032.5  289.48
  5106.9  289.69  5112.1  288.97  5273.7  293.55  5278.9  292.63    5306  295.94
  5311.2  295.52  5343.5   299.9  5542.6  307.49    5602  308.08  5623.4  309.49
#Mann= 4 ,-1 , 0
  4531.2     .17       0  4954.5     .09       0  5026.5     .12       0
  5032.5     .17       0
Bank Sta=4954.5,5026.5
XS Rating Curve= 0 ,0
Exp/Cntr=0.3,0.1

Type RM Length L Ch R = 1 ,20897   ,544,544,544
BEGIN DESCRIPTION:
CASIDY BRANCH 38.0
END DESCRIPTION:
XS GIS Cut Line= 3
       3749923.5     10229280.87      3750138.23     10228866.84
      3750194.18     10228194.17
#Sta/Elev= 30
  4533.6  306.13  4668.6  300.16  4723.5   296.3  4729.1  293.47  4736.1  294.67
  4745.6   294.5  4751.2  293.33  4781.2  292.65  4817.6  289.81  4839.7  289.73
    4884  286.99  4972.7  288.15    4989  285.32  4993.1  282.76    5000  283.26
  5005.8  285.99  5015.8  287.05  5045.9   288.1  5106.1  288.78  5126.2  287.61
  5156.3  288.33  5166.3   289.7  5173.9  288.53  5196.4   288.5  5226.6  290.98
  5246.6  293.78  5286.8  296.47  5447.3  301.83  5535.5  305.82    5675  308.02
#Mann= 3 , 0 , 0
  4533.6     .17       0  4972.7     .09       0  5045.9     .17       0
Bank Sta=4972.7,5045.9
XS Rating Curve= 0 ,0
Exp/Cntr=0.3,0.1

Type RM Length L Ch R = 1 ,20353   ,284,284,284
BEGIN DESCRIPTION:
CASIDY BRANCH 37.0
END DESCRIPTION:
XS GIS Cut Line= 3
       3750129.2     10229319.97      3750436.52     10228942.33
      3750441.73     10228270.44
#Sta/Elev= 30
  4593.3  306.47  4598.7  305.58  4605.2  306.33  4619.5   306.1  4633.9  304.33
  4656.2  303.64  4720.1   298.4  4790.5  291.24  4883.1  285.49  4903.9  286.97
  4911.8  286.21    4940  287.15  4967.8   286.5  4982.2  283.79  4996.6  283.09
  5009.2   280.7  5012.7   280.7  5017.4  282.31  5025.3  283.41  5031.8  285.87
  5054.1  291.01  5141.4  293.39  5341.5  296.49  5361.5  297.86  5391.5  296.77
  5471.5  299.34  5511.5  299.12  5611.5  302.51  5701.5  302.98  5752.1  304.32
#Mann= 3 , 0 , 0
  4593.3     .17       0  4967.8     .09       0  5031.8     .17       0
Bank Sta=4967.8,5031.8
XS Rating Curve= 0 ,0
Exp/Cntr=0.3,0.1

Type RM Length L Ch R = 1 ,20069   ,248,248,248
BEGIN DESCRIPTION:
CASIDY BRANCH 36.0
END DESCRIPTION:
XS GIS Cut Line= 3
      3750504.23     10229460.56      3750627.79     10229179.62
        3750611.      10228379.8
#Sta/Elev= 30
  4610.3  304.33  4628.9  302.64  4675.3  300.27  4740.8   293.7  4751.1  293.83
  4808.7   289.1  4902.1  284.54  4917.2  284.46  4925.8  285.26  4965.8  283.33
  4975.8  282.02    4984   279.3  4995.8  280.15  5025.8     286  5055.8  286.76
  5105.2  287.98  5156.6  288.57  5205.8  287.96  5225.8  289.54  5235.8  289.55
  5255.8  288.03  5295.8  288.06  5335.8  289.63  5355.9  292.48  5405.9  294.33
  5415.9  295.39  5515.9  297.83  5624.9  302.26  5655.9  302.16  5717.2  303.78
#Mann= 5 ,-1 , 0
  4610.3     .17       0  4925.8     .09       0  5025.8     .17       0
  5055.8     .11       0  5105.2     .17       0
#XS Ineff= 1 ,-1
  5235.8    5335  289.55
Permanent Ineff=
       F
Bank Sta=4925.8,5025.8
XS Rating Curve= 0 ,0
Exp/Cntr=0.3,0.1

Type RM Length L Ch R = 1 ,19821   ,491,491,491
BEGIN DESCRIPTION:
Mapping XS e2860ef8
END DESCRIPTION:
XS GIS Cut Line= 4
      3750821.94     10229616.82      3750824.54     10229207.96
      3750814.13     10228629.83      3750736.54     10228394.48
#Sta/Elev= 30
    4470  305.51  4565.7  300.86  4585.7  300.48  4617.1  298.37  4655.7  297.36
  4695.7  294.39  4775.8  289.82  4805.8  286.86  4878.9  284.25  4895.8  282.61
  4905.8  282.37  4955.8  284.67  4976.7  283.69  4985.8  282.55    4994  279.91
  5005.8  281.12  5015.8  283.41  5025.8  284.75  5035.8  285.74  5069.5  286.41
  5147.1   288.9  5305.8  292.56  5355.8  294.97  5425.8   296.5  5461.1  296.33
    5519  297.48  5524.6  298.16  5529.9  297.67  5676.9  302.43  5704.9   302.3
#Mann= 5 ,-1 , 0
    4470     .17       0  4955.8     .09       0  5025.8     .15       0
  5069.5     .11       0  5147.1     .17       0
Bank Sta=4955.8,5025.8
XS Rating Curve= 0 ,0
Exp/Cntr=0.3,0.1

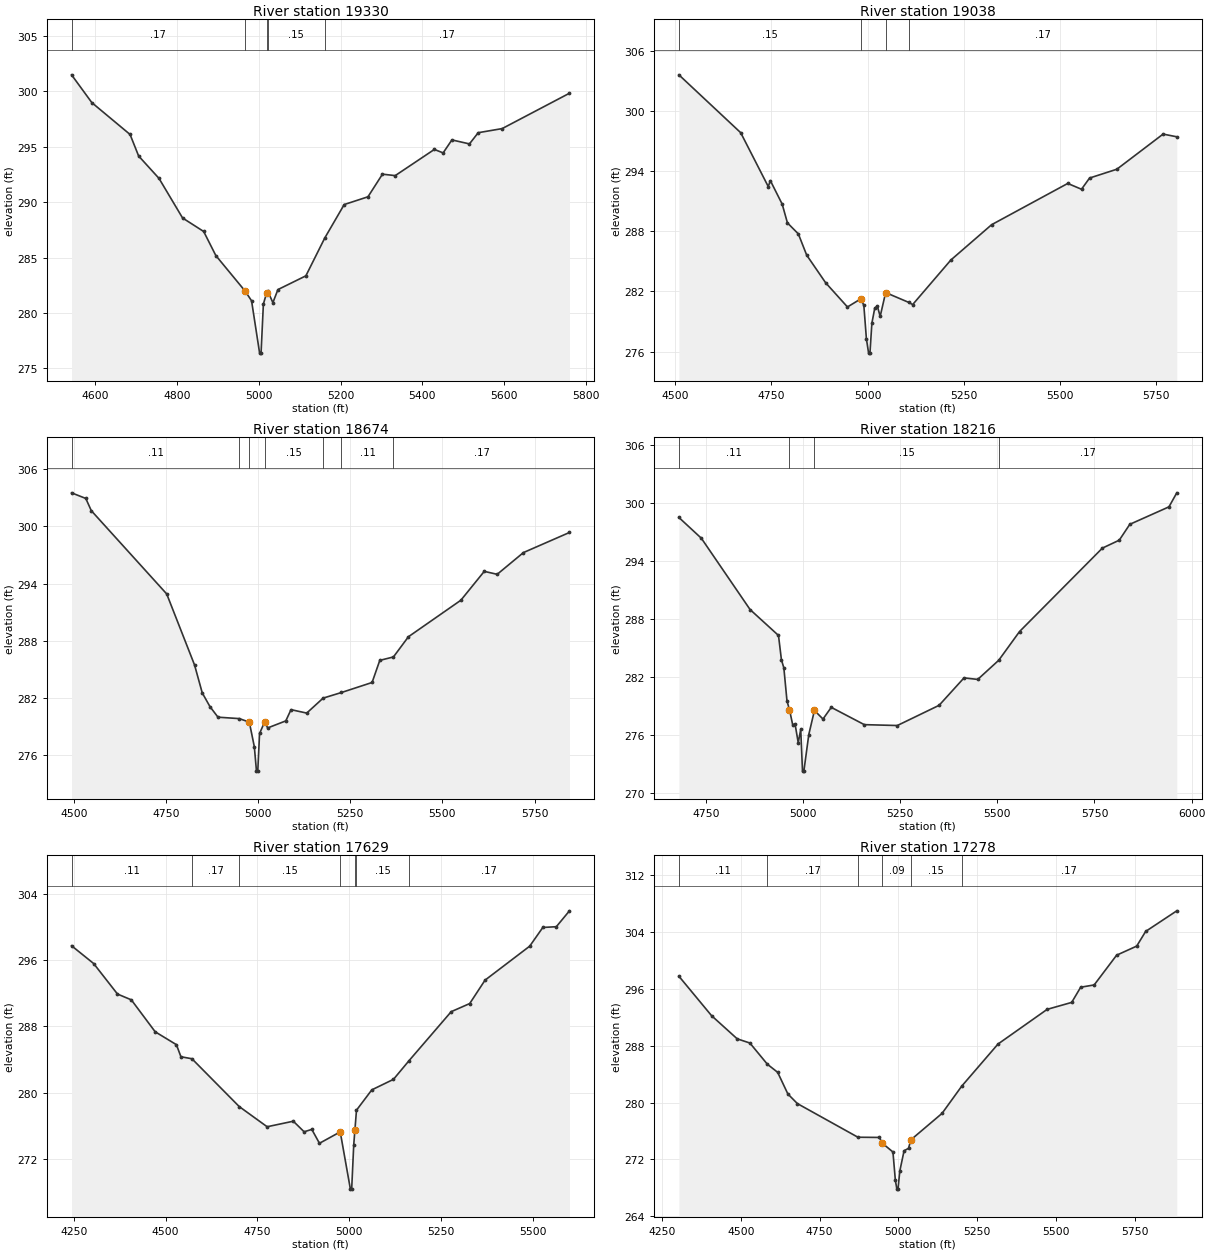
Type RM Length L Ch R = 1 ,19330   ,292,292,292
BEGIN DESCRIPTION:
CASIDY BRANCH 35.0
END DESCRIPTION:
XS GIS Cut Line= 3
      3751480.77     10229408.45      3751334.96     10229218.38
      3750837.54      10228377.2
#Sta/Elev= 30
  4542.7  301.48  4592.3  298.97  4685.7   296.1  4706.6  294.16  4756.4  292.14
    4814  288.57  4865.6  287.35  4895.3  285.18    4967  281.97  4982.6   281.1
  5002.3  276.38  5005.8  276.38  5011.5  280.81  5019.7  281.84    5022  281.99
  5034.7  280.93    5047  282.11  5115.3  283.35  5161.6  286.77    5209  289.78
  5267.1  290.48  5302.5  292.52  5333.7  292.39  5429.3  294.75  5450.8  294.44
  5472.2  295.61  5515.1  295.25  5536.5  296.26    5595  296.63  5759.5  299.82
#Mann= 5 ,-1 , 0
  4542.7     .17       0    4967     .09       0  5019.7     .17       0
    5022     .15       0  5161.6     .17       0
Bank Sta=4967,5019.7
XS Rating Curve= 0 ,0
Exp/Cntr=0.3,0.1

Type RM Length L Ch R = 1 ,19038   ,364,364,364
BEGIN DESCRIPTION:
CASIDY BRANCH 34.0
END DESCRIPTION:
XS GIS Cut Line= 3
      3751722.98     10229327.74      3751624.02     10229088.17
      3750928.69     10228319.92
#Sta/Elev= 30
  4509.2  303.64    4670  297.86  4741.7  292.48  4747.2  293.07    4778  290.72
  4791.6  288.85    4820  287.75  4841.7  285.63    4891  282.87  4947.8  280.45
  4982.9  281.27  4990.4   280.6  4997.1  277.26  5002.8  275.84  5006.3  275.84
  5011.3  278.83  5018.8  280.33  5025.5  280.54  5032.9  279.51  5047.1  281.89
  5107.1  280.91  5117.4  280.69  5216.8  285.14  5322.9  288.67  5520.9  292.79
  5556.7  292.21  5577.7  293.33  5648.7  294.21    5769  297.72  5804.6  297.45
#Mann= 4 ,-1 , 0
  4509.2     .15       0  4982.9     .09       0  5047.1     .15       0
  5107.1     .17       0
Bank Sta=4982.9,5047.1
XS Rating Curve= 0 ,0
Exp/Cntr=0.3,0.1

Type RM Length L Ch R = 1 ,18674   ,458,458,458
BEGIN DESCRIPTION:
CASIDY BRANCH 33.0
END DESCRIPTION:
XS GIS Cut Line= 3
      3752012.05     10229111.62      3751868.81     10228900.67
       3751139.6     10228082.98
#Sta/Elev= 30
    4494  303.53  4532.6  302.94  4547.5  301.66  4752.1  292.92  4827.6  285.47
  4848.5  282.54  4869.4   281.1  4891.2  279.99  4949.1  279.84  4976.2  279.47
  4989.8  276.89  4995.6  274.33  4999.1  274.33    5004  278.28  5018.2  279.53
  5025.8  278.86  5075.1   279.6  5089.3  280.78  5131.9  280.42  5176.4  281.99
  5226.2  282.58  5309.2  283.63  5330.1  285.95  5367.1  286.31  5407.8  288.43
    5550  292.26  5613.5  295.29  5648.6  294.98  5719.7  297.26  5844.6  299.37
#Mann= 7 ,-1 , 0
    4494     .11       0  4949.1     .15       0  4976.2     .09       0
  5018.2     .15       0  5176.4     .17       0  5226.2     .11       0
  5367.1     .17       0
Bank Sta=4976.2,5018.2
XS Rating Curve= 0 ,0
Exp/Cntr=0.3,0.1

Type RM Length L Ch R = 1 ,18216   ,587,587,587
BEGIN DESCRIPTION:
CASIDY BRANCH 32.0
END DESCRIPTION:
XS GIS Cut Line= 3
       3752178.7     10228856.37      3752092.77     10228676.71
      3751242.03     10228008.08
#Sta/Elev= 30
  4680.6  298.53  4738.4  296.38  4863.8     289  4936.9  286.32  4944.4  283.82
  4950.7  282.96  4958.8  279.53  4965.2  278.64  4973.3   277.1  4979.6  277.14
  4987.7  275.22  4994.1  276.59  4998.7  272.28  5002.2  272.28  5014.9  276.07
  5029.4  278.56  5051.4  277.67  5072.7  278.88  5157.7  277.09  5242.7     277
  5350.2  279.09  5414.3  281.93  5449.6  281.77  5503.6  283.75  5557.1  286.72
  5770.4  295.36  5813.8  296.18  5840.9  297.82  5941.7  299.63  5961.8  301.08
#Mann= 4 ,-1 , 0
  4680.6     .11       0  4965.2     .07       0  5029.4     .15       0
  5503.6     .17       0
Bank Sta=4965.2,5029.4
XS Rating Curve= 0 ,0
Exp/Cntr=0.3,0.1

Type RM Length L Ch R = 1 ,17629   ,351,351,351
BEGIN DESCRIPTION:
CASIDY BRANCH 31.0
END DESCRIPTION:
XS GIS Cut Line= 3
      3752290.68     10228793.86      3752150.06     10228343.38
      3751428.71     10227830.35
#Sta/Elev= 30
  4243.6  297.74  4303.8  295.59  4368.8   291.9  4406.5   291.2  4471.5  287.34
  4529.4  285.78  4541.7  284.32  4571.7  284.08  4700.6   278.3  4776.7  275.86
    4848  276.53  4877.5  275.25  4898.4  275.54  4919.3  273.86  4975.9  275.24
  5003.6  268.32  5007.1  268.32  5012.7  273.67    5016 275.514  5020.2  277.86
    5062  280.32    5121  281.59  5163.7  283.86  5278.4  289.77  5328.8  290.75
  5370.6  293.58  5492.4  297.69  5528.1  299.95  5564.9  300.04  5600.7  301.96
#Mann= 7 ,-1 , 0
  4243.6     .11       0  4571.7     .17       0  4700.6     .15       0
  4975.9     .09       0    5016     .12       0  5020.2     .15       0
  5163.7     .17       0
Bank Sta=4975.9,5016
XS Rating Curve= 0 ,0
Exp/Cntr=0.3,0.1

Type RM Length L Ch R = 1 ,17278   ,281,281,281
BEGIN DESCRIPTION:
CASIDY BRANCH 30.0
END DESCRIPTION:
XS GIS Cut Line= 3
      3752353.19     10228765.26      3752311.52     10228332.96
      3751562.33      10227466.7
#Sta/Elev= 30
  4303.8   297.8  4407.5  292.24  4488.8  288.98    4529  288.39  4584.6   285.4
  4617.2  284.26  4649.6  281.21  4679.7  279.86  4871.8  275.12  4940.2  275.09
  4947.8  274.33  4982.9  273.04  4990.6  269.05  4995.4  267.81  4998.9  267.81
  5004.8  270.39  5018.2  273.21  5032.3  273.56  5039.9  274.76  5138.7  278.48
  5201.2  282.32  5316.3  288.25  5472.1  293.13    5550  294.11  5578.5  296.25
  5621.3  296.57  5692.5  300.76  5756.2  302.04  5784.7  304.11  5883.4  307.01
#Mann= 6 ,-1 , 0
  4303.8     .11       0  4584.6     .17       0  4871.8     .15       0
  4947.8     .09       0  5039.9     .15       0  5201.2     .17       0
Bank Sta=4947.8,5039.9
XS Rating Curve= 0 ,0
Exp/Cntr=0.3,0.1

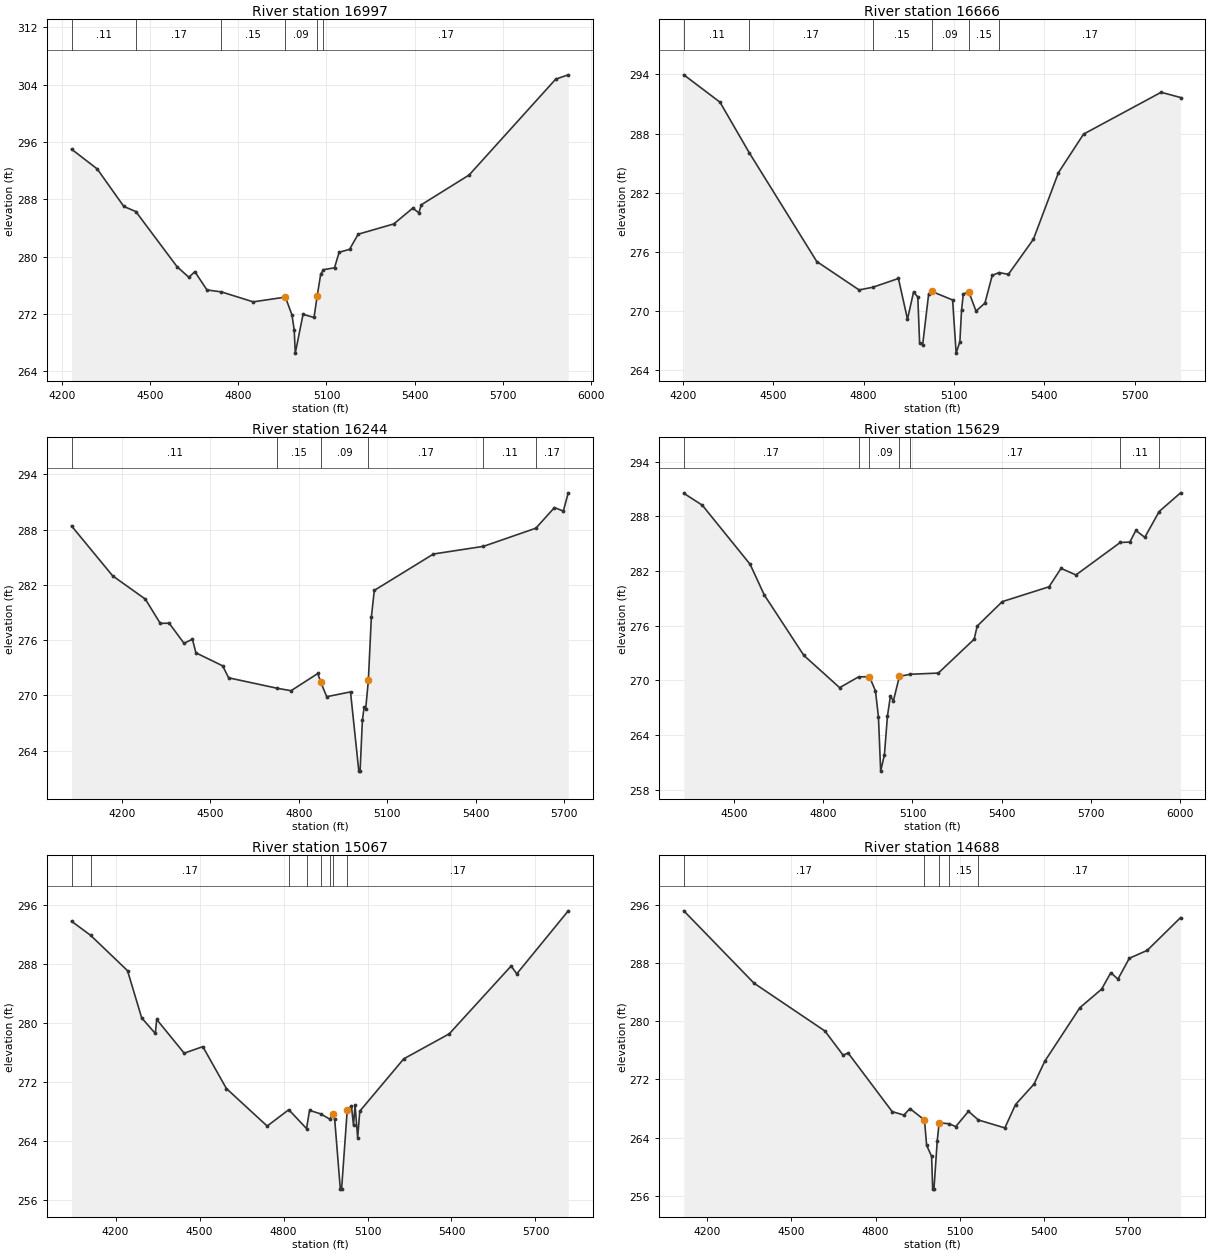
Type RM Length L Ch R = 1 ,16997   ,331,331,331
BEGIN DESCRIPTION:
Mapping XS 10123026
END DESCRIPTION:
XS GIS Cut Line= 4
      3752472.98     10228707.99       3752426.1     10228267.85
      3752264.65     10227845.98      3751626.66     10227372.05
#Sta/Elev= 30
    4233  294.99  4320.4  292.23  4410.9     287  4451.7  286.29  4591.9   278.6
  4632.2  277.12  4652.3  277.91  4693.6  275.36  4742.4  275.09  4850.7   273.7
  4960.2  274.36  4982.7  271.87  4990.3  269.76  4993.9  266.55  5020.3  271.96
  5057.6  271.52  5068.4  274.53  5080.4  277.57  5089.8  278.18  5127.3  278.45
    5143  280.61  5178.5  281.02  5207.7  283.13  5328.7  284.56  5393.3  286.76
  5414.2  286.11  5422.3  287.23  5585.2  291.39  5879.4  304.75  5922.1  305.35
#Mann= 6 ,-1 , 0
    4233     .11       0  4451.7     .17       0  4742.4     .15       0
  4960.2     .09       0  5068.4     .15       0  5089.8     .17       0
Bank Sta=4960.2,5068.4
XS Rating Curve= 0 ,0
Exp/Cntr=0.3,0.1

Type RM Length L Ch R = 1 ,16666   ,422,422,422
BEGIN DESCRIPTION:
CASIDY BRANCH 29.0
END DESCRIPTION:
XS GIS Cut Line= 3
      3752530.27     10228710.55        3752611.     10227851.19
      3752905.29     10227121.98
#Sta/Elev= 30
  4202.8  293.96  4322.8  291.19  4419.9  286.07  4644.2  275.03  4784.8  272.15
  4830.4  272.42  4915.4  273.31  4945.5  269.18  4965.6  271.93  4979.8  271.44
  4985.7  266.81  4995.8  266.57  5015.8  271.74  5025.9     272  5095.3  271.13
  5107.1  265.74  5119.5  266.91  5124.9  270.07  5130.8  271.72    5149  271.97
  5173.1     270  5202.7  270.82  5226.8  273.62  5249.4  273.91  5280.5  273.73
  5363.7  277.29  5446.9  284.05  5530.2  287.95  5787.8  292.19  5852.3  291.66
#Mann= 6 ,-1 , 0
  4202.8     .11       0  4419.9     .17       0  4830.4     .15       0
  5025.9     .09       0    5149     .15       0  5249.4     .17       0
Bank Sta=5025.9,5149
XS Rating Curve= 0 ,0
Exp/Cntr=0.3,0.1

Type RM Length L Ch R = 1 ,16244   ,615,615,615
BEGIN DESCRIPTION:
CASIDY BRANCH 28.0
END DESCRIPTION:
XS GIS Cut Line= 3
       3752855.8     10228809.48      3753006.83     10227723.58
      3753043.18     10227134.25
#Sta/Elev= 30
  4028.1   288.4  4167.8  282.98  4278.9  280.45  4329.4  277.82  4359.7  277.84
  4410.1  275.66  4438.8   276.1  4450.5  274.62  4541.4  273.21  4561.6  271.91
  4727.4  270.77  4773.6  270.51  4864.5  272.38  4873.7  271.49  4894.8  269.86
  4975.5  270.38  5003.7  261.78    5008  261.78  5015.9  267.33    5022  268.77
    5027  268.53  5036.1  271.62  5046.2  278.47  5056.3   281.4  5257.2  285.35
  5426.9  286.18  5604.8  288.15    5668  290.39    5698  290.01  5714.9  291.99
#Mann= 6 ,-1 , 0
  4028.1     .11       0  4727.4     .15       0  4873.7     .09       0
  5036.1     .17       0  5426.9     .11       0  5604.8     .17       0
Bank Sta=4873.7,5036.1
XS Rating Curve= 0 ,0
Exp/Cntr=0.3,0.1

Type RM Length L Ch R = 1 ,15629   ,562,562,562
BEGIN DESCRIPTION:
CASIDY BRANCH 27.0
END DESCRIPTION:
XS GIS Cut Line= 3
      3753316.73     10228773.08      3753258.23     10228106.84
      3753144.85     10227111.58
#Sta/Elev= 30
  4331.2  290.54  4393.4  289.23  4554.1  282.75  4601.7  279.39  4734.8  272.75
  4855.2  269.21  4919.2   270.4  4955.6  270.41  4975.7  268.85  4985.7     266
  4993.2  260.05  5005.8  261.86  5015.9  266.08  5025.9  268.27    5036  267.76
  5056.1  270.45  5092.7  270.68    5187  270.81  5307.6  274.53  5317.8  275.97
  5402.1  278.65  5559.4  280.28  5599.6   282.3  5649.9  281.58  5798.7  285.14
  5831.1  285.19  5851.2  286.46  5881.4  285.71  5929.7  288.54  6001.7  290.59
#Mann= 7 ,-1 , 0
  4331.2     .17       0  4919.2     .15       0  4955.6     .09       0
  5056.1     .15       0  5092.7     .17       0  5798.7     .11       0
  5929.7     .17       0
Bank Sta=4955.6,5056.1
XS Rating Curve= 0 ,0
Exp/Cntr=0.3,0.1

Type RM Length L Ch R = 1 ,15067   ,379,379,379
BEGIN DESCRIPTION:
CASIDY BRANCH 26.0
END DESCRIPTION:
XS GIS Cut Line= 4
      3753829.76     10228788.72      3753759.44     10228340.77
      3753355.79     10227525.67      3753420.89     10227119.46
#Sta/Elev= 30
  4042.7  293.81  4110.7   291.9  4242.8  287.09  4293.4  280.67    4342  278.56
  4347.1  280.46  4445.2  275.88  4511.8  276.77  4595.9  271.08  4741.6  265.98
  4818.8   268.2  4882.2  265.64    4893  268.11  4932.3  267.64  4965.9  266.91
  4975.6  267.57  4982.7  266.95  5002.9  257.41  5007.4  257.41  5027.6  268.16
  5042.6  268.71    5050  266.09  5055.6  268.83  5064.9  264.38  5072.4     268
  5229.4  275.11    5392  278.51  5612.9  287.72  5633.2  286.66  5817.1  295.22
#Mann= 8 ,-1 , 0
  4042.7     .11       0  4110.7     .17       0  4818.8     .11       0
  4882.2     .15       0  4932.3     .17       0  4965.9     .12       0
  4975.6     .09       0  5027.6     .17       0
Bank Sta=4975.6,5027.6
XS Rating Curve= 0 ,0
Exp/Cntr=0.3,0.1

Type RM Length L Ch R = 1 ,14688   ,429,429,429
BEGIN DESCRIPTION:
CASIDY BRANCH 25.0
END DESCRIPTION:
XS GIS Cut Line= 3
      3754131.82       10228760.      3753868.23     10227916.84
        3753611.     10227067.33
#Sta/Elev= 30
  4116.6  295.17  4366.9  285.23  4619.7  278.66  4684.7  275.33  4702.2  275.65
  4859.4  267.59  4901.3  267.11  4922.5  268.01  4974.6  266.44  4982.2  262.97
    5000  261.44  5003.8  256.94  5008.3  256.94  5020.1  263.59  5026.9  266.05
  5062.8  265.92    5086  265.53  5131.4  267.63  5166.7  266.44  5261.1  265.35
  5299.2  268.56  5365.1  271.37  5403.2  274.49  5528.5  281.86    5606  284.41
  5638.9  286.67  5664.3  285.79  5704.8  288.65  5768.8  289.74  5887.6  294.24
#Mann= 5 ,-1 , 0
  4116.6     .17       0  4974.6     .07       0  5026.9     .15       0
  5062.8     .15       0  5166.7     .17       0
Bank Sta=4974.6,5026.9
XS Rating Curve= 0 ,0
Exp/Cntr=0.3,0.1

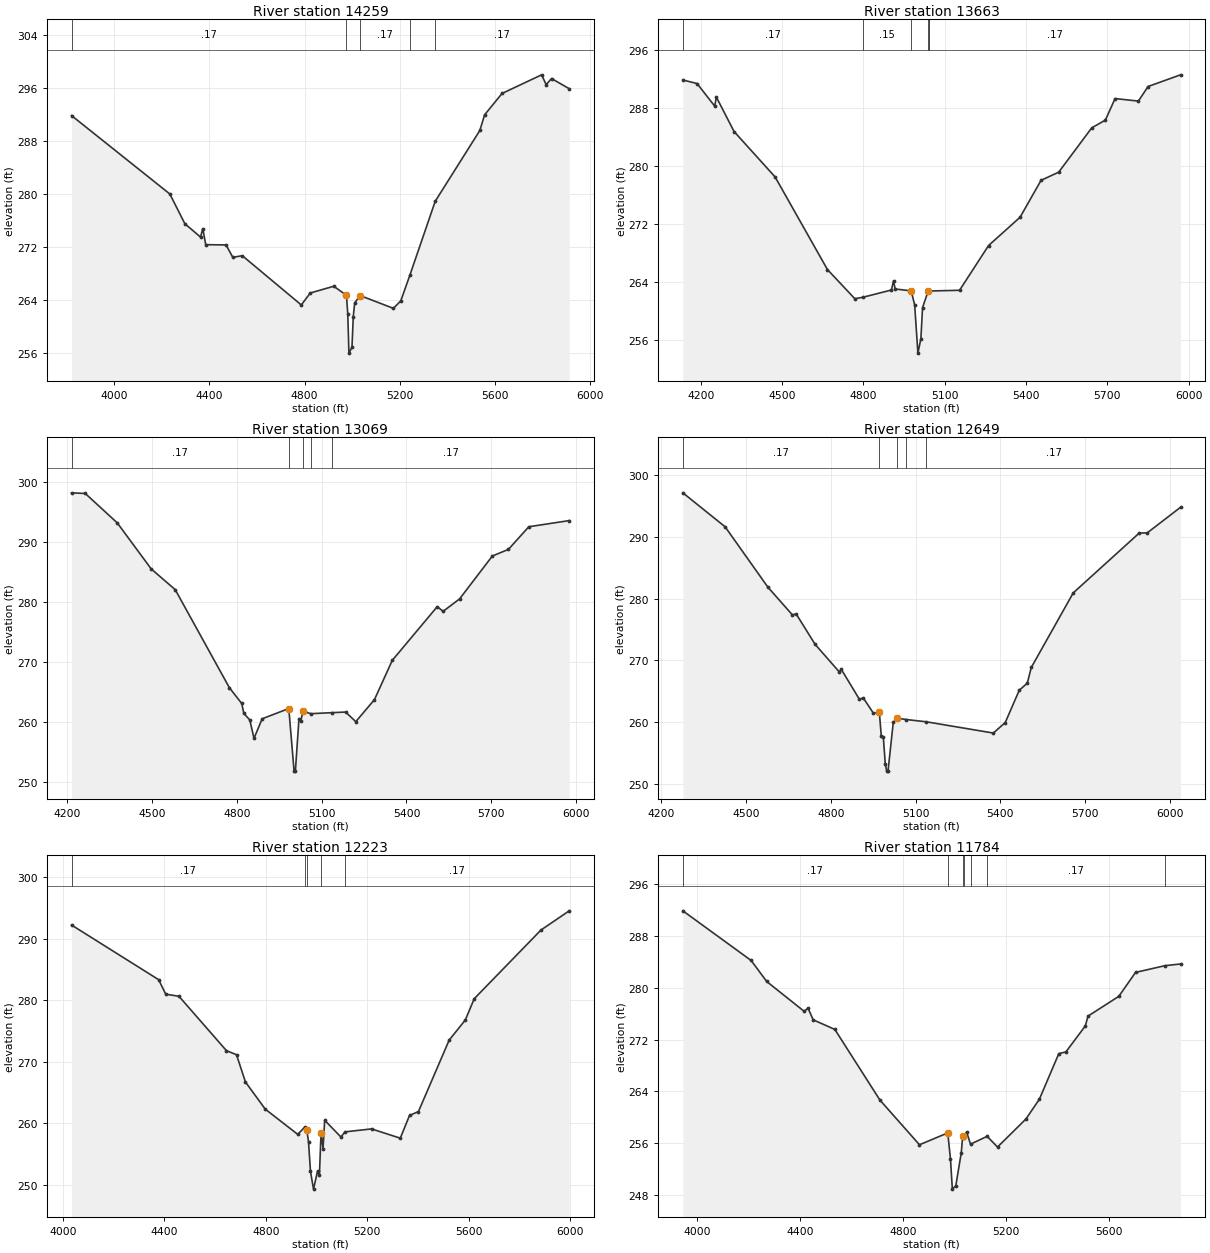
Type RM Length L Ch R = 1 ,14259   ,596,596,596
BEGIN DESCRIPTION:
CASIDY BRANCH 24.0
END DESCRIPTION:
XS GIS Cut Line= 3
      3754652.67     10228754.83       3754108.4     10227556.92
      3753897.45     10226809.48
#Sta/Elev= 30
    3820  291.79  4233.3  279.97  4296.4  275.49  4362.3  273.48  4371.7  274.75
  4384.3  272.33  4469.5   272.3    4498  270.43  4538.1  270.67  4785.9  263.25
  4823.7  265.05  4922.5  266.07  4975.9   264.7  4981.4  261.87  4986.2  255.99
    4999  256.85  5004.5  261.49  5010.4  263.55  5033.1  264.67    5173  262.74
  5204.2  263.86  5242.5  267.74  5349.1  278.88  5536.7  289.55  5556.7   291.9
  5629.9  295.12  5796.4  297.93  5815.5  296.45    5838  297.37  5912.4  295.84
#Mann= 5 ,-1 , 0
    3820     .17       0  4975.9     .09       0  5033.1     .17       0
  5242.5     .15       0  5349.1     .17       0
Bank Sta=4975.9,5033.1
XS Rating Curve= 0 ,0
Exp/Cntr=0.3,0.1

Type RM Length L Ch R = 1 ,13663   ,594,594,594
BEGIN DESCRIPTION:
CASIDY BRANCH 23.0
END DESCRIPTION:
XS GIS Cut Line= 3
      3755306.32     10228025.67      3754377.27     10227368.81
      3753972.97      10226799.1
#Sta/Elev= 30
  4134.1  291.83  4186.4  291.34  4251.6  288.23  4257.7  289.47    4323  284.73
  4474.4  278.47  4667.7   265.7  4768.6  261.69  4797.7  261.88  4903.8  262.89
  4911.4  264.16  4917.5  263.03  4976.7  262.77  4989.5  260.82  5001.4  254.19
  5012.4  256.17  5018.5  260.46  5039.4  262.76  5042.3  262.75  5155.1  262.85
  5262.2  269.02  5378.3  272.91  5455.8     278    5521  279.13  5642.8  285.23
  5693.2   286.3  5728.9  289.27    5815  288.92  5850.7  290.93  5970.5  292.54
#Mann= 6 ,-1 , 0
  4134.1     .17       0  4797.7     .15       0  4976.7     .09       0
  5039.4     .12       0  5042.3     .15       0  5042.3     .17       0
Bank Sta=4976.7,5039.4
XS Rating Curve= 0 ,0
Exp/Cntr=0.3,0.1

Type RM Length L Ch R = 1 ,13069   ,420,420,420
BEGIN DESCRIPTION:
CASIDY BRANCH 22.0
END DESCRIPTION:
XS GIS Cut Line= 3
      3755428.71      10227918.9       3755078.2     10227571.12
      3754372.14     10226518.93
#Sta/Elev= 30
  4214.9  298.27  4263.5  298.16  4376.6  293.25  4496.8  285.55  4581.7  282.09
  4773.5  265.69  4817.1  263.07  4824.5  261.41  4845.6  260.31  4860.5  257.24
  4889.4  260.51  4983.6  262.22  5002.3  251.76  5006.9  251.76  5019.6  260.54
  5025.6   260.1  5033.9  261.74  5062.1  261.36  5135.5  261.53  5184.6  261.63
  5220.7  260.03  5286.7  263.71  5349.7  270.27  5508.7  279.24  5529.8  278.47
  5587.9  280.54  5703.8  287.71  5760.8  288.82  5832.8   292.6  5975.8  293.63
#Mann= 5 ,-1 , 0
  4214.9     .17       0  4983.6     .09       0  5033.9     .17       0
  5062.1     .15       0  5135.5     .17       0
Bank Sta=4983.6,5033.9
XS Rating Curve= 0 ,0
Exp/Cntr=0.3,0.1

Type RM Length L Ch R = 1 ,12649   ,426,426,426
BEGIN DESCRIPTION:
CASIDY BRANCH 21.0
END DESCRIPTION:
XS GIS Cut Line= 3
      3755655.27     10227718.38      3755366.21     10227262.65
      3754475.55     10226426.68
#Sta/Elev= 30
  4276.5  297.13  4425.9  291.64  4577.5  281.86  4664.1  277.38  4677.5  277.53
  4744.4  272.62  4830.1  268.15  4837.4  268.55    4901  263.74  4915.1  263.94
  4950.8  261.47  4971.8  261.64  4978.6   257.8  4985.9  257.61  4992.8  253.29
  4997.8   252.1  5002.5   252.1  5021.1  259.98  5035.3  260.66  5066.9  260.45
  5138.3  260.08  5375.2  258.26  5417.4  259.96    5467  265.19  5495.4  266.33
  5509.5  268.87    5658  280.94  5891.5  290.62  5919.8  290.65  6037.7  294.79
#Mann= 5 ,-1 , 0
  4276.5     .17       0  4971.8     .09       0  5035.3     .17       0
  5066.9     .15       0  5138.3     .17       0
Bank Sta=4971.8,5035.3
XS Rating Curve= 0 ,0
Exp/Cntr=0.3,0.1

Type RM Length L Ch R = 1 ,12223   ,439,439,439
BEGIN DESCRIPTION:
CASIDY BRANCH 20.0
END DESCRIPTION:
XS GIS Cut Line= 3
      3755827.14     10227648.06      3755650.06     10227030.88
      3754634.41      10226187.1
#Sta/Elev= 30
  4034.2  292.24  4377.8  283.34  4405.6  280.98  4457.6  280.65  4644.9   271.8
  4684.7  271.13  4719.9   266.7    4798  262.28  4926.2  258.17  4954.3  259.38
  4962.1  258.83  4968.6  256.98  4976.4  252.14  4988.4  249.26  5004.2  252.19
  5011.6  251.53  5018.1  258.43  5025.9  255.86  5032.4  260.47  5096.2  257.75
  5112.9  258.58  5217.3  259.06  5330.5  257.55    5367  261.25  5402.2  261.89
  5523.3  273.51  5587.1  276.79  5622.2  280.25  5885.2  291.42  5996.7  294.55
#Mann= 5 ,-1 , 0
  4034.2     .17       0  4954.3     .12       0  4962.1     .09       0
  5018.1     .17       0  5112.9     .17       0
Bank Sta=4962.1,5018.1
XS Rating Curve= 0 ,0
Exp/Cntr=0.3,0.1

Type RM Length L Ch R = 1 ,11784   ,377,377,377
BEGIN DESCRIPTION:
CASIDY BRANCH 19.0
END DESCRIPTION:
XS GIS Cut Line= 3
      3755842.77     10227645.45      3755777.67     10226879.83
      3755431.33      10225767.9
#Sta/Elev= 30
  3945.7  291.92    4211  284.24  4271.2     281  4416.8  276.38  4431.8  276.87
  4451.9  275.07    4536  273.58  4710.9  262.67  4864.7  255.75  4974.6  257.58
  4985.1  253.54  4992.4  248.89    5006  249.44    5027   254.5  5032.6  257.11
  5037.8  256.84  5047.9  257.74  5062.9  255.84  5127.5  257.05  5167.9   255.4
  5278.4  259.74  5330.5   262.8    5406  269.85  5433.3   270.1  5508.9  274.12
  5519.3  275.64    5639   278.7    5704   282.4  5818.3  283.44  5878.7   283.7
#Mann= 7 ,-1 , 0
  3945.7     .17       0  4974.6     .09       0  5032.6     .12       0
  5037.8     .17       0  5062.9     .15       0  5127.5     .17       0
  5818.3     .11       0
Bank Sta=4974.6,5032.6
XS Rating Curve= 0 ,0
Exp/Cntr=0.3,0.1