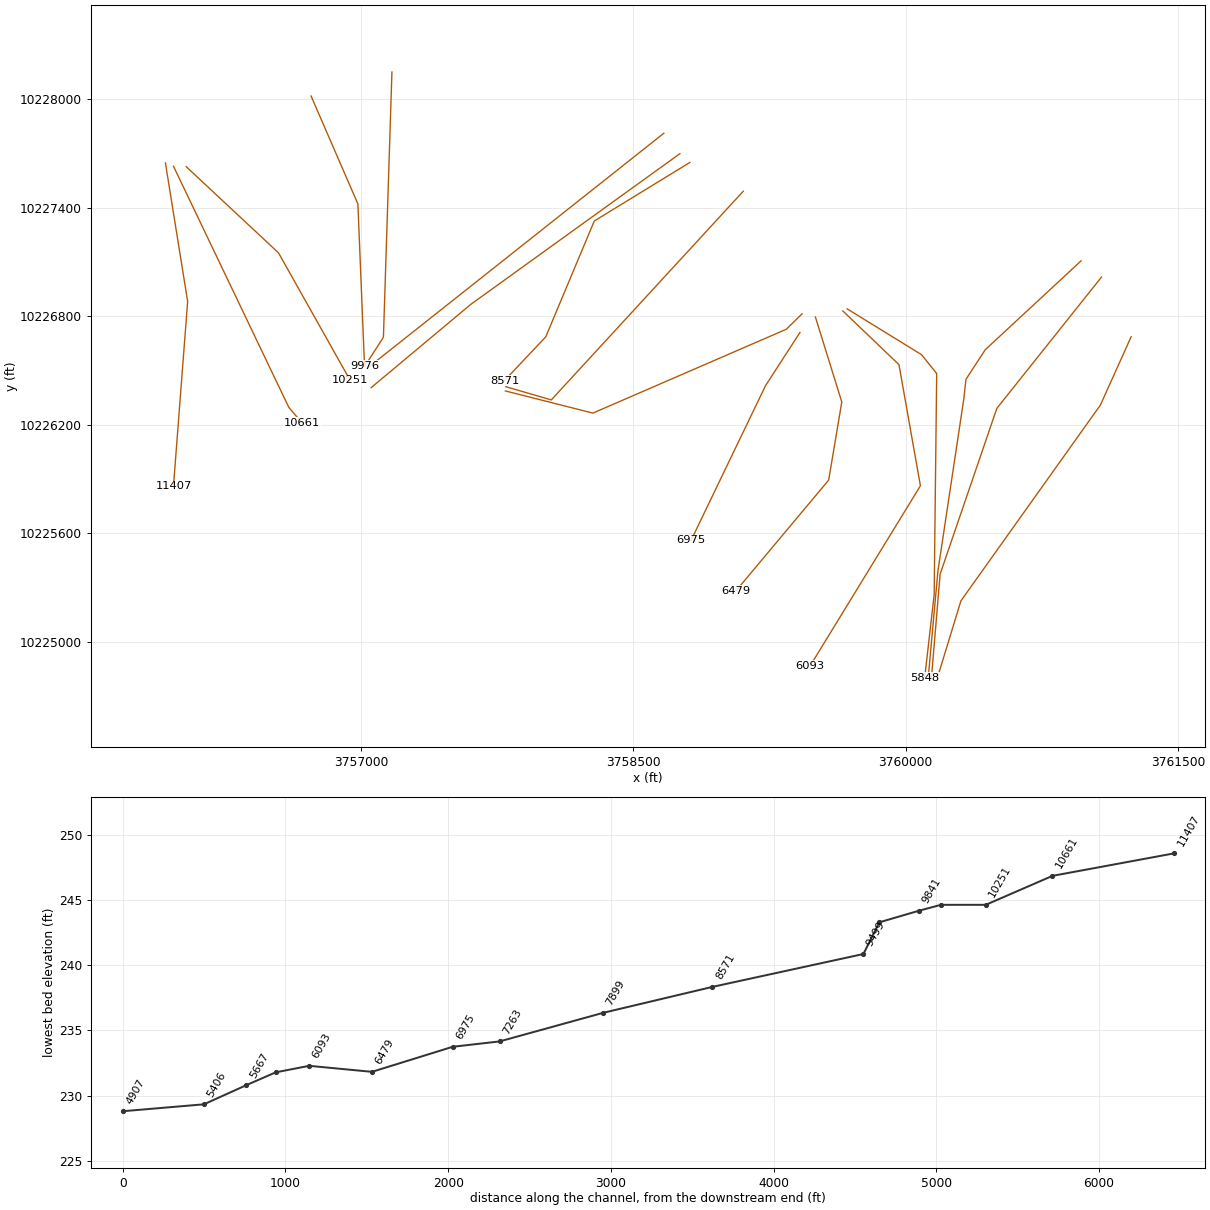
HEC-RAS study CASIDY BRANCH.prj: CASIDY BRANCH Base Level Engineering

--- CASIDY BRANCH.g01 (geometry) --- (continued)

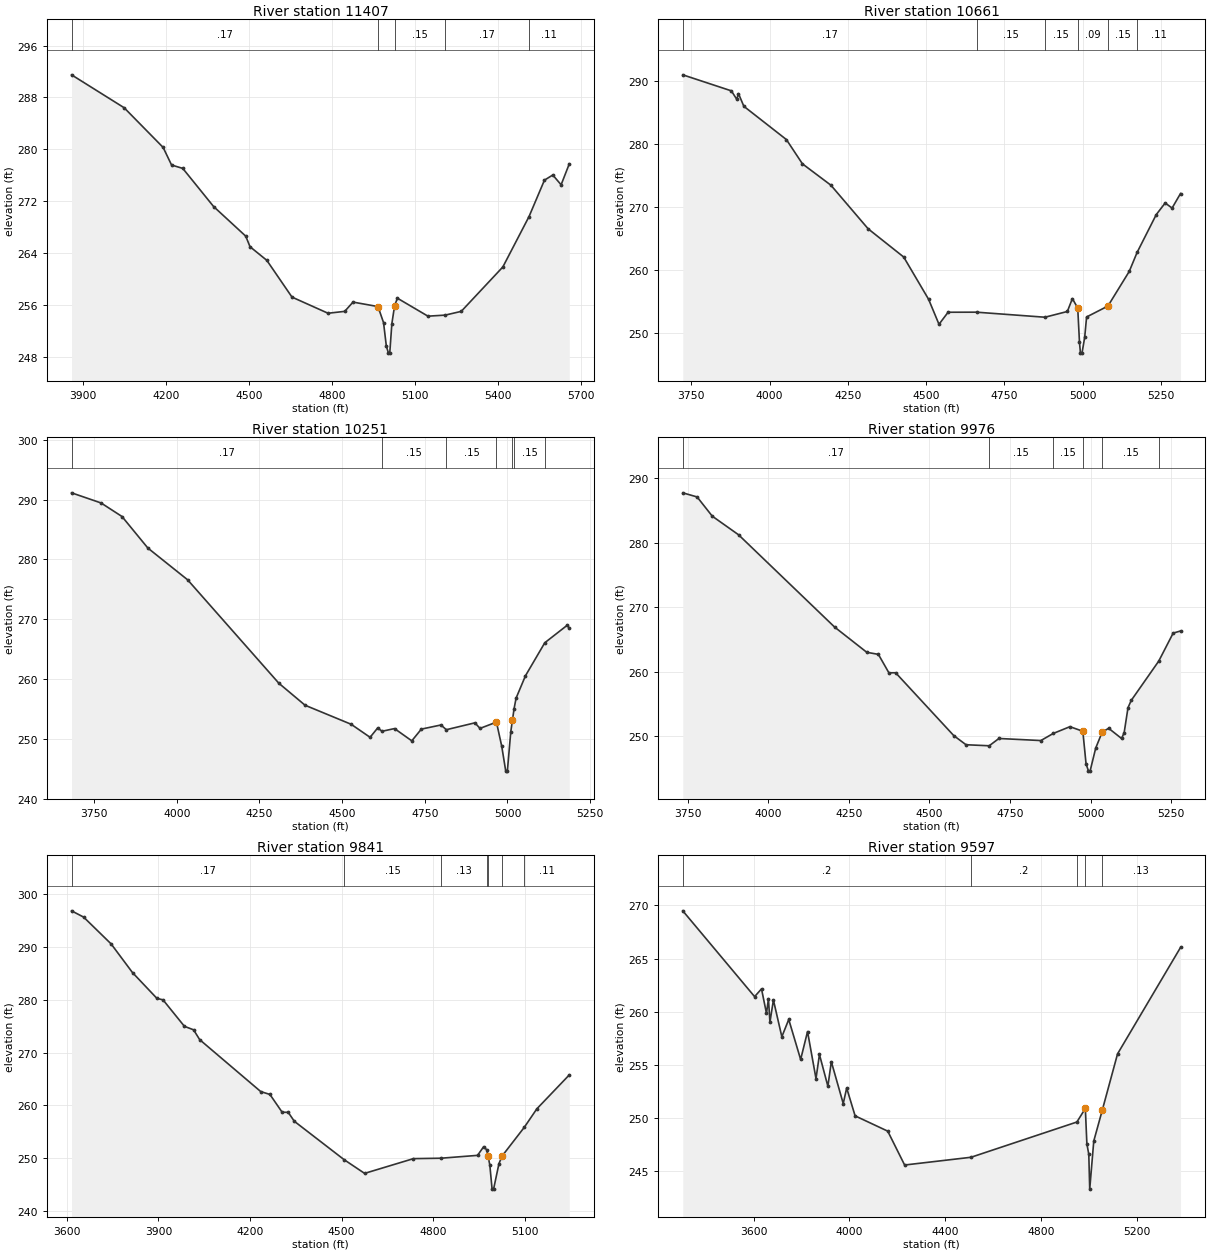
Type RM Length L Ch R = 1 ,11407   ,746,746,746
BEGIN DESCRIPTION:
Mapping XS 8053eac1
END DESCRIPTION:
XS GIS Cut Line= 3
       3755923.5     10227648.05       3756045.9     10226882.44
      3755967.77     10225861.56
#Sta/Elev= 30
    3858  291.48  4048.2   286.4  4189.1  280.28  4219.5  277.57    4260  277.05
  4371.4  271.17  4487.6   266.6  4503.1  264.97  4563.8  262.87  4654.8   257.2
  4785.1  254.71  4845.3     255  4875.4  256.43  4965.7  255.74  4985.7  253.27
  4995.8  249.66  5003.4  248.56  5008.2  248.56  5015.8  253.11  5025.8   255.9
  5035.9  257.03  5146.2  254.26  5208.3  254.42  5266.6     255    5417  261.85
  5511.6  269.62  5567.4  275.24  5597.5  276.03  5627.6  274.52  5657.2  277.76
#Mann= 5 ,-1 , 0
    3858     .17       0  4965.7     .09       0  5025.8     .15       0
  5208.3     .17       0  5511.6     .11       0
Bank Sta=4965.7,5025.8
XS Rating Curve= 0 ,0
Exp/Cntr=0.3,0.1

Type RM Length L Ch R = 1 ,10661   ,410,410,410
BEGIN DESCRIPTION:
CASIDY BRANCH 18.0
END DESCRIPTION:
XS GIS Cut Line= 3
      3755967.78     10227629.81      3756603.19      10226296.5
      3756676.12     10226210.55
#Sta/Elev= 30
  3722.8  290.95    3878  288.41  3895.2  287.07  3900.7  287.97  3917.9  285.96
  4053.7  280.69    4105  276.84  4195.8  273.46  4314.9  266.54  4428.4  262.07
  4507.9  255.37  4541.1  251.41  4570.1  253.32  4660.9  253.33  4879.5  252.53
    4951  253.44  4967.1  255.48  4984.2  253.99  4989.8  248.53  4992.9  246.84
  4997.8  246.84  5006.4  249.33  5012.5  252.57  5080.6   254.3  5148.7  259.79
  5173.8   262.8  5234.9  268.79  5263.5  270.64  5285.5  269.83  5312.5  272.14
#Mann= 6 ,-1 , 0
  3722.8     .17       0  4660.9     .15       0  4879.5     .15       0
  4984.2     .09       0  5080.6     .15       0  5173.8     .11       0
Bank Sta=4984.2,5080.6
XS Rating Curve= 0 ,0
Exp/Cntr=0.3,0.1

Type RM Length L Ch R = 1 ,10251   ,275,275,275
BEGIN DESCRIPTION:
CASIDY BRANCH 17.0
END DESCRIPTION:
XS GIS Cut Line= 3
      3756038.06     10227627.25      3756546.14     10227151.07
      3756941.42     10226445.49
#Sta/Elev= 30
  3681.9  291.12    3771  289.43  3834.5  287.16  3912.7  281.89  4032.8  276.59
  4308.8   259.3    4388  255.63  4527.3  252.45  4584.6  250.27  4607.5  251.83
  4620.9  251.28  4658.5  251.73  4710.7  249.68  4739.6  251.64  4798.9  252.33
  4815.2  251.54  4901.6  252.69    4917  251.76  4966.7  252.81  4982.7  248.77
  4994.8  244.62  4999.7  244.62  5010.1  251.23    5015 253.117  5020.1  255.08
  5026.1  256.82  5054.5  260.56  5112.9  266.07  5180.6  268.99    5187  268.52
#Mann= 7 ,-1 , 0
  3681.9     .17       0  4620.9     .15       0  4815.2     .15       0
  4966.7     .09       0    5015     .12       0  5020.1     .15       0
  5112.9     .11       0
Bank Sta=4966.7,5015
XS Rating Curve= 0 ,0
Exp/Cntr=0.3,0.1

Type RM Length L Ch R = 1 ,9976    ,135,135,135
BEGIN DESCRIPTION:
CASIDY BRANCH 16.0
END DESCRIPTION:
XS GIS Cut Line= 3
       3756725.6     10228017.83       3756983.4      10227421.5
      3757019.85     10226528.31
#Sta/Elev= 30
  3734.9  287.76  3779.4  287.12  3826.4  284.14  3907.8  281.26    4206  266.94
  4305.5  263.04  4341.5  262.72  4374.1  259.86    4395  259.87  4575.2  250.13
  4613.3  248.71  4685.2  248.55  4715.3  249.68  4845.4  249.36  4883.8  250.46
  4935.5  251.51  4975.5   250.8  4985.5  245.77  4993.1  244.62    4998  244.62
  5015.5   248.2  5035.5  250.66  5055.6  251.26  5095.6  249.68  5103.7  250.58
  5115.6  254.45  5125.6  255.58    5211  261.68  5255.7  266.02  5278.5  266.34
#Mann= 6 ,-1 , 0
  3734.9     .17       0  4685.2     .15       0  4883.8     .15       0
  4975.5     .09       0  5035.5     .15       0    5211     .11       0
Bank Sta=4975.5,5035.5
XS Rating Curve= 0 ,0
Exp/Cntr=0.3,0.1

Type RM Length L Ch R = 1 ,9841    ,244,244,244
BEGIN DESCRIPTION:
CASIDY BRANCH 15.0
END DESCRIPTION:
XS GIS Cut Line= 3
       3757170.9     10228150.64      3757124.02     10226684.52
       3757035.5     10226546.54
#Sta/Elev= 30
  3615.5  296.84  3655.1  295.65  3745.1  290.58  3815.2  285.15  3895.2  280.27
  3915.2  279.99  3985.3  274.98  4015.3  274.32  4035.3  272.46  4235.4  262.63
  4265.4  262.09  4305.4  258.73  4325.4   258.7  4345.4  257.01  4508.4  249.75
  4575.6  247.15  4735.6  249.94  4825.7  250.02  4945.7  250.56  4965.8  252.21
  4975.8   251.6    4980 250.407  4985.8  248.76  4993.3  244.17  4998.2  244.17
  5015.8  248.98  5025.8  250.41  5098.7  255.86    5140  259.37  5246.3  265.79
#Mann= 7 ,-1 , 0
  3615.5     .17       0  4508.4     .15       0  4825.7     .13       0
  4975.8     .12       0    4980     .09       0  5025.8     .13       0
  5098.7     .11       0
Bank Sta=4980,5025.8
XS Rating Curve= 0 ,0
Exp/Cntr=0.3,0.1

Type RM Length L Ch R = 1 ,9597    ,98,98,98
BEGIN DESCRIPTION:
Mapping XS e2cb30f0
END DESCRIPTION:
XS GIS Cut Line= 2
      3758668.29     10227812.13      3757041.77     10226518.71
#Sta/Elev= 30
  3304.5  269.49  3604.4  261.41  3633.2  262.14    3654  259.83  3662.1  261.22
  3668.4     259  3682.9  261.09  3718.1  257.63  3746.9  259.26  3796.6  255.49
  3825.4  258.12  3860.7  253.69  3875.1  255.96  3910.3  252.97  3924.7  255.28
  3974.4  251.34  3988.8   252.8    4024  250.18  4160.2  248.74  4230.7  245.55
  4507.8  246.28  4949.9   249.6  4985.2  250.88  4991.6  247.55  4999.6  246.56
  5003.5  243.28  5020.4  247.81  5055.6  250.69  5119.7  256.02  5382.6  266.04
#Mann= 5 ,-1 , 0
  3304.5      .2       0  4507.8      .2       0  4949.9     .13       0
  4985.2     .09       0  5055.6     .13       0
Bank Sta=4985.2,5055.6
XS Rating Curve= 0 ,0
Exp/Cntr=0.3,0.1

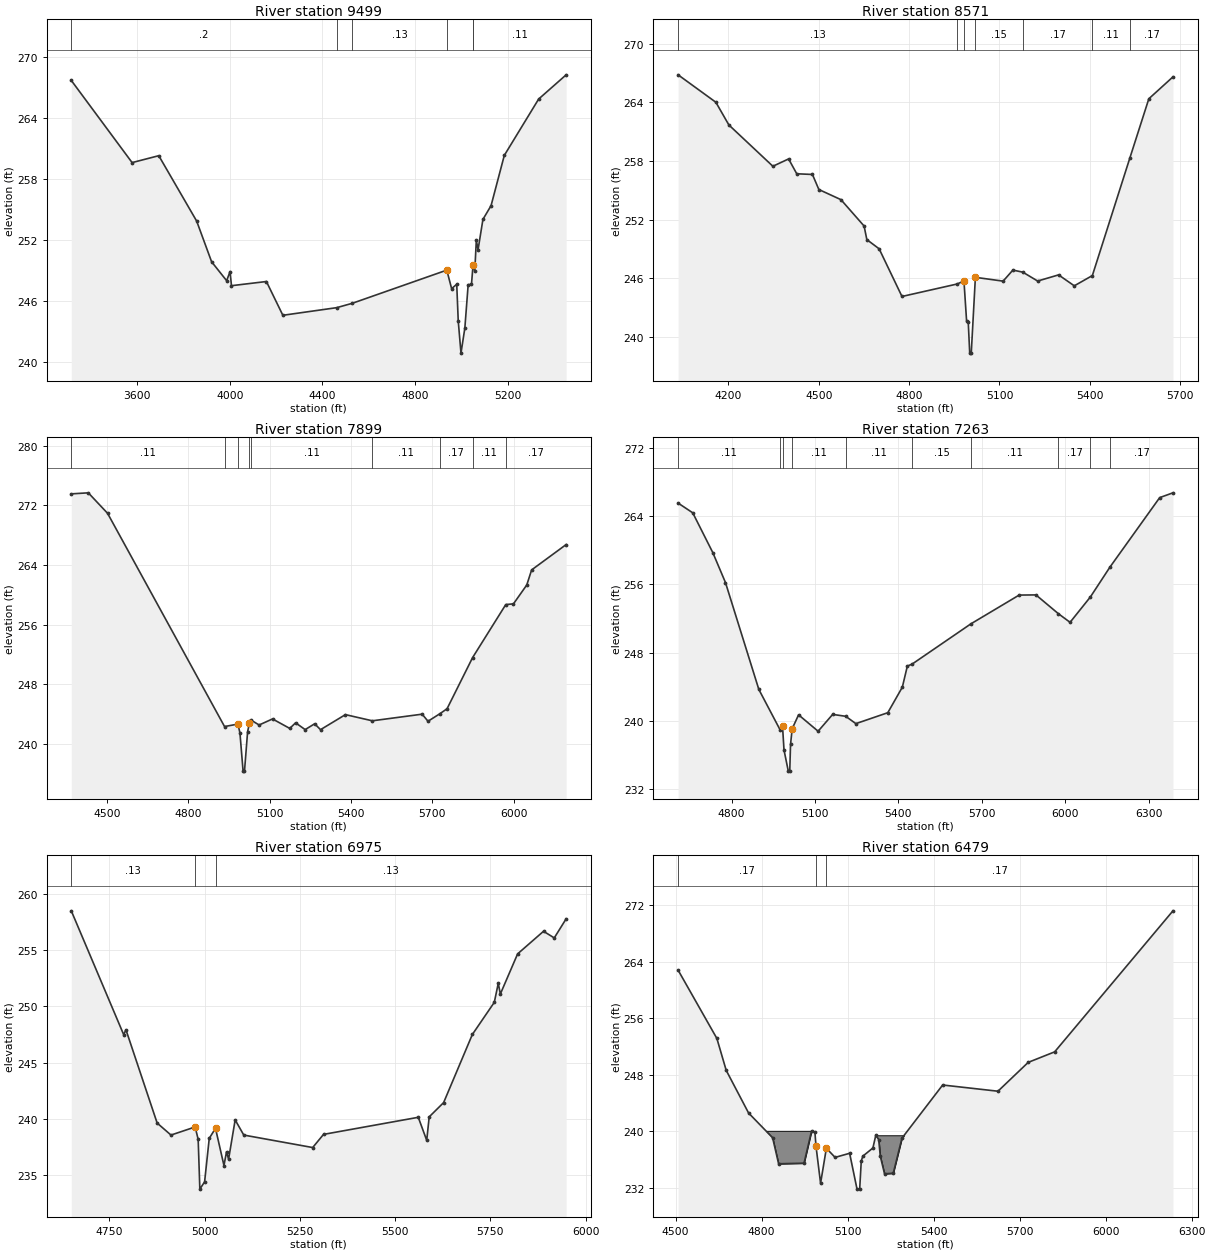
Type RM Length L Ch R = 1 ,9499    ,928,928,928
BEGIN DESCRIPTION:
CASIDY BRANCH 14.0
END DESCRIPTION:
XS GIS Cut Line= 3
      3758756.73     10227699.26      3757605.79     10226866.81
      3757056.42     10226405.97
#Sta/Elev= 30
  3315.1  267.66  3577.8  259.58    3693  260.26  3856.7  253.83  3921.2  249.83
  3986.2  247.97  4000.9  248.87    4007  247.48  4157.9  247.89    4229  244.57
  4461.6  245.32    4529  245.75  4937.1  249.01  4957.9  247.19    4980  247.62
  4986.5  244.02  4998.4  240.85  5015.1  243.32  5029.4  247.58  5043.7   247.6
  5050.3  249.47  5050.5  249.46    5058  248.93  5064.6  251.93  5072.2  251.03
  5093.2     254  5128.3  255.35  5185.5  260.29  5333.9  265.83  5452.6  268.21
#Mann= 6 ,-1 , 0
  3315.1      .2       0  4461.6     .17       0    4529     .13       0
  4937.1     .09       0  5050.3     .12       0  5050.5     .11       0
Bank Sta=4937.1,5050.3
XS Rating Curve= 0 ,0
Exp/Cntr=0.3,0.1

Type RM Length L Ch R = 1 ,8571    ,672,672,672
BEGIN DESCRIPTION:
CASIDY BRANCH 13.0
END DESCRIPTION:
XS GIS Cut Line= 4
      3758811.52     10227650.67       3758285.2     10227327.12
       3758018.1     10226686.98      3757790.66     10226444.91
#Sta/Elev= 30
  4032.6  266.82  4158.1  264.01  4201.2  261.69  4347.4  257.46  4399.6  258.21
  4426.7  256.69  4478.8  256.62  4500.1  255.08  4573.5  254.04  4650.4  251.34
  4659.5  249.95  4700.3  249.01  4776.2  244.13    4960  245.41    4982  245.73
  4990.8  241.62  4996.2  241.55  5001.2  238.33  5006.3  238.33    5020  246.09
  5112.1   245.7  5144.5  246.83  5177.5  246.62  5226.8  245.71  5296.3  246.34
  5348.5  245.22  5408.5  246.27    5533   258.3  5596.1  264.37  5676.2  266.61
#Mann= 7 ,-1 , 0
  4032.6     .13       0    4960     .15       0    4982     .09       0
    5020     .15       0  5177.5     .17       0  5408.5     .11       0
    5533     .17       0
Bank Sta=4982,5020
XS Rating Curve= 0 ,0
Exp/Cntr=0.3,0.1

Type RM Length L Ch R = 1 ,7899    ,636,636,636
BEGIN DESCRIPTION:
Mapping XS 28fc3c7b
END DESCRIPTION:
XS GIS Cut Line= 3
      3759105.78      10227491.8       3758048.5     10226338.17
      3757798.46      10226411.1
#Sta/Elev= 30
  4368.3  273.53  4431.1  273.67    4502  270.93  4933.6  242.32    4983  242.65
  4990.4  241.46    5002  236.34  5007.2  236.34  5018.7  241.64  5025.5  242.78
  5032.9  243.15  5061.1  242.53  5110.6  243.34  5174.1  242.07  5195.7  242.82
  5230.9  241.91    5266  242.69  5287.6   241.9  5379.5  243.92  5478.7  243.09
  5662.5  243.98  5684.1  243.03  5727.9  244.04  5754.4  244.71  5848.4  251.56
  5970.9  258.68  5999.3  258.78  6048.4  261.31  6066.3  263.33  6193.6  266.73
#Mann= 9 ,-1 , 0
  4368.3     .11       0  4933.6     .11       0    4983     .06       0
  5025.5     .09       0  5032.9     .11       0  5478.7     .11       0
  5727.9     .17       0  5848.4     .11       0  5970.9     .17       0
Bank Sta=4983,5025.5
XS Rating Curve= 0 ,0
Exp/Cntr=0.3,0.1

Type RM Length L Ch R = 1 ,7263    ,288,288,288
BEGIN DESCRIPTION:
CASIDY BRANCH 12.0
END DESCRIPTION:
XS GIS Cut Line= 4
      3759429.52     10226813.88      3759342.77     10226728.79
      3758277.67     10226265.25      3757795.88     10226387.65
#Sta/Elev= 30
  4607.6  265.53  4660.3  264.39  4732.5  259.73  4778.1  256.22  4898.1  243.71
  4974.4  238.99  4983.2  239.44  4988.6  236.63    5004  234.15  5009.3  234.15
  5012.1  237.27    5018  239.11    5041  240.74  5111.3  238.82  5163.6  240.79
  5210.5  240.57  5247.1  239.71    5362  240.99  5414.3  243.98  5432.3  246.45
    5449  246.67  5660.8  251.39  5834.5  254.76  5894.9  254.78    5976  252.57
  6017.7  251.57    6091  254.55  6160.8  258.02  6340.1  266.17  6387.8  266.73
#Mann= 10 ,-1 , 0
  4607.6     .11       0  4974.4     .11       0  4983.2     .06       0
    5018     .11       0  5210.5     .11       0    5449     .15       0
  5660.8     .11       0    5976     .17       0    6091     .11       0
  6160.8     .17       0
Bank Sta=4983.2,5018
XS Rating Curve= 0 ,0
Exp/Cntr=0.3,0.1

Type RM Length L Ch R = 1 ,6975    ,496,496,496
BEGIN DESCRIPTION:
CASIDY BRANCH 11.0
END DESCRIPTION:
XS GIS Cut Line= 3
      3759417.83     10226711.04      3759228.23     10226416.84
      3758817.84     10225561.06
#Sta/Elev= 30
    4650   258.5  4787.6  247.48  4793.5  247.92  4875.4  239.62  4911.7  238.55
  4975.1  239.27  4983.1  238.17  4987.5  233.74    5000  234.39  5012.2  238.26
  5028.6  239.15  5050.8  235.84  5057.5  237.06    5063  236.41  5080.2   239.9
  5102.8  238.55  5283.7  237.44  5312.2  238.61  5560.9  240.13  5583.1  238.08
  5589.6  240.17  5627.5  241.44  5702.9   247.5  5760.5  250.36  5770.9  252.05
  5776.4   251.1  5821.7  254.67  5889.7  256.68  5917.9  256.09  5949.1  257.79
#Mann= 3 , 0 , 0
    4650     .13       0  4975.1     .07       0  5028.6     .13       0
Bank Sta=4975.1,5028.6
XS Rating Curve= 0 ,0
Exp/Cntr=0.3,0.1

Type RM Length L Ch R = 1 ,6479    ,386,386,386
BEGIN DESCRIPTION:
CASIDY BRANCH 10.0
END DESCRIPTION:
XS GIS Cut Line= 4
       3759503.1      10226795.9      3759648.23     10226326.84
        3759576.      10225894.9      3759065.61     10225282.95
#Sta/Elev= 30
    4509   262.8  4644.2  253.14  4676.8  248.62  4754.8  242.59  4838.6  239.09
  4859.5  235.41  4948.2  235.49  4974.6  240.07  4986.1   239.9    4990 237.873
  5005.9  232.65  5026.1   237.6  5056.5  236.31  5107.2  236.89    5133  231.82
  5142.3  231.82  5147.8  235.81  5153.4  236.49  5188.4  237.64  5198.5  239.44
  5208.6  238.83  5214.1  236.48  5228.9  233.99  5259.3  234.07  5289.7  239.03
  5431.7  246.55  5624.5  245.67  5729.9  249.75  5822.3  251.24  6234.8  271.19
#Mann= 3 , 0 , 0
    4509     .17       0    4990     .08       0  5026.1     .17       0
#Block Obstruct= 2 ,-1
    4770  4974.6  240.07  5198.5    5330  239.44
Bank Sta=4990,5026.1
XS Rating Curve= 0 ,0
Exp/Cntr=0.3,0.1

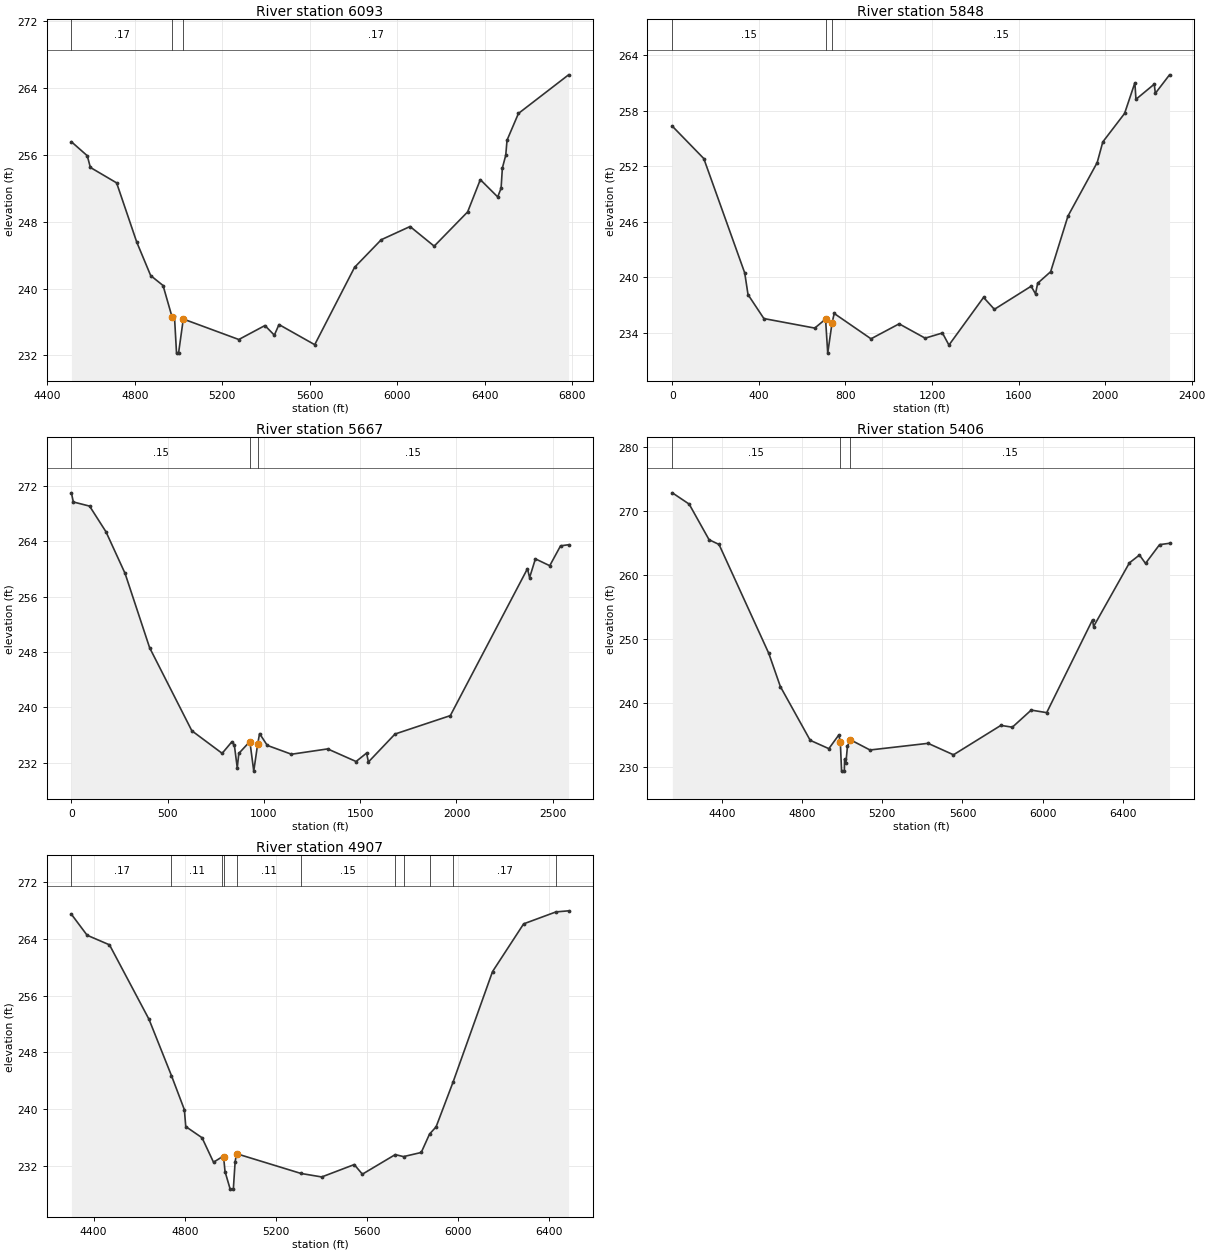
Type RM Length L Ch R = 1 ,6093    ,206,206,206
BEGIN DESCRIPTION:
CASIDY BRANCH 9.0
END DESCRIPTION:
XS GIS Cut Line= 4
      3759654.14     10226829.78      3759963.07     10226533.32
      3760081.21     10225863.65      3759474.44     10224868.87
#Sta/Elev= 30
    4510  257.57  4582.5   255.9  4596.7   254.5  4716.8  252.65  4808.7  245.57
  4872.5  241.56  4929.1  240.37  4970.9  236.55  4981.1  236.77  4990.7  232.28
    5000  232.28  5021.7  236.36  5275.5  233.91  5394.9  235.58    5438  234.43
  5459.2   235.7  5622.6  233.29  5804.9  242.55  5926.9  245.85  6058.6  247.43
  6168.9  245.08  6321.9  249.18  6379.9  253.04  6459.3  250.97  6474.8  252.01
  6480.7  254.44  6496.1  255.95    6502  257.76  6554.2  260.96  6783.4  265.58
#Mann= 3 , 0 , 0
    4510     .17       0  4970.9     .08       0  5021.7     .17       0
Bank Sta=4970.9,5021.7
XS Rating Curve= 0 ,0
Exp/Cntr=0.3,0.1

Type RM Length L Ch R = 1 ,5848    ,180,180,180
XS GIS Cut Line= 5
      3759677.79     10226841.54      3760087.51     10226588.07
      3760170.84      10226483.9      3760156.96     10225261.68
      3760104.87     10224803.35
#Sta/Elev= 30
       0  256.33   145.3  252.83   334.4  240.46   349.7  238.11     423  235.52
     658  234.49     708  235.46     718  231.78     738  235.05     748  236.07
     918  233.33    1048  234.95  1168.1   233.4  1248.1  233.96  1278.1  232.65
  1438.1  237.81  1488.1  236.52  1658.1  239.02  1678.1  238.19  1688.1  239.34
  1748.1  240.59  1828.1  246.61  1963.2   252.4  1989.1  254.63  2089.7  257.71
  2137.3  261.03  2142.3  259.24  2226.8  260.88  2231.9  259.89  2297.4  261.89
#Mann= 3 , 0 , 0
       0     .15       0     708     .07       0     738     .15       0
Bank Sta=708,738
XS Rating Curve= 0 ,0
Exp/Cntr=0.3,0.1

Type RM Length L Ch R = 1 ,5667    ,261,261,261
XS GIS Cut Line= 6
      3760965.98     10227106.82      3760438.58     10226615.85
      3760332.12     10226452.33      3760320.62     10226346.54
      3760177.53     10225391.58      3760123.97     10224799.53
#Sta/Elev= 30
       0  271.01      10  269.69    94.5  269.09   179.6  265.38   278.7  259.37
   406.3  248.63   625.6  236.63     783  233.37   833.7  235.05   846.3  234.57
   861.4  231.28   869.5  233.36     927  235.08   947.1   230.8   967.2  234.67
   977.3  236.22  1017.3  234.52  1142.9  233.24    1331  234.01  1478.5  232.19
  1533.2  233.41  1542.6  232.12  1680.8  236.16    1968  238.82  2368.7  260.05
  2379.8  258.76  2409.9  261.47  2484.4  260.48  2540.5  263.35  2582.2  263.51
#Mann= 3 , 0 , 0
       0     .15       0     927     .07       0   967.2     .15       0
Bank Sta=927,967.2
XS Rating Curve= 0 ,0
Exp/Cntr=0.3,0.1

Type RM Length L Ch R = 1 ,5406    ,499,499,499
BEGIN DESCRIPTION:
CASIDY BRANCH 8.0
END DESCRIPTION:
XS GIS Cut Line= 4
      3761078.58     10227017.27      3760502.22     10226291.61
      3760189.72     10225374.94      3760141.11     10224791.64
#Sta/Elev= 30
  4152.4  272.78  4236.3  271.02  4335.6  265.46  4385.3  264.72  4633.6  247.71
  4691.2  242.54  4840.2  234.14  4933.2  232.84  4982.8  234.97  4990.4  233.92
  4996.7  229.33  5010.5  229.33  5011.7   231.2    5018  230.54  5026.1  233.23
  5040.5  234.23  5138.5  232.63  5428.3  233.67  5555.1  231.88  5791.4  236.47
  5848.8  236.19  5942.8  238.86    6020  238.46  6248.9  252.96  6253.9   251.9
  6432.8  261.85    6483  263.07  6513.1  261.76  6583.3  264.69  6632.9   264.9
#Mann= 3 , 0 , 0
  4152.4     .15       0  4990.4     .07       0  5040.5     .15       0
Bank Sta=4990.4,5040.5
XS Rating Curve= 0 ,0
Exp/Cntr=0.3,0.1

Type RM Length L Ch R = 1 ,4907    ,284,284,284
BEGIN DESCRIPTION:
CASIDY BRANCH 7.0
END DESCRIPTION:
XS GIS Cut Line= 4
       3761241.8     10226687.45      3761072.43     10226309.77
       3760304.3     10225227.51      3760175.91     10224805.78
#Sta/Elev= 30
  4302.6  267.42  4371.6  264.47  4469.8  263.12    4643  252.67  4741.8  244.74
  4798.4  239.96  4804.5  237.59  4875.9  236.02  4926.3  232.58    4962  233.29
  4970.6  233.32  4976.8  231.27  4999.4   228.8  5013.3   228.8  5021.1  232.63
  5027.2  233.78  5310.4     231  5401.2  230.51  5543.9  232.25  5579.6   230.9
  5723.8  233.65  5760.2  233.37  5837.9  233.95  5874.4  236.54  5903.1  237.55
    5977  243.79  6150.7  259.36  6287.3  266.07  6429.4  267.75  6484.5   267.9
#Mann= 11 ,-1 , 0
  4302.6     .17       0  4741.8     .11       0    4962     .11       0
  4970.6     .07       0  5027.2     .11       0  5310.4     .15       0
  5723.8     .11       0  5760.2     .17       0  5874.4     .11       0
    5977     .17       0  6429.4     .11       0
Bank Sta=4970.6,5027.2
XS Rating Curve= 0 ,0
Exp/Cntr=0.3,0.1