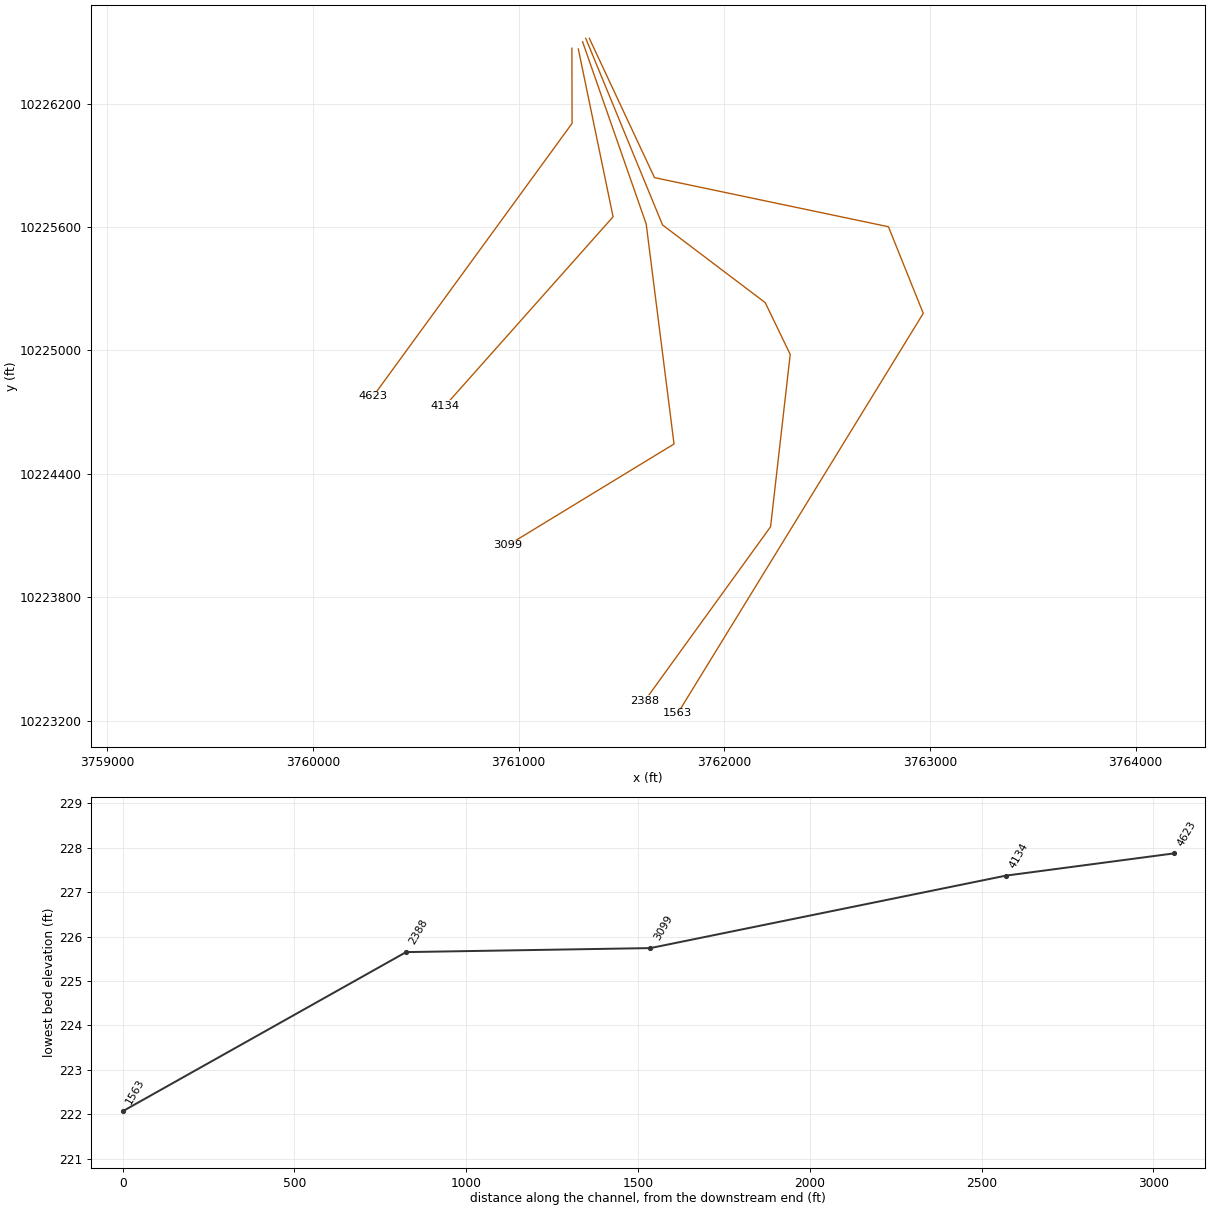
HEC-RAS study CASIDY BRANCH.prj: CASIDY BRANCH Base Level Engineering

--- CASIDY BRANCH.g01 (geometry) --- (continued)

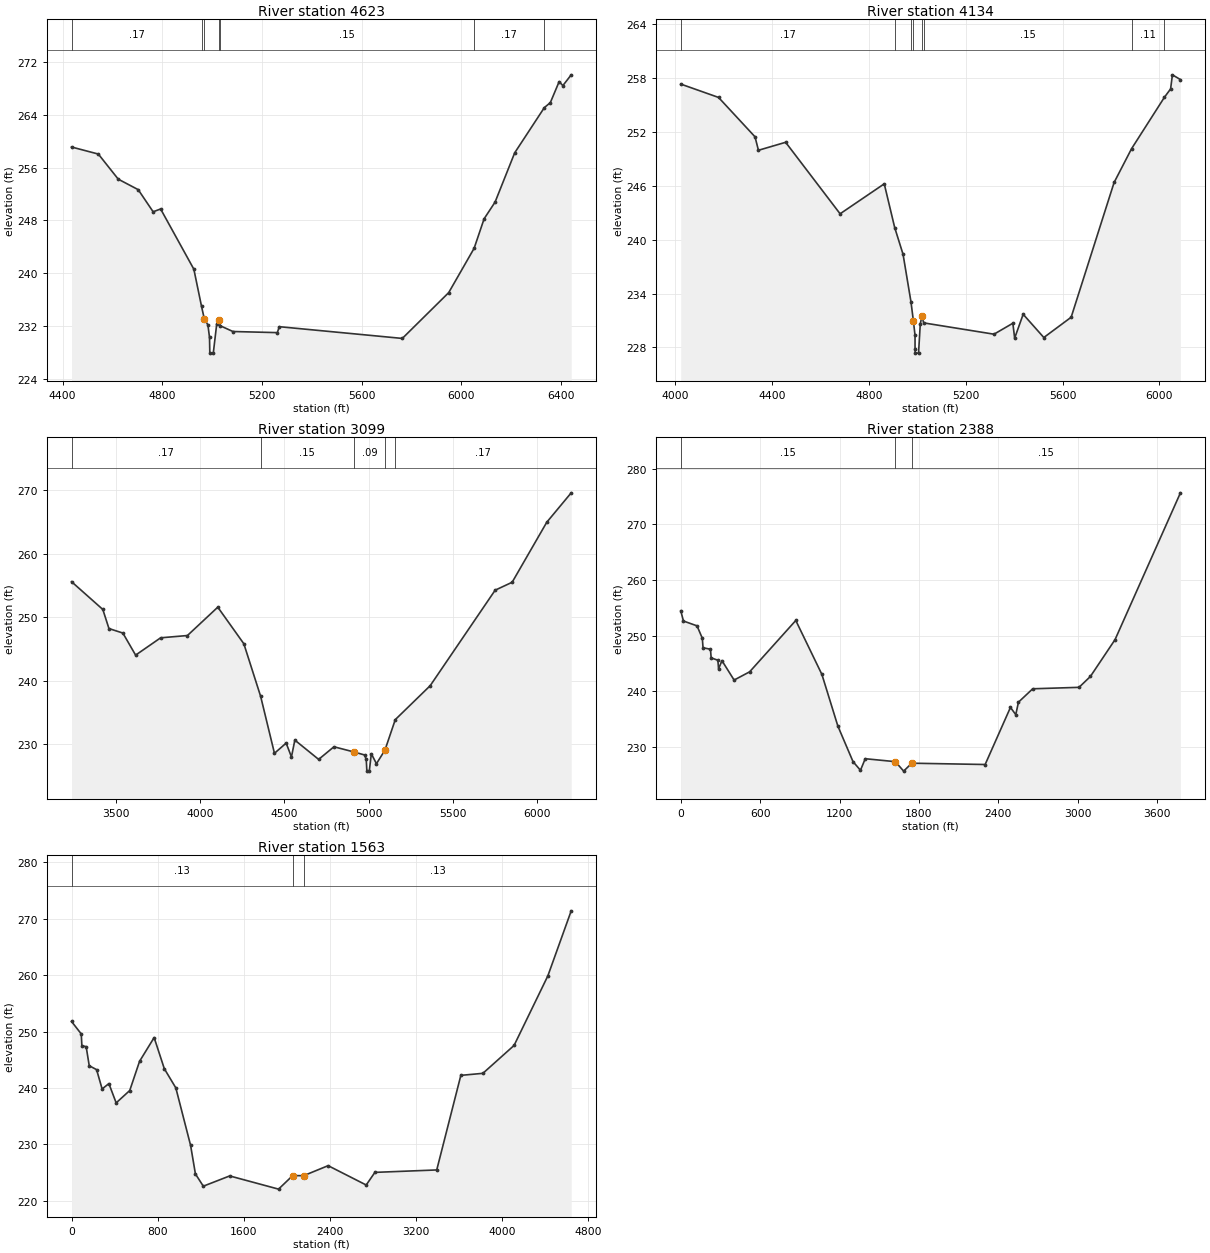
Type RM Length L Ch R = 1 ,4623    ,489,489,489
BEGIN DESCRIPTION:
CASIDY BRANCH 6.0
END DESCRIPTION:
XS GIS Cut Line= 3
      3761259.16     10226468.68      3761260.03     10226103.52
      3760293.91     10224777.76
#Sta/Elev= 30
  4435.6  259.14  4543.2  258.07  4623.2  254.26  4703.2  252.67  4763.2  249.31
  4793.2  249.74  4926.6   240.6  4957.5  234.95  4968.3  233.11    4983  232.15
  4989.4  230.26  4990.7  227.87  5004.6  227.87  5018.5  232.33  5026.5  232.84
  5033.2  232.01  5083.4  231.15  5261.6  230.98  5269.6  231.88  5763.3   230.1
  5949.5  237.05  6051.6  243.78  6091.6  248.25  6135.7  250.79  6214.4  258.26
  6333.4  265.12  6357.4  265.87  6392.9  269.07  6407.6  268.45  6441.2  270.09
#Mann= 7 ,-1 , 0
  4435.6     .17       0  4957.5     .15       0  4968.3     .09       0
  5026.5     .12       0  5033.2     .15       0  6051.6     .17       0
  6333.4     .11       0
Bank Sta=4968.3,5026.5
XS Rating Curve= 0 ,0
Exp/Cntr=0.3,0.1

Type RM Length L Ch R = 1 ,4134    ,1035,1035,1035
BEGIN DESCRIPTION:
CASIDY BRANCH 5.0
END DESCRIPTION:
XS GIS Cut Line= 3
      3761290.41     10226465.21      3761459.36     10225649.29
      3760641.97     10224730.08
#Sta/Elev= 30
  4023.4  257.36  4179.5  255.87  4330.1  251.48  4344.2  249.98  4456.5  250.87
  4681.4   242.9  4863.7  246.24  4906.8  241.37  4941.4  238.38    4974 233.098
  4984.1  230.95  4990.8  229.35  4990.9  227.87  4991.4  227.37  5005.3  227.37
  5012.5  230.63  5019.2  231.48  5026.7  230.74  5316.9  229.48  5394.7   230.7
  5402.2  229.04  5437.3   231.7  5522.6  229.11  5635.5  231.37  5812.8  246.39
  5884.8  250.15  6020.9   255.9  6046.1  256.82  6053.6  258.39  6086.7  257.86
#Mann= 8 ,-1 , 0
  4023.4     .17       0  4906.8     .15       0    4974     .12       0
  4984.1     .09       0  5019.2     .12       0  5026.7     .15       0
  5884.8     .11       0  6020.9     .17       0
Bank Sta=4984.1,5019.2
XS Rating Curve= 0 ,0
Exp/Cntr=0.3,0.1

Type RM Length L Ch R = 1 ,3099    ,711,711,711
BEGIN DESCRIPTION:
CASIDY BRANCH 4.0
END DESCRIPTION:
XS GIS Cut Line= 4
      3761311.23     10226499.97      3761620.27     10225614.52
      3761755.69     10224545.08       3760946.7     10224052.04
#Sta/Elev= 30
  3237.8  255.61  3423.4  251.23  3459.7  248.22  3542.3  247.51  3617.9  244.03
  3766.2  246.76  3925.1  247.12  4105.1  251.59  4259.7  245.82  4359.3  237.53
  4441.2  228.55  4510.6  230.16    4542  227.98  4562.1  230.63  4703.3  227.59
    4794  229.58  4911.3  228.77  4975.4  228.29  4985.5  227.59  4989.2  225.74
  5003.6  225.74  5015.7  228.48    5046  226.91  5096.4  229.05  5157.7  233.86
  5364.7  239.21    5750  254.27  5850.8  255.52    6056  264.98    6201  269.62
#Mann= 5 ,-1 , 0
  3237.8     .17       0  4359.3     .15       0  4911.3     .09       0
  5096.4     .15       0  5157.7     .17       0
Bank Sta=4911.3,5096.4
XS Rating Curve= 0 ,0
Exp/Cntr=0.3,0.1

Type RM Length L Ch R = 1 ,2388    ,825,825,825
XS GIS Cut Line= 6
      3761326.53     10226516.84      3761699.79     10225609.72
      3762198.92     10225232.12      3762320.45     10224980.38
      3762224.97     10224142.71      3761612.99     10223296.35
#Sta/Elev= 30
       0  254.48    20.4  252.63   123.1  251.76   163.1  249.52   168.4  247.82
   224.5  247.56   229.8  246.01   280.5  245.58   285.8  244.02   311.2  245.51
   403.2  242.02   520.6   243.5   869.2  252.73  1066.5  243.03  1187.2  233.74
  1301.6  227.36  1357.9   225.8  1393.9  227.88  1621.8  227.35  1684.1  225.65
  1745.6 227.075  2299.9  226.84  2491.1   237.1  2531.4   235.8  2551.5  238.04
  2659.3  240.45  3009.2  240.71    3095  242.66  3281.5  249.29  3775.4  275.67
#Mann= 3 , 0 , 0
       0     .15       0  1621.8     .09       0  1745.6     .15       0
Bank Sta=1621.8,1745.6
XS Rating Curve= 0 ,0
Exp/Cntr=0.3,0.1

Type RM Length L Ch R = 1 ,1563    ,0,0,0
XS GIS Cut Line= 5
      3761343.89     10226516.84      3761660.73     10225839.76
      3762797.88     10225601.04      3762967.15     10225180.03
      3761773.58     10223235.59
#Sta/Elev= 30
       0   251.8    90.5  249.58    96.1  247.52   136.2  247.31   164.6  243.95
   233.1  243.25   284.3  239.83   347.3  240.78   414.9  237.36     541  239.55
   632.4  244.73   767.8  248.94   862.5  243.42   969.4  240.02  1106.8  229.82
  1151.5  224.77  1224.9  222.59  1470.1  224.41  1924.2  222.07  2055.9  224.47
  2157.3  224.45  2385.1  226.23    2739   222.8  2819.6  225.04  3394.6  225.47
  3618.7  242.24  3823.6   242.6  4113.6  247.55  4427.2  259.87  4644.5  271.41
#Mann= 3 , 0 , 0
       0     .13       0  2055.9     .08       0  2157.3     .13       0
Bank Sta=2055.9,2157.3
XS Rating Curve= 0 ,0
Exp/Cntr=0.3,0.1
Stream Node=CASIDY BRANCH   ,Reach-1         , 0 , 0 ,Upstream end
Stream Node=CASIDY BRANCH   ,Reach-1         , 0 , 1 ,Downstream end

Chan Stop Cuts=-1
Use User Specified Reach Order=0
Composite Channel Slope=5