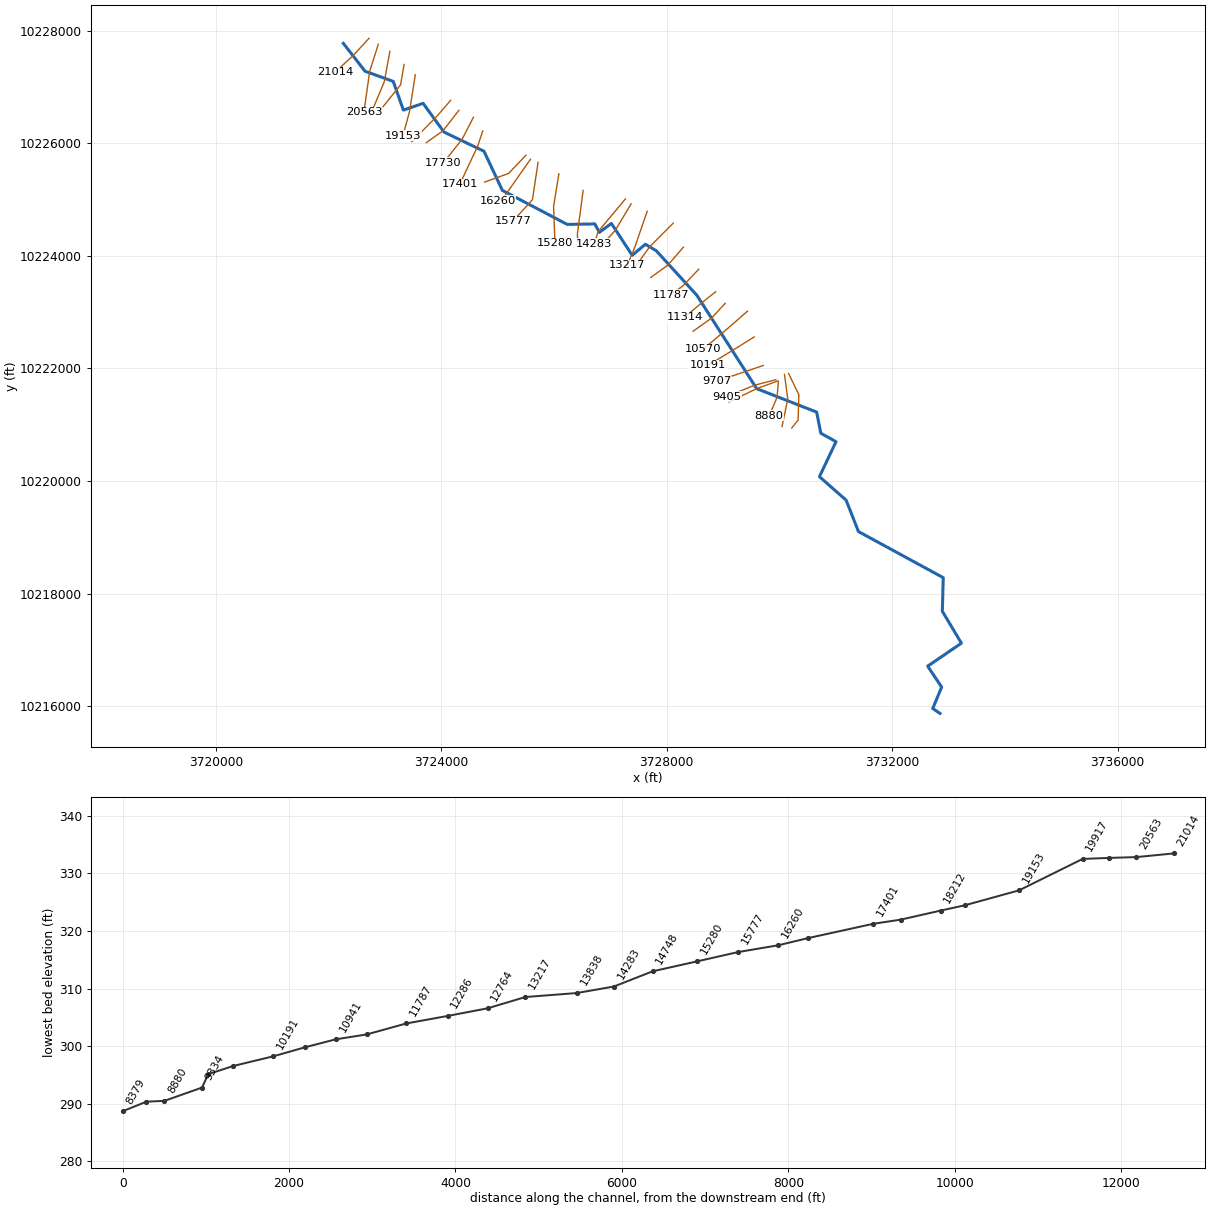
--- CLEAR BRANCH.prj (project) ---

Proj Title=CLEAR BRANCH Base Level Engineering
Current Plan=p01
Default Exp/Contr=0.3,0.1
English Units
Geom File=g01
Flow File=f01
Plan File=p01
Y Axis Title=Elevation
X Axis Title(PF)=Main Channel Distance
X Axis Title(XS)=Station
BEGIN DESCRIPTION:
CLEAR BRANCH
END DESCRIPTION:
DSS Export Rating Curves= 0
DSS Export Rating Curve Sorted= 0
DSS Export Volume Flow Curves= 0
DXF OffsetX= 0
DXF OffsetY= 0
DXF ScaleX= 1
DXF ScaleY= 10

--- CLEAR BRANCH.p01 (plan) ---

Plan Title=Multiple Run
Program Version=4.10
Short Identifier=Multiple
Geom File=g01
Flow File=f01
Subcritical Flow
K Sum by GR= 0
Std Step Tol= 0.01
Critical Tol= 0.01
Num of Std Step Trials= 20
Max Error Tol= 0.3
Flow Tol Ratio= 0.001
Split Flow NTrial= 30
Split Flow Tol= 0.02
Split Flow Ratio= 0.02
Log Output Level= 0
Friction Slope Method= 1
Unsteady Friction Slope Method= 2
Unsteady Bridges Friction Slope Method= 1
Parabolic Critical Depth
Global Vel Dist= 1 , 1 , 1
Global Log Level= 0
CheckData=True
Encroach Param=-1 ,0,0, 0
BEGIN DESCRIPTION:
Multiple Run
END DESCRIPTION:
Computation Interval=1HOUR
Output Interval=1HOUR
Run HTab= 0
Run UNet= 0
Run PostProcess= 0
Run WQNet= 0
UNET Theta= 1
UNET Theta Warmup= 1
UNET ZTol= 0.02
UNET ZSATol= 0.05
UNET MxIter= 20
UNET MaxInSteps= 0
UNET DtIC= 0
UNET DtMin= 0
UNET MaxCRTS= 20
UNET WFStab= 2
UNET SFStab= 1
UNET WFX= 1
UNET SFX= 1
UNET DSS MLevel= 4
UNET DZMax Abort= 100
UNET Convert EG Bridges= 0
UNET Use Existing IB Tables=-1
UNET Froude Reduction=False
UNET Froude Limit= 1
UNET Froude Power= 10
UNET Time Slicing=0,0, 5
UNET Junction Losses=0
Instantaneous Interval=1HOUR
Write IC File= 0
Write IC File at Sim End=0
Echo Input=False
Echo Parameters=False
Echo Output=False
Write Detailed= 0
WQ AD Non Conservative
WQ ULTIMATE=-1
WQ Max Comp Step=1HOUR
WQ Output Interval=15MIN
WQ Output Selected Increments= 0
WQ Output face flow=0
WQ Output face velocity=0
WQ Output face area=0
WQ Output face dispersion=0
WQ Output cell volume=0
WQ Output cell surface area=0
WQ Output cell continuity=0
WQ Output cumulative cell continuity=0
WQ Output face conc=0
WQ Output face dconc_dx=0
WQ Output face courant=0
WQ Output face peclet=0
WQ Output face adv mass=0
WQ Output face disp mass=0
WQ Output cell mass=0
WQ Output cell source sink temp=0
WQ Output cell source sink nsm=0
WQ Output MaxMinRange=-1
WQ Daily Max Min Mean=-1
WQ Daily Range=0
WQ Daily Time=0
WQ Create Restart=0
WQ Fixed Restart=0
WQ System Summary=0
WQ Use Fixed Temperature=0
Sorting and Armoring Iterations= 10
XS Update Threshold= 0.02
Hydraulics Update Threshold= 0.02
Energy Slope Method= 1
Volume Change Method= 0
XS Weighting Method= 0
Number of US Weighted Cross Sections= 1
Number of DS Weighted Cross Sections= 1
Upstream XS Weight=0.25
Main XS Weight=0.5
Downstream XS Weight=0.25
Number of DS XS's Weighted with US Boundary= 1
Upstream Boundary Weight= 1
Weight of XSs Associated with US Boundary= 0
Number of US XS's Weighted with DS Boundary= 1
Downstream Boundary Weight= 0.5
Weight of XSs Associated with DS Boundary= 0.5
Sediment Output Level= 4
Mass or Volume Output= 0
Output Increment Type= 1
Profile and TS Output Increment= 10
XS Output Flag= 0
XS Output Increment= 10
Disregard all LS=0
Disregard all Conn=0
Disregard all Breaches=0
Disregard all Pumps=0

--- CLEAR BRANCH.f01 (steady flow) ---

Flow Title=Multiple
Program Version=4.10
Number of Profiles= 7
Profile Names=10-year,25-year,50-year,1pct_min,100-year,1pct_plu,500-year
River Rch & RM=CLEAR BRANCH,Reach-1         ,21014
     777    1080    1487     674    2035    6146    3941
River Rch & RM=CLEAR BRANCH,Reach-1         ,20563
     827    1145    1572     709    2142    6469    4114
River Rch & RM=CLEAR BRANCH,Reach-1         ,16613
    1508    2145    2995    1371    4141   12506    8199
River Rch & RM=CLEAR BRANCH,Reach-1         ,7882
    2135    3068    4313    1984    5993   18099   11988
Boundary for River Rch & Prof#=CLEAR BRANCH,Reach-1         , 1
Up Type= 0
Dn Type= 3
Dn Slope=0.0055
Boundary for River Rch & Prof#=CLEAR BRANCH,Reach-1         , 2
Up Type= 0
Dn Type= 3
Dn Slope=0.0055
Boundary for River Rch & Prof#=CLEAR BRANCH,Reach-1         , 3
Up Type= 0
Dn Type= 3
Dn Slope=0.0055
Boundary for River Rch & Prof#=CLEAR BRANCH,Reach-1         , 4
Up Type= 0
Dn Type= 3
Dn Slope=0.0055
Boundary for River Rch & Prof#=CLEAR BRANCH,Reach-1         , 5
Up Type= 0
Dn Type= 3
Dn Slope=0.0055
Boundary for River Rch & Prof#=CLEAR BRANCH,Reach-1         , 6
Up Type= 0
Dn Type= 3
Dn Slope=0.0055
Boundary for River Rch & Prof#=CLEAR BRANCH,Reach-1         , 7
Up Type= 0
Dn Type= 3
Dn Slope=0.0055
DSS Import GetInterval= 0
DSS Import GetPeak= 0
DSS Import FillOption= 0

--- CLEAR BRANCH.g01 (geometry) ---

Geom Title=Existing Conditions
Program Version=4.10

River Reach=CLEAR BRANCH    ,Reach-1
Reach XY= 30
      3722263.23     10227771.84      3722648.23     10227276.84
      3723148.23     10227096.84      3723328.23     10226586.84
      3723678.23     10226706.84      3724048.23     10226196.84
      3724758.23     10225856.84      3725084.37     10225161.62
       3726235.6     10224557.53      3726723.96     10224566.16
      3726805.17     10224416.26      3727018.27     10224574.73
      3727387.44     10224009.33      3727620.65     10224205.27
      3727813.63     10224090.86      3728533.67     10223300.82
      3729596.17     10221642.02      3730660.19     10221225.28
      3730733.67     10220850.15       3731003.6     10220700.74
      3730709.81     10220079.41      3731182.82     10219661.77
      3731401.88     10219104.79      3732906.14     10218285.99
      3732889.63     10217689.34      3733228.46     10217123.01
      3732629.96     10216715.19      3732877.33     10216343.57
      3732719.53     10215962.47      3732848.23     10215876.84

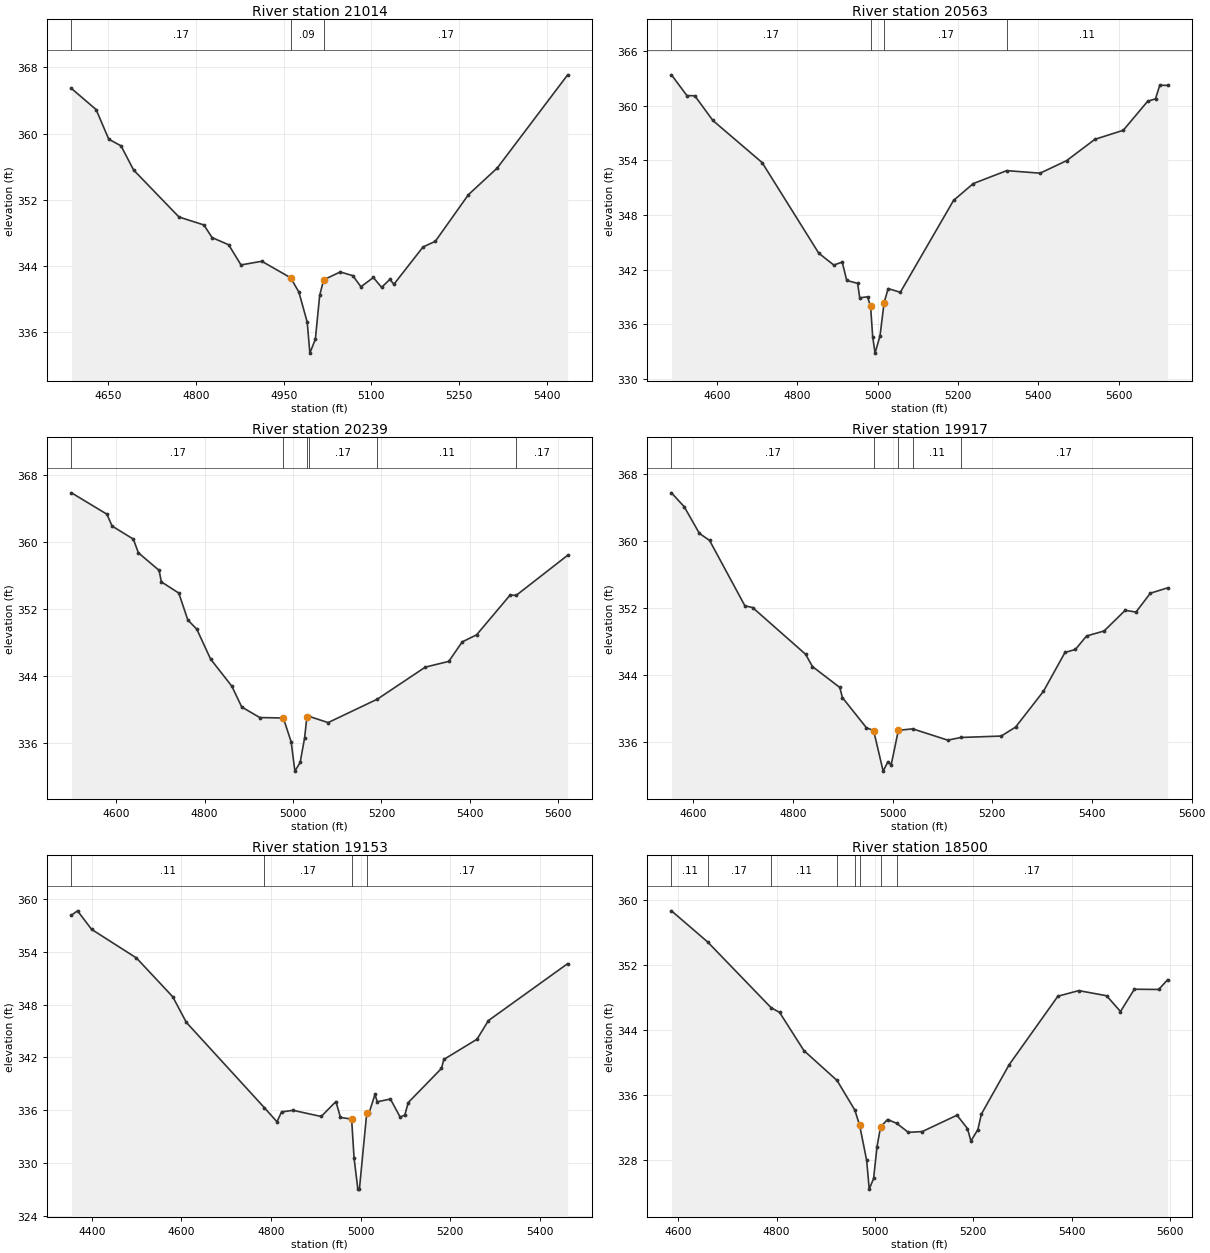
Type RM Length L Ch R = 1 ,21014   ,451,451,451
BEGIN DESCRIPTION:
CLEAR BRANCH 41.0
END DESCRIPTION:
XS GIS Cut Line= 3
      3722717.85     10227861.06      3722438.23     10227556.84
      3722117.88     10227261.09
#Sta/Elev= 30
  4586.8  365.46    4629  362.91  4650.6  359.33  4671.6  358.53  4693.1  355.61
  4770.8  349.93  4813.4  348.97  4827.5  347.44  4855.9  346.57  4876.9  344.14
  4912.6  344.58    4962  342.58  4976.1  340.84  4990.3  337.21  4994.8  333.48
  5004.2  335.16  5011.6  340.46  5018.4  342.34  5046.8  343.29  5068.3  342.84
  5082.2   341.5  5103.5  342.62  5117.6  341.43  5131.8   342.4  5138.6   341.8
  5188.5  346.31  5209.5  346.99  5266.2  352.63  5315.5  355.85    5436  367.11
#Mann= 3 ,-1 , 0
  4586.8     .17       0    4962     .09       0  5018.4     .17       0
Bank Sta=4962,5018.4
XS Rating Curve= 0 ,0
Exp/Cntr=0.3,0.1

Type RM Length L Ch R = 1 ,20563   ,324,324,324
BEGIN DESCRIPTION:
CLEAR BRANCH 40.0
END DESCRIPTION:
XS GIS Cut Line= 3
      3722883.31     10227756.47      3722728.23     10227266.84
      3722629.34     10226551.65
#Sta/Elev= 30
  4486.4   363.4  4524.9  361.12  4544.5   361.1  4589.5  358.39  4712.3  353.76
  4853.1  343.82  4890.7  342.51  4911.6  342.84  4922.9  340.82    4950   340.5
  4955.2  338.91  4974.6  339.03  4982.3  337.97  4987.5  334.64  4993.4  332.84
  5005.8  334.75  5015.9  338.37    5026  339.93  5056.3  339.52  5188.9  349.61
    5238  351.46  5321.4  352.88  5404.4   352.6  5470.2  353.97  5540.9  356.32
  5611.5  357.31  5672.1  360.49  5691.8  360.77  5702.4  362.26    5722  362.24
#Mann= 4 ,-1 , 0
  4486.4     .17       0  4982.3     .09       0  5015.9     .17       0
  5321.4     .11       0
Bank Sta=4982.3,5015.9
XS Rating Curve= 0 ,0
Exp/Cntr=0.3,0.1

Type RM Length L Ch R = 1 ,20239   ,322,322,322
BEGIN DESCRIPTION:
CLEAR BRANCH 39.0
END DESCRIPTION:
XS GIS Cut Line= 3
      3723088.75     10227629.94      3722990.67     10227094.41
      3722767.83     10226561.03
#Sta/Elev= 30
  4498.7   365.9  4578.9  363.35  4590.5  361.94  4638.6  360.38    4650  358.75
  4696.9  356.65    4702  355.28  4741.5  353.94  4761.9  350.73  4782.2  349.64
  4813.4  346.07  4861.5  342.83  4883.9  340.35  4924.8  339.09    4978  339.04
  4995.7  336.19  5004.1   332.7    5016  333.73  5026.1  336.66  5031.2  339.12
  5036.4  339.23  5079.3  338.49  5190.8  341.29  5299.2  345.11  5352.2  345.79
  5382.7  348.12  5415.2  348.96  5491.1  353.71  5504.6  353.66  5621.2  358.45
#Mann= 6 ,-1 , 0
  4498.7     .17       0    4978     .09       0  5031.2     .12       0
  5036.4     .17       0  5190.8     .11       0  5504.6     .17       0
Bank Sta=4978,5031.2
XS Rating Curve= 0 ,0
Exp/Cntr=0.3,0.1

Type RM Length L Ch R = 1 ,19917   ,764,764,764
BEGIN DESCRIPTION:
CLEAR BRANCH 38.0
END DESCRIPTION:
XS GIS Cut Line= 3
      3723340.39     10227396.35      3723278.45     10227035.05
      3722884.63     10226544.69
#Sta/Elev= 30
  4556.3  365.76  4581.9   364.1  4612.4  360.91  4632.7  360.08  4703.7  352.26
  4719.1  352.06  4825.4  346.48  4839.2  345.01  4894.1  342.51  4899.2  341.31
  4947.5   337.7  4961.9  337.37    4981  332.52  4990.7  333.65  4997.1  333.26
  5011.5  337.39  5040.3  337.57  5110.7  336.22  5137.1  336.54  5217.9  336.71
  5246.7  337.78  5302.7  342.06  5345.9   346.7  5366.7  347.05  5389.1  348.66
  5424.3  349.26  5466.7  351.73  5488.3  351.52  5517.1  353.77  5551.8  354.41
#Mann= 5 ,-1 , 0
  4556.3     .17       0  4961.9     .09       0  5011.5     .17       0
  5040.3     .11       0  5137.1     .17       0
Bank Sta=4961.9,5011.5
XS Rating Curve= 0 ,0
Exp/Cntr=0.3,0.1

Type RM Length L Ch R = 1 ,19153   ,653,653,653
BEGIN DESCRIPTION:
CLEAR BRANCH 37.0
END DESCRIPTION:
XS GIS Cut Line= 3
      3723539.14     10227214.44      3723437.14     10226560.44
      3723319.74     10226130.38
#Sta/Elev= 30
  4354.7  358.14  4368.2  358.63  4399.6  356.53  4499.8  353.28  4580.8  348.88
  4611.1  345.98  4785.3   336.3  4813.5   334.7  4823.7  335.82  4849.4     336
  4912.2   335.3  4945.1     337  4955.2  335.19  4980.1  335.01  4985.6  330.58
    4994  327.06  4997.5  327.06  5013.8  335.67  5018.9  335.67  5032.2   337.8
  5037.4  336.97  5066.7  337.28  5088.5  335.23  5098.9  335.47  5106.5  336.88
  5180.7  340.75  5185.9  341.77  5260.1  344.07  5285.5  346.18  5462.4  352.64
#Mann= 4 ,-1 , 0
  4354.7     .11       0  4785.3     .17       0  4980.1     .09       0
  5013.8     .17       0
#XS Ineff= 1 ,-1
  5032.2    5130   337.8
Permanent Ineff=
       F
Bank Sta=4980.1,5013.8
XS Rating Curve= 0 ,0
Exp/Cntr=0.3,0.1

Type RM Length L Ch R = 1 ,18500   ,288,288,288
BEGIN DESCRIPTION:
CLEAR BRANCH 36.0
END DESCRIPTION:
XS GIS Cut Line= 3
      3724167.83     10226761.05      3723927.58     10226482.71
      3723477.27     10226025.95
#Sta/Elev= 30
  4586.2  358.68  4659.5  354.87  4788.7  346.78  4806.1  346.19  4855.5   341.5
    4923  337.82  4959.2  334.17    4969  332.29  4983.2  327.99  4988.4  324.46
  4997.3  325.77  5004.3   329.7  5011.5  332.11  5025.6  333.02  5044.1  332.56
    5068  331.44  5096.3  331.54  5166.9  333.55  5188.2  331.91  5195.2  330.37
  5209.4  331.79  5216.5  333.69  5273.1  339.77  5372.1  348.18  5414.5  348.87
  5471.1  348.24  5499.4   346.3  5527.6  349.04  5577.1  349.01  5595.3  350.21
#Mann= 8 ,-1 , 0
  4586.2     .11       0  4659.5     .17       0  4788.7     .11       0
    4923     .17       0  4959.2     .11       0    4969     .06       0
  5011.5     .11       0  5044.1     .17       0
#XS Ineff= 2 ,-1
  5025.6    5150  333.02  5166.9    5220  333.55
Permanent Ineff=
       F       F
Bank Sta=4969,5011.5
XS Rating Curve= 0 ,0
Exp/Cntr=0.3,0.1

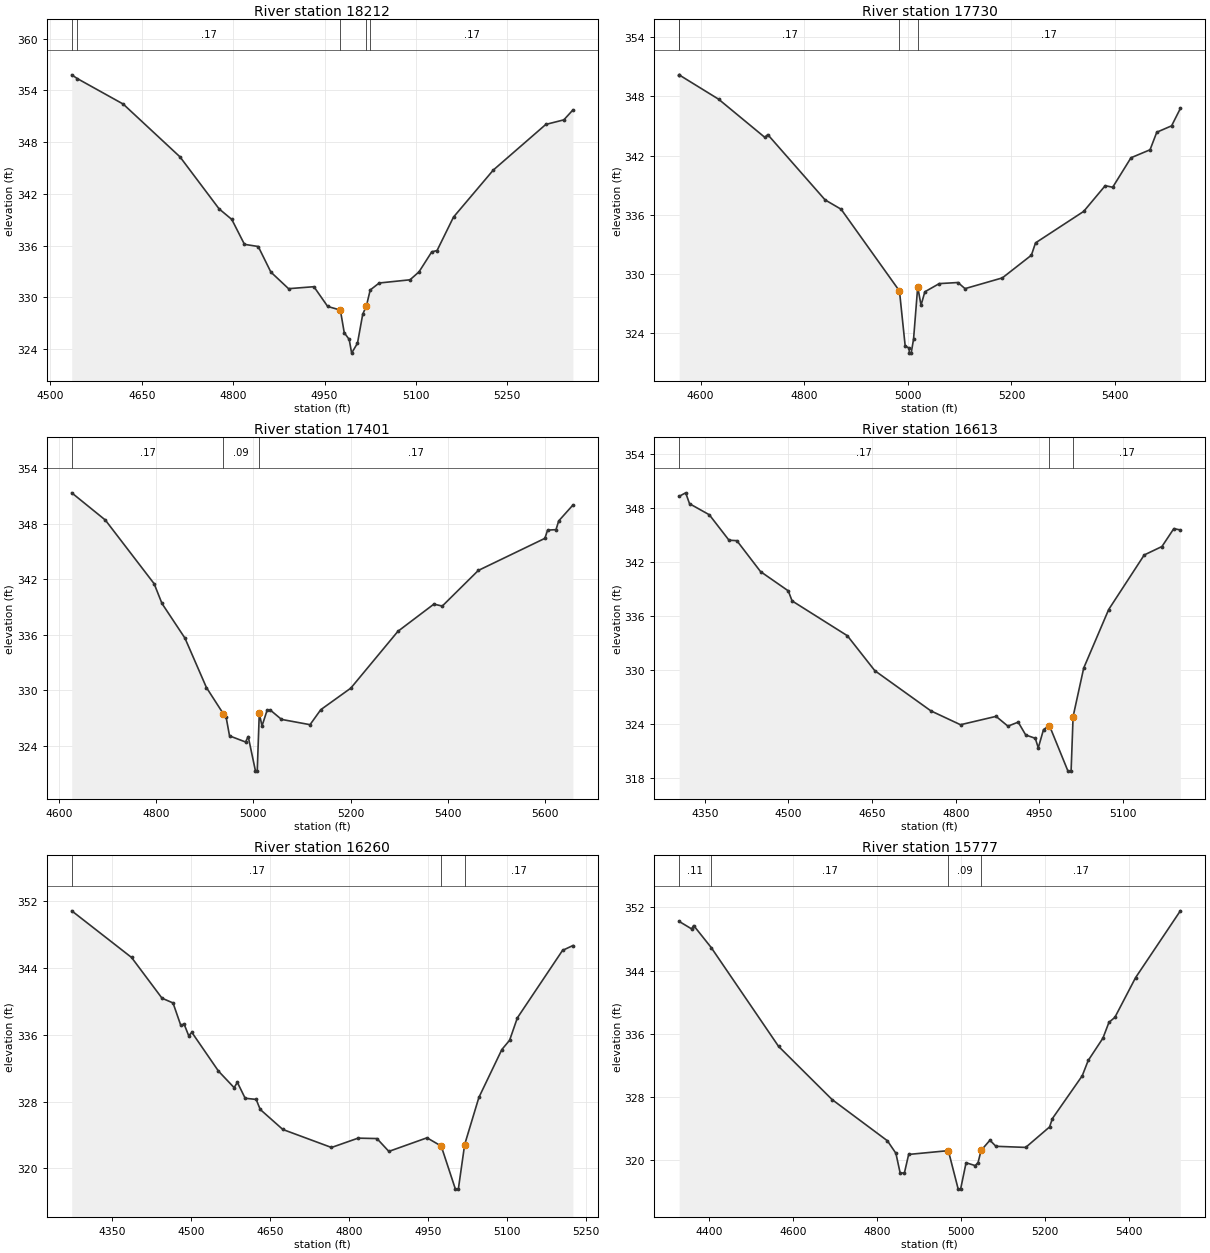
Type RM Length L Ch R = 1 ,18212   ,482,482,482
BEGIN DESCRIPTION:
CLEAR BRANCH 35.0
END DESCRIPTION:
XS GIS Cut Line= 3
      3724314.06     10226583.62      3724028.23     10226216.84
      3723735.99     10226010.75
#Sta/Elev= 30
    4535  355.81  4544.3  355.37  4619.5  352.42  4712.7   346.3  4776.9  340.27
  4797.7  339.05  4818.5  336.16  4841.1  335.91  4861.9  332.94  4890.9  331.02
  4932.5  331.25  4955.1  328.96  4975.9  328.54  4982.3  325.91  4990.4  325.14
  4994.4  323.55    5004   324.7  5012.6  328.05  5018.8  329.07  5024.9  330.87
  5039.7  331.68  5090.2  332.05    5105  332.97  5125.9  335.29  5134.6  335.44
  5161.6  339.32  5226.9  344.77  5313.1  350.06  5342.7  350.59  5357.6  351.74
#Mann= 5 ,-1 , 0
    4535     .11       0  4544.3     .17       0  4975.9     .09       0
  5018.8     .12       0  5024.9     .17       0
Bank Sta=4975.9,5018.8
XS Rating Curve= 0 ,0
Exp/Cntr=0.3,0.1

Type RM Length L Ch R = 1 ,17730   ,329,329,329
BEGIN DESCRIPTION:
CLEAR BRANCH 34.0
END DESCRIPTION:
XS GIS Cut Line= 3
      3724571.04     10226458.67      3724368.23     10226066.84
      3724040.28     10225655.47
#Sta/Elev= 30
  4558.8  350.19  4559.2  350.17  4634.9  347.72  4724.1  343.85  4729.8  344.13
  4840.4  337.51  4871.4  336.56    4984  328.27    4995  322.71  5002.7  322.47
    5003  321.97  5006.6  321.97  5011.2   323.4  5019.2  328.69  5025.6  326.83
    5033  328.19  5060.8  329.02  5096.9  329.13  5110.5  328.51  5182.6   329.6
  5238.6   331.9  5246.6  333.15  5339.5  336.34  5381.1  338.95  5395.5  338.79
  5430.8  341.78  5467.6  342.59  5480.6  344.37  5509.2  345.02  5526.1  346.78
#Mann= 4 ,-1 , 0
  4558.8     .11       0  4559.2     .17       0    4984     .09       0
  5019.2     .17       0
Bank Sta=4984,5019.2
XS Rating Curve= 0 ,0
Exp/Cntr=0.3,0.1

Type RM Length L Ch R = 1 ,17401   ,788,788,788
BEGIN DESCRIPTION:
CLEAR BRANCH 33.0
END DESCRIPTION:
XS GIS Cut Line= 3
      3724735.97     10226217.37      3724648.28     10225952.29
      3724329.69     10225271.12
#Sta/Elev= 30
  4626.4  351.33  4695.5  348.39  4795.9  341.51  4812.1  339.37  4859.4  335.62
  4903.6  330.28  4938.3  327.45  4943.8  327.15  4951.1  325.06    4984   324.4
  4989.5  324.99  5004.5  321.25  5008.1  321.25  5012.3  327.51  5017.9  326.13
  5028.4  327.83  5035.2  327.84    5058  326.84  5116.7  326.27  5138.8  327.89
  5200.6  330.22  5297.5  336.36  5371.5   339.3  5388.8  339.09  5462.9  342.94
  5599.9  346.41  5605.5   347.3  5622.8  347.35  5628.3  348.29  5657.6  350.01
#Mann= 3 , 0 , 0
  4626.4     .17       0  4938.3     .09       0  5012.3     .17       0
Bank Sta=4938.3,5012.3
XS Rating Curve= 0 ,0
Exp/Cntr=0.3,0.1

Type RM Length L Ch R = 1 ,16613   ,353,353,353
BEGIN DESCRIPTION:
CLEAR BRANCH 32.0
END DESCRIPTION:
XS GIS Cut Line= 3
      3725501.31     10225784.09      3725194.39     10225462.38
      3724766.85     10225308.29
#Sta/Elev= 30
  4303.9  349.31  4315.6   349.7  4322.5  348.49    4358  347.26  4393.3  344.43
  4407.4  344.38  4449.9  340.94  4499.6   338.8  4506.5  337.68  4605.6  333.81
  4654.9  329.92  4755.5  325.45  4808.6  323.91  4872.4  324.84  4893.7  323.75
  4912.1   324.2  4925.6  322.77  4942.8   322.4  4948.1  321.33  4957.5  323.37
  4968.1  323.82  5001.4  318.75    5007  318.75  5010.6  324.82  5029.6  330.21
  5074.4  336.72  5138.2  342.79    5170  343.73  5191.3  345.72    5203  345.57
#Mann= 3 , 0 , 0
  4303.9     .17       0  4968.1     .09       0  5010.6     .17       0
Bank Sta=4968.1,5010.6
XS Rating Curve= 0 ,0
Exp/Cntr=0.3,0.1

Type RM Length L Ch R = 1 ,16260   ,483,483,483
BEGIN DESCRIPTION:
CLEAR BRANCH 31.0
END DESCRIPTION:
XS GIS Cut Line= 3
      3725582.84      10225714.1      3725135.79     10225076.09
      3724996.12      10224975.1
#Sta/Elev= 30
  4273.4  350.87    4387  345.28  4444.8   340.4  4465.7  339.83  4480.5  337.13
  4486.6  337.32  4495.4  335.91  4501.5   336.3    4552  331.66  4581.7  329.68
  4587.8  330.32  4602.6  328.41  4623.5  328.27  4631.2  327.07  4674.1  324.67
  4766.5  322.51    4817  323.63  4852.8  323.58  4875.4  322.04  4947.8  323.67
  4974.8  322.68  5001.7  317.52  5007.3  317.52  5019.3  322.86  5046.3  328.51
  5089.9  334.25  5104.6  335.36  5119.3  338.04  5205.1  346.13  5224.8  346.71
#Mann= 3 , 0 , 0
  4273.4     .17       0  4974.8     .09       0  5019.3     .17       0
Bank Sta=4974.8,5019.3
XS Rating Curve= 0 ,0
Exp/Cntr=0.3,0.1

Type RM Length L Ch R = 1 ,15777   ,497,497,497
BEGIN DESCRIPTION:
CLEAR BRANCH 30.0
END DESCRIPTION:
XS GIS Cut Line= 3
      3725717.85     10225661.05        3725618.     10224997.12
      3725267.84     10224611.06
#Sta/Elev= 30
  4328.6  350.22    4358  349.28  4363.1   349.7  4404.9  346.91  4565.1  334.41
  4692.6  327.67  4824.1  322.46  4844.3  320.88  4854.4   318.4  4864.5  318.37
  4874.7  320.73  4969.1  321.21  4992.6  316.34  4998.3  316.34  5011.3  319.68
  5032.9  319.32  5039.7  319.68  5047.1  321.24  5068.1  322.53  5082.3  321.76
  5153.2  321.62    5210  324.21  5216.7  325.27  5287.7  330.68  5301.9  332.62
    5337  335.45  5351.2  337.44  5365.4  338.08  5414.7  343.11  5521.2  351.56
#Mann= 4 ,-1 , 0
  4328.6     .11       0  4404.9     .17       0  4969.1     .09       0
  5047.1     .17       0
Bank Sta=4969.1,5047.1
XS Rating Curve= 0 ,0
Exp/Cntr=0.3,0.1

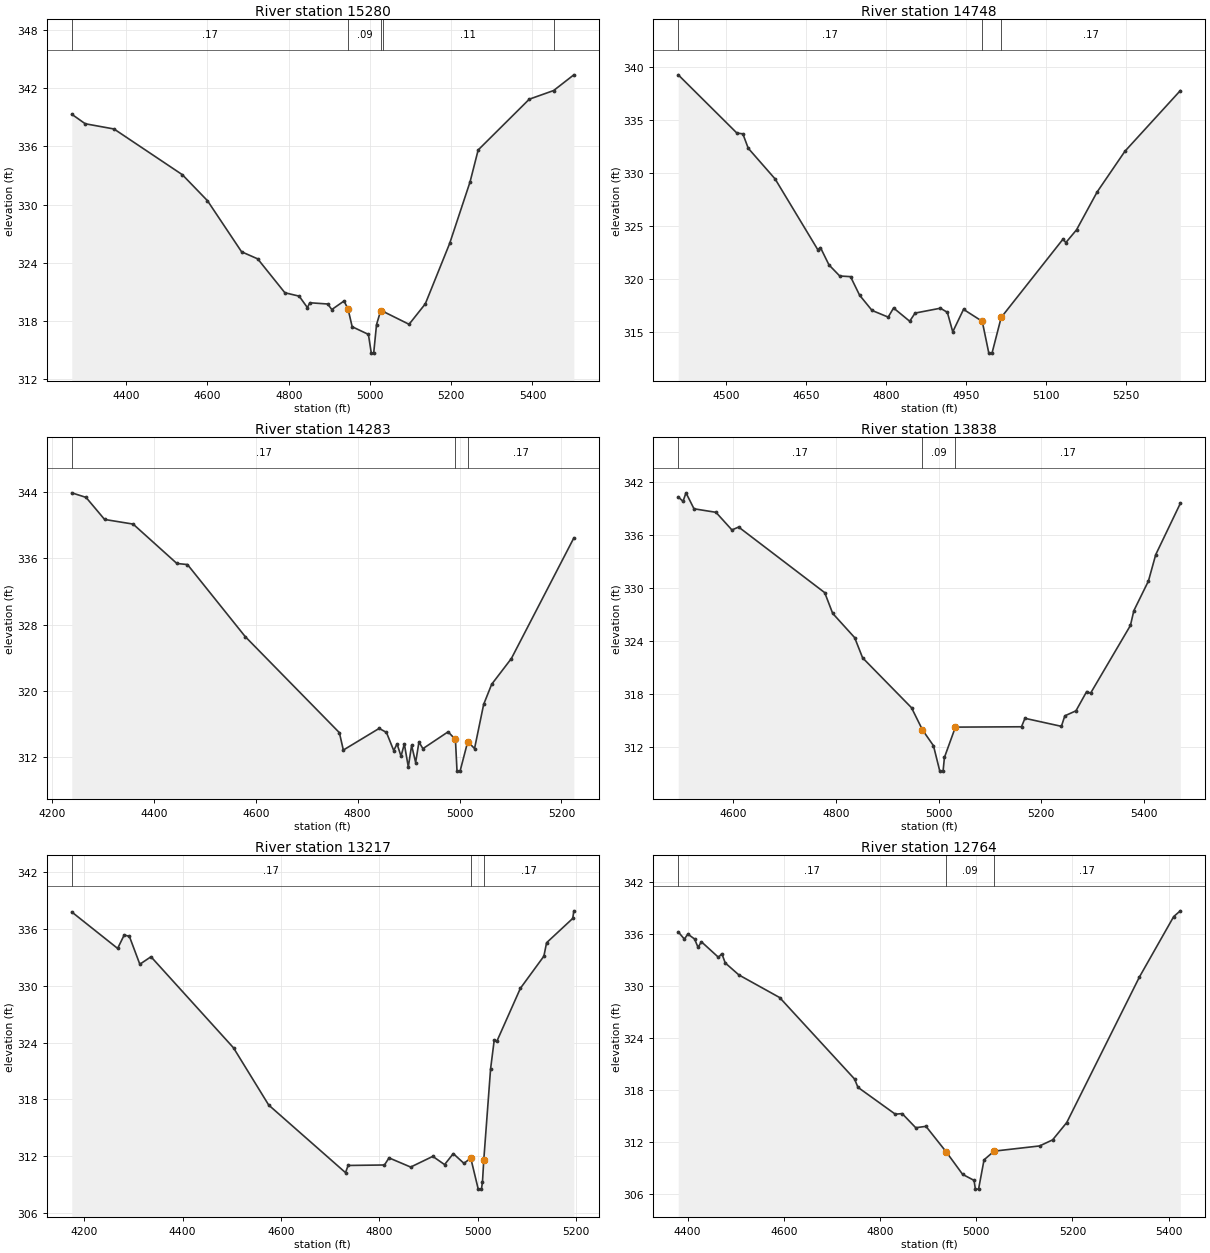
Type RM Length L Ch R = 1 ,15280   ,532,532,532
BEGIN DESCRIPTION:
CLEAR BRANCH 29.0
END DESCRIPTION:
XS GIS Cut Line= 3
      3726086.32     10225453.71        3725993.     10224874.27
      3726016.86     10224225.71
#Sta/Elev= 30
  4265.9  339.32    4299  338.34  4369.9   337.8  4538.1  333.09    4600  330.41
  4683.9  325.15  4723.6  324.42  4790.5  320.93  4825.7  320.58  4845.9   319.4
  4851.9   319.9    4896  319.77    4906   319.2  4936.1  320.08  4946.1  319.24
  4956.1  317.43  4996.1  316.64  5003.2  314.71  5009.1  314.71  5016.1  317.65
  5026.1  319.06  5032.1  319.01  5096.2  317.68  5136.2  319.79  5196.2  326.02
  5246.3  332.35  5266.3  335.64  5392.1  340.87    5452  341.76  5501.8  343.38
#Mann= 5 ,-1 , 0
  4265.9     .17       0  4946.1     .09       0  5026.1     .17       0
  5032.1     .11       0    5452     .17       0
Bank Sta=4946.1,5026.1
XS Rating Curve= 0 ,0
Exp/Cntr=0.3,0.1

Type RM Length L Ch R = 1 ,14748   ,465,465,465
BEGIN DESCRIPTION:
CLEAR BRANCH 28.0
END DESCRIPTION:
XS GIS Cut Line= 3
      3726517.86     10225161.12      3726414.01     10224379.48
      3726427.03     10224227.54
#Sta/Elev= 30
  4410.7  339.26  4520.7  333.76  4531.8  333.69  4541.9  332.33  4592.3  329.43
  4672.2  322.76  4677.3  322.95  4693.2  321.32  4713.4  320.27  4733.6  320.21
  4750.6  318.46  4773.9  317.02  4804.2  316.39  4814.3  317.25  4844.5     316
  4854.6  316.77  4902.1  317.23  4915.1  316.84  4925.2     315  4945.4  317.12
  4980.5  315.99  4992.8  312.99  4998.8  312.99    5016  316.36    5132  323.76
  5137.1  323.42  5157.2  324.63  5195.9  328.21  5247.8  332.04  5351.7  337.77
#Mann= 3 , 0 , 0
  4410.7     .17       0  4980.5     .09       0    5016     .17       0
Bank Sta=4980.5,5016
XS Rating Curve= 0 ,0
Exp/Cntr=0.3,0.1

Type RM Length L Ch R = 1 ,14283   ,445,445,445
BEGIN DESCRIPTION:
CLEAR BRANCH 27.0
END DESCRIPTION:
XS GIS Cut Line= 3
      3727267.83     10225011.05      3726780.44     10224426.61
      3726717.86     10224211.11
#Sta/Elev= 30
    4239  343.91    4267  343.36  4303.4   340.7  4359.4  340.14  4445.3  335.39
  4466.1  335.26  4579.3  326.58  4764.2  314.99    4772  312.89  4842.3   315.5
  4856.6  315.02  4870.9  312.83  4877.4  313.64  4885.2  312.15  4891.7  313.63
  4899.5  310.86    4906  313.46  4913.9  311.39  4920.4  313.86  4928.2  313.06
  4977.6  315.09    4992  314.17  4995.1  310.35  5001.1  310.35  5016.2  313.92
  5029.5  313.07  5047.4   318.4  5063.1  320.82  5101.8  323.93  5224.4  338.47
#Mann= 3 , 0 , 0
    4239     .17       0    4992     .09       0  5016.2     .17       0
Bank Sta=4992,5016.2
XS Rating Curve= 0 ,0
Exp/Cntr=0.3,0.1

Type RM Length L Ch R = 1 ,13838   ,621,621,621
BEGIN DESCRIPTION:
CLEAR BRANCH 26.0
END DESCRIPTION:
XS GIS Cut Line= 3
      3727368.86       10224922.      3727086.32     10224450.66
      3726798.55     10224132.95
#Sta/Elev= 30
  4492.7  340.32    4502  339.81  4507.8  340.78  4523.4  338.97  4566.2  338.57
  4597.3  336.57  4610.4   336.9  4778.1  329.46  4793.6  327.11  4836.4  324.36
  4851.9  322.07  4947.2  316.41  4968.6  313.89    4990   312.1  5002.3  309.22
  5008.7  309.22  5011.3  310.77  5032.7  314.21  5161.5  314.25  5168.2  315.21
  5239.2   314.3  5245.9  315.49  5267.6  316.06  5288.5  318.25    5296  318.05
  5373.7  325.74  5380.4  327.42  5408.8  330.78    5423  333.77  5470.9  339.58
#Mann= 3 , 0 , 0
  4492.7     .17       0  4968.6     .09       0  5032.7     .17       0
Bank Sta=4968.6,5032.7
XS Rating Curve= 0 ,0
Exp/Cntr=0.3,0.1

Type RM Length L Ch R = 1 ,13217   ,453,453,453
BEGIN DESCRIPTION:
CLEAR BRANCH 25.0
END DESCRIPTION:
XS GIS Cut Line= 3
      3727654.04     10224791.84      3727436.58     10224160.29
       3727301.7     10223834.77
#Sta/Elev= 30
  4174.7  337.79  4267.9  333.94  4281.3  335.36  4291.8  335.21    4313  332.27
  4335.7  333.06  4503.4  323.44  4574.9   317.4    4731  310.26  4736.3  311.02
  4810.1  311.07  4819.4  311.82  4863.4  310.85  4908.4  311.98  4932.3  311.11
    4950  312.27  4971.7  311.24  4985.5   311.8  5000.7  308.52  5007.2  308.52
  5009.3  309.26    5012 311.629  5025.8  321.22  5033.2  324.26  5038.6  324.14
  5086.4  329.73  5134.1  333.12  5139.6  334.54  5192.8  337.11    5195  337.91
#Mann= 3 , 0 , 0
  4174.7     .17       0  4985.5     .09       0    5012     .17       0
Bank Sta=4985.5,5012
XS Rating Curve= 0 ,0
Exp/Cntr=0.3,0.1

Type RM Length L Ch R = 1 ,12764   ,478,478,478
BEGIN DESCRIPTION:
CLEAR BRANCH 24.0
END DESCRIPTION:
XS GIS Cut Line= 3
      3728116.23     10224580.83      3727696.21      10224158.3
      3727435.07     10223794.63
#Sta/Elev= 30
  4380.6  336.22  4393.4  335.39  4400.5  335.97  4414.6   335.4  4421.7  334.44
  4428.8  335.08  4464.2  333.29  4471.2  333.71  4478.3  332.64  4506.6  331.26
  4591.4  328.65    4747  319.26  4754.1   318.3  4831.8   315.2    4846  315.27
  4874.2  313.64  4895.5   313.8  4937.9  310.83  4971.7  308.26  4995.4  307.57
  4998.2  306.56  5004.8  306.56  5016.2  309.94  5037.1  310.94  5131.6  311.54
  5158.7  312.24  5188.1  314.24  5339.2  331.03  5410.4  337.99  5424.1  338.65
#Mann= 3 , 0 , 0
  4380.6     .17       0  4937.9     .09       0  5037.1     .17       0
Bank Sta=4937.9,5037.1
XS Rating Curve= 0 ,0
Exp/Cntr=0.3,0.1

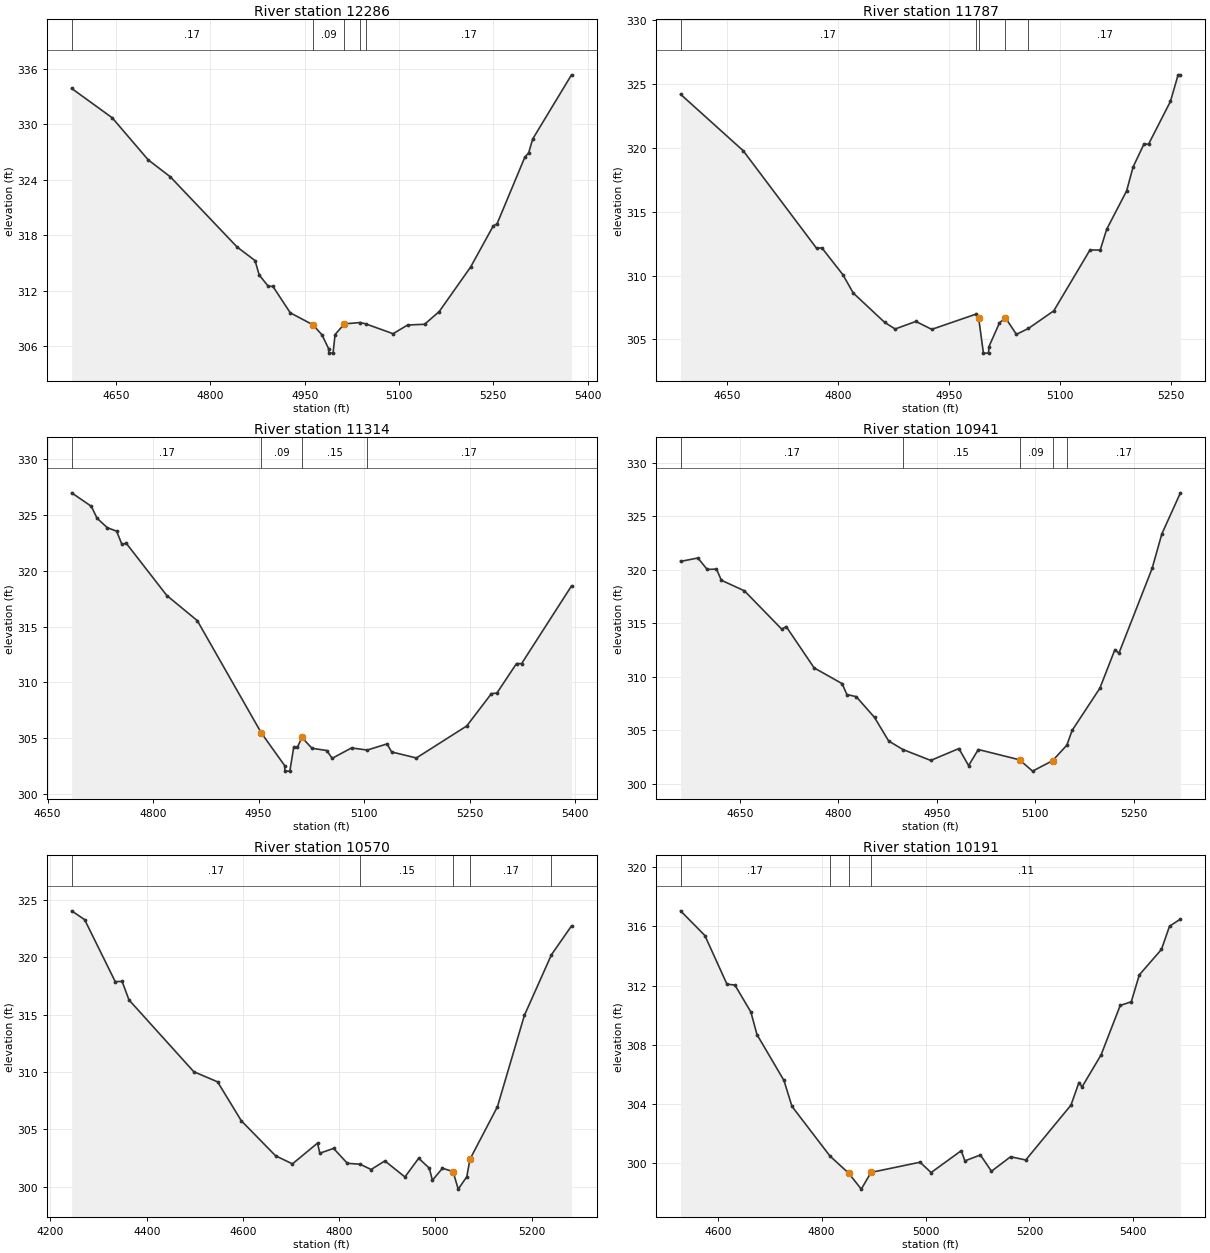
Type RM Length L Ch R = 1 ,12286   ,499,499,499
BEGIN DESCRIPTION:
CLEAR BRANCH 23.0
END DESCRIPTION:
XS GIS Cut Line= 3
      3728295.83      10224154.1      3728021.25     10223835.36
      3727717.84       10223616.
#Sta/Elev= 30
  4579.3  333.86  4643.9  330.68    4701  326.14  4736.1  324.31  4842.5  316.71
    4871  315.25  4877.6  313.69  4891.9  312.48  4899.5  312.45    4927   309.6
  4963.2   308.3  4977.4  307.22  4987.9  305.74  4988.4  305.24  4995.1  305.24
  4998.3  307.25  5013.1   308.4  5038.3  308.55  5046.8  308.41  5090.6  307.34
  5113.7  308.28  5140.7  308.36    5164  309.74    5214  314.56  5249.8  318.98
    5256  319.23  5300.1  326.42  5306.3  326.91  5312.7   328.4  5374.4  335.33
#Mann= 5 ,-1 , 0
  4579.3     .17       0  4963.2     .09       0  5013.1     .17       0
  5038.3     .15       0  5046.8     .17       0
Bank Sta=4963.2,5013.1
XS Rating Curve= 0 ,0
Exp/Cntr=0.3,0.1

Type RM Length L Ch R = 1 ,11787   ,473,473,473
BEGIN DESCRIPTION:
CLEAR BRANCH 22.0
END DESCRIPTION:
XS GIS Cut Line= 3
      3728567.83     10223761.05      3728282.62     10223462.35
      3728067.85     10223311.07
#Sta/Elev= 30
    4587  324.19  4671.7  319.77  4770.8  312.14    4778  312.17  4806.4  310.07
  4820.5  308.63    4863  306.33  4877.1  305.82  4905.1  306.41  4926.5  305.79
  4985.8  306.97    4990  306.66  4996.4  303.93  5003.3  303.93  5003.8  304.43
  5018.1   306.3  5026.2  306.69    5041   305.4  5057.2  305.86  5091.5  307.24
  5140.4     312  5154.3     312    5163  313.62    5190  316.63  5198.7   318.5
  5213.5   320.3  5219.6  320.28  5249.2  323.63  5259.6  325.71  5262.7  325.71
#Mann= 5 ,-1 , 0
    4587     .17       0  4985.8     .15       0    4990     .09       0
  5026.2     .15       0  5057.2     .17       0
Bank Sta=4990,5026.2
XS Rating Curve= 0 ,0
Exp/Cntr=0.3,0.1

Type RM Length L Ch R = 1 ,11314   ,373,373,373
BEGIN DESCRIPTION:
CLEAR BRANCH 21.0
END DESCRIPTION:
XS GIS Cut Line= 3
      3728867.84     10223361.06      3728620.88      10223164.4
      3728317.83     10222911.05
#Sta/Elev= 30
  4684.3  326.99  4712.3  325.78  4720.3  324.72  4734.8  323.87  4748.2  323.55
  4755.6  322.39    4762  322.46  4819.6  317.78  4862.9  315.53  4954.1  305.44
  4987.1  302.53  4987.6  302.03  4994.5  302.03    5000  304.16  5005.2  304.16
  5011.7  305.05    5026  304.08  5046.9  303.88  5054.7  303.18  5082.2  304.11
  5104.5  303.92  5132.7  304.47  5139.3  303.75  5174.4  303.21    5246  306.08
  5281.1  308.98  5288.9  309.03  5316.8  311.68    5324  311.67    5395  318.64
#Mann= 4 ,-1 , 0
  4684.3     .17       0  4954.1     .09       0  5011.7     .15       0
  5104.5     .17       0
Bank Sta=4954.1,5011.7
XS Rating Curve= 0 ,0
Exp/Cntr=0.3,0.1

Type RM Length L Ch R = 1 ,10941   ,371,371,371
BEGIN DESCRIPTION:
CLEAR BRANCH 20.0
END DESCRIPTION:
XS GIS Cut Line= 3
      3729038.35     10223158.01      3728792.91     10222891.51
      3728467.82     10222661.05
#Sta/Elev= 30
    4560  320.78  4586.4   321.1  4600.5  320.03  4614.7  320.06  4622.1  319.02
  4657.2  318.03    4714  314.45  4720.8  314.69  4763.3  310.83  4805.8  309.36
  4813.2  308.34  4827.4  308.14  4855.2   306.2  4876.7     304  4898.4   303.2
  4940.8  302.18  4983.6  303.29  4998.4   301.7  5013.2   303.2  5075.9  302.24
  5095.8  301.18  5126.3  302.16    5148  303.61  5155.9  304.98  5198.2  308.93
  5221.1  312.54  5227.2   312.2  5277.7  320.12  5292.5  323.35  5320.8  327.19
#Mann= 5 ,-1 , 0
    4560     .17       0  4898.4     .15       0  5075.9     .09       0
  5126.3     .15       0    5148     .17       0
Bank Sta=5075.9,5126.3
XS Rating Curve= 0 ,0
Exp/Cntr=0.3,0.1

Type RM Length L Ch R = 1 ,10570   ,379,379,379
BEGIN DESCRIPTION:
CLEAR BRANCH 19.0
END DESCRIPTION:
XS GIS Cut Line= 3
       3729431.2     10223015.59      3729049.25     10222682.25
      3728643.01     10222338.52
#Sta/Elev= 30
    4244  324.04    4271  323.27  4334.6  317.87  4348.9  317.89  4363.1  316.28
  4497.9  310.02  4547.3  309.14  4596.6  305.75  4667.8   302.7  4702.9  301.99
  4755.1   303.8  4759.9  302.92  4788.5  303.34  4817.1  302.04  4843.7  301.96
  4866.5   301.5  4895.1  302.25  4936.8  300.85  4965.4  302.48  4987.4  301.62
  4993.9  300.56  5014.8  301.61  5036.8  301.32  5047.6  299.79  5065.4  300.87
  5071.9  302.39  5129.1  306.97  5185.1  314.93  5241.3  320.21  5283.1  322.73
#Mann= 5 ,-1 , 0
    4244     .17       0  4843.7     .15       0  5036.8     .09       0
  5071.9     .17       0  5241.3     .11       0
Bank Sta=5036.8,5071.9
XS Rating Curve= 0 ,0
Exp/Cntr=0.3,0.1

Type RM Length L Ch R = 1 ,10191   ,484,484,484
BEGIN DESCRIPTION:
CLEAR BRANCH 18.0
END DESCRIPTION:
XS GIS Cut Line= 3
      3729552.71     10222560.72        3729143.     10222305.52
      3728733.76     10222055.81
#Sta/Elev= 30
  4528.5  317.05  4575.3  315.38  4617.8  312.09  4633.1  312.03  4663.8  310.21
  4675.6  308.68  4727.5  305.58  4742.9  303.83    4816  300.47  4852.3   299.3
  4876.3  298.23  4895.1  299.36  4989.5  300.05  5010.7  299.35  5068.8  300.83
  5075.8  300.14  5105.6  300.54  5126.9  299.44  5163.7  300.42  5192.9   300.2
  5279.9  303.91  5295.3  305.44  5301.2  305.14  5337.9  307.31  5374.7  310.65
    5396   310.9  5411.5  312.72  5454.1  314.44  5469.6  316.01  5490.6  316.49
#Mann= 4 ,-1 , 0
  4528.5     .17       0    4816     .11       0  4852.3     .06       0
  4895.1     .11       0
Bank Sta=4852.3,4895.1
XS Rating Curve= 0 ,0
Exp/Cntr=0.3,0.1

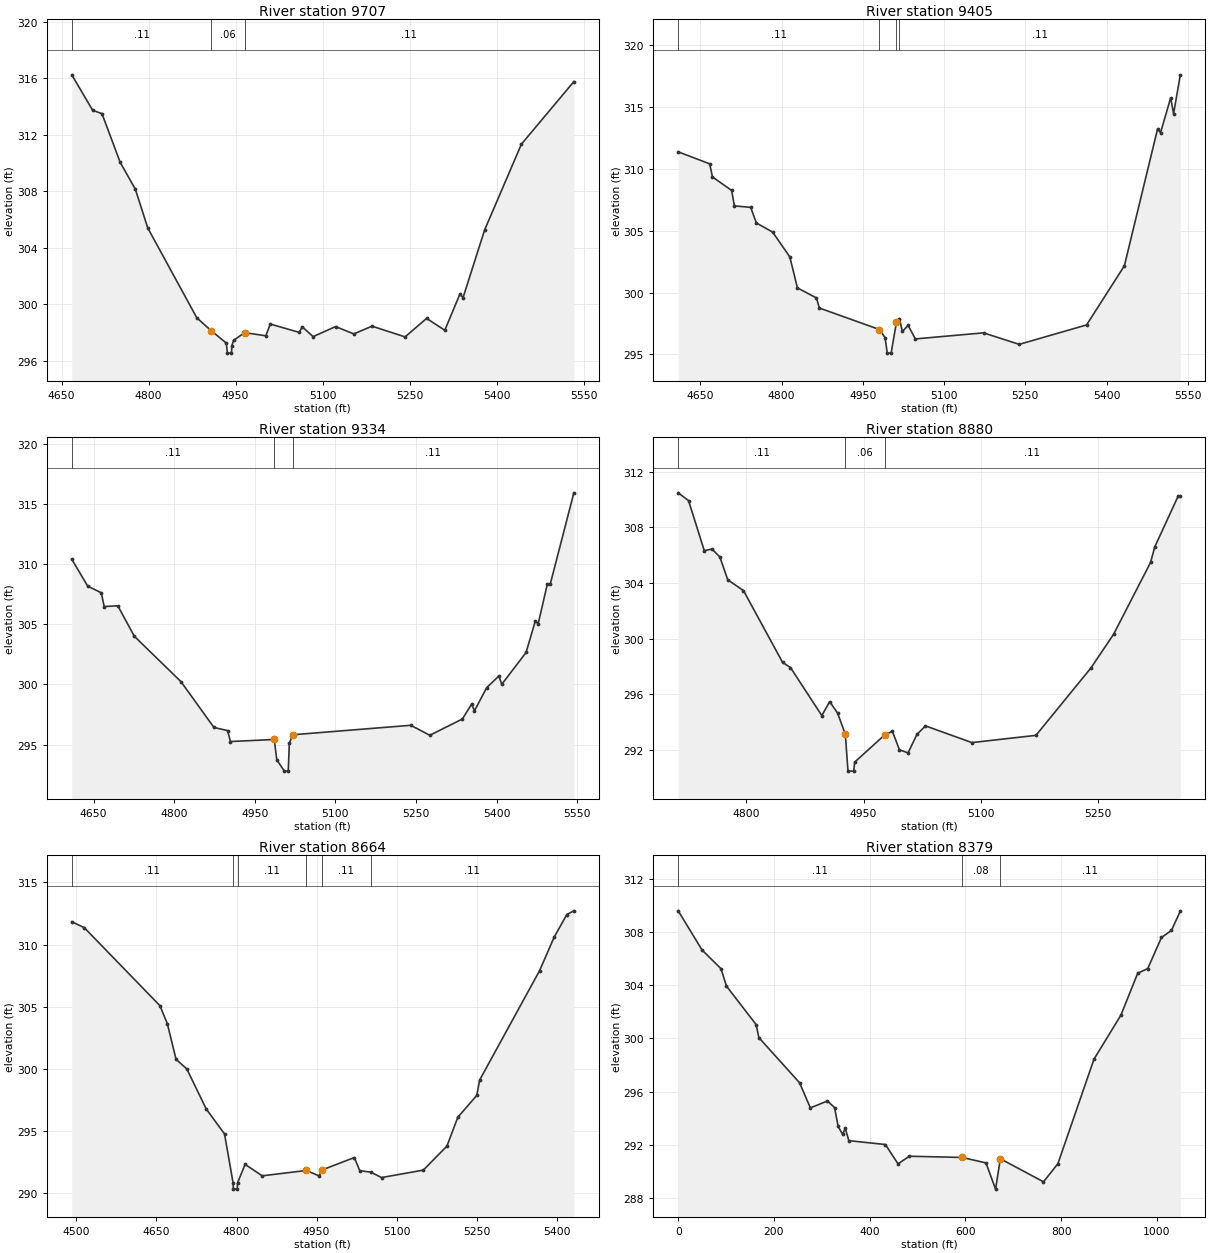
Type RM Length L Ch R = 1 ,9707    ,302,302,302
BEGIN DESCRIPTION:
Mapping XS 0c83ba19
END DESCRIPTION:
XS GIS Cut Line= 2
      3729711.98      10222052.9      3728892.28     10221774.47
#Sta/Elev= 30
  4667.5  316.25  4703.5  313.74  4719.6   313.5    4751  310.05  4777.1  308.15
  4798.6   305.4  4883.1  299.04  4907.9  298.13    4934  297.25  4935.8  296.54
  4942.9  296.54  4943.4  297.04  4946.4  297.44  4965.4  297.99  5002.1  297.77
  5009.8   298.6  5059.6  298.01  5064.9   298.4  5083.7  297.71  5122.4  298.42
  5153.8   297.9  5185.1  298.45  5242.2  297.69  5279.3     299  5310.7  298.16
  5336.8  300.73  5342.1  300.46  5379.5  305.28  5442.8  311.34  5533.2  315.77
#Mann= 3 , 0 , 0
  4667.5     .11       0  4907.9     .06       0  4965.4     .11       0
Bank Sta=4907.9,4965.4
XS Rating Curve= 0 ,0
Exp/Cntr=0.3,0.1

Type RM Length L Ch R = 1 ,9405    ,71,71,71
BEGIN DESCRIPTION:
Mapping XS e5b7b772
END DESCRIPTION:
XS GIS Cut Line= 3
       3729937.3     10221801.19      3729557.93     10221702.22
      3729062.13     10221501.13
#Sta/Elev= 30
    4609  311.39  4667.1  310.42  4672.2  309.36  4707.6  308.27  4712.7  307.02
  4742.8   306.9  4753.2  305.64  4783.3   304.9  4815.1  302.89    4829  300.39
  4864.3  299.57  4869.5  298.76  4980.5  297.02  4990.9  296.37    4995  295.11
  5002.1  295.11  5011.9   297.6  5017.4  297.91  5022.8  296.86  5033.5  297.35
  5046.9  296.26  5172.7  296.75  5238.6  295.82    5363  297.39  5432.8  302.17
  5494.2  313.26  5499.6  312.94  5518.3  315.76  5523.7  314.48  5536.1  317.62
#Mann= 4 ,-1 , 0
    4609     .11       0  4980.5     .07       0  5011.9     .11       0
  5017.4     .11       0
Bank Sta=4980.5,5011.9
XS Rating Curve= 0 ,0
Exp/Cntr=0.3,0.1

Type RM Length L Ch R = 1 ,9334    ,454,454,454
BEGIN DESCRIPTION:
CLEAR BRANCH 17.0
END DESCRIPTION:
XS GIS Cut Line= 3
      3729963.33     10221775.14      3729603.93      10221645.8
       3729106.4      10221405.7
#Sta/Elev= 30
  4609.4  310.41    4639  308.18  4664.4  307.62  4669.7  306.48  4695.1  306.54
  4725.8  304.01  4812.6  300.24    4874  296.43  4899.4  296.17  4904.7  295.26
  4986.2  295.43    4991  293.74  5005.1   292.8  5012.3   292.8  5014.3   295.1
  5020.3  295.82  5240.3  296.61  5275.7  295.78  5336.3  297.13  5353.4  298.36
  5358.9  297.82  5381.5  299.73  5404.1   300.7  5409.7  300.02  5454.9  302.66
    5472  305.26  5477.5  305.06  5494.6  308.37  5500.1  308.38  5543.8  315.93
#Mann= 3 ,-1 , 0
  4609.4     .11       0  4986.2     .07       0  5020.3     .11       0
Bank Sta=4986.2,5020.3
XS Rating Curve= 0 ,0
Exp/Cntr=0.3,0.1

Type RM Length L Ch R = 1 ,8880    ,216,216,216
BEGIN DESCRIPTION:
CLEAR BRANCH 16.0
END DESCRIPTION:
XS GIS Cut Line= 3
      3729981.53     10221774.23      3729957.45     10221487.94
      3729817.86      10221161.1
#Sta/Elev= 30
  4712.7  310.47  4725.9  309.91    4746  306.32    4756  306.43    4766  305.86
  4776.1  304.22  4796.2  303.45  4846.3  298.29  4856.4  297.92  4896.5  294.47
  4906.5  295.47  4916.6  294.66  4926.6  293.13    4930  290.48  4937.3  290.48
  4938.6  291.13  4976.8  293.07  4986.8  293.34  4995.9  292.01  5006.9  291.79
  5018.3  293.12  5029.2  293.73  5088.6  292.53  5170.6  293.05  5241.1   297.9
  5270.1  300.32  5317.3  305.47  5322.8   306.6  5352.7  310.24  5355.4  310.24
#Mann= 3 , 0 , 0
  4712.7     .11       0  4926.6     .06       0  4976.8     .11       0
Bank Sta=4926.6,4976.8
XS Rating Curve= 0 ,0
Exp/Cntr=0.3,0.1

Type RM Length L Ch R = 1 ,8664    ,285,285,285
BEGIN DESCRIPTION:
CLEAR BRANCH 15.0
END DESCRIPTION:
XS GIS Cut Line= 3
      3730089.17     10221894.86      3730147.77     10221458.62
      3730045.77     10220968.17
#Sta/Elev= 30
  4491.2  311.84  4514.5  311.37  4656.5  305.09  4670.3  303.65  4686.7  300.78
  4706.9     300  4743.2  296.79  4777.5  294.78  4793.6  290.84  4794.1  290.34
  4801.4  290.34  4801.9  290.84  4816.1  292.33  4848.2  291.41  4930.8  291.84
    4955   291.4  4960.1  291.88  5020.8  292.88    5031  291.83  5051.9   291.7
  5071.8  291.27  5150.2  291.87  5194.4   293.8  5214.8  296.12  5250.4  297.88
  5255.7  299.11  5368.1  307.91  5395.6  310.62  5419.1  312.42  5432.3  312.72
#Mann= 6 ,-1 , 0
  4491.2     .11       0  4793.6     .12       0  4801.9     .11       0
  4930.8     .07       0  4960.1     .11       0  5051.9     .11       0
Bank Sta=4930.8,4960.1
XS Rating Curve= 0 ,0
Exp/Cntr=0.3,0.1

Type RM Length L Ch R = 1 ,8379    ,286,286,286
XS GIS Cut Line= 5
      3730161.81     10221911.83      3730293.32      10221638.4
       3730344.1     10221536.83      3730331.08     10221085.01
       3730217.8     10220943.08
#Sta/Elev= 30
       0  309.58    49.7  306.64    89.4  305.23   100.7  303.93   162.8  301.03
   168.4  300.06   253.4  296.67     276  294.78   311.6   295.3   326.6   294.8
     334  293.39   343.3   292.8   348.9  293.25   356.3  292.32   432.7  292.03
   459.1  290.58   482.8  291.15   592.8  291.06   642.8  290.65   662.8  288.68
   672.8  290.96   762.9  289.23   792.9  290.58   868.4  298.44   924.5  301.74
   959.8   304.9   980.6  305.24  1009.4  307.58  1030.2  308.11  1048.7  309.56
#Mann= 3 , 0 , 0
       0     .11       0   592.8     .08       0   672.8     .11       0
Bank Sta=592.8,672.8
XS Rating Curve= 0 ,0
Exp/Cntr=0.3,0.1