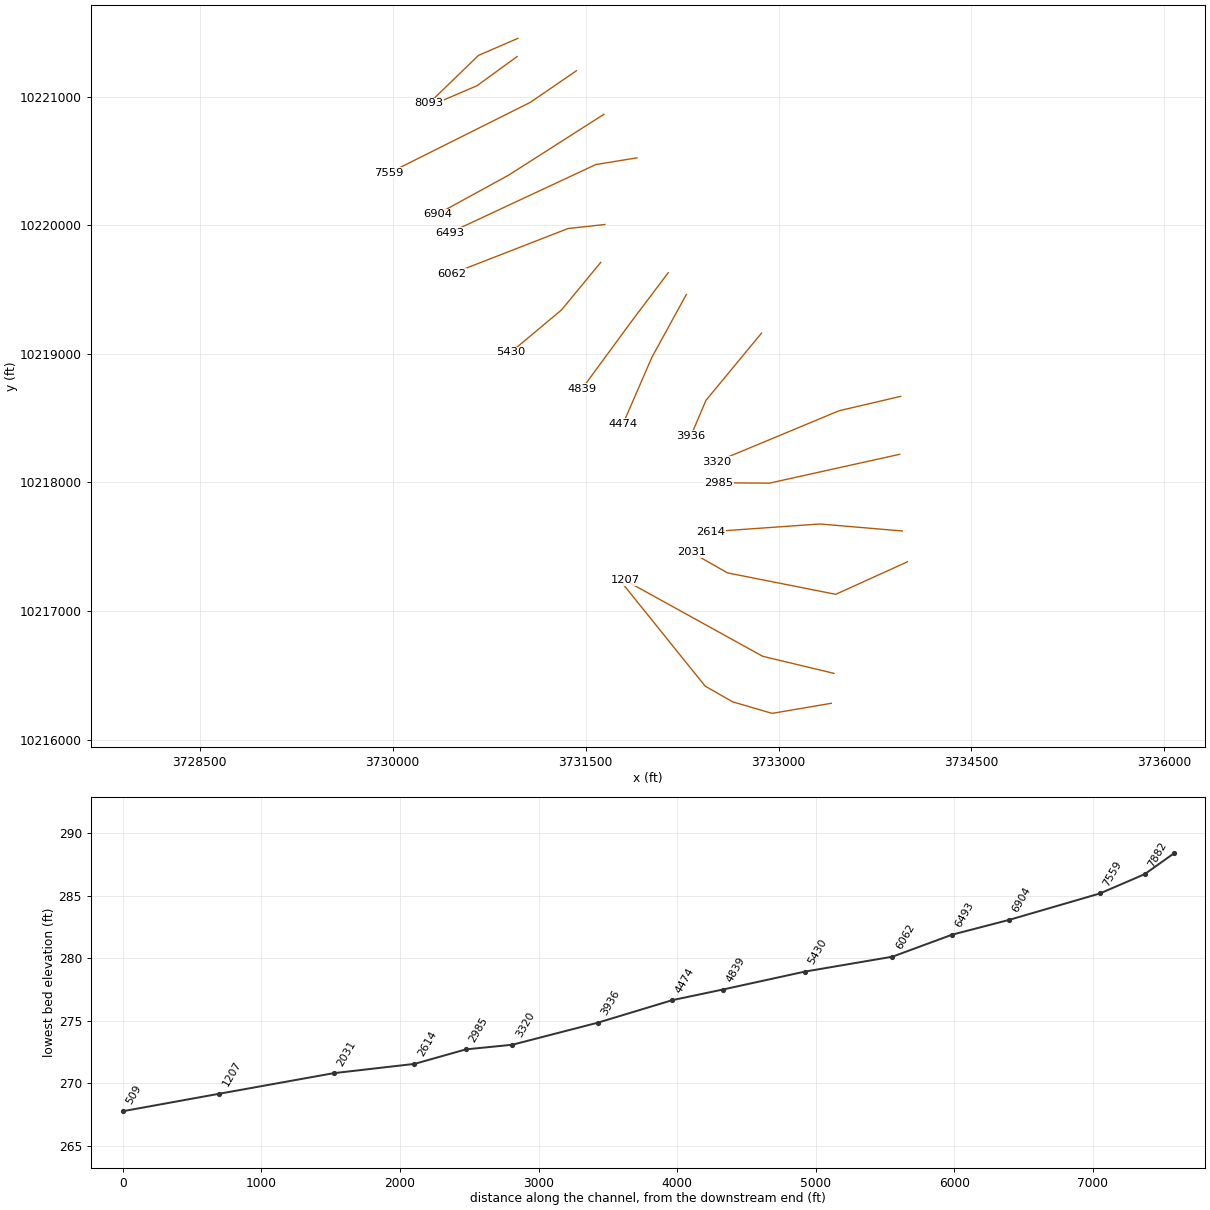
HEC-RAS study CLEAR BRANCH.prj: CLEAR BRANCH Base Level Engineering

--- CLEAR BRANCH.g01 (geometry) --- (continued)

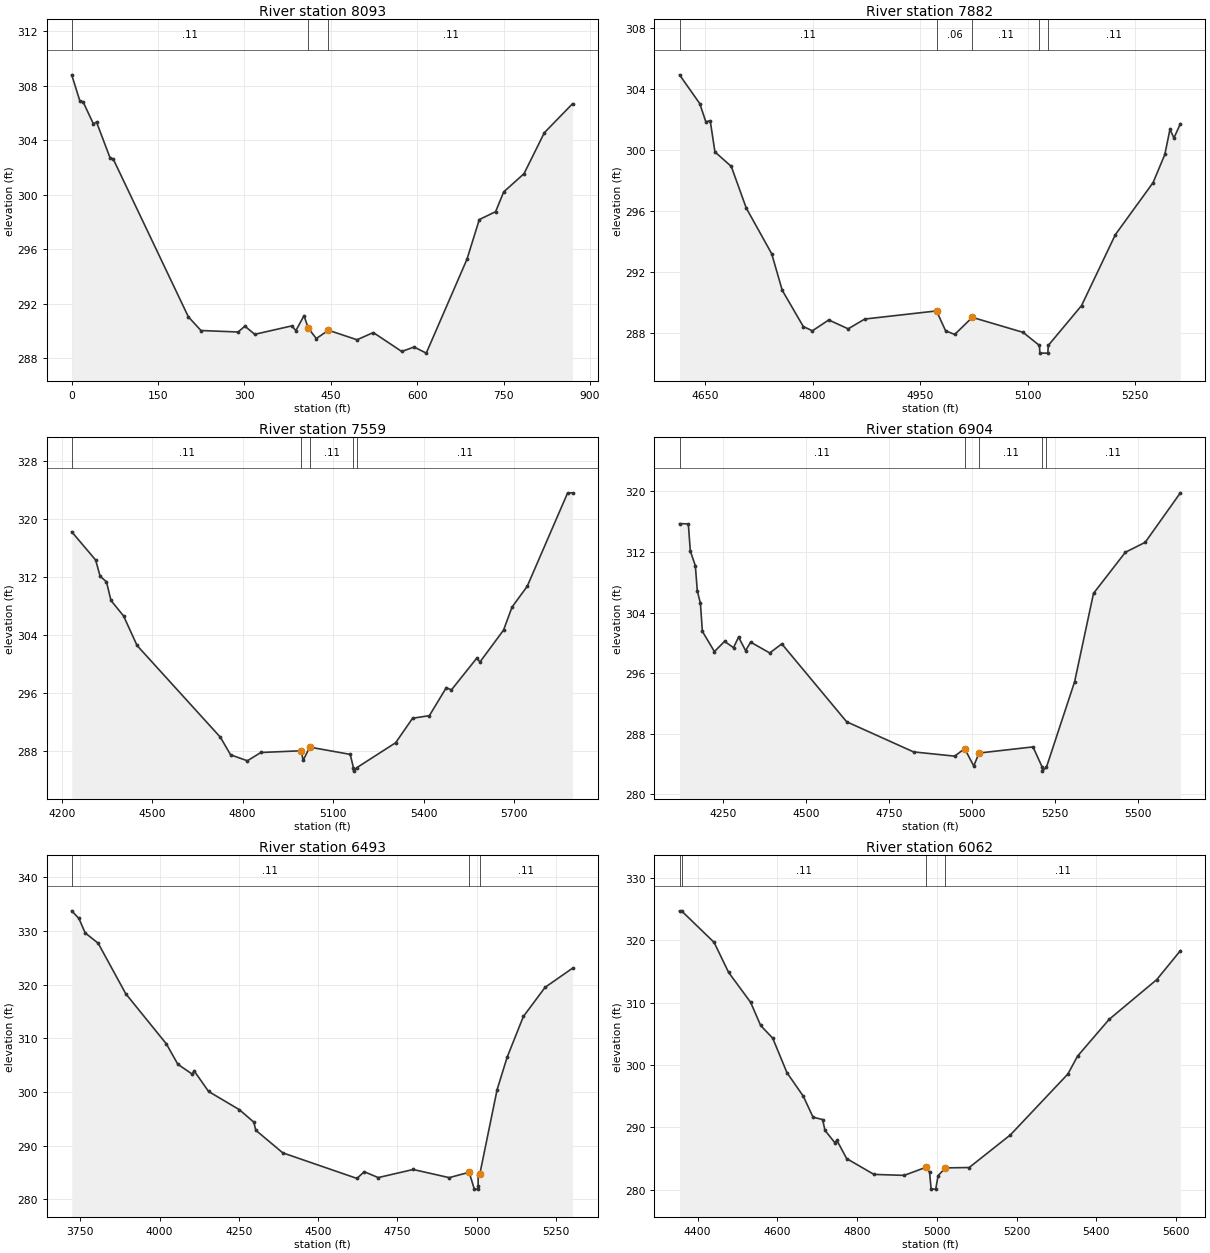
Type RM Length L Ch R = 1 ,8093    ,211,211,211
XS GIS Cut Line= 3
       3730973.8     10221452.58      3730667.81      10221320.2
      3730281.52     10220946.93
#Sta/Elev= 30
       0  308.79    14.2  306.87    19.6  306.82    37.6   305.2    43.1  305.32
    66.6   302.7      72  302.62   202.6  291.03   224.4  290.03   288.9  289.92
   300.7  290.35   317.8  289.75   382.3  290.37   389.2  290.02   403.4  291.12
   410.6  290.21   424.7  289.44   445.8  290.05   495.4  289.35   523.7  289.88
   573.1  288.49   594.5  288.82   615.6  288.37   686.3  295.26   707.7  298.17
     736  298.75   750.1   300.2   785.4  301.54   820.6  304.54   869.6  306.67
#Mann= 3 , 0 , 0
       0     .11       0   410.6     .07       0   445.8     .11       0
Bank Sta=410.6,445.8
XS Rating Curve= 0 ,0
Exp/Cntr=0.3,0.1

Type RM Length L Ch R = 1 ,7882    ,323,323,323
BEGIN DESCRIPTION:
CLEAR BRANCH 14.0
END DESCRIPTION:
XS GIS Cut Line= 3
      3730967.81     10221311.04      3730655.98     10221084.23
      3730367.89     10220961.09
#Sta/Elev= 30
  4614.4  304.91  4642.6  303.03  4651.1  301.84  4657.2  301.91  4663.8  299.87
  4686.6  298.92  4707.5   296.2    4743  293.21  4757.7  290.82  4787.1  288.45
  4799.8  288.17  4822.6  288.88  4849.7   288.3  4872.9  288.94    4973  289.47
  4985.7  288.17  4998.4  287.93  5022.9  289.05  5093.7  288.07  5116.7  287.21
  5117.2  286.71  5128.4  286.71  5128.9  287.21  5175.4  289.82  5222.6  294.46
  5275.2  297.86  5291.6   299.7  5298.8  301.35  5304.3  300.78  5313.3  301.71
#Mann= 5 ,-1 , 0
  4614.4     .11       0    4973     .06       0  5022.9     .11       0
  5116.7     .11       0  5128.9     .11       0
Bank Sta=4973,5022.9
XS Rating Curve= 0 ,0
Exp/Cntr=0.3,0.1

Type RM Length L Ch R = 1 ,7559    ,655,655,655
BEGIN DESCRIPTION:
CLEAR BRANCH 13.0
END DESCRIPTION:
XS GIS Cut Line= 3
      3731428.81     10221200.68      3731072.05      10220955.9
      3729973.12     10220406.43
#Sta/Elev= 30
  4232.9  318.19  4312.3  314.29  4327.2  312.05  4348.2  311.29  4363.1  308.72
    4405  306.57  4449.7   302.5  4726.2  289.84  4759.9  287.42  4815.6   286.6
  4860.3  287.74  4994.5  287.98  5000.3  286.65  5022.7  288.48  5156.8  287.48
  5167.2  285.67  5167.7  285.17  5179.5  285.67  5307.5  289.09  5363.7  292.47
  5419.3  292.82  5475.5  296.69  5492.3  296.37  5575.9  300.72  5587.3  300.24
  5665.3  304.62  5693.5   307.8  5743.8  310.66    5878  323.56  5894.2  323.55
#Mann= 5 ,-1 , 0
  4232.9     .11       0  4994.5     .06       0  5022.7     .11       0
  5167.2     .11       0  5179.5     .11       0
Bank Sta=4994.5,5022.7
XS Rating Curve= 0 ,0
Exp/Cntr=0.3,0.1

Type RM Length L Ch R = 1 ,6904    ,411,411,411
BEGIN DESCRIPTION:
CLEAR BRANCH 12.0
END DESCRIPTION:
XS GIS Cut Line= 3
      3731642.39     10220862.17      3730900.01     10220387.98
      3730348.08      10220086.1
#Sta/Elev= 30
  4119.1  315.75  4145.6  315.72  4151.6  312.14  4166.8  310.18  4172.7  306.85
    4182  305.24    4188  301.52  4224.3  298.85  4254.8   300.2  4281.9  299.37
  4297.1  300.77  4318.2  298.98  4333.5   300.1    4391  298.67  4427.4  299.87
  4622.9  289.58  4824.6   285.6  4948.5  285.04  4978.8  286.03  5006.1  283.74
  5022.2  285.45  5184.8  286.26  5212.8  283.56  5213.3  283.06  5225.2  283.56
  5310.2  294.86  5367.2  306.54  5463.3  311.97    5523  313.28  5629.1  319.82
#Mann= 5 ,-1 , 0
  4119.1     .11       0  4978.8     .06       0  5022.2     .11       0
  5212.8     .11       0  5225.2     .11       0
Bank Sta=4978.8,5022.2
XS Rating Curve= 0 ,0
Exp/Cntr=0.3,0.1

Type RM Length L Ch R = 1 ,6493    ,431,431,431
BEGIN DESCRIPTION:
CLEAR BRANCH 11.0
END DESCRIPTION:
XS GIS Cut Line= 3
      3731900.16      10220523.6      3731579.86     10220471.52
      3730442.31     10219940.49
#Sta/Elev= 30
  3722.9  333.74  3745.5  332.33  3765.3  329.63  3806.3  327.71  3893.4  318.29
  4021.6  308.94  4057.7  305.15  4103.4   303.3  4108.9  303.94  4154.7  300.08
  4251.6  296.69  4297.3  294.37  4303.5  292.86  4388.7  288.64  4622.8  283.87
  4645.6  285.13  4689.7  284.03  4800.1  285.54  4913.7  284.02  4976.6  285.02
    4993  281.88  5004.5  281.88    5005  282.38  5005.1  284.56  5010.6  284.78
  5064.9  300.43  5096.5  306.46  5147.7  314.05  5216.3  319.49  5302.8  323.05
#Mann= 3 , 0 , 0
  3722.9     .11       0  4976.6     .06       0  5010.6     .11       0
Bank Sta=4976.6,5010.6
XS Rating Curve= 0 ,0
Exp/Cntr=0.3,0.1

Type RM Length L Ch R = 1 ,6062    ,632,632,632
BEGIN DESCRIPTION:
CLEAR BRANCH 10.0
END DESCRIPTION:
XS GIS Cut Line= 3
      3731650.13     10220005.37      3731363.72     10219974.13
       3730461.5     10219623.12
#Sta/Elev= 30
  4354.6  324.68  4360.3  324.63  4441.4  319.62  4477.6  314.83  4532.8  310.04
  4558.1  306.32  4588.3  304.29  4624.1  298.76    4665     295  4689.5  291.64
  4713.4  291.26  4719.4  289.53  4743.9  287.57  4749.3  287.93  4773.8  285.01
  4842.1  282.48  4917.9  282.32  4972.3  283.61  4981.6  282.86  4985.7  280.12
  4997.2  280.12  5003.1  282.27  5021.3  283.52  5081.1  283.58  5184.6  288.81
  5328.6  298.55  5353.1  301.43  5432.1   307.3  5551.6  313.67  5610.8   318.3
#Mann= 4 ,-1 , 0
  4354.6     .15       0  4360.3     .11       0  4972.3     .06       0
  5021.3     .11       0
Bank Sta=4972.3,5021.3
XS Rating Curve= 0 ,0
Exp/Cntr=0.3,0.1

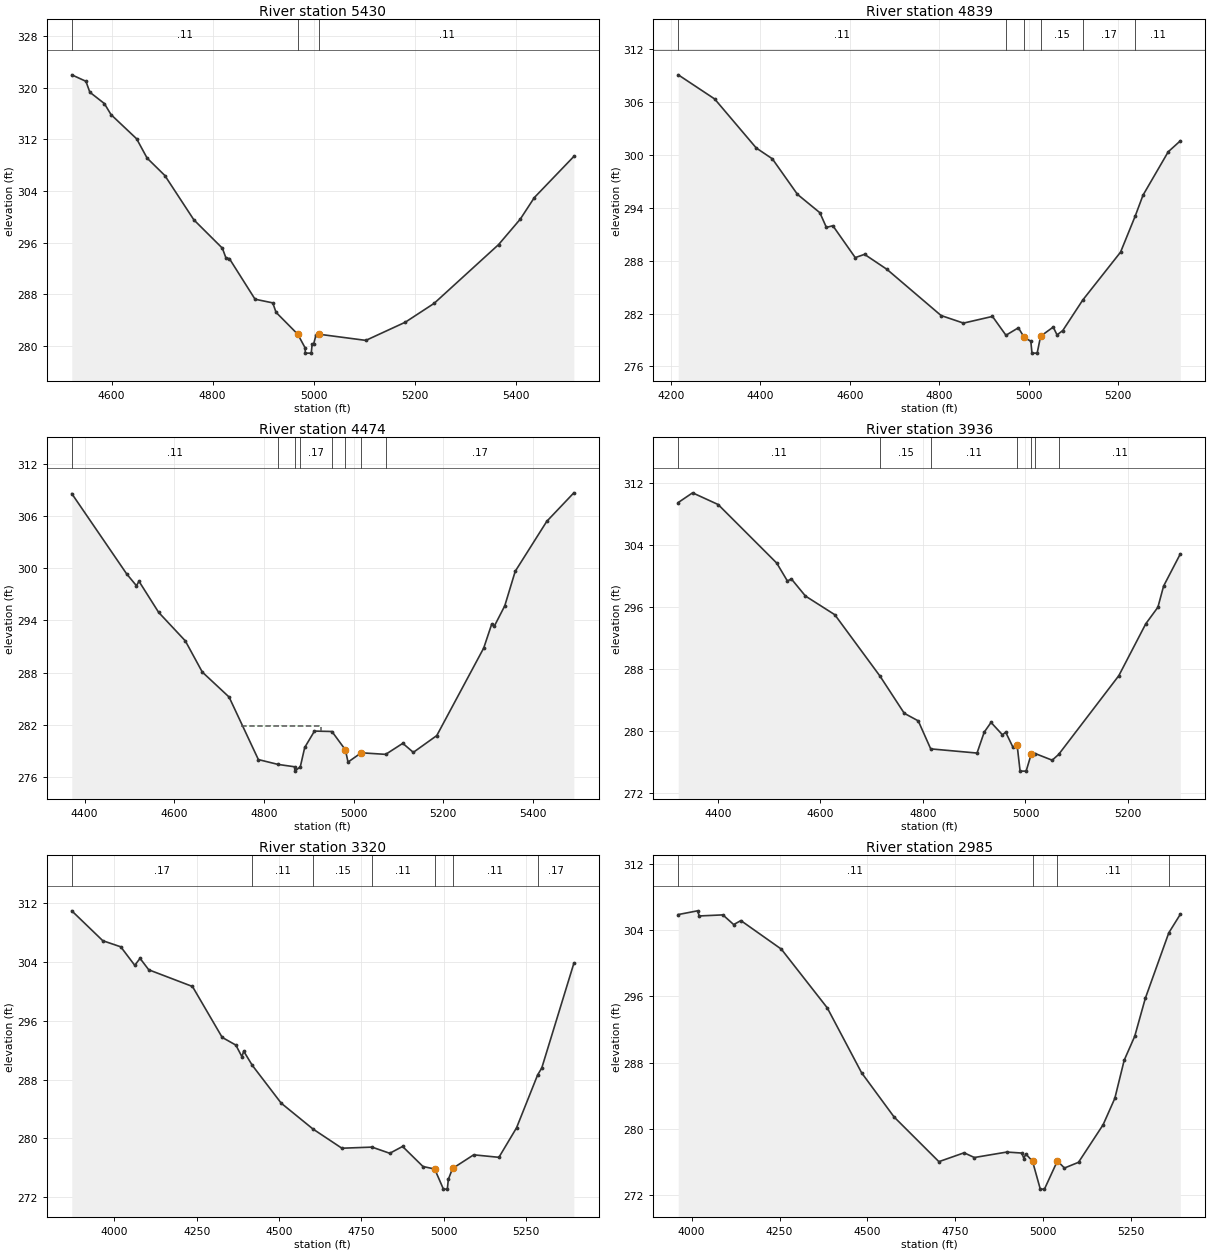
Type RM Length L Ch R = 1 ,5430    ,591,591,591
BEGIN DESCRIPTION:
CLEAR BRANCH 9.0
END DESCRIPTION:
XS GIS Cut Line= 3
      3731617.85     10219711.07      3731313.04     10219341.56
      3730917.83     10219011.05
#Sta/Elev= 30
    4521  321.97    4549  320.97  4556.8  319.28  4585.5  317.53  4598.8  315.81
  4649.4  312.08  4670.2  309.09  4705.3   306.4  4762.7  299.55  4819.2  295.16
  4826.5  293.61    4833  293.56  4883.9  287.27    4919   286.7  4925.5  285.24
  4968.5  281.85  4982.9  279.77  4983.6  278.93  4995.2  278.93  4997.1  280.37
    5000  280.37  5004.4  281.66  5010.9  281.85  5103.3   280.9  5181.4  283.71
  5238.6  286.63  5366.2  295.72  5409.1  299.65    5437  302.99  5515.2  309.35
#Mann= 3 , 0 , 0
    4521     .11       0  4968.5     .06       0  5010.9     .11       0
Bank Sta=4968.5,5010.9
XS Rating Curve= 0 ,0
Exp/Cntr=0.3,0.1

Type RM Length L Ch R = 1 ,4839    ,365,365,365
BEGIN DESCRIPTION:
CLEAR BRANCH 8.0
END DESCRIPTION:
XS GIS Cut Line= 3
      3732142.34     10219630.35      3731851.31     10219244.34
      3731473.09     10218729.33
#Sta/Elev= 30
  4216.6  309.11    4298  306.37    4391   300.8    4427  299.57  4483.2  295.53
  4533.2  293.45  4547.8  291.78  4562.3  291.97  4612.3  288.35  4633.1  288.72
  4683.1  287.02  4804.2  281.77  4854.3  280.91  4919.1  281.67  4949.2  279.53
    4977  280.38  4990.1  279.28  5004.8  278.85  5007.4   277.5    5019   277.5
  5026.7  279.42  5054.9  280.46  5063.4  279.57  5076.3  280.07  5120.9  283.53
  5205.4  288.97  5238.2  293.07  5255.6  295.44    5312  300.37    5339  301.61
#Mann= 6 ,-1 , 0
  4216.6     .11       0  4949.2     .15       0  4990.1     .07       0
  5026.7     .15       0  5120.9     .17       0  5238.2     .11       0
Bank Sta=4990.1,5026.7
XS Rating Curve= 0 ,0
Exp/Cntr=0.3,0.1

Type RM Length L Ch R = 1 ,4474    ,538,538,538
BEGIN DESCRIPTION:
CLEAR BRANCH 7.0
END DESCRIPTION:
XS GIS Cut Line= 3
      3732283.01     10219461.15      3732014.76     10218971.52
      3731790.82     10218455.95
#Sta/Elev= 30
  4371.3  308.59  4493.8  299.35  4515.6  297.99  4521.3   298.5  4565.2  294.92
  4624.7  291.64  4662.6  288.05  4722.3  285.18  4787.7  277.98  4831.8  277.42
  4868.6  277.15  4869.1  276.65  4881.3  277.15  4891.1  279.37  4912.9  281.26
  4951.9  281.21  4981.9   279.1  4987.8  277.69  5017.3  278.76  5071.8  278.58
    5110  279.85  5133.5  278.81  5185.8  280.74  5290.6  290.82  5308.6   293.6
    5314  293.31  5337.5  295.67  5360.9  299.65  5431.3   305.4  5491.7  308.68
#Mann= 8 ,-1 , 0
  4371.3     .11       0  4831.8     .17       0  4868.6     .12       0
  4881.3     .17       0  4951.9     .11       0  4981.9     .06       0
  5017.3     .11       0  5071.8     .17       0
#XS Ineff= 1 ,-1
    4750    4927  281.85
Permanent Ineff=
       F
Bank Sta=4981.9,5017.3
XS Rating Curve= 0 ,0
Exp/Cntr=0.3,0.1

Type RM Length L Ch R = 1 ,3936    ,616,616,616
BEGIN DESCRIPTION:
CLEAR BRANCH 6.0
END DESCRIPTION:
XS GIS Cut Line= 3
      3732867.87      10219161.1      3732436.06     10218639.04
      3732317.84     10218361.04
#Sta/Elev= 30
  4322.5  309.49  4350.5  310.74  4400.4  309.23  4514.7  301.68  4535.5  299.37
  4543.2  299.64  4570.7  297.43    4628  295.02  4716.4  287.08  4763.5  282.31
  4790.8  281.33  4815.1  277.72  4905.5  277.18  4919.5  279.88  4932.8  281.13
    4955  279.54  4961.4  279.87  4975.8   277.9  4983.6  278.27  4989.5  274.85
  5001.3  274.85  5011.1  277.02  5019.3  277.11  5052.1  276.26  5064.7     277
  5182.1  287.16  5234.8  293.86  5258.4  295.99  5269.5  298.72  5302.1  302.86
#Mann= 7 ,-1 , 0
  4322.5     .11       0  4716.4     .15       0  4815.1     .11       0
  4983.6     .06       0  5011.1     .11       0  5019.3     .15       0
  5064.7     .11       0
#XS Ineff= 1 ,-1
    4790  4932.8  281.13
Permanent Ineff=
       F
Bank Sta=4983.6,5011.1
XS Rating Curve= 0 ,0
Exp/Cntr=0.3,0.1

Type RM Length L Ch R = 1 ,3320    ,335,335,335
BEGIN DESCRIPTION:
CLEAR BRANCH 5.0
END DESCRIPTION:
XS GIS Cut Line= 3
      3733949.61     10218669.43      3733470.49     10218557.46
       3732517.9     10218161.09
#Sta/Elev= 30
  3870.8  310.98    3965  306.91  4019.5  306.08    4062  303.56    4078  304.51
  4104.5  302.95  4237.1  300.68  4327.3  293.75  4368.8   292.7  4387.2  291.12
  4392.6  291.87  4418.6  289.95  4506.5  284.79  4602.7  281.28  4690.6  278.66
  4782.1  278.81  4835.9  277.97  4874.8   278.9  4936.7  276.17  4972.2  275.83
  4998.8  273.09  5010.6  273.09  5013.7  274.42  5026.4   275.9  5090.6  277.76
  5167.2  277.42  5220.7  281.44  5284.7  288.64  5297.2  289.58  5394.6  303.83
#Mann= 7 ,-1 , 0
  3870.8     .17       0  4418.6     .11       0  4602.7     .15       0
  4782.1     .11       0  4972.2     .06       0  5026.4     .11       0
  5284.7     .17       0
Bank Sta=4972.2,5026.4
XS Rating Curve= 0 ,0
Exp/Cntr=0.3,0.1

Type RM Length L Ch R = 1 ,2985    ,371,371,371
BEGIN DESCRIPTION:
CLEAR BRANCH 4.0
END DESCRIPTION:
XS GIS Cut Line= 3
      3733941.85     10218218.92       3732928.3     10217994.47
      3732538.22     10217997.56
#Sta/Elev= 30
  3961.9   305.9  4016.7  306.35  4021.8  305.73  4088.9  305.86  4119.6  304.69
  4140.1  305.17  4255.2  301.72  4385.9  294.62  4483.5  286.78  4575.9  281.44
  4703.4  276.04  4775.1  277.11  4804.2  276.54  4896.5   277.2    4939  277.08
  4945.2  276.42  4950.4  276.98  4969.7  276.09  4991.8  272.72  5003.6  272.72
  5040.5  276.13  5060.5  275.27  5100.5  275.96  5170.5   280.5  5203.8  283.69
  5230.5   288.3  5260.5   291.2  5290.5  295.77  5357.3  303.69  5390.1  305.93
#Mann= 4 ,-1 , 0
  3961.9     .11       0  4969.7     .06       0  5040.5     .11       0
  5357.3     .17       0
Bank Sta=4969.7,5040.5
XS Rating Curve= 0 ,0
Exp/Cntr=0.3,0.1

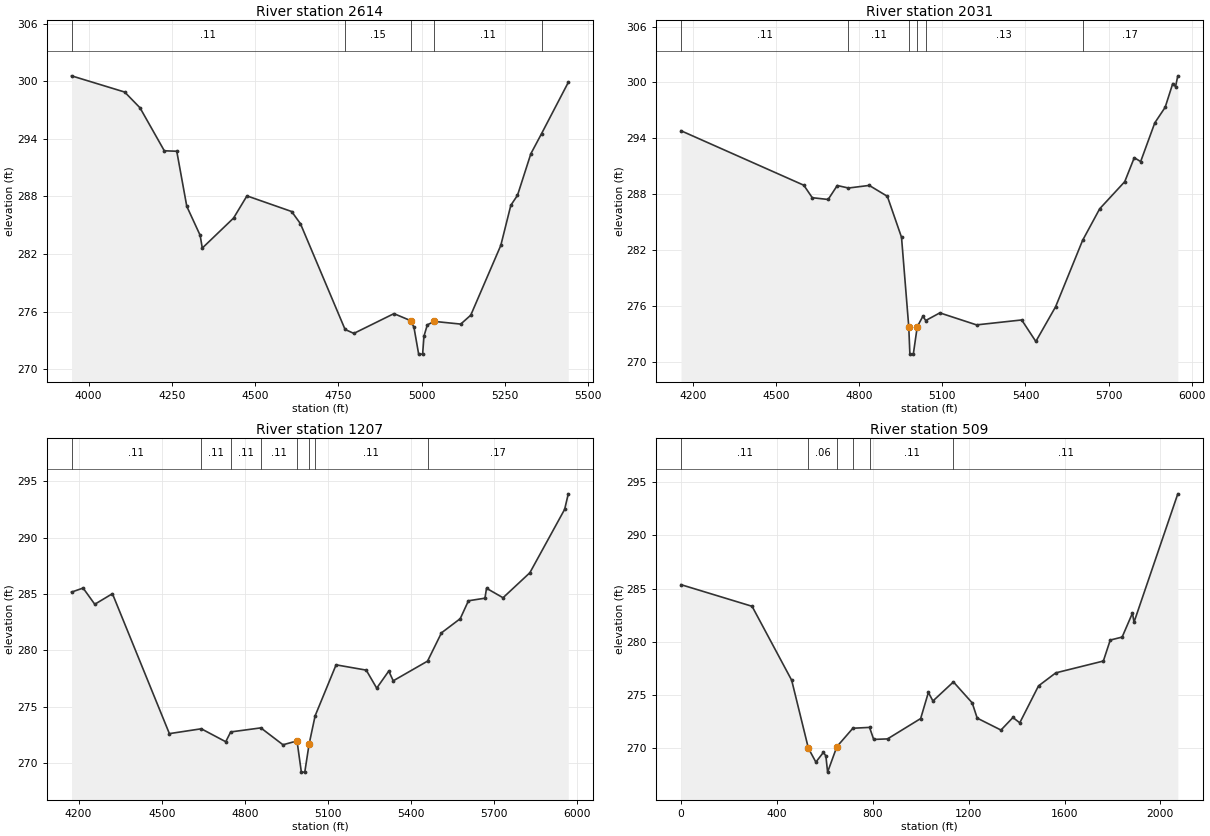
Type RM Length L Ch R = 1 ,2614    ,583,583,583
BEGIN DESCRIPTION:
CLEAR BRANCH 3.0
END DESCRIPTION:
XS GIS Cut Line= 3
      3733962.69     10217622.56      3733322.05     10217677.25
      3732475.73     10217617.36
#Sta/Elev= 30
  3948.7  300.56  4108.3  298.87  4154.3  297.23  4227.3  292.75  4264.7   292.7
  4294.8  286.96  4334.9  283.94  4341.3  282.61  4435.3  285.74  4475.4  288.05
  4609.6  286.42    4636  285.15    4770  274.13  4796.4  273.72  4916.7  275.78
  4966.8  275.05  4976.8  274.35  4990.9  271.56  5002.8  271.56  5006.9  273.44
  5016.9  274.61  5037.7  274.97  5117.2  274.69  5147.3  275.62  5237.5  282.89
  5267.6  287.07  5287.6  288.11  5327.7  292.44  5359.9  294.54  5440.1  299.88
#Mann= 5 ,-1 , 0
  3948.7     .11       0    4770     .15       0  4966.8     .06       0
  5037.7     .11       0  5359.9     .17       0
Bank Sta=4966.8,5037.7
XS Rating Curve= 0 ,0
Exp/Cntr=0.3,0.1

Type RM Length L Ch R = 1 ,2031    ,824,824,824
BEGIN DESCRIPTION:
CLEAR BRANCH 2.0
END DESCRIPTION:
XS GIS Cut Line= 4
      3734001.71     10217382.97      3733444.45     10217130.38
       3732603.3     10217297.04      3732321.18     10217457.52
#Sta/Elev= 30
  4156.2  294.81  4599.6  288.96  4630.1  287.62  4687.4  287.43  4720.4  288.93
  4760.8  288.66  4835.9  288.94  4901.2  287.77  4952.4  283.37  4978.6  273.74
  4982.6  270.82    4995  270.82  5009.2  273.76  5029.6  274.89  5039.8  274.43
  5090.8  275.25  5223.3  273.96  5386.4  274.49  5437.4  272.18  5508.8  275.91
  5606.3  283.04    5668  286.43  5758.4  289.34  5792.9  291.92  5815.9   291.5
    5867  295.66  5904.4  297.33  5931.8  299.88  5941.9  299.55  5950.1  300.71
#Mann= 6 ,-1 , 0
  4156.2     .11       0  4760.8     .11       0  4978.6     .06       0
  5009.2     .11       0  5039.8     .13       0  5606.3     .17       0
Bank Sta=4978.6,5009.2
XS Rating Curve= 0 ,0
Exp/Cntr=0.3,0.1

Type RM Length L Ch R = 1 ,1207    ,698,698,698
BEGIN DESCRIPTION:
CLEAR BRANCH 1.0
END DESCRIPTION:
XS GIS Cut Line= 3
      3733431.45     10216515.79      3732876.74     10216648.61
      3731806.42     10217239.75
#Sta/Elev= 30
  4174.4  285.17  4216.3  285.53  4258.4  284.09  4322.1  285.03  4527.7   272.6
  4642.8  273.03  4731.1  271.88    4749  272.75  4857.8  273.11  4937.7  271.61
  4988.4  271.95    5004  269.18  5016.4  269.18    5032  271.67  5053.7  274.18
  5129.4  278.71  5238.2  278.24    5276  276.64  5319.6  278.16  5335.6  277.29
  5459.5  279.04  5509.7  281.55  5577.5  282.81  5607.1   284.4  5666.7  284.63
  5672.4  285.51    5732  284.67  5828.8  286.89  5954.3  292.52  5967.5   293.9
#Mann= 8 ,-1 , 0
  4174.4     .11       0  4642.8     .11       0    4749     .11       0
  4857.8     .11       0  4988.4     .06       0    5032     .11       0
  5053.7     .11       0  5459.5     .17       0
Bank Sta=4988.4,5032
XS Rating Curve= 0 ,0
Exp/Cntr=0.3,0.1

Type RM Length L Ch R = 1 ,509     ,0,0,0
XS GIS Cut Line= 5
        3733410.     10216283.29      3732949.84     10216204.84
      3732642.93      10216294.7       3732429.1     10216416.97
      3731776.32     10217227.73
#Sta/Elev= 30
       0  285.38   296.4  283.35   461.6  276.41   531.4  270.02   562.6  268.72
   593.9  269.63   604.3  269.31   611.5  267.78   650.2  270.17     717   271.9
   786.6  271.98   803.8  270.85   861.6   270.9   999.8  272.81    1032  275.26
    1051  274.46  1136.5  276.25  1214.9  274.28  1235.7  272.85  1334.9  271.73
  1384.8  272.91  1413.3  272.41  1491.6  275.88  1563.6   277.1    1762  278.21
  1790.8  280.18  1840.4  280.46  1883.5  282.71    1890  281.86  2072.7  293.91
#Mann= 6 ,-1 , 0
       0     .11       0   531.4     .06       0   650.2     .11       0
     717     .11       0   786.6     .11       0  1136.5     .11       0
Bank Sta=531.4,650.2
XS Rating Curve= 0 ,0
Exp/Cntr=0.3,0.1

Chan Stop Cuts=-1
Use User Specified Reach Order=0
Composite Channel Slope=5