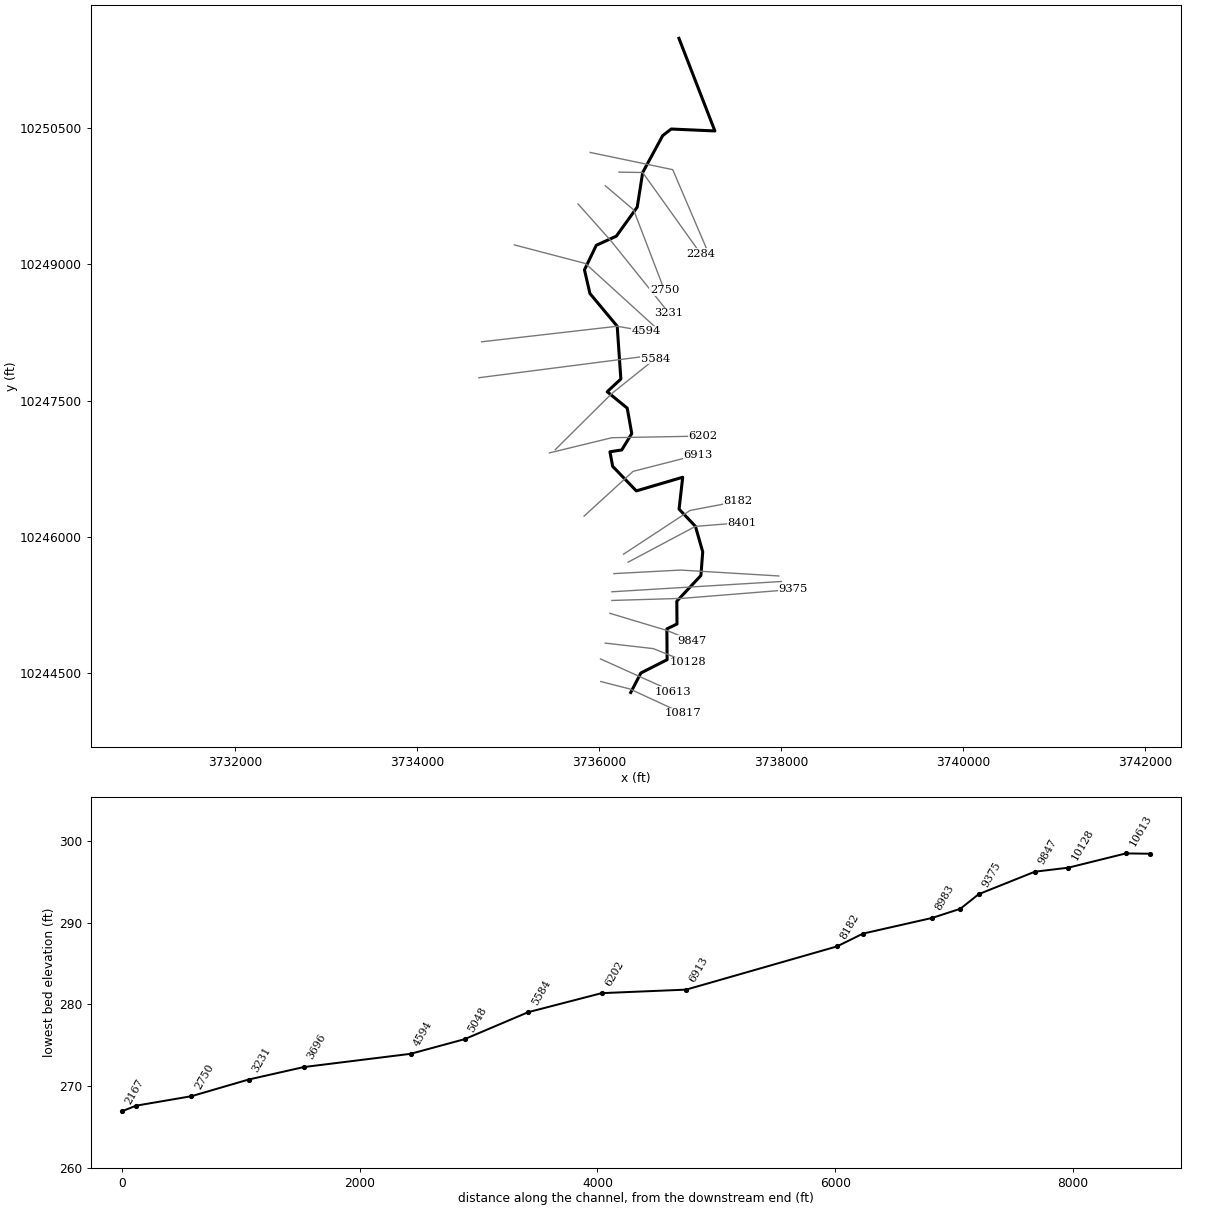
--- ERA BRANCH.prj (project) ---

Proj Title=ERA BRANCH Base Level Engineering
Current Plan=p01
Default Exp/Contr=0.3,0.1
English Units
Geom File=g01
Flow File=f01
Plan File=p01
Y Axis Title=Elevation
X Axis Title(PF)=Main Channel Distance
X Axis Title(XS)=Station
BEGIN DESCRIPTION:
ERA BRANCH
END DESCRIPTION:
DSS Export Rating Curves= 0
DSS Export Rating Curve Sorted= 0
DSS Export Volume Flow Curves= 0
DXF OffsetX= 0
DXF OffsetY= 0
DXF ScaleX= 1
DXF ScaleY= 10

--- ERA BRANCH.p01 (plan) ---

Plan Title=Multiple Run
Program Version=4.10
Short Identifier=Multiple
Geom File=g01
Flow File=f01
Subcritical Flow
K Sum by GR= 0
Std Step Tol= 0.01
Critical Tol= 0.01
Num of Std Step Trials= 20
Max Error Tol= 0.3
Flow Tol Ratio= 0.001
Split Flow NTrial= 30
Split Flow Tol= 0.02
Split Flow Ratio= 0.02
Log Output Level= 0
Friction Slope Method= 1
Unsteady Friction Slope Method= 2
Unsteady Bridges Friction Slope Method= 1
Parabolic Critical Depth
Global Vel Dist= 1 , 1 , 1
Global Log Level= 0
CheckData=True
Encroach Param=-1 ,0,0, 0
BEGIN DESCRIPTION:
Multiple Run
END DESCRIPTION:
Computation Interval=1HOUR
Output Interval=1HOUR
Run HTab= 0
Run UNet= 0
Run PostProcess= 0
Run WQNet= 0
UNET Theta= 1
UNET Theta Warmup= 1
UNET ZTol= 0.02
UNET ZSATol= 0.05
UNET MxIter= 20
UNET MaxInSteps= 0
UNET DtIC= 0
UNET DtMin= 0
UNET MaxCRTS= 20
UNET WFStab= 2
UNET SFStab= 1
UNET WFX= 1
UNET SFX= 1
UNET DSS MLevel= 4
UNET DZMax Abort= 100
UNET Convert EG Bridges= 0
UNET Use Existing IB Tables=-1
UNET Froude Reduction=False
UNET Froude Limit= 1
UNET Froude Power= 10
UNET Time Slicing=0,0, 5
UNET Junction Losses=0
Instantaneous Interval=1HOUR
Write IC File= 0
Write IC File at Sim End=0
Echo Input=False
Echo Parameters=False
Echo Output=False
Write Detailed= 0
WQ AD Non Conservative
WQ ULTIMATE=-1
WQ Max Comp Step=1HOUR
WQ Output Interval=15MIN
WQ Output Selected Increments= 0
WQ Output face flow=0
WQ Output face velocity=0
WQ Output face area=0
WQ Output face dispersion=0
WQ Output cell volume=0
WQ Output cell surface area=0
WQ Output cell continuity=0
WQ Output cumulative cell continuity=0
WQ Output face conc=0
WQ Output face dconc_dx=0
WQ Output face courant=0
WQ Output face peclet=0
WQ Output face adv mass=0
WQ Output face disp mass=0
WQ Output cell mass=0
WQ Output cell source sink temp=0
WQ Output cell source sink nsm=0
WQ Output MaxMinRange=-1
WQ Daily Max Min Mean=-1
WQ Daily Range=0
WQ Daily Time=0
WQ Create Restart=0
WQ Fixed Restart=0
WQ System Summary=0
WQ Use Fixed Temperature=0
Sorting and Armoring Iterations= 10
XS Update Threshold= 0.02
Hydraulics Update Threshold= 0.02
Energy Slope Method= 1
Volume Change Method= 0
XS Weighting Method= 0
Number of US Weighted Cross Sections= 1
Number of DS Weighted Cross Sections= 1
Upstream XS Weight=0.25
Main XS Weight=0.5
Downstream XS Weight=0.25
Number of DS XS's Weighted with US Boundary= 1
Upstream Boundary Weight= 1
Weight of XSs Associated with US Boundary= 0
Number of US XS's Weighted with DS Boundary= 1
Downstream Boundary Weight= 0.5
Weight of XSs Associated with DS Boundary= 0.5
Sediment Output Level= 4
Mass or Volume Output= 0
Output Increment Type= 1
Profile and TS Output Increment= 10
XS Output Flag= 0
XS Output Increment= 10
Disregard all LS=0
Disregard all Conn=0
Disregard all Breaches=0
Disregard all Pumps=0

--- ERA BRANCH.f01 (steady flow) ---

Flow Title=Multiple
Program Version=4.10
Number of Profiles= 7
Profile Names=10-year,25-year,50-year,1pct_min,100-year,1pct_plu,500-year
River Rch & RM=ERA BRANCH,Reach-1         ,10817
     476     642     866     385    1164    3515    2172
River Rch & RM=ERA BRANCH,Reach-1         ,9220
     887    1233    1695     766    2314    6988    4463
River Rch & RM=ERA BRANCH,Reach-1         ,3696
     927    1286    1765     796    2405    7263    4618
Boundary for River Rch & Prof#=ERA BRANCH,Reach-1         , 1
Up Type= 0
Dn Type= 3
Dn Slope=0.005
Boundary for River Rch & Prof#=ERA BRANCH,Reach-1         , 2
Up Type= 0
Dn Type= 3
Dn Slope=0.005
Boundary for River Rch & Prof#=ERA BRANCH,Reach-1         , 3
Up Type= 0
Dn Type= 3
Dn Slope=0.005
Boundary for River Rch & Prof#=ERA BRANCH,Reach-1         , 4
Up Type= 0
Dn Type= 3
Dn Slope=0.005
Boundary for River Rch & Prof#=ERA BRANCH,Reach-1         , 5
Up Type= 0
Dn Type= 3
Dn Slope=0.005
Boundary for River Rch & Prof#=ERA BRANCH,Reach-1         , 6
Up Type= 0
Dn Type= 3
Dn Slope=0.005
Boundary for River Rch & Prof#=ERA BRANCH,Reach-1         , 7
Up Type= 0
Dn Type= 3
Dn Slope=0.005
DSS Import GetInterval= 0
DSS Import GetPeak= 0
DSS Import FillOption= 0

--- ERA BRANCH.g01 (geometry) ---

Geom Title=Existing Conditions
Program Version=4.10

River Reach=ERA BRANCH      ,Reach-1
Reach XY= 30
      3736346.79     10244290.65      3736458.57     10244505.19
      3736746.77     10244651.03      3736744.16     10244989.57
      3736855.28     10245043.39      3736853.54     10245294.26
      3737118.23     10245576.84      3737138.23     10245836.84
      3737058.23     10246116.84      3736878.23     10246306.84
      3736918.23     10246656.84      3736408.23     10246506.84
      3736148.23     10246776.84      3736118.23     10246936.84
      3736248.23     10246956.84      3736358.23     10247136.84
      3736308.23     10247416.84      3736088.23     10247596.84
      3736238.23     10247736.84      3736198.23     10248316.84
      3735898.23     10248676.84      3735838.23     10248936.84
      3735968.23     10249206.84      3736188.23     10249306.84
      3736418.23     10249626.84      3736478.23     10250006.84
      3736698.23      10250412.4      3736791.51     10250484.91
      3737271.93     10250463.75      3736876.76     10251481.87

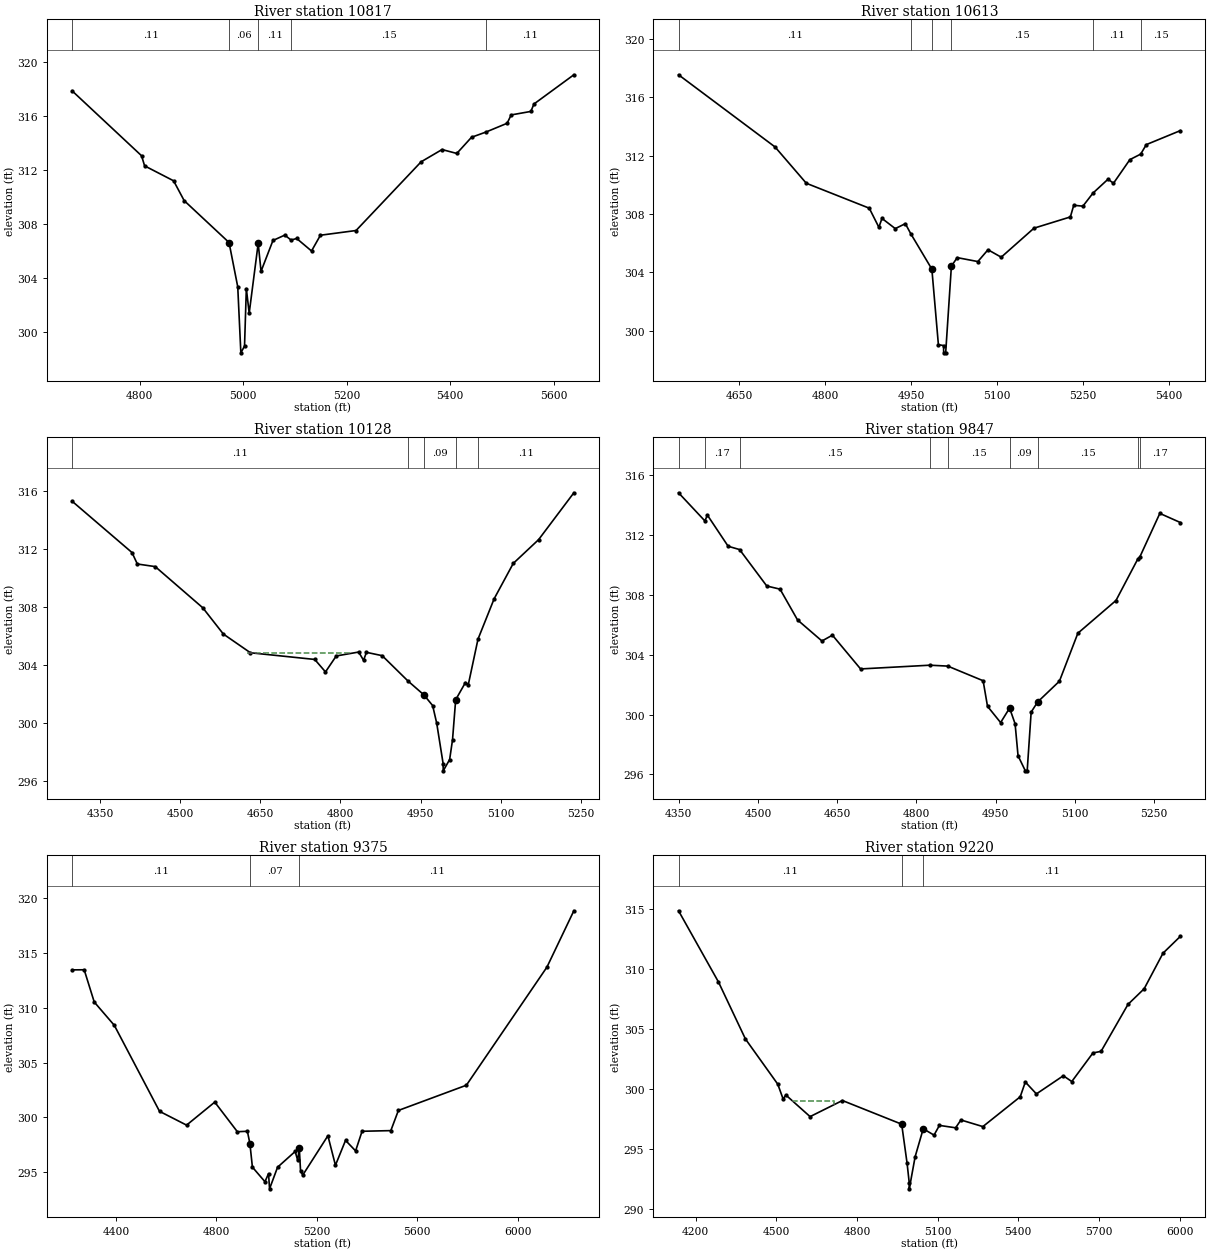
Type RM Length L Ch R = 1 ,10817   ,204,204,204
BEGIN DESCRIPTION:
ERA BRANCH 16.0
END DESCRIPTION:
XS GIS Cut Line= 3
      3736017.87     10244411.07      3736337.91     10244328.98
      3736917.83     10244061.08
#Sta/Elev= 30
  4669.6  317.88  4803.8  313.06  4809.7  312.31  4865.7   311.2  4886.1  309.73
  4972.8  306.62  4989.6  303.33  4995.6  298.43  5002.7  298.93  5006.2   303.2
  5011.7  301.37  5029.1  306.56  5034.6  304.48  5057.6  306.77  5080.5  307.17
  5092.6   306.8  5103.4  306.92  5132.1  305.99  5149.3  307.16  5218.1  307.51
  5343.8  312.61  5384.2  313.52  5412.7  313.23  5441.1  314.43  5469.1  314.82
  5509.9  315.47  5517.7  316.09  5555.8  316.35  5561.7   316.9  5638.8  319.07
#Mann= 5 ,-1 , 0
  4669.6     .11       0  4972.8     .06       0  5029.1     .11       0
  5092.6     .15       0  5469.1     .11       0
Bank Sta=4972.8,5029.1
XS Rating Curve= 0 ,0
Exp/Cntr=0.3,0.1

Type RM Length L Ch R = 1 ,10613   ,485,485,485
BEGIN DESCRIPTION:
ERA BRANCH 15.0
END DESCRIPTION:
XS GIS Cut Line= 2
      3736014.29       10244660.       3736812.9     10244299.76
#Sta/Elev= 30
  4544.3  317.54  4712.8  312.59  4767.4   310.1  4877.3  308.39  4894.1  307.08
  4899.5  307.69  4922.7  306.99  4940.3  307.33  4949.6  306.65  4986.6  304.21
    4998  299.03    5007  298.97  5007.2  298.47  5010.7  298.47  5020.7  304.42
  5030.9     305  5066.9  304.73  5084.6  305.54  5107.7  305.03  5164.9  307.02
  5228.4  307.79  5234.3  308.59  5250.3  308.53    5268  309.43  5294.2  310.38
  5303.7   310.1  5332.3  311.72  5351.2   312.1    5361  312.75  5420.4  313.71
#Mann= 6 ,-1 , 0
  4544.3     .11       0  4949.6     .15       0  4986.6     .09       0
  5020.7     .15       0    5268     .11       0  5351.2     .15       0
Bank Sta=4986.6,5020.7
XS Rating Curve= 0 ,0
Exp/Cntr=0.3,0.1

Type RM Length L Ch R = 1 ,10128   ,281,281,281
BEGIN DESCRIPTION:
Mapping XS 4db31181
END DESCRIPTION:
XS GIS Cut Line= 3
      3736066.41     10244833.61      3736595.89     10244772.85
      3736973.15     10244621.08
#Sta/Elev= 30
  4297.5  315.31  4409.7  311.77  4419.7  310.98  4453.2   310.8  4542.3  307.96
  4580.8  306.15  4631.5  304.86  4751.9   304.4    4772  303.54  4792.2  304.64
  4834.2  304.91  4843.3  304.34  4848.7  304.89  4878.2  304.66  4926.6  302.91
  4956.2  301.96  4972.7  301.22  4980.3     300  4992.3  297.22  4992.5  296.72
  5004.5   297.5  5009.9  298.86  5015.8  301.62  5034.1  302.81  5039.5  302.67
  5057.6   305.8  5087.8  308.58  5123.6  311.02  5171.1  312.66  5237.1  315.89
#Mann= 5 ,-1 , 0
  4297.5     .11       0  4926.6     .15       0  4956.2     .09       0
  5015.8     .15       0  5057.6     .11       0
#XS Ineff= 1 ,-1
    4625  4822.4  304.86
Permanent Ineff=
       F
Bank Sta=4956.2,5015.8
XS Rating Curve= 0 ,0
Exp/Cntr=0.3,0.1

Type RM Length L Ch R = 1 ,9847    ,472,472,472
BEGIN DESCRIPTION:
ERA BRANCH 14.0
END DESCRIPTION:
XS GIS Cut Line= 3
      3736117.89     10245161.06      3736740.69     10244973.94
      3737017.89     10244861.06
#Sta/Elev= 30
  4349.7  314.84  4399.5  312.96  4404.4  313.34  4443.6  311.26  4465.2  311.04
  4516.7   308.6  4541.8  308.39  4574.9  306.33  4621.1  304.92  4640.9  305.31
  4694.2  303.05  4825.3   303.3  4859.2  303.24  4926.1  302.26  4934.4  300.55
  4959.2  299.46  4976.2  300.43  4986.6  299.38  4992.2  297.24    5006  296.23
  5009.5  296.23    5017  300.16  5029.3  300.84  5070.5  302.23  5105.4  305.44
  5177.5  307.63    5219  310.42  5222.6  310.54  5260.5  313.46  5299.3  312.85
#Mann= 9 ,-1 , 0
  4349.7     .11       0  4399.5     .17       0  4465.2     .15       0
  4825.3     .11       0  4859.2     .15       0  4976.2     .09       0
  5029.3     .15       0    5219     .11       0  5222.6     .17       0
#XS Ineff= 1 ,-1
    4930  4976.2  300.43
Permanent Ineff=
       F
Bank Sta=4976.2,5029.3
XS Rating Curve= 0 ,0
Exp/Cntr=0.3,0.1

Type RM Length L Ch R = 1 ,9375    ,155,155,155
BEGIN DESCRIPTION:
ERA BRANCH 13.0
END DESCRIPTION:
XS GIS Cut Line= 3
      3736139.55     10245302.36       3736914.3     10245325.51
      3738134.76     10245423.74
#Sta/Elev= 30
  4224.9  313.45  4273.2  313.46  4313.2  310.52  4393.3  308.39  4573.4  300.55
  4681.2  299.29  4793.5  301.39  4883.5  298.69  4923.5  298.73  4933.5  297.61
  4943.5  295.46  4993.5  294.13  5007.8  294.87  5011.8  293.48  5043.7  295.45
  5113.9  296.89  5123.9  296.08  5130.3   297.2  5135.3  295.14    5144  294.73
  5244.3  298.32  5274.4  295.63  5314.6   297.9  5354.7  296.94  5380.4  298.73
  5495.1  298.79  5525.2  300.63  5796.1  302.93  6117.1   313.7  6224.4  318.84
#Mann= 3 ,-1 , 0
  4224.9     .11       0  4933.5     .07       0  5130.3     .11       0
Bank Sta=4933.5,5130.3
XS Rating Curve= 0 ,0
Exp/Cntr=0.3,0.1

Type RM Length L Ch R = 1 ,9220    ,237,237,237
BEGIN DESCRIPTION:
ERA BRANCH 12.0
END DESCRIPTION:
XS GIS Cut Line= 2
      3736139.54     10245397.85      3738002.12      10245510.7
#Sta/Elev= 30
  4136.5  314.83  4285.1   308.9  4385.3  304.16  4505.5   300.4  4525.5  299.16
  4535.5   299.5  4625.7   297.7  4745.9  299.04  4966.3  297.07  4986.4  293.82
  4994.4  292.19  4994.6  291.69  5016.4  294.37  5046.5  296.69  5086.6  296.16
  5106.6  296.97  5166.7  296.77  5186.7  297.42  5268.2  296.87  5407.1  299.35
  5426.1  300.58  5467.3  299.59  5567.4   301.1  5598.9  300.62  5677.6     303
  5707.7  303.13  5807.9  307.04    5868  308.34  5938.1   311.3  6002.5   312.7
#Mann= 3 ,-1 , 0
  4136.5     .11       0  4966.3     .07       0  5046.5     .11       0
#XS Ineff= 1 ,-1
    4560  4715.9  299.02
Permanent Ineff=
       F
Bank Sta=4966.3,5046.5
XS Rating Curve= 0 ,0
Exp/Cntr=0.3,0.1

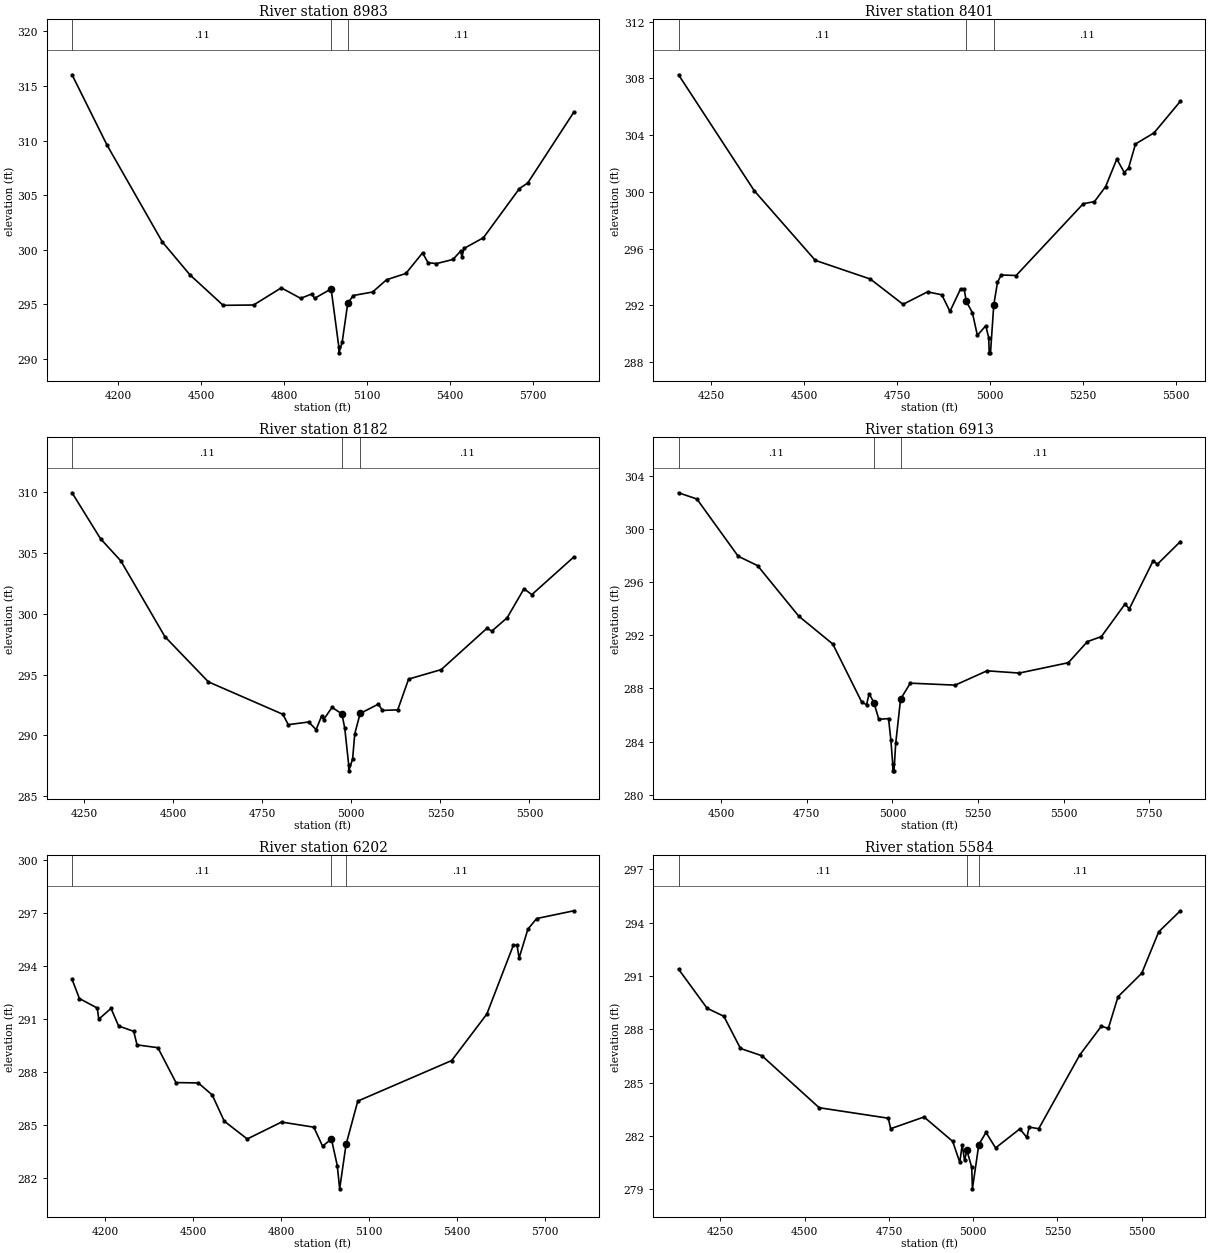
Type RM Length L Ch R = 1 ,8983    ,582,582,582
BEGIN DESCRIPTION:
Mapping XS 78db12ab
END DESCRIPTION:
XS GIS Cut Line= 3
      3736161.89     10245597.51      3736895.37     10245636.57
       3737974.5     10245571.56
#Sta/Elev= 30
  4032.2  316.03  4158.3  309.61  4358.6  300.73  4458.8  297.71  4578.9  294.92
  4689.1  294.95  4789.2  296.52  4859.4  295.56  4899.4  295.96  4909.5  295.56
  4969.6  296.42  4997.6  291.07  4997.9  290.57  5009.6  291.56  5029.7  295.11
  5049.7  295.82  5119.8  296.14  5169.9  297.26  5240.1  297.84  5300.2  299.72
  5320.2  298.83  5350.3  298.74  5410.4  299.12  5437.8  299.88  5442.8  299.36
  5450.4  300.13  5520.6  301.11  5650.8  305.61  5680.9  306.12  5847.8  312.61
#Mann= 3 ,-1 , 0
  4032.2     .11       0  4969.6     .06       0  5029.7     .11       0
Bank Sta=4969.6,5029.7
XS Rating Curve= 0 ,0
Exp/Cntr=0.3,0.1

Type RM Length L Ch R = 1 ,8401    ,219,219,219
BEGIN DESCRIPTION:
ERA BRANCH 11.0
END DESCRIPTION:
XS GIS Cut Line= 3
      3736318.12     10245723.38      3737058.23     10246116.84
      3737568.12      10246157.4
#Sta/Elev= 30
  4161.8  308.25  4365.4  300.08  4529.6  295.17  4677.8  293.85  4765.7  292.07
  4831.6  292.95  4869.9  292.74  4891.9  291.57  4920.3  293.15  4930.2  293.12
  4935.9  292.27  4952.2  291.48  4965.6  289.88  4988.2  290.56  4996.1  289.71
  4997.4  288.65  5000.9  288.65  5009.7  292.03  5019.7  293.62  5029.7  294.14
  5069.8   294.1  5250.4  299.16  5280.5  299.31  5310.6  300.37  5340.7  302.31
  5360.8  301.36  5372.2  301.67  5390.9  303.37    5441  304.16  5511.5  306.38
#Mann= 3 , 0 , 0
  4161.8     .11       0  4935.9     .06       0  5009.7     .11       0
Bank Sta=4935.9,5009.7
XS Rating Curve= 0 ,0
Exp/Cntr=0.3,0.1

Type RM Length L Ch R = 1 ,8182    ,1269,1269,1269
BEGIN DESCRIPTION:
ERA BRANCH 10.0
END DESCRIPTION:
XS GIS Cut Line= 3
      3736267.84     10245811.06      3736999.53     10246291.95
      3737523.77      10246391.6
#Sta/Elev= 30
  4215.7  309.96  4295.6  306.18  4352.8  304.35  4476.4  298.12  4598.6   294.4
  4807.8  291.73  4822.8  290.88  4880.1   291.1  4901.1  290.47  4916.2  291.57
  4922.2   291.3  4945.7   292.3  4973.5  291.77  4981.6  290.57  4992.5  287.58
  4992.8  287.08  5003.6  288.07  5009.6  290.13  5024.7   291.8  5075.9  292.57
  5087.3  292.05  5130.3   292.1  5160.8  294.63  5252.4  295.41  5380.4   298.8
  5394.9  298.59  5437.7  299.68  5484.8  302.06  5506.9  301.58  5624.9  304.68
#Mann= 3 , 0 , 0
  4215.7     .11       0  4973.5     .06       0  5024.7     .11       0
Bank Sta=4973.5,5024.7
XS Rating Curve= 0 ,0
Exp/Cntr=0.3,0.1

Type RM Length L Ch R = 1 ,6913    ,711,711,711
BEGIN DESCRIPTION:
ERA BRANCH 9.0
END DESCRIPTION:
XS GIS Cut Line= 3
      3735833.76     10246229.47       3736372.8     10246721.64
      3737084.61     10246903.49
#Sta/Elev= 30
  4375.8  302.75  4429.4  302.28  4549.7  297.97  4606.4  297.26  4726.7  293.45
    4826  291.35  4910.4  286.98  4924.6  286.77    4932   287.6  4946.2  286.93
  4960.4  285.67  4988.8  285.73  4995.6   284.1    5001  282.29  5001.2  281.79
  5004.7  281.79  5009.7  283.86  5023.9   287.2  5052.3   288.4  5183.2  288.25
  5276.1  289.33  5370.1  289.16  5513.5  289.94  5569.1  291.53    5610  291.91
  5678.6  294.35  5691.7  294.01  5761.2  297.63  5773.3  297.36  5840.4  299.07
#Mann= 3 ,-1 , 0
  4375.8     .11       0  4946.2     .06       0  5023.9     .11       0
Bank Sta=4946.2,5023.9
XS Rating Curve= 0 ,0
Exp/Cntr=0.3,0.1

Type RM Length L Ch R = 1 ,6202    ,618,618,618
BEGIN DESCRIPTION:
ERA BRANCH 8.0
END DESCRIPTION:
XS GIS Cut Line= 3
      3735453.55     10246924.77      3736139.58     10247091.43
      3737144.53     10247109.63
#Sta/Elev= 30
    4087  293.25    4112  292.16  4172.9  291.62  4178.1  290.99  4219.8   291.6
  4245.8   290.6  4297.2   290.3  4308.5  289.53  4379.6  289.37  4441.3  287.39
  4517.3  287.37  4564.8  286.69    4606   285.2  4684.4  284.19  4801.3  285.15
  4911.3  284.86  4941.3  283.78  4971.3  284.19  4991.3  282.68  4999.5  281.36
  5021.3  283.88  5061.3  286.34  5381.4  288.64  5501.4  291.28  5591.4  295.17
  5604.1  295.19  5611.4  294.46  5641.4   296.1  5671.4   296.7  5798.1  297.14
#Mann= 3 , 0 , 0
    4087     .11       0  4971.3     .06       0  5021.3     .11       0
Bank Sta=4971.3,5021.3
XS Rating Curve= 0 ,0
Exp/Cntr=0.3,0.1

Type RM Length L Ch R = 1 ,5584    ,536,536,536
BEGIN DESCRIPTION:
ERA BRANCH 7.0
END DESCRIPTION:
XS GIS Cut Line= 3
      3735517.85     10246961.07      3736138.23     10247576.84
      3736617.82     10247961.04
#Sta/Elev= 30
  4125.9  291.38  4210.7  289.18  4260.3  288.73  4309.7  286.92  4373.4  286.51
  4543.1  283.59  4748.1     283  4755.2  282.41  4854.2  283.07  4939.1   281.7
  4960.3  280.52  4967.4  281.51  4974.4  280.63  4981.5  281.19  4995.7  280.23
  4997.7  279.03  5016.7  281.52    5038   282.2  5066.4  281.33  5138.4   282.4
  5159.2  281.92  5166.1   282.5  5194.4  282.41    5316  286.55  5380.1  288.17
  5400.9  288.05  5429.7  289.83  5500.1  291.15  5550.5  293.48  5614.5  294.66
#Mann= 3 , 0 , 0
  4125.9     .11       0  4981.5     .06       0  5016.7     .11       0
Bank Sta=4981.5,5016.7
XS Rating Curve= 0 ,0
Exp/Cntr=0.3,0.1

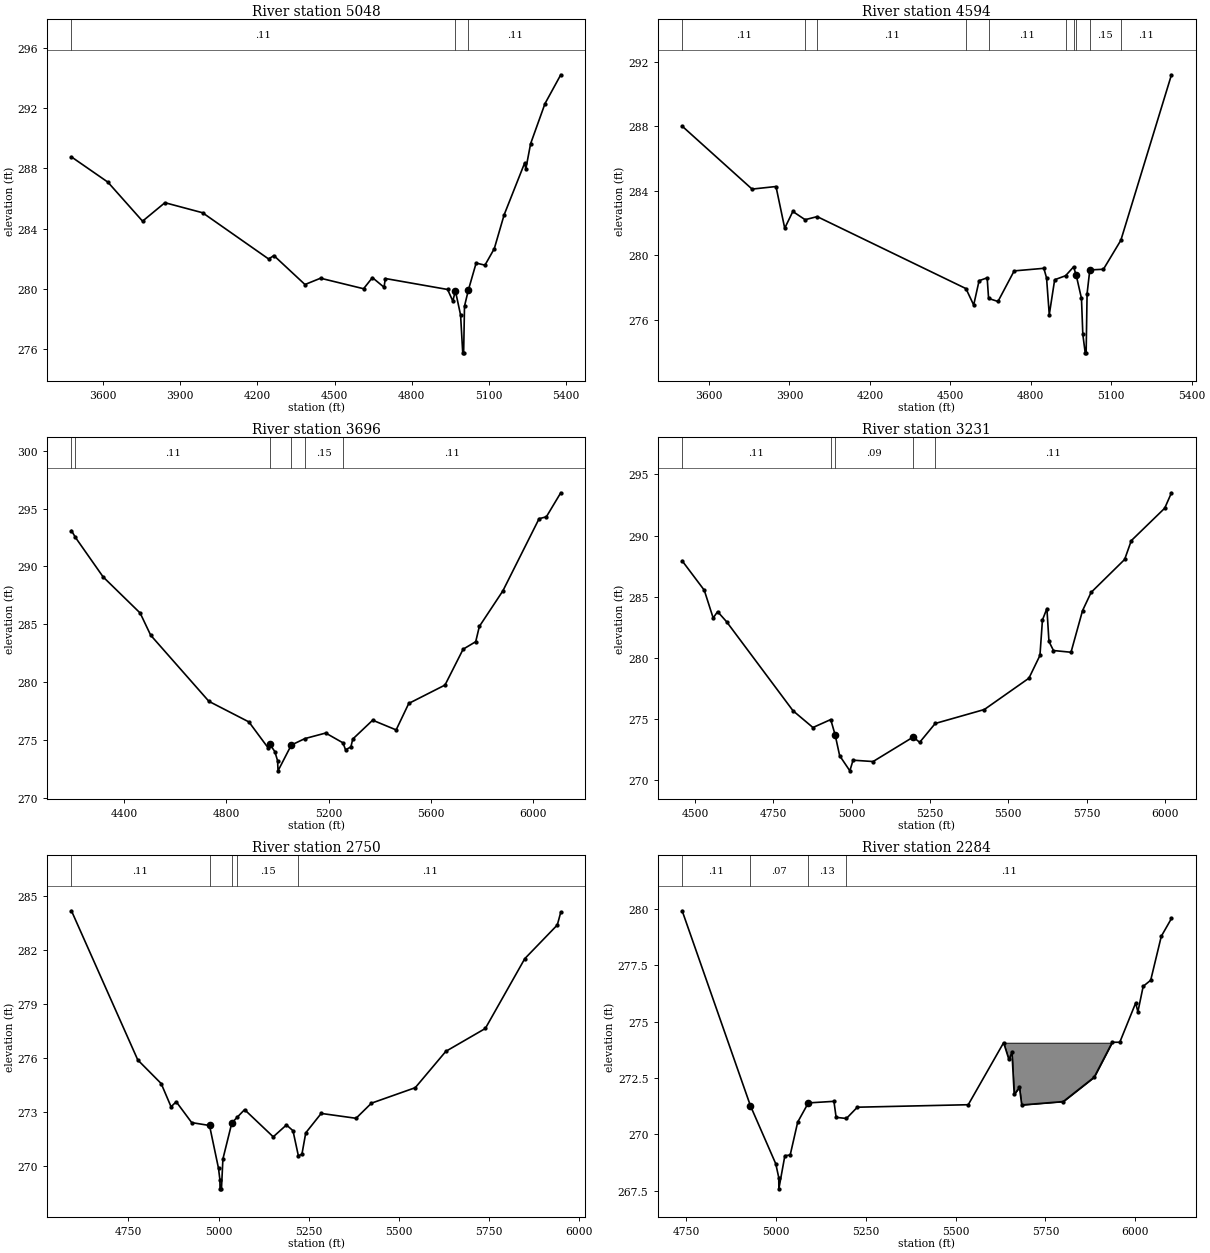
Type RM Length L Ch R = 1 ,5048    ,454,454,454
BEGIN DESCRIPTION:
Mapping XS e67ff54b
END DESCRIPTION:
XS GIS Cut Line= 2
       3734677.4     10247750.94      3736564.13     10247993.82
#Sta/Elev= 30
  3476.7  288.77  3618.3  287.09  3753.2  284.49  3840.1  285.72  3986.6  285.05
  4243.4  281.97  4263.6   282.2  4384.6  280.27  4445.1  280.69  4612.4  279.99
  4646.7  280.73  4691.9  280.09  4697.1  280.67  4939.1  279.94  4959.3  279.17
  4969.4  279.85  4989.5  278.24  4997.9  275.72  5001.4  275.72  5004.8  278.83
  5019.8   279.9    5050   281.7  5084.3  281.56  5120.6  282.66  5158.8  284.91
  5238.3  288.35  5243.3  287.98  5261.8  289.65  5317.7  292.32    5379  294.24
#Mann= 3 , 0 , 0
  3476.7     .11       0  4969.4     .06       0  5019.8     .11       0
Bank Sta=4969.4,5019.8
XS Rating Curve= 0 ,0
Exp/Cntr=0.3,0.1

Type RM Length L Ch R = 1 ,4594    ,898,898,898
BEGIN DESCRIPTION:
ERA BRANCH 6.0
END DESCRIPTION:
XS GIS Cut Line= 3
       3734707.8      10248145.9      3736198.23     10248316.84
       3736517.9     10248261.06
#Sta/Elev= 30
  3499.8  288.01  3760.5   284.1  3849.7  284.26  3882.3  281.67  3912.5  282.71
  3958.3   282.2  4003.4  282.39  4558.1  277.92  4586.9   276.9  4607.1  278.41
  4637.2  278.59  4642.5  277.31  4677.5  277.12  4737.9  279.02  4848.6  279.18
  4858.7  278.58  4868.8   276.3  4888.9  278.47  4929.7  278.72  4959.4  279.27
  4969.4  278.74  4988.9  277.31  4993.9  275.08  5002.8  273.93  5006.3  273.93
  5009.8   277.6  5019.9  279.08  5070.7  279.12  5135.7  280.92  5324.5   291.2
#Mann= 10 ,-1 , 0
  3499.8     .11       0  3958.3     .15       0  4003.4     .11       0
  4558.1     .15       0  4642.5     .11       0  4929.7     .15       0
  4959.4     .12       0  4969.4     .09       0  5019.9     .15       0
  5135.7     .11       0
Bank Sta=4969.4,5019.9
XS Rating Curve= 0 ,0
Exp/Cntr=0.3,0.1

Type RM Length L Ch R = 1 ,3696    ,465,465,465
BEGIN DESCRIPTION:
ERA BRANCH 5.0
END DESCRIPTION:
XS GIS Cut Line= 3
      3735067.81     10249211.08      3735848.23     10249006.84
      3736667.83     10248261.09
#Sta/Elev= 30
  4193.3  293.09  4208.9   292.5  4317.4  289.08  4462.1  285.96  4503.4  284.04
  4731.3  278.32  4887.8  276.54  4963.5  274.28  4968.7  274.64  4989.3  273.97
    5000  273.18  5001.7  272.31  5053.6  274.54  5106.9   275.1  5188.2  275.58
  5255.9  274.73  5265.9  274.13  5286.8  274.38  5294.2  275.06    5372  276.69
  5463.9  275.85  5513.3  278.14  5655.1  279.73    5726  282.83  5775.3  283.48
  5789.5   284.8  5881.4  287.87  6023.3  294.12  6051.7  294.28  6108.1  296.36
#Mann= 6 ,-1 , 0
  4193.3     .17       0  4208.9     .11       0  4968.7     .06       0
  5053.6     .11       0  5106.9     .15       0  5255.9     .11       0
Bank Sta=4968.7,5053.6
XS Rating Curve= 0 ,0
Exp/Cntr=0.3,0.1

Type RM Length L Ch R = 1 ,3231    ,481,481,481
BEGIN DESCRIPTION:
ERA BRANCH 4.0
END DESCRIPTION:
XS GIS Cut Line= 3
      3735767.88     10249661.04      3736128.23     10249256.84
      3736767.87     10248461.04
#Sta/Elev= 30
  4458.5  287.94  4529.1  285.54  4557.5  283.27  4571.7  283.79  4600.2  282.97
  4812.5  275.69  4876.1  274.32  4932.9  274.97  4947.1  273.71  4961.4  272.02
    4994  270.78  5004.2  271.65  5068.2  271.54  5196.2  273.54    5217  273.11
  5266.6  274.65  5423.4  275.79  5565.8  278.35    5601  280.21    5609  283.11
  5623.2  284.04  5629.8  281.35  5644.2  280.61  5700.2  280.47    5737  283.87
  5764.4  285.36  5871.4  288.05  5892.7  289.59  5999.4  292.24    6021   293.5
#Mann= 5 ,-1 , 0
  4458.5     .11       0  4932.9     .15       0  4947.1     .09       0
  5196.2     .13       0  5266.6     .11       0
Bank Sta=4947.1,5196.2
XS Rating Curve= 0 ,0
Exp/Cntr=0.3,0.1

Type RM Length L Ch R = 1 ,2750    ,466,466,466
BEGIN DESCRIPTION:
ERA BRANCH 3.0
END DESCRIPTION:
XS GIS Cut Line= 3
      3736067.86     10249861.06      3736378.23     10249596.84
      3736717.83     10248711.12
#Sta/Elev= 30
  4592.4  284.19  4776.3   275.9  4841.1  274.59  4868.5   273.3  4882.8  273.58
  4925.7  272.42  4975.1  272.26    5000  269.88  5003.9  269.24  5004.2  268.74
  5008.2  268.74  5012.2   270.4  5036.9   272.4  5051.4  272.71  5072.3  273.14
  5151.7  271.63  5188.3  272.29  5206.4  271.97  5221.2  270.59  5231.1  270.65
  5241.8  271.85  5284.6  272.93  5381.2  272.66  5423.9   273.5  5545.3  274.36
  5630.1  276.38  5739.5  277.65  5848.9  281.53    5939   283.4  5948.6  284.11
#Mann= 5 ,-1 , 0
  4592.4     .11       0  4975.1     .06       0  5036.9     .11       0
  5051.4     .15       0  5221.2     .11       0
Bank Sta=4975.1,5036.9
XS Rating Curve= 0 ,0
Exp/Cntr=0.3,0.1

Type RM Length L Ch R = 1 ,2284    ,117,117,117
BEGIN DESCRIPTION:
ERA BRANCH 2.0
END DESCRIPTION:
XS GIS Cut Line= 3
      3736217.86     10250011.07      3736478.23     10250006.84
      3737117.86     10249111.07
#Sta/Elev= 30
  4739.6  279.91  4929.6  271.26    5000  268.69  5008.3  268.08  5008.6  267.58
  5025.3  269.05  5040.1  269.08    5061  270.54  5090.5  271.39  5161.8  271.46
  5167.9  270.75  5196.5   270.7  5226.9   271.2  5535.4  271.31  5633.8  274.06
  5648.4  273.32    5657  273.63  5663.2  271.77  5677.9  272.08  5684.1   271.3
  5799.6  271.45  5885.6  272.53    5936  274.08  5956.9  274.08  6001.1  275.82
  6007.3  275.43    6022  276.56  6042.9  276.83  6072.4  278.78  6100.7  279.57
#Mann= 4 ,-1 , 0
  4739.6     .11       0  4929.6     .07       0  5090.5     .13       0
  5196.5     .11       0
#Block Obstruct= 1 ,-1
  5633.8    5948  274.06
Bank Sta=4929.6,5090.5
XS Rating Curve= 0 ,0
Exp/Cntr=0.3,0.1

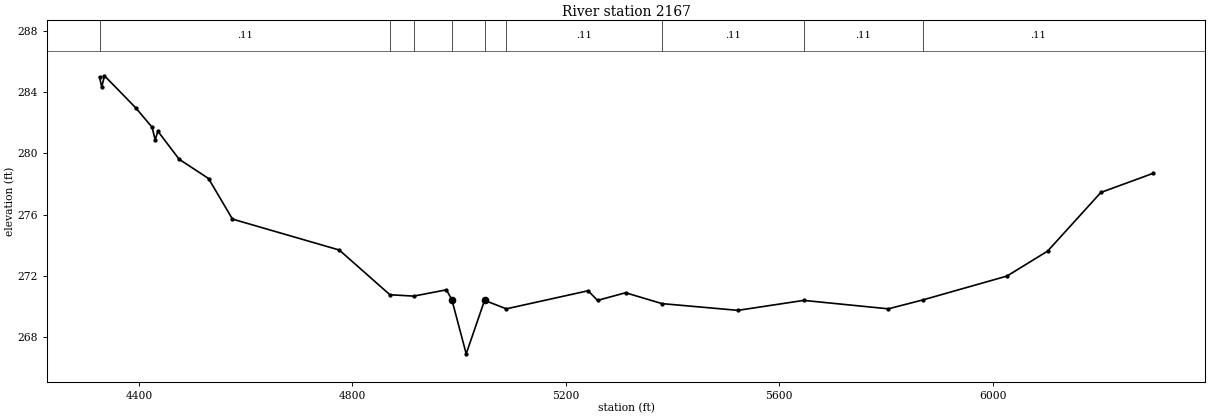
Type RM Length L Ch R = 1 ,2167    ,0,0,0
BEGIN DESCRIPTION:
ERA BRANCH 1.0
END DESCRIPTION:
XS GIS Cut Line= 3
      3735901.44      10250227.5      3736808.52     10250038.27
      3737220.55     10249075.43
#Sta/Elev= 30
    4326  284.97  4330.2  284.33  4335.3  285.06  4393.8  282.97  4424.5   281.7
  4430.3  280.88  4435.4  281.44  4475.2  279.61  4530.3  278.35  4575.2   275.7
  4775.3  273.68  4870.2  270.76  4914.8  270.67  4976.1  271.08  4986.3  270.44
  5013.2   266.9  5047.6  270.39  5088.5  269.84  5241.7  271.02  5259.3  270.39
  5311.9  270.89  5380.1  270.18  5522.4  269.74  5645.7  270.39  5804.3  269.84
  5868.9  270.42  6026.7  271.98  6102.9  273.61  6202.7  277.44  6299.9  278.68
#Mann= 9 ,-1 , 0
    4326     .11       0  4870.2     .11       0  4914.8     .11       0
  4986.3     .06       0  5047.6     .11       0  5088.5     .11       0
  5380.1     .11       0  5645.7     .11       0  5868.9     .11       0
Bank Sta=4986.3,5047.6
XS Rating Curve= 0 ,0
Exp/Cntr=0.3,0.1

Chan Stop Cuts=-1
Use User Specified Reach Order=0
Composite Channel Slope=5