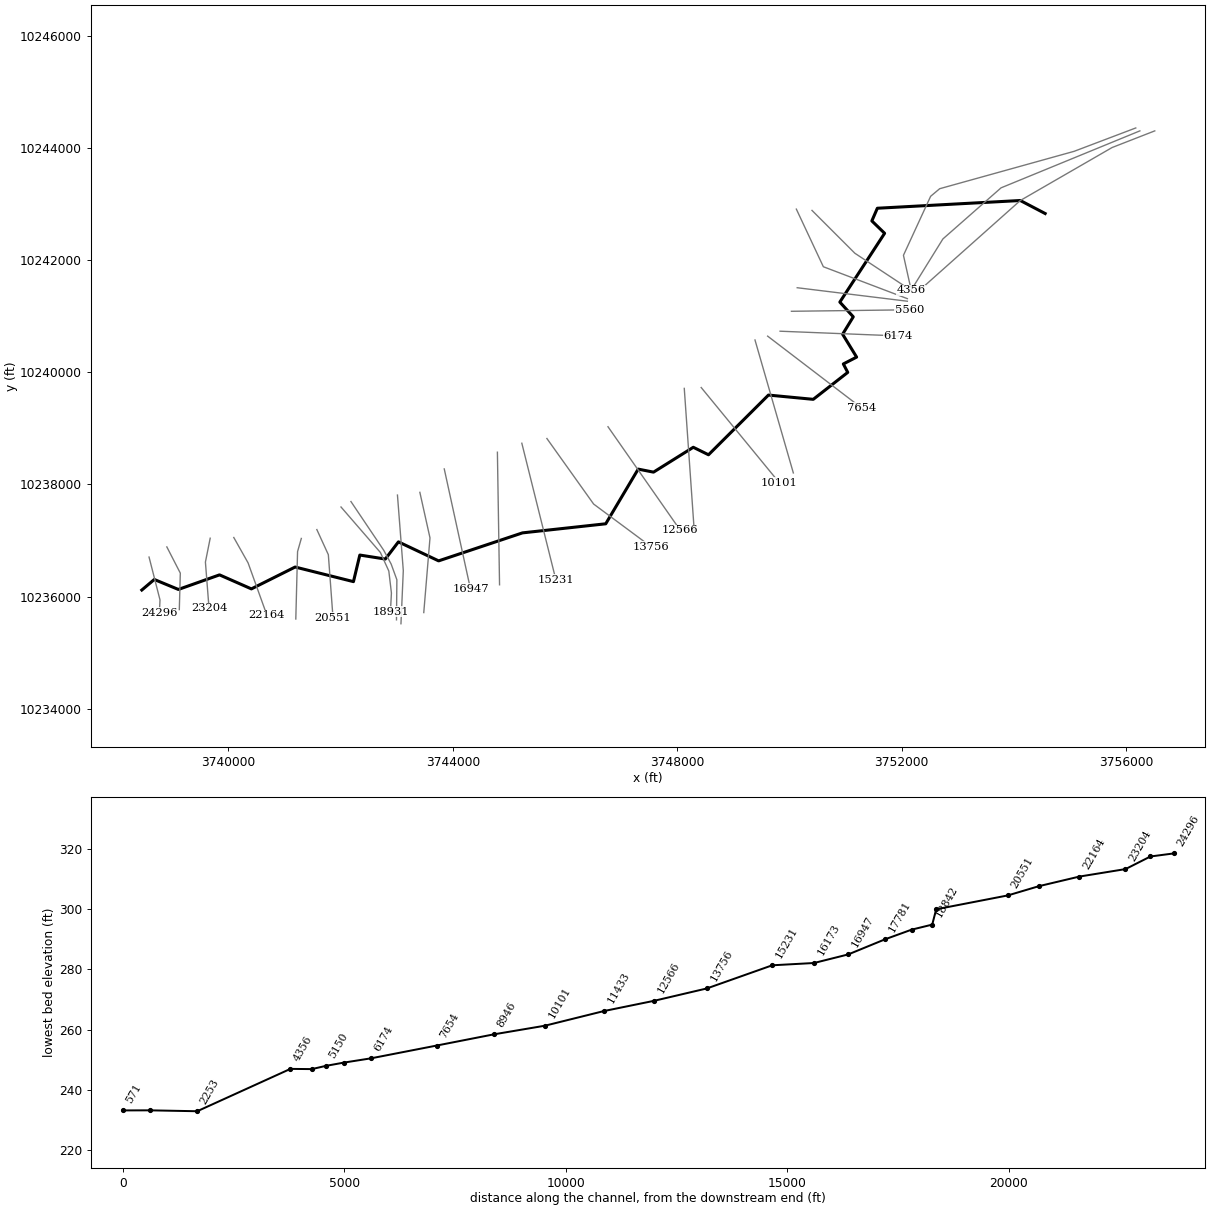
--- GUM BRANCH.prj (project) ---

Proj Title=GUM BRANCH Base Level Engineering
Current Plan=p01
Default Exp/Contr=0.3,0.1
English Units
Geom File=g01
Flow File=f01
Plan File=p01
Y Axis Title=Elevation
X Axis Title(PF)=Main Channel Distance
X Axis Title(XS)=Station
BEGIN DESCRIPTION:
GUM BRANCH
END DESCRIPTION:
DSS Export Rating Curves= 0
DSS Export Rating Curve Sorted= 0
DSS Export Volume Flow Curves= 0
DXF OffsetX= 0
DXF OffsetY= 0
DXF ScaleX= 1
DXF ScaleY= 10

--- GUM BRANCH.p01 (plan) ---

Plan Title=Multiple Run
Program Version=4.10
Short Identifier=Multiple
Geom File=g01
Flow File=f01
Subcritical Flow
K Sum by GR= 0
Std Step Tol= 0.01
Critical Tol= 0.01
Num of Std Step Trials= 20
Max Error Tol= 0.3
Flow Tol Ratio= 0.001
Split Flow NTrial= 30
Split Flow Tol= 0.02
Split Flow Ratio= 0.02
Log Output Level= 0
Friction Slope Method= 1
Unsteady Friction Slope Method= 2
Unsteady Bridges Friction Slope Method= 1
Parabolic Critical Depth
Global Vel Dist= 1 , 1 , 1
Global Log Level= 0
CheckData=True
Encroach Param=-1 ,0,0, 0
BEGIN DESCRIPTION:
Multiple Run
END DESCRIPTION:
Computation Interval=1HOUR
Output Interval=1HOUR
Run HTab= 0
Run UNet= 0
Run PostProcess= 0
Run WQNet= 0
UNET Theta= 1
UNET Theta Warmup= 1
UNET ZTol= 0.02
UNET ZSATol= 0.05
UNET MxIter= 20
UNET MaxInSteps= 0
UNET DtIC= 0
UNET DtMin= 0
UNET MaxCRTS= 20
UNET WFStab= 2
UNET SFStab= 1
UNET WFX= 1
UNET SFX= 1
UNET DSS MLevel= 4
UNET DZMax Abort= 100
UNET Convert EG Bridges= 0
UNET Use Existing IB Tables=-1
UNET Froude Reduction=False
UNET Froude Limit= 1
UNET Froude Power= 10
UNET Time Slicing=0,0, 5
UNET Junction Losses=0
Instantaneous Interval=1HOUR
Write IC File= 0
Write IC File at Sim End=0
Echo Input=False
Echo Parameters=False
Echo Output=False
Write Detailed= 0
WQ AD Non Conservative
WQ ULTIMATE=-1
WQ Max Comp Step=1HOUR
WQ Output Interval=15MIN
WQ Output Selected Increments= 0
WQ Output face flow=0
WQ Output face velocity=0
WQ Output face area=0
WQ Output face dispersion=0
WQ Output cell volume=0
WQ Output cell surface area=0
WQ Output cell continuity=0
WQ Output cumulative cell continuity=0
WQ Output face conc=0
WQ Output face dconc_dx=0
WQ Output face courant=0
WQ Output face peclet=0
WQ Output face adv mass=0
WQ Output face disp mass=0
WQ Output cell mass=0
WQ Output cell source sink temp=0
WQ Output cell source sink nsm=0
WQ Output MaxMinRange=-1
WQ Daily Max Min Mean=-1
WQ Daily Range=0
WQ Daily Time=0
WQ Create Restart=0
WQ Fixed Restart=0
WQ System Summary=0
WQ Use Fixed Temperature=0
Sorting and Armoring Iterations= 10
XS Update Threshold= 0.02
Hydraulics Update Threshold= 0.02
Energy Slope Method= 1
Volume Change Method= 0
XS Weighting Method= 0
Number of US Weighted Cross Sections= 1
Number of DS Weighted Cross Sections= 1
Upstream XS Weight=0.25
Main XS Weight=0.5
Downstream XS Weight=0.25
Number of DS XS's Weighted with US Boundary= 1
Upstream Boundary Weight= 1
Weight of XSs Associated with US Boundary= 0
Number of US XS's Weighted with DS Boundary= 1
Downstream Boundary Weight= 0.5
Weight of XSs Associated with DS Boundary= 0.5
Sediment Output Level= 4
Mass or Volume Output= 0
Output Increment Type= 1
Profile and TS Output Increment= 10
XS Output Flag= 0
XS Output Increment= 10
Disregard all LS=0
Disregard all Conn=0
Disregard all Breaches=0
Disregard all Pumps=0

--- GUM BRANCH.f01 (steady flow) ---

Flow Title=Multiple
Program Version=4.10
Number of Profiles= 7
Profile Names=10-year,25-year,50-year,1pct_min,100-year,1pct_plu,500-year
River Rch & RM=GUM BRANCH,Reach-1         ,24296
    1325    1877    2613    1195    3608   10896    7116
River Rch & RM=GUM BRANCH,Reach-1         ,15231
    1611    2294    3205    1469    4437   13400    8798
River Rch & RM=GUM BRANCH,Reach-1         ,10101
    1698    2411    3363    1536    4640   14013    9150
River Rch & RM=GUM BRANCH,Reach-1         ,4356
    1883    2682    3746    1714    5177   15634   10239
River Rch & RM=GUM BRANCH,Reach-1         ,2253
    1883    2682    3746    1714    5177   15634   10239
Boundary for River Rch & Prof#=GUM BRANCH,Reach-1         , 1
Up Type= 0
Dn Type= 3
Dn Slope=0.0035
Boundary for River Rch & Prof#=GUM BRANCH,Reach-1         , 2
Up Type= 0
Dn Type= 3
Dn Slope=0.0035
Boundary for River Rch & Prof#=GUM BRANCH,Reach-1         , 3
Up Type= 0
Dn Type= 3
Dn Slope=0.0035
Boundary for River Rch & Prof#=GUM BRANCH,Reach-1         , 4
Up Type= 0
Dn Type= 3
Dn Slope=0.0035
Boundary for River Rch & Prof#=GUM BRANCH,Reach-1         , 5
Up Type= 0
Dn Type= 3
Dn Slope=0.0035
Boundary for River Rch & Prof#=GUM BRANCH,Reach-1         , 6
Up Type= 0
Dn Type= 3
Dn Slope=0.0035
Boundary for River Rch & Prof#=GUM BRANCH,Reach-1         , 7
Up Type= 0
Dn Type= 3
Dn Slope=0.0035
DSS Import GetInterval= 0
DSS Import GetPeak= 0
DSS Import FillOption= 0

--- GUM BRANCH.g01 (geometry) ---

Geom Title=Existing Conditions
Program Version=4.10

River Reach=GUM BRANCH      ,Reach-1
Reach XY= 30
      3738458.23     10236116.84      3738680.63     10236305.02
      3739110.04     10236127.16      3739843.31     10236387.21
      3740411.16     10236137.23      3741190.83     10236527.07
      3742230.12     10236266.68      3742343.64     10236740.68
      3742798.26     10236669.24      3743031.58     10236975.86
      3743748.07     10236636.87      3745242.52      10237136.1
      3746726.57     10237298.17      3747305.01     10238273.16
      3747578.32     10238219.22      3748286.89     10238662.58
      3748558.13     10238528.85      3749626.29     10239593.67
      3750425.08     10239517.57      3751039.78     10239998.13
      3750961.15     10240148.44      3751197.82     10240270.66
      3750948.28     10240678.69      3751138.23     10240988.89
       3750898.7     10241251.75      3751696.85     10242478.57
      3751469.42     10242699.36      3751567.36     10242925.31
      3754115.39      10243063.2      3754558.05     10242831.09

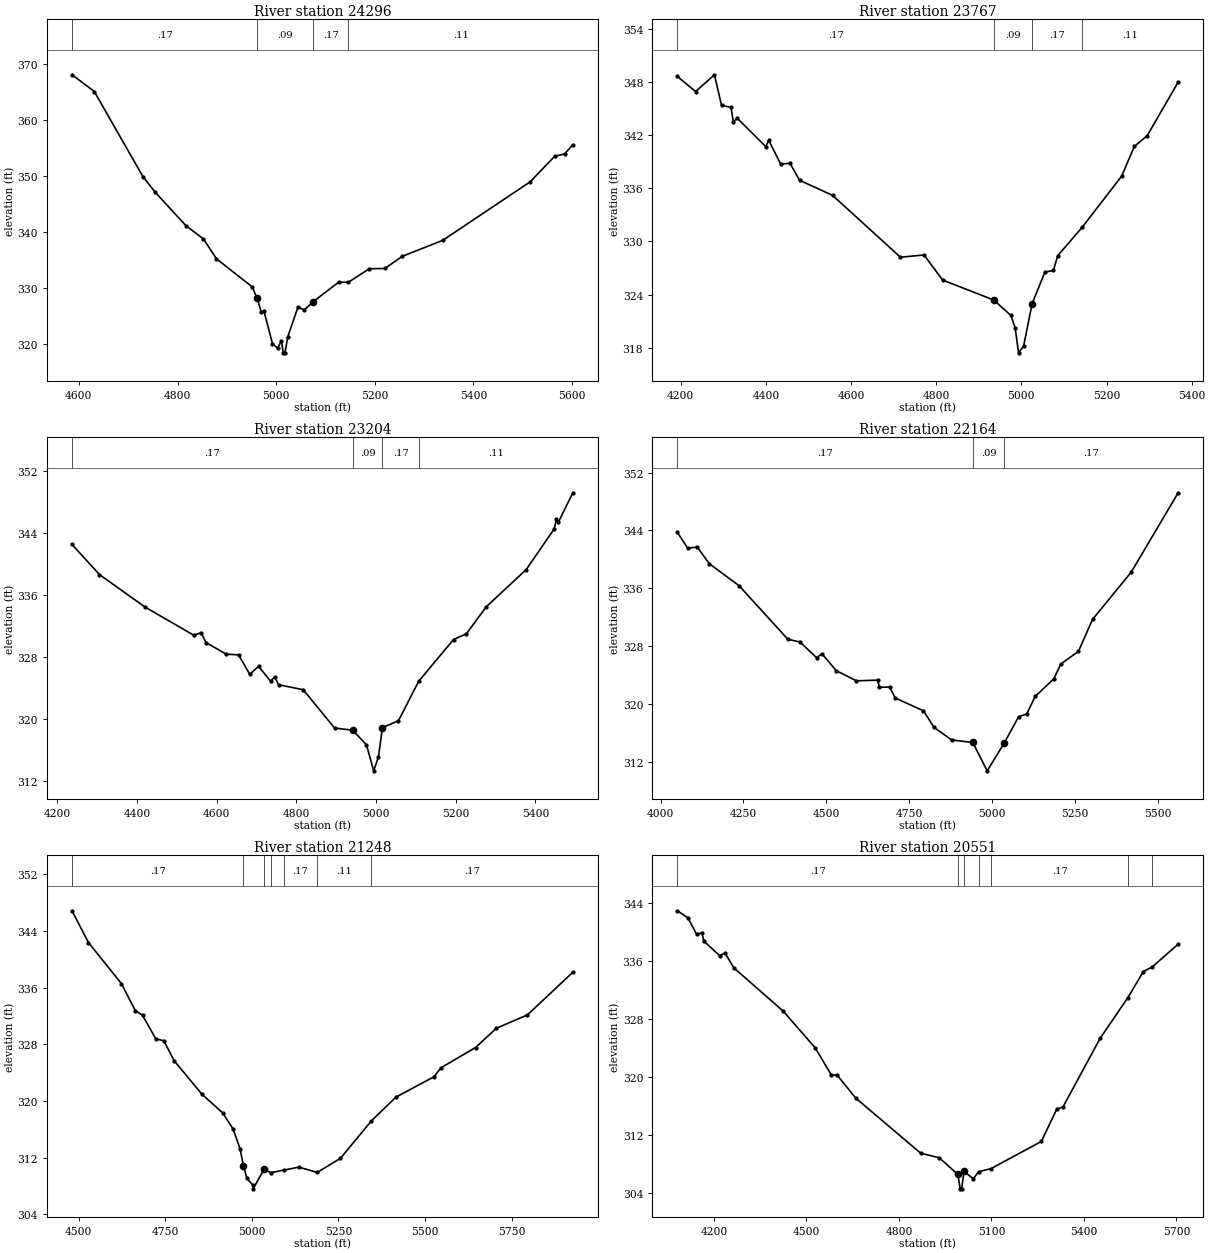
Type RM Length L Ch R = 1 ,24296   ,529,529,529
BEGIN DESCRIPTION:
GUM BRANCH 3.0
END DESCRIPTION:
XS GIS Cut Line= 3
      3738587.08     10236704.89      3738782.38     10235939.95
      3738771.56     10235714.39
#Sta/Elev= 30
  4586.1  368.16  4631.3  365.17    4730  349.93  4755.2  347.12  4817.1  341.18
  4852.6  338.81    4879  335.26  4951.3  330.25  4961.6  328.17    4970  325.67
  4975.2  325.91  4992.5   320.1  5002.9  319.29  5010.8  320.62  5014.3  318.45
  5017.8  318.45  5023.5  321.31  5044.2  326.63  5056.9  326.12  5075.1   327.6
  5126.7  331.08  5146.6  331.07  5188.6  333.48  5220.3  333.53    5256  335.72
  5337.7  338.56  5514.6     349  5564.7  353.59  5584.7     354  5601.4  355.65
#Mann= 4 ,-1 , 0
  4586.1     .17       0  4961.6     .09       0  5075.1     .17       0
  5146.6     .11       0
Bank Sta=4961.6,5075.1
XS Rating Curve= 0 ,0
Exp/Cntr=0.3,0.1

Type RM Length L Ch R = 1 ,23767   ,563,563,563
BEGIN DESCRIPTION:
Mapping XS 18239812
END DESCRIPTION:
XS GIS Cut Line= 3
      3738904.19     10236885.84      3739144.36     10236418.51
      3739126.52     10235768.29
#Sta/Elev= 30
  4192.3  348.61  4235.1  346.91  4279.4   348.8    4296  345.35  4318.2  345.13
  4323.8  343.46  4332.6  343.91    4400  340.69  4406.9  341.41  4434.7  338.74
  4456.9  338.81  4479.1   336.9  4556.6   335.2  4716.1  328.22  4771.5  328.47
  4815.2  325.64  4935.3  323.39  4975.3  321.65  4985.3  320.28  4993.5  317.43
  5005.3  318.19  5025.3  322.98  5055.3  326.54  5075.3  326.73  5085.3  328.38
  5143.1  331.61  5235.4  337.36  5265.4  340.72  5295.4  341.92  5368.2  347.97
#Mann= 4 ,-1 , 0
  4192.3     .17       0  4935.3     .09       0  5025.3     .17       0
  5143.1     .11       0
Bank Sta=4935.3,5025.3
XS Rating Curve= 0 ,0
Exp/Cntr=0.3,0.1

Type RM Length L Ch R = 1 ,23204   ,1040,1040,1040
BEGIN DESCRIPTION:
Mapping XS 09ad70d0
END DESCRIPTION:
XS GIS Cut Line= 3
      3739676.91     10237041.04       3739591.7     10236614.98
      3739656.04      10235794.6
#Sta/Elev= 30
  4236.7  342.46  4305.7  338.57  4420.2  334.38  4542.6  330.74  4560.6  331.08
  4573.2   329.8  4624.2   328.3  4654.8  328.22    4683   325.7  4705.2  326.74
  4735.3   324.8  4745.3  325.37  4755.4  324.36  4817.2  323.72  4895.8  318.78
  4941.3  318.49    4976  316.61  4994.2  313.25  5006.1  315.05  5016.2  318.83
  5056.3  319.71  5106.9  324.79  5194.6  330.19  5226.8  330.93    5277  334.43
  5377.3  339.23  5447.5  344.48  5452.9  345.72  5457.9  345.33  5494.1  349.13
#Mann= 4 ,-1 , 0
  4236.7     .17       0  4941.3     .09       0  5016.2     .17       0
  5106.9     .11       0
Bank Sta=4941.3,5016.2
XS Rating Curve= 0 ,0
Exp/Cntr=0.3,0.1

Type RM Length L Ch R = 1 ,22164   ,916,916,916
BEGIN DESCRIPTION:
Mapping XS 8539e488
END DESCRIPTION:
XS GIS Cut Line= 3
      3740097.52      10237053.4      3740352.12     10236601.09
      3740688.04     10235667.96
#Sta/Elev= 30
  4050.9  343.72  4082.2  341.55    4111  341.69  4147.2   339.4  4237.2  336.35
  4384.3  328.95  4420.8  328.58    4471   326.4  4486.9  326.96  4530.2  324.62
  4591.2  323.21    4655  323.31  4660.5  322.31  4691.2  322.36  4708.1  320.84
  4793.2  319.07    4825  316.79  4878.2  315.04    4942  314.69  4985.6  310.77
  5037.6  314.66  5080.1  318.23  5105.1  318.65  5130.5  321.06  5186.4  323.48
  5207.7  325.53  5260.8  327.28  5303.3  331.69  5420.2  338.24  5561.7   349.2
#Mann= 3 , 0 , 0
  4050.9     .17       0    4942     .09       0  5037.6     .17       0
Bank Sta=4942,5037.6
XS Rating Curve= 0 ,0
Exp/Cntr=0.3,0.1

Type RM Length L Ch R = 1 ,21248   ,697,697,697
BEGIN DESCRIPTION:
Mapping XS 08288919
END DESCRIPTION:
XS GIS Cut Line= 3
      3741301.02     10237036.84      3741234.06     10236802.48
      3741202.67     10235600.23
#Sta/Elev= 30
  4480.6  346.83  4528.2  342.34  4623.3  336.55  4663.4  332.73  4684.2  332.08
  4722.5  328.76  4745.8  328.48  4775.8  325.65  4855.8  320.94  4915.8   318.3
  4945.8  316.03  4965.8  313.26  4975.8  310.86  4985.8  309.04  5003.4  308.08
  5003.7  307.58  5035.9   310.4  5054.2  309.85  5091.8  310.22  5135.9  310.64
  5189.1   309.9  5255.9  311.89    5345  317.16    5416  320.52    5526   323.4
    5546  324.66  5646.1  327.53  5706.1  330.24  5796.1  332.14    5927  338.15
#Mann= 7 ,-1 , 0
  4480.6     .17       0  4975.8     .09       0  5035.9     .17       0
  5054.2     .11       0  5091.8     .17       0  5189.1     .11       0
    5345     .17       0
Bank Sta=4975.8,5035.9
XS Rating Curve= 0 ,0
Exp/Cntr=0.3,0.1

Type RM Length L Ch R = 1 ,20551   ,1620,1620,1620
BEGIN DESCRIPTION:
Mapping XS 1370336e
END DESCRIPTION:
XS GIS Cut Line= 3
       3741577.8     10237194.85      3741782.67     10236746.92
        3741866.     10235618.45
#Sta/Elev= 30
  4081.4  342.93  4115.3  341.97  4143.8  339.69  4161.4  339.89  4166.8  338.76
  4218.4  336.73  4235.9   337.1  4264.4  335.05  4425.5  329.04  4528.6  323.99
  4580.6  320.26  4599.9  320.22    4660  317.05  4870.6  309.45  4930.8  308.82
  4990.9  306.52  4998.7  304.53  5003.2  304.53    5011  306.94  5041.1  305.92
  5058.1  306.89    5099  307.33  5261.7  311.07  5311.8  315.54  5331.9  315.83
  5452.2   325.3  5542.4  330.93  5592.6  334.54  5621.3  335.17  5705.5  338.32
#Mann= 7 ,-1 , 0
  4081.4     .17       0  4990.9     .09       0    5011     .17       0
  5058.1     .15       0    5099     .17       0  5542.4     .11       0
  5621.3     .17       0
Bank Sta=4990.9,5011
XS Rating Curve= 0 ,0
Exp/Cntr=0.3,0.1

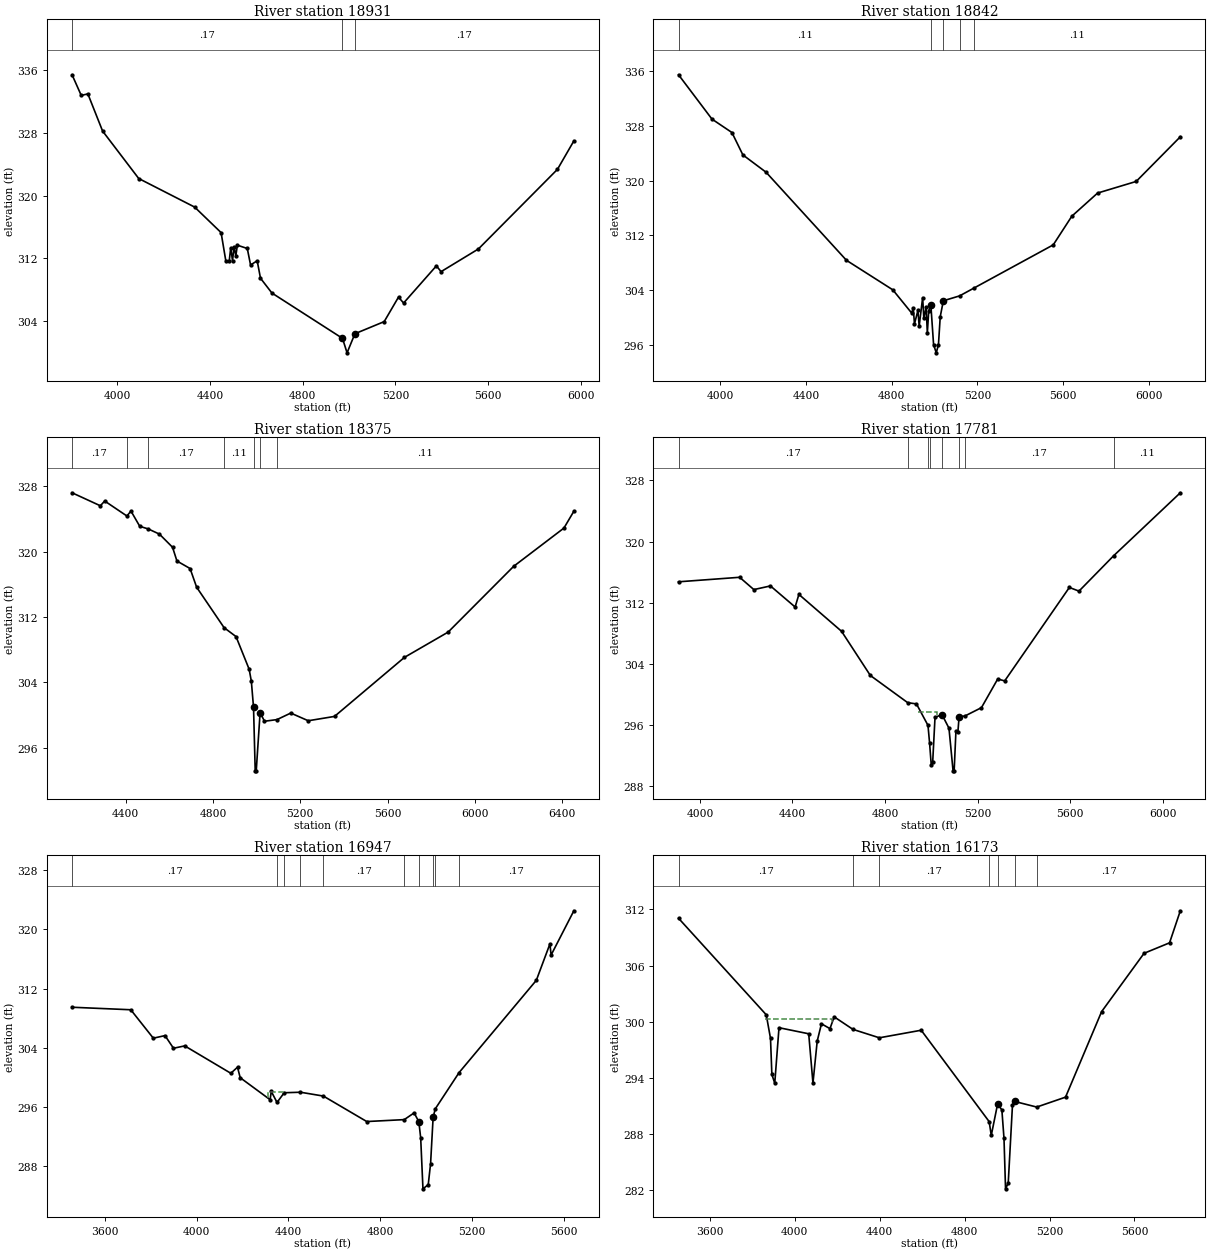
Type RM Length L Ch R = 1 ,18931   ,89,89,89
BEGIN DESCRIPTION:
Mapping XS a27b7f12
END DESCRIPTION:
XS GIS Cut Line= 5
      3742008.36     10237597.62      3742710.46     10236786.37
       3742860.5     10236455.21       3742906.8     10236063.69
      3742889.44     10235730.34
#Sta/Elev= 30
  3805.1  335.44  3844.7   332.8  3873.2     333  3936.8  328.25  4092.6  322.19
  4333.8  318.54  4447.9  315.28  4468.7   311.6    4483  311.65  4489.6  313.35
  4497.2  311.69  4503.8  313.45  4511.5  312.32  4518.1  313.67  4560.9  313.25
  4575.1  311.14  4603.6  311.68  4617.9  309.45  4667.2  307.56  4971.6  301.77
  4991.3  299.92  5025.1  302.36  5151.5  303.91  5213.2  307.04  5235.1  306.28
  5376.6  311.03  5396.8  310.29  5557.9  313.19  5898.8  323.36  5969.6  326.99
#Mann= 3 , 0 , 0
  3805.1     .17       0  4971.6     .09       0  5025.1     .17       0
Bank Sta=4971.6,5025.1
XS Rating Curve= 0 ,0
Exp/Cntr=0.3,0.1

Type RM Length L Ch R = 1 ,18842   ,467,467,467
BEGIN DESCRIPTION:
Mapping XS f580e2e7
END DESCRIPTION:
XS GIS Cut Line= 5
      3742185.44     10237694.86      3742769.94     10236825.57
       3742902.4     10236579.56      3743004.02      10236299.8
      3742997.09     10235585.31
#Sta/Elev= 30
  3806.6  335.48  3962.5     329  4055.5  327.04  4106.5  323.77  4214.5  321.24
  4589.5  308.36  4805.4  304.05  4893.3  300.66  4900.7  301.41  4906.4  299.07
  4922.6  301.05  4928.3  298.74  4944.5  302.91  4950.2  299.87  4960.8  301.54
  4966.4  297.74  4972.8  300.96  4982.7  301.87  4995.5  296.04  5007.9  294.84
  5018.2  296.03  5026.5  300.12    5041  302.45  5116.5  303.16  5182.7  304.29
  5553.3  310.62  5639.9  314.81  5759.9  318.19  5939.9  319.89  6145.7  326.42
#Mann= 5 ,-1 , 0
  3806.6     .11       0  4982.7     .07       0    5041     .11       0
  5116.5     .17       0  5182.7     .11       0
Bank Sta=4982.7,5041
XS Rating Curve= 0 ,0
Exp/Cntr=0.3,0.1

Type RM Length L Ch R = 1 ,18375   ,594,594,594
BEGIN DESCRIPTION:
Mapping XS f8637c2d
END DESCRIPTION:
XS GIS Cut Line= 3
      3743014.44     10237810.24      3743118.61       10236463.
      3743076.96     10235515.58
#Sta/Elev= 30
  4154.1  327.19  4283.7   325.6  4303.7  326.18  4405.3  324.35  4424.1  324.95
  4464.2  323.09  4503.6  322.76  4554.5  322.13  4614.6  320.52  4634.7  318.84
  4694.9  317.92    4725  315.63  4850.8  310.68  4905.5  309.59  4965.7  305.59
  4975.7  304.12  4985.7  300.92  4993.4  293.16  4998.1  293.16  5015.8  300.29
  5035.9  299.23  5093.1  299.43  5156.3  300.23  5236.5  299.29  5356.8  299.82
  5677.5  307.05  5877.6  310.14  6177.9  318.19  6408.2  322.87  6453.7  324.93
#Mann= 7 ,-1 , 0
  4154.1     .17       0  4405.3     .11       0  4503.6     .17       0
  4850.8     .11       0  4985.7     .09       0  5015.8     .11       0
  5093.1     .11       0
Bank Sta=4985.7,5015.8
XS Rating Curve= 0 ,0
Exp/Cntr=0.3,0.1

Type RM Length L Ch R = 1 ,17781   ,834,834,834
BEGIN DESCRIPTION:
Mapping XS da995a22
END DESCRIPTION:
XS GIS Cut Line= 3
      3743413.74     10237858.85       3743594.3     10237046.33
      3743483.32     10235714.58
#Sta/Elev= 30
  3907.6  314.73  4171.7  315.32  4233.1  313.71  4304.8  314.19  4411.5  311.43
  4427.8  313.08  4612.2  308.25  4736.6  302.47  4898.1  298.91  4935.9  298.75
  4985.7  295.94  4992.6  293.64  4999.7  290.79  5006.1  291.17  5016.1  296.99
  5046.3  297.35  5076.4  295.57  5094.1  289.99  5098.8  289.99  5106.5  295.21
  5115.1  295.11  5120.1  297.06  5145.5  297.17  5216.8  298.26  5287.1  302.01
  5317.2  301.76  5596.7  313.99  5638.3  313.51  5788.2  318.14  6076.3  326.38
#Mann= 8 ,-1 , 0
  3907.6     .17       0  4898.1     .15       0  4985.7     .17       0
  4992.6     .15       0  5046.3     .09       0  5120.1     .15       0
  5145.5     .17       0  5788.2     .11       0
#XS Ineff= 1 ,-1
    4943  5026.2  297.73
Permanent Ineff=
       F
Bank Sta=5046.3,5120.1
XS Rating Curve= 0 ,0
Exp/Cntr=0.3,0.1

Type RM Length L Ch R = 1 ,16947   ,774,774,774
BEGIN DESCRIPTION:
Mapping XS 87b21622
END DESCRIPTION:
XS GIS Cut Line= 2
      3743848.46     10238276.57      3744314.45     10236141.43
#Sta/Elev= 30
    3458  309.49  3713.7  309.15  3811.8  305.31  3862.8  305.66  3899.7  303.95
  3948.7  304.27  4149.4  300.57  4178.5  301.39  4190.3  299.97  4320.5     297
  4325.6  298.12  4350.6  296.63  4381.9  297.94  4452.8  298.01  4552.6  297.49
  4741.4  294.05  4904.7  294.31  4947.8  295.22  4968.2  294.03  4976.3  291.85
  4986.2  284.96  5009.2  285.53  5019.4  288.37  5030.5  294.63  5039.9  295.77
  5143.7  300.67    5480  313.13  5539.2  318.05  5544.3  316.54  5643.4  322.52
#Mann= 10 ,-1 , 0
    3458     .17       0  4350.6     .11       0  4381.9     .17       0
  4452.8     .11       0  4552.6     .17       0  4904.7     .15       0
  4968.2     .09       0  5030.5     .12       0  5039.9     .15       0
  5143.7     .17       0
#XS Ineff= 1 ,-1
    4310  4384.8  298.04
Permanent Ineff=
       F
Bank Sta=4968.2,5030.5
XS Rating Curve= 0 ,0
Exp/Cntr=0.3,0.1

Type RM Length L Ch R = 1 ,16173   ,942,942,942
BEGIN DESCRIPTION:
Mapping XS 76786d4d
END DESCRIPTION:
XS GIS Cut Line= 2
      3744795.73     10238574.43      3744833.92     10236210.24
#Sta/Elev= 30
  3451.9  311.06  3865.3  300.73  3885.3   298.2  3891.7  294.35  3905.3  293.41
  3925.3  299.35  4065.3   298.7  4085.3  293.42  4105.3  297.91  4125.3  299.77
  4165.4  299.25  4185.4  300.51  4273.9  299.17  4398.1  298.27  4595.4  299.08
  4915.7   289.3  4925.5  287.83  4955.5   291.2  4975.5  290.55  4985.5  287.51
  4992.8  282.11  5005.5  282.74  5025.5  291.08  5035.5  291.46  5139.7  290.86
  5275.5  291.92  5445.5  301.07  5645.5  307.31  5765.6  308.43  5816.4  311.86
#Mann= 7 ,-1 , 0
  3451.9     .17       0  4273.9     .11       0  4398.1     .17       0
  4915.7     .15       0  4955.5     .09       0  5035.5     .15       0
  5139.7     .17       0
#XS Ineff= 1 ,-1
    3860  4175.4  300.23
Permanent Ineff=
       F
Bank Sta=4955.5,5035.5
XS Rating Curve= 0 ,0
Exp/Cntr=0.3,0.1

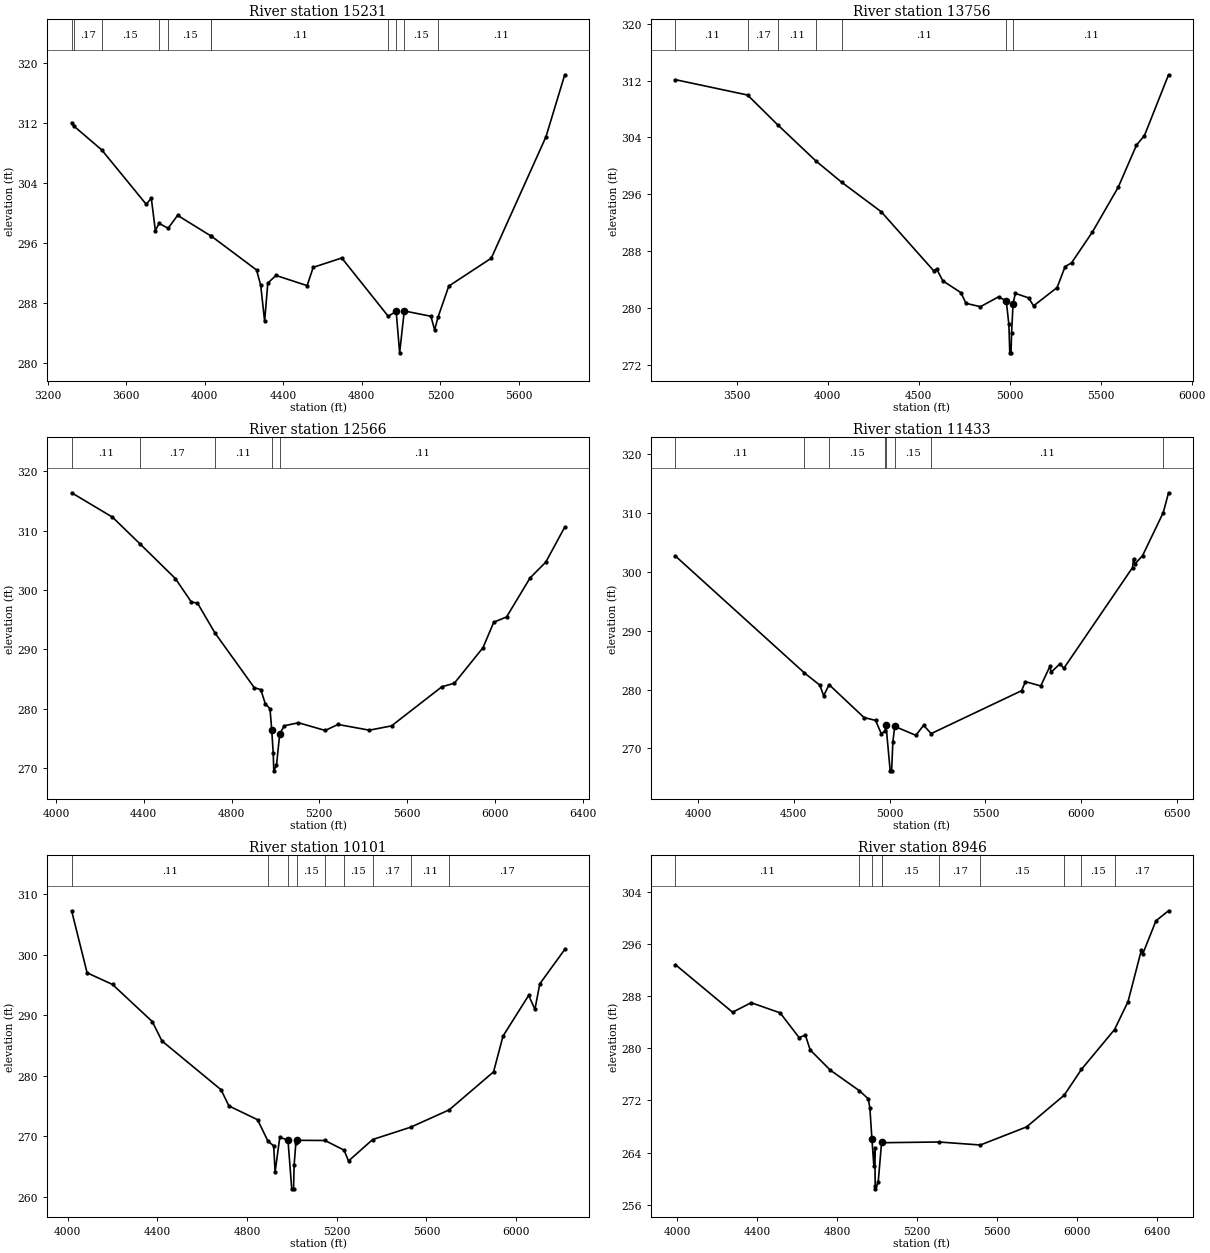
Type RM Length L Ch R = 1 ,15231   ,1475,1475,1475
BEGIN DESCRIPTION:
Mapping XS c5663ee9
END DESCRIPTION:
XS GIS Cut Line= 2
      3745231.11     10238734.83       3745838.4     10236298.07
#Sta/Elev= 30
  3322.2  312.07    3332  311.65  3475.6  308.43  3701.9  301.18    3728  301.97
  3748.6  297.67  3767.7  298.63  3813.6  297.97  3861.9   299.7    4032  296.94
    4034  296.92  4263.9  292.41  4285.1  290.37  4305.1  285.57  4321.2  290.65
  4362.5  291.68  4521.6  290.32  4552.5  292.76    4698  294.01  4934.3  286.24
    4975  286.87  4992.7  281.35  5016.2  286.94  5152.1  286.23  5170.8   284.4
  5188.1  286.11    5243  290.26  5459.4  293.98  5737.7  310.17  5833.5  318.46
#Mann= 11 ,-1 , 0
  3322.2     .11       0    3332     .17       0  3475.6     .15       0
  3767.7     .17       0  3813.6     .15       0    4032     .17       0
    4034     .11       0  4934.3     .15       0    4975     .09       0
  5016.2     .15       0  5188.1     .11       0
#XS Ineff= 1 ,-1
    4160    4698  294.01
Permanent Ineff=
       F
Bank Sta=4975,5016.2
XS Rating Curve= 0 ,0
Exp/Cntr=0.3,0.1

Type RM Length L Ch R = 1 ,13756   ,1190,1190,1190
BEGIN DESCRIPTION:
Mapping XS a1b1749d
END DESCRIPTION:
XS GIS Cut Line= 3
      3745677.96     10238818.92      3746510.62     10237650.15
      3747533.52     10236890.61
#Sta/Elev= 30
  3163.8  312.12  3560.2  309.96  3724.8  305.79    3936  300.67    4077  297.69
  4294.7  293.53  4582.4  285.24  4598.8  285.49  4632.8  283.81  4732.4  282.15
  4760.1  280.65  4839.4  280.17  4939.5  281.57  4981.5  280.97  4995.8  277.67
  5000.8  273.68  5007.7  273.68  5010.5  276.42  5018.8   280.6  5031.3  282.05
  5104.4  281.41  5131.4  280.29  5260.8  282.87  5304.7  285.82  5340.1  286.34
  5454.8  290.69  5596.7  296.99  5696.8  302.91  5740.7  304.26  5872.9  312.81
#Mann= 7 ,-1 , 0
  3163.8     .11       0  3560.2     .17       0  3724.8     .11       0
    3936     .17       0    4077     .11       0  4981.5     .06       0
  5018.8     .11       0
Bank Sta=4981.5,5018.8
XS Rating Curve= 0 ,0
Exp/Cntr=0.3,0.1

Type RM Length L Ch R = 1 ,12566   ,1133,1133,1133
BEGIN DESCRIPTION:
Mapping XS 08ff591d
END DESCRIPTION:
XS GIS Cut Line= 2
      3746766.55     10239028.93      3748052.59     10237185.74
#Sta/Elev= 30
  4071.2  316.35  4257.3  312.25  4382.1  307.78  4544.1  301.92  4617.3  297.95
  4644.6  297.81  4724.5  292.77  4903.7  283.57  4933.4  283.24  4954.3  280.82
  4975.3  280.04  4983.1  276.51  4990.1   272.5  4992.6  269.58  5004.9  270.49
  5019.7  275.83  5040.7  277.16    5105  277.67    5227  276.37    5285  277.38
    5428  276.42  5529.2  277.14  5758.7  283.72  5815.4  284.31  5946.2   290.3
  5995.2  294.58  6053.5  295.46  6160.8  302.03  6232.4  304.69  6318.7  310.58
#Mann= 5 ,-1 , 0
  4071.2     .11       0  4382.1     .17       0  4724.5     .11       0
  4983.1     .06       0  5019.7     .11       0
Bank Sta=4983.1,5019.7
XS Rating Curve= 0 ,0
Exp/Cntr=0.3,0.1

Type RM Length L Ch R = 1 ,11433   ,1332,1332,1332
BEGIN DESCRIPTION:
Mapping XS 9cb093c5
END DESCRIPTION:
XS GIS Cut Line= 2
      3748126.24     10239712.68      3748305.75     10237146.05
#Sta/Elev= 30
  3882.2  302.72  4554.7  282.85  4635.6  280.76  4655.7  278.95  4683.9  280.84
  4866.2  275.25  4926.4  274.76  4956.4   272.5  4975.9  272.96  4980.9  273.95
  5002.8  266.18  5010.3  266.18  5016.6   271.1  5026.6  273.74  5136.9  272.22
    5177  273.92  5216.9  272.52  5688.2  279.81  5708.3  281.35  5788.5  280.62
  5836.9  284.01  5841.9  282.93  5888.7  284.39  5908.8  283.62  6267.4  300.76
  6272.4  302.24  6279.7  301.36  6319.8   302.8  6427.6  310.11  6455.1  313.48
#Mann= 8 ,-1 , 0
  3882.2     .11       0  4554.7     .17       0  4683.9     .15       0
  4975.9     .12       0  4980.9     .09       0  5026.6     .15       0
  5216.9     .11       0  6427.6     .17       0
Bank Sta=4980.9,5026.6
XS Rating Curve= 0 ,0
Exp/Cntr=0.3,0.1

Type RM Length L Ch R = 1 ,10101   ,1155,1155,1155
BEGIN DESCRIPTION:
Mapping XS ddc6a946
END DESCRIPTION:
XS GIS Cut Line= 2
      3748427.99     10239727.91      3749822.05      10238028.3
#Sta/Elev= 30
  4018.2  307.27  4087.1  297.02  4200.5  295.09  4377.7  288.96  4420.8  285.76
  4684.2   277.7  4719.3  275.02  4847.1  272.74  4893.7  269.17  4918.8  268.44
  4925.3  264.12  4946.1  269.85  4982.7  269.35  4999.4  261.32  5007.6  261.32
    5010  265.23  5017.9  268.95  5024.3  269.34  5147.6  269.31  5232.8  267.71
  5252.5  265.92  5360.2  269.47    5529   271.5  5701.2  274.37  5899.1  280.65
  5941.2  286.56  6055.6  293.29  6083.5  290.98  6105.1  295.19  6216.4  300.88
#Mann= 9 ,-1 , 0
  4018.2     .11       0  4893.7     .17       0  4982.7     .09       0
  5024.3     .15       0  5147.6     .17       0  5232.8     .15       0
  5360.2     .17       0    5529     .11       0  5701.2     .17       0
Bank Sta=4982.7,5024.3
XS Rating Curve= 0 ,0
Exp/Cntr=0.3,0.1

Type RM Length L Ch R = 1 ,8946    ,1292,1292,1292
BEGIN DESCRIPTION:
Mapping XS c1102d4a
END DESCRIPTION:
XS GIS Cut Line= 2
      3749386.65     10240575.87      3750070.05     10238204.99
#Sta/Elev= 30
    3991  292.81    4277  285.52  4369.9  286.98    4515  285.42    4610  281.63
  4641.2  282.02  4665.3  279.74  4766.1  276.64  4911.1   273.5  4955.4  272.27
  4963.9  270.89  4974.3  266.06  4983.8  262.02    4989  264.75  4990.4  258.95
  4990.9  258.45  5005.5  259.43  5022.7   265.6  5026.3  265.52  5309.5  265.63
  5516.9  265.17    5748  267.94  5936.2   272.8  6022.9  276.77  6188.2  282.86
  6255.7  287.14    6323   295.1  6328.3  294.37  6395.6  299.54  6458.4  301.07
#Mann= 10 ,-1 , 0
    3991     .11       0  4911.1     .17       0  4974.3     .09       0
  5022.7     .17       0  5026.3     .15       0  5309.5     .17       0
  5516.9     .15       0  5936.2     .17       0  6022.9     .15       0
  6188.2     .17       0
Bank Sta=4974.3,5022.7
XS Rating Curve= 0 ,0
Exp/Cntr=0.3,0.1

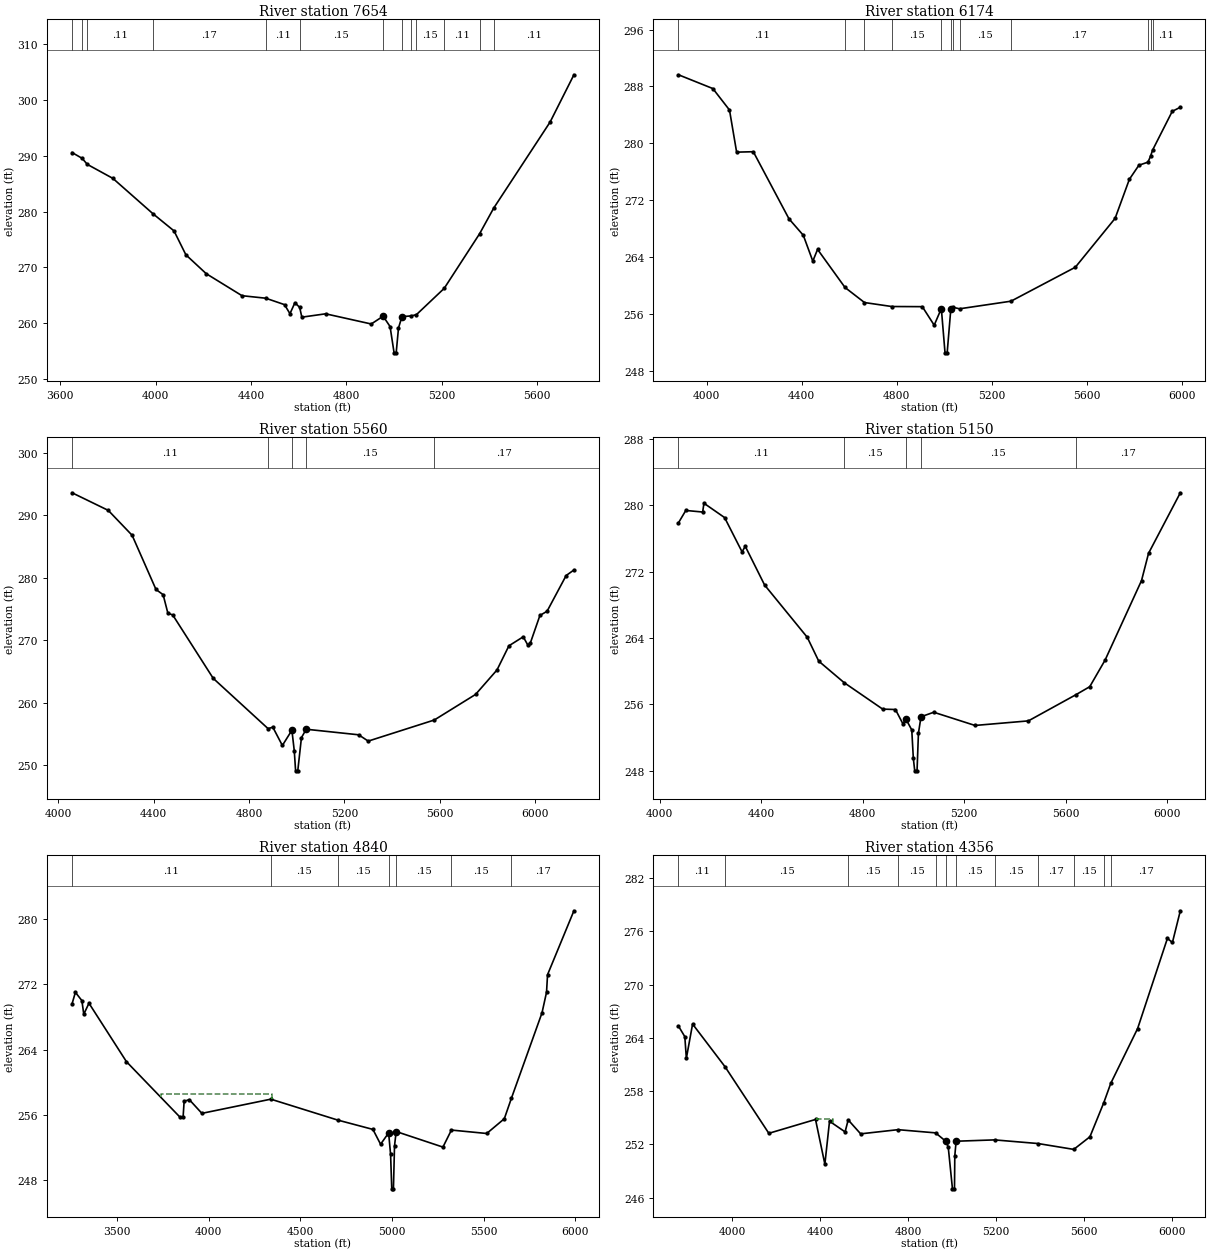
Type RM Length L Ch R = 1 ,7654    ,1480,1480,1480
BEGIN DESCRIPTION:
Mapping XS d2e488a9
END DESCRIPTION:
XS GIS Cut Line= 2
      3749611.98     10240644.62      3751283.28     10239366.34
#Sta/Elev= 30
    3650  290.55  3692.5  289.51  3713.7  288.44  3821.1  285.93  3989.1  279.61
  4077.4  276.54  4127.2  272.26  4212.4  268.89  4362.4  264.95  4462.1   264.5
  4540.7  263.35  4563.5  261.73  4584.3  263.69  4604.3  262.86  4613.3  261.11
  4713.1  261.71  4904.3  259.89  4954.2  261.28  4983.3  259.43  5000.1  254.73
  5008.9  254.73  5018.6  259.17  5033.1  261.21  5070.8  261.33  5093.8  261.56
  5210.2  266.26  5358.5  276.02    5418  280.63  5654.3  296.01  5754.1  304.46
#Mann= 13 ,-1 , 0
    3650     .11       0  3692.5     .17       0  3713.7     .11       0
  3989.1     .17       0  4462.1     .11       0  4604.3     .15       0
  4954.2     .09       0  5033.1     .15       0  5070.8     .17       0
  5093.8     .15       0  5210.2     .11       0  5358.5     .17       0
    5418     .11       0
Bank Sta=4954.2,5033.1
XS Rating Curve= 0 ,0
Exp/Cntr=0.3,0.1

Type RM Length L Ch R = 1 ,6174    ,614,614,614
BEGIN DESCRIPTION:
Mapping XS 9c6f9571
END DESCRIPTION:
XS GIS Cut Line= 2
      3749833.51     10240732.44      3751941.84     10240648.41
#Sta/Elev= 30
  3881.8  289.64  4026.3   287.7  4096.3  284.68  4126.3  278.75  4196.4  278.81
  4346.5  269.36  4406.6  267.05  4446.6  263.41  4466.6  265.06    4582   259.7
  4663.9  257.58  4778.6  257.02    4907     257    4957  254.39    4987  256.74
  5002.5   250.5  5011.5   250.5    5027  256.73  5037.1   256.9  5063.7   256.7
  5279.8  257.77  5550.4  262.55  5717.6  269.43  5777.6  274.93  5817.7  276.91
  5855.7  277.34  5866.5  278.17  5875.2  279.04  5957.8  284.49  5991.8  285.07
#Mann= 12 ,-1 , 0
  3881.8     .11       0    4582     .17       0  4663.9     .11       0
  4778.6     .15       0    4987     .09       0    5027     .12       0
  5037.1     .17       0  5063.7     .15       0  5279.8     .17       0
  5855.7     .11       0  5866.5     .17       0  5875.2     .11       0
Bank Sta=4987,5027
XS Rating Curve= 0 ,0
Exp/Cntr=0.3,0.1

Type RM Length L Ch R = 1 ,5560    ,410,410,410
BEGIN DESCRIPTION:
Mapping XS 1e0e3fc8
END DESCRIPTION:
XS GIS Cut Line= 2
      3750036.01     10241087.65      3752140.44     10241114.38
#Sta/Elev= 30
  4058.1   293.6    4210  290.78    4310  286.79    4410  278.12    4440  277.28
    4460   274.3    4480  274.05    4650  263.89    4880  255.84    4900  256.07
    4940  253.14    4980  255.58    4990  252.27  4995.5  249.08  5004.6  249.08
    5020  254.39    5040  255.74    5260  254.85    5300  253.84  5577.2  257.22
  5750.1  261.31  5840.1  265.23  5890.1   269.1  5950.1  270.54  5970.1  269.17
  5980.1  269.56  6020.1  273.96  6050.1  274.63  6130.1  280.35  6162.7  281.24
#Mann= 5 ,-1 , 0
  4058.1     .11       0    4880     .15       0    4980     .09       0
    5040     .15       0  5577.2     .17       0
Bank Sta=4980,5040
XS Rating Curve= 0 ,0
Exp/Cntr=0.3,0.1

Type RM Length L Ch R = 1 ,5150    ,310,310,310
BEGIN DESCRIPTION:
Mapping XS 54cf1652
END DESCRIPTION:
XS GIS Cut Line= 2
      3750139.13     10241507.78      3752102.24     10241267.17
#Sta/Elev= 30
  4073.7  277.87  4102.6  279.36    4169  279.17  4174.1  280.23  4255.5   278.5
  4324.3  274.37  4336.9  275.04  4413.2  270.37  4581.1  264.08  4626.5   261.2
  4726.1  258.62  4878.4  255.42  4928.8  255.37    4959   253.6  4969.1  254.27
  4993.1  252.91  4999.3  249.48  5004.8  247.98  5013.9  247.98  5019.4  252.51
  5029.5   254.5  5079.9  255.04  5242.3  253.45  5452.7     254  5639.2  257.14
  5694.5  258.12  5754.9  261.32  5898.6  270.91  5926.2  274.19  6051.5  281.49
#Mann= 5 ,-1 , 0
  4073.7     .11       0  4726.1     .15       0  4969.1     .09       0
  5029.5     .15       0  5639.2     .17       0
Bank Sta=4969.1,5029.5
XS Rating Curve= 0 ,0
Exp/Cntr=0.3,0.1

Type RM Length L Ch R = 1 ,4840    ,484,484,484
BEGIN DESCRIPTION:
Mapping XS 9c83f2a5
END DESCRIPTION:
XS GIS Cut Line= 3
       3750123.8     10242909.56      3750605.06     10241882.09
      3752102.27       10241313.
#Sta/Elev= 30
  3255.2  269.63  3273.3  271.04  3308.7  270.02    3319  268.35  3347.3   269.7
  3551.7  262.53  3843.3  255.73  3860.6  255.75  3866.2  257.67  3894.5  257.87
    3963  256.19  4338.9  257.93    4703  255.37  4895.6  254.22  4937.3   252.4
  4981.2  253.79  4991.9  251.15  4998.3  246.93  5007.4  246.93  5013.3  252.19
  5022.3  253.96  5277.3  252.05  5323.5  254.14  5516.1  253.72    5612  255.53
  5650.8  258.05  5817.5  268.52  5842.2  271.05  5847.7   273.2  5991.5  281.04
#Mann= 7 ,-1 , 0
  3255.2     .11       0  4338.9     .15       0    4703     .15       0
  4981.2     .09       0  5022.3     .15       0  5323.5     .15       0
  5650.8     .17       0
#XS Ineff= 1 ,-1
    3740  4346.7  258.53
Permanent Ineff=
       F
Bank Sta=4981.2,5022.3
XS Rating Curve= 0 ,0
Exp/Cntr=0.3,0.1

Type RM Length L Ch R = 1 ,4356    ,2103,2103,2103
BEGIN DESCRIPTION:
Mapping XS aec5a453
END DESCRIPTION:
XS GIS Cut Line= 3
      3750402.67     10242886.57      3751166.52     10242122.72
      3752167.82     10241461.09
#Sta/Elev= 30
  3756.3  265.32  3785.1  264.13  3792.1  261.69  3820.4  265.55    3968  260.74
  4166.9  253.25    4379  254.81  4421.5  249.78  4442.7  254.61  4513.4  253.41
  4527.5  254.76  4584.1  253.19  4753.8  253.66  4924.6   253.3  4969.8  252.38
    4982  251.72  5001.3     247  5010.5     247  5011.9  250.71  5017.9  252.36
  5192.5  252.51  5390.1   252.1  5552.5  251.44  5625.9  252.86  5688.8  256.69
  5720.9  258.89  5842.6  265.04    5978  275.19  6000.8  274.73  6036.7   278.3
#Mann= 12 ,-1 , 0
  3756.3     .11       0    3968     .15       0  4527.5     .15       0
  4753.8     .15       0  4924.6     .15       0  4969.8     .08       0
  5017.9     .15       0  5192.5     .15       0  5390.1     .17       0
  5552.5     .15       0  5688.8     .11       0  5720.9     .17       0
#XS Ineff= 1 ,-1
    4379  4456.8  254.81
Permanent Ineff=
       T
Bank Sta=4969.8,5017.9
XS Rating Curve= 0 ,0
Exp/Cntr=0.3,0.1

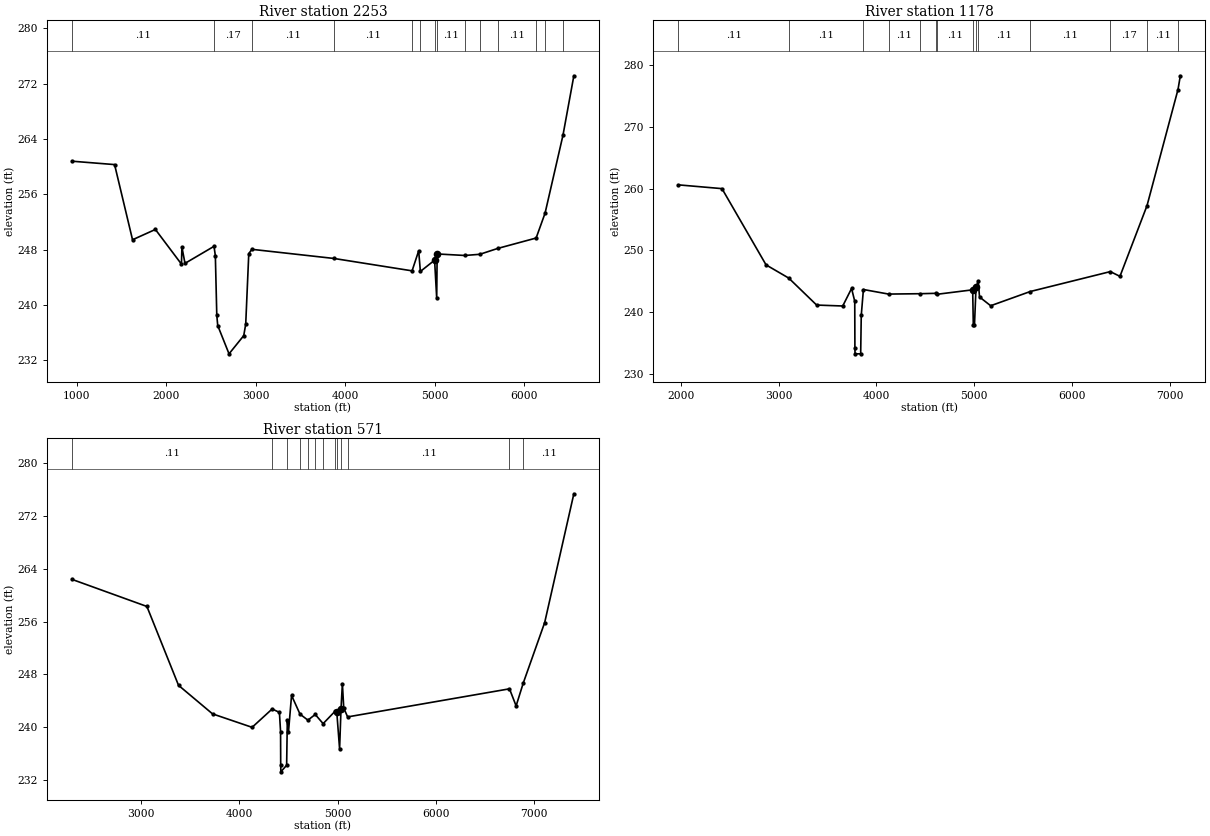
Type RM Length L Ch R = 1 ,2253    ,1075,1075,1075
BEGIN DESCRIPTION:
Mapping XS 868e7941
END DESCRIPTION:
XS GIS Cut Line= 6
      3756173.12     10244356.92      3755074.16     10243940.25
      3752678.33     10243273.59      3752516.87     10243138.17
      3752032.49     10242086.09      3752157.23      10241524.8
#Sta/Elev= 30
   945.8  260.79    1422   260.3  1622.5  249.44  1877.8  250.93    2169  245.92
  2174.2  248.37  2208.4  246.03  2532.5  248.49  2547.5  247.15  2563.6  238.54
    2574  237.05  2700.3  232.96  2864.6  235.59  2886.7  237.24  2920.9  247.43
  2955.1  248.06  3871.5  246.74  4744.9  244.95  4818.7  247.84  4837.5  244.86
  4996.4  246.49    5020     241  5024.9  247.39  5334.4  247.17  5501.6  247.34
    5702  248.19  6130.5  249.69  6230.3  253.28  6429.9  264.51  6551.9  273.13
#Mann= 14 ,-1 , 0
   945.8     .11       0  2532.5     .17       0  2955.1     .11       0
  3871.5     .11       0  4744.9     .11       0  4837.5     .11       0
  4996.4     .06       0  5024.9     .11       0  5334.4     .11       0
  5501.6     .17       0    5702     .11       0  6130.5     .17       0
  6230.3     .11       0  6429.9     .17       0
Bank Sta=4996.4,5024.9
XS Rating Curve= 0 ,0
Exp/Cntr=0.3,0.1

Type RM Length L Ch R = 1 ,1178    ,607,607,607
BEGIN DESCRIPTION:
GUM BRANCH 2.0
END DESCRIPTION:
XS GIS Cut Line= 4
      3756246.02     10244304.83      3753772.08     10243289.21
      3752735.62     10242377.75      3752167.84     10241461.06
#Sta/Elev= 30
  1975.1  260.63  2420.6  260.02  2871.4  247.67  3103.4  245.53  3388.8  241.16
  3655.6  241.01  3745.9  243.85  3778.4  241.77    3780  234.26  3781.5  233.26
    3839  233.26    3845  239.48  3866.9  243.68  4124.3  242.94  4445.1     243
  4605.2  243.06  4621.5  242.91  4984.3  243.63  4990.9     238    5003     238
  5018.8 244.066  5041.2  245.07  5054.5  242.47  5168.4  241.05  5572.5  243.35
    6392  246.58  6490.5  245.81  6767.4  257.27  7084.1  276.07  7107.9   278.3
#Mann= 14 ,-1 , 0
  1975.1     .11       0  3103.4     .11       0  3866.9     .15       0
  4124.3     .11       0  4445.1     .11       0  4605.2     .11       0
  4621.5     .11       0  4984.3     .06       0  5018.8     .11       0
  5041.2     .11       0  5572.5     .11       0    6392     .17       0
  6767.4     .11       0  7084.1     .17       0
Bank Sta=4984.3,5018.8
XS Rating Curve= 0 ,0
Exp/Cntr=0.3,0.1

Type RM Length L Ch R = 1 ,571     ,0,0,0
BEGIN DESCRIPTION:
GUM BRANCH 1.0
END DESCRIPTION:
XS GIS Cut Line= 4
      3756511.68     10244304.84      3755751.24     10244007.96
      3754115.39      10243063.2      3752317.85     10241461.07
#Sta/Elev= 30
  2294.6  262.42  3058.3  258.31  3380.4  246.35  3726.9  242.02  4129.9  239.98
  4334.1  242.76  4408.2  242.25    4420   239.3  4421.3  234.23  4422.8  233.23
  4481.8  234.23  4488.8  241.05  4500.6  239.29  4531.9  244.82  4618.1  241.98
  4698.5  241.07  4773.1  241.93  4853.6  240.54  4977.1  242.45  4992.8  242.27
  5021.3   236.7  5035.5  242.69  5049.7   246.6  5063.7  242.91    5103  241.56
  6752.1  245.82  6819.7  243.23  6892.1  246.68  7110.7  255.87  7407.9   275.4
#Mann= 13 ,-1 , 0
  2294.6     .11       0  4334.1     .12       0  4481.8     .11       0
  4618.1     .11       0  4698.5     .11       0  4773.1     .11       0
  4853.6     .11       0  4977.1     .11       0  4992.8     .06       0
  5035.5     .11       0    5103     .11       0  6752.1     .17       0
  6892.1     .11       0
Bank Sta=4992.8,5035.5
XS Rating Curve= 0 ,0
Exp/Cntr=0.3,0.1

Chan Stop Cuts=-1
Use User Specified Reach Order=0
Composite Channel Slope=5