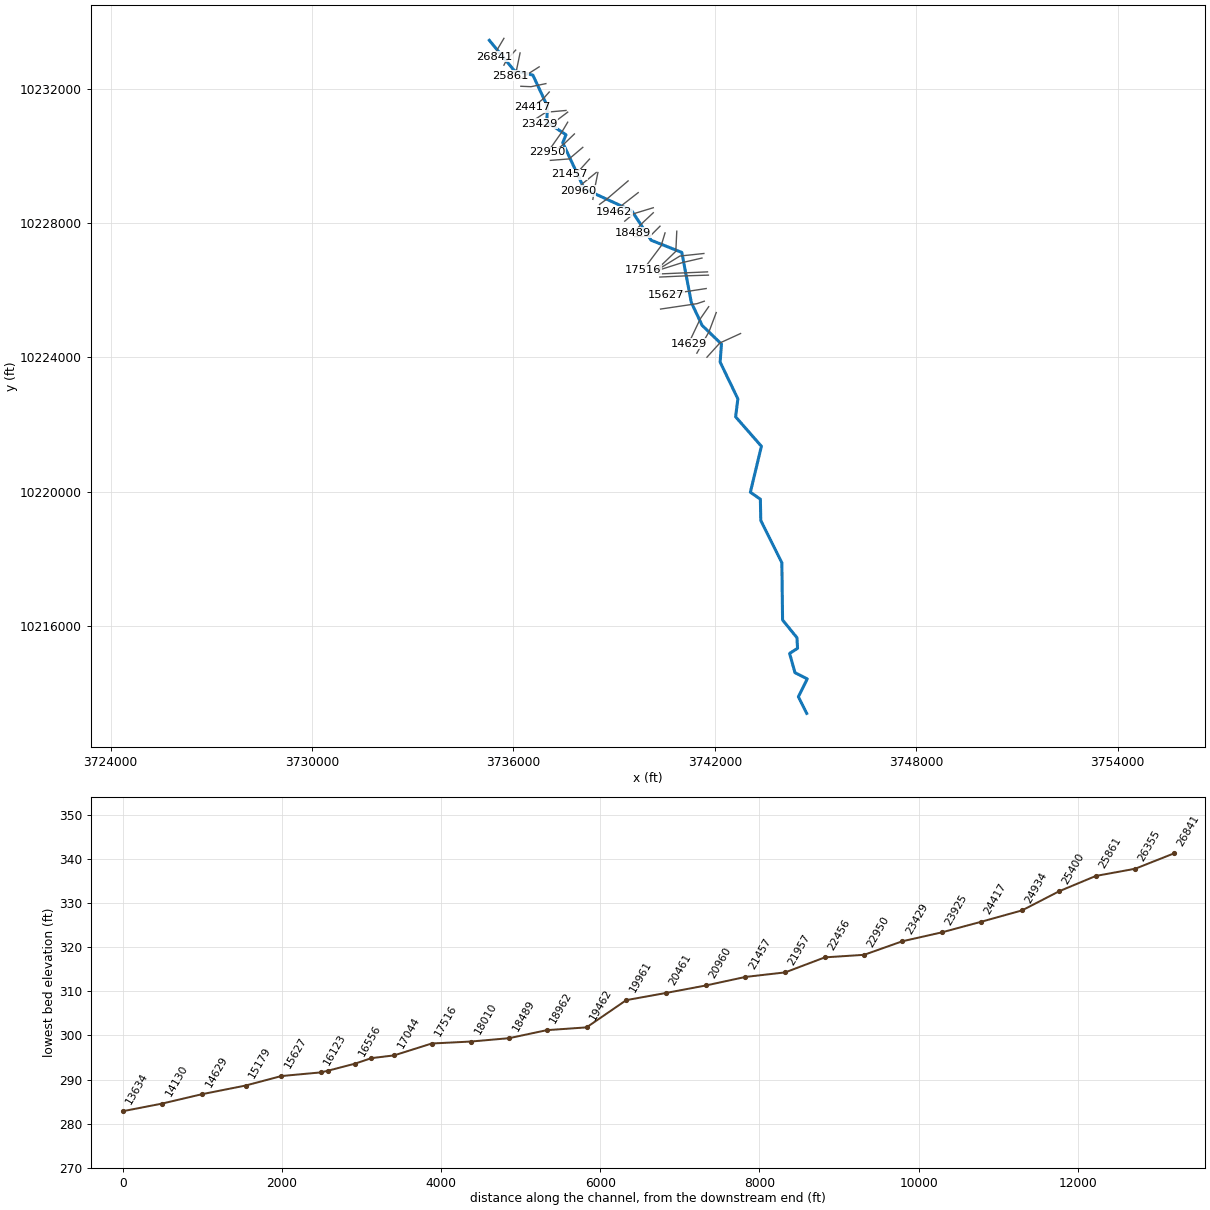
--- LEE BRANCH.prj (project) ---

Proj Title=LEE BRANCH Base Level Engineering
Current Plan=p01
Default Exp/Contr=0.3,0.1
English Units
Geom File=g01
Flow File=f01
Plan File=p01
Y Axis Title=Elevation
X Axis Title(PF)=Main Channel Distance
X Axis Title(XS)=Station
BEGIN DESCRIPTION:
LEE BRANCH
END DESCRIPTION:
DSS Export Rating Curves= 0
DSS Export Rating Curve Sorted= 0
DSS Export Volume Flow Curves= 0
DXF OffsetX= 0
DXF OffsetY= 0
DXF ScaleX= 1
DXF ScaleY= 10

--- LEE BRANCH.p01 (plan) ---

Plan Title=Multiple Run
Program Version=4.10
Short Identifier=Multiple
Geom File=g01
Flow File=f01
Subcritical Flow
K Sum by GR= 0
Std Step Tol= 0.01
Critical Tol= 0.01
Num of Std Step Trials= 20
Max Error Tol= 0.3
Flow Tol Ratio= 0.001
Split Flow NTrial= 30
Split Flow Tol= 0.02
Split Flow Ratio= 0.02
Log Output Level= 0
Friction Slope Method= 1
Unsteady Friction Slope Method= 2
Unsteady Bridges Friction Slope Method= 1
Parabolic Critical Depth
Global Vel Dist= 1 , 1 , 1
Global Log Level= 0
CheckData=True
Encroach Param=-1 ,0,0, 0
BEGIN DESCRIPTION:
Multiple Run
END DESCRIPTION:
Computation Interval=1HOUR
Output Interval=1HOUR
Run HTab= 0
Run UNet= 0
Run PostProcess= 0
Run WQNet= 0
UNET Theta= 1
UNET Theta Warmup= 1
UNET ZTol= 0.02
UNET ZSATol= 0.05
UNET MxIter= 20
UNET MaxInSteps= 0
UNET DtIC= 0
UNET DtMin= 0
UNET MaxCRTS= 20
UNET WFStab= 2
UNET SFStab= 1
UNET WFX= 1
UNET SFX= 1
UNET DSS MLevel= 4
UNET DZMax Abort= 100
UNET Convert EG Bridges= 0
UNET Use Existing IB Tables=-1
UNET Froude Reduction=False
UNET Froude Limit= 1
UNET Froude Power= 10
UNET Time Slicing=0,0, 5
UNET Junction Losses=0
Instantaneous Interval=1HOUR
Write IC File= 0
Write IC File at Sim End=0
Echo Input=False
Echo Parameters=False
Echo Output=False
Write Detailed= 0
WQ AD Non Conservative
WQ ULTIMATE=-1
WQ Max Comp Step=1HOUR
WQ Output Interval=15MIN
WQ Output Selected Increments= 0
WQ Output face flow=0
WQ Output face velocity=0
WQ Output face area=0
WQ Output face dispersion=0
WQ Output cell volume=0
WQ Output cell surface area=0
WQ Output cell continuity=0
WQ Output cumulative cell continuity=0
WQ Output face conc=0
WQ Output face dconc_dx=0
WQ Output face courant=0
WQ Output face peclet=0
WQ Output face adv mass=0
WQ Output face disp mass=0
WQ Output cell mass=0
WQ Output cell source sink temp=0
WQ Output cell source sink nsm=0
WQ Output MaxMinRange=-1
WQ Daily Max Min Mean=-1
WQ Daily Range=0
WQ Daily Time=0
WQ Create Restart=0
WQ Fixed Restart=0
WQ System Summary=0
WQ Use Fixed Temperature=0
Sorting and Armoring Iterations= 10
XS Update Threshold= 0.02
Hydraulics Update Threshold= 0.02
Energy Slope Method= 1
Volume Change Method= 0
XS Weighting Method= 0
Number of US Weighted Cross Sections= 1
Number of DS Weighted Cross Sections= 1
Upstream XS Weight=0.25
Main XS Weight=0.5
Downstream XS Weight=0.25
Number of DS XS's Weighted with US Boundary= 1
Upstream Boundary Weight= 1
Weight of XSs Associated with US Boundary= 0
Number of US XS's Weighted with DS Boundary= 1
Downstream Boundary Weight= 0.5
Weight of XSs Associated with DS Boundary= 0.5
Sediment Output Level= 4
Mass or Volume Output= 0
Output Increment Type= 1
Profile and TS Output Increment= 10
XS Output Flag= 0
XS Output Increment= 10
Disregard all LS=0
Disregard all Conn=0
Disregard all Breaches=0
Disregard all Pumps=0

--- LEE BRANCH.f01 (steady flow) ---

Flow Title=Multiple
Program Version=4.10
Number of Profiles= 7
Profile Names=10-year,25-year,50-year,1pct_min,100-year,1pct_plu,500-year
River Rch & RM=LEE BRANCH,Reach-1         ,26841
    1276    1806    2514    1148    3467   10470    6834
River Rch & RM=LEE BRANCH,Reach-1         ,16758
    2038    2924    4108    1891    5710   17244   11417
River Rch & RM=LEE BRANCH,Reach-1         ,16556
    2038    2924    4108    1891    5710   17244   11417
River Rch & RM=LEE BRANCH,Reach-1         ,7988
    2387    3451    4870    2251    6798   20530   13717
River Rch & RM=LEE BRANCH,Reach-1         ,7778
    2387    3451    4870    2251    6798   20530   13717
River Rch & RM=LEE BRANCH,Reach-1         ,4928
    2405    3467    4884    2253    6803   20545   13669
Boundary for River Rch & Prof#=LEE BRANCH,Reach-1         , 1
Up Type= 0
Dn Type= 3
Dn Slope=0.004
Boundary for River Rch & Prof#=LEE BRANCH,Reach-1         , 2
Up Type= 0
Dn Type= 3
Dn Slope=0.004
Boundary for River Rch & Prof#=LEE BRANCH,Reach-1         , 3
Up Type= 0
Dn Type= 3
Dn Slope=0.004
Boundary for River Rch & Prof#=LEE BRANCH,Reach-1         , 4
Up Type= 0
Dn Type= 3
Dn Slope=0.004
Boundary for River Rch & Prof#=LEE BRANCH,Reach-1         , 5
Up Type= 0
Dn Type= 3
Dn Slope=0.004
Boundary for River Rch & Prof#=LEE BRANCH,Reach-1         , 6
Up Type= 0
Dn Type= 3
Dn Slope=0.004
Boundary for River Rch & Prof#=LEE BRANCH,Reach-1         , 7
Up Type= 0
Dn Type= 3
Dn Slope=0.004
DSS Import GetInterval= 0
DSS Import GetPeak= 0
DSS Import FillOption= 0

--- LEE BRANCH.g01 (geometry) ---

Geom Title=Existing Conditions
Program Version=4.10

River Reach=LEE BRANCH      ,Reach-1
Reach XY= 30
      3735283.23     10233451.84      3736028.23     10232546.84
      3736580.49     10232414.75      3737008.23     10231496.84
      3736998.23     10231016.84      3737566.65     10230636.08
      3737470.43     10230397.63      3738112.37     10229023.84
      3739524.48     10228372.15      3740102.83     10227492.76
      3741017.28     10227128.51      3741300.74     10225636.77
      3741623.01     10224952.93      3742198.23     10224396.84
      3742159.15     10223860.22      3742687.65     10222762.51
      3742619.96     10222228.46       3743388.2     10221349.92
      3743059.82     10219979.29      3743357.63     10219772.76
      3743370.18     10219137.65      3743998.23     10217876.84
      3744019.08     10216171.89      3744447.25     10215642.54
      3744465.52     10215326.02      3744228.57     10215173.81
      3744387.74     10214601.67      3744754.41     10214415.25
      3744490.02     10213881.85      3744738.23     10213386.84

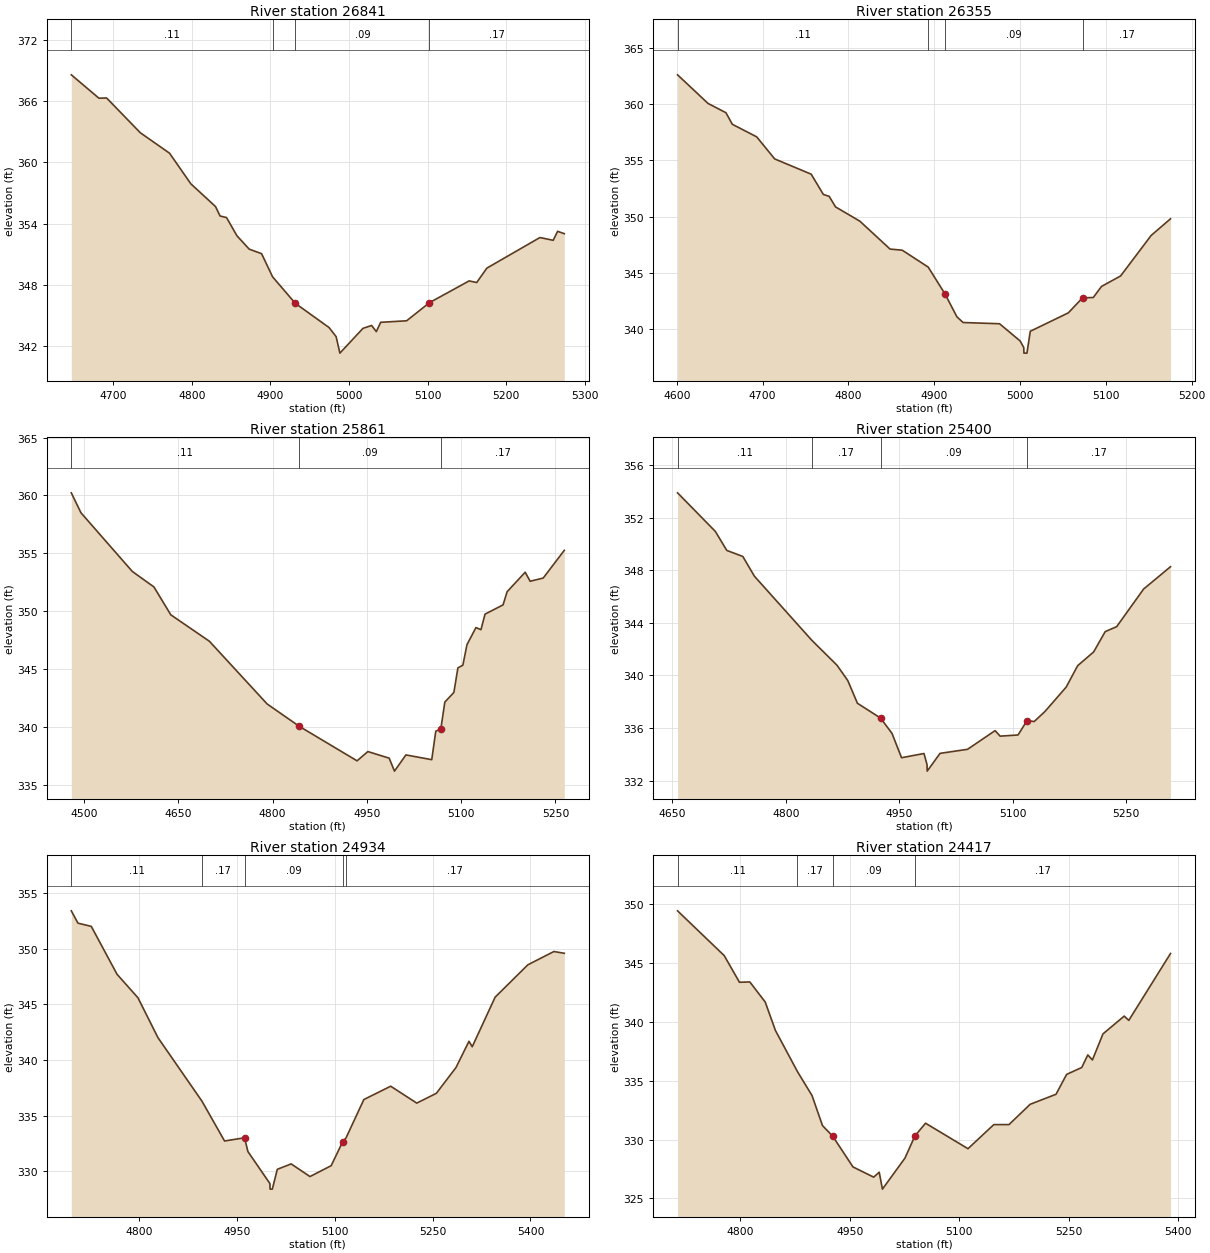
Type RM Length L Ch R = 1 ,26841   ,486,486,486
BEGIN DESCRIPTION:
LEE BRANCH 53.0
END DESCRIPTION:
XS GIS Cut Line= 3
      3735717.85     10233511.08      3735538.23     10233206.84
      3735417.84     10232961.04
#Sta/Elev= 30
  4646.7  368.58  4681.8  366.29  4691.6  366.31  4734.5   362.9  4771.6   360.9
  4798.8  357.89  4830.1  355.67  4835.9  354.74  4844.1  354.59  4857.4   352.8
    4873  351.49  4888.7  351.05  4902.7  348.78  4931.6  346.18  4974.5  343.81
  4983.5  342.92  4988.3   341.3  5017.7  343.73  5028.7  344.01  5034.6  343.41
  5040.2  344.32  5073.2  344.47  5102.1  346.24  5152.7  348.38  5162.3  348.22
  5175.2  349.63  5242.7  352.63  5259.6  352.36  5265.2  353.24  5273.7  353.01
#Mann= 4 ,-1 , 0
  4646.7     .11       0  4902.7     .17       0  4931.6     .09       0
  5102.1     .17       0
Bank Sta=4931.6,5102.1
XS Rating Curve= 0 ,0
Exp/Cntr=0.3,0.1

Type RM Length L Ch R = 1 ,26355   ,494,494,494
BEGIN DESCRIPTION:
LEE BRANCH 52.0
END DESCRIPTION:
XS GIS Cut Line= 3
      3736067.86     10233161.09      3735798.23     10232866.84
      3735717.85     10232711.06
#Sta/Elev= 30
  4600.9  362.64  4636.4  360.09  4657.3  359.26  4664.7  358.23  4693.1  357.11
  4714.1  355.14  4756.6  353.78  4770.8  351.97  4777.6   351.8    4785  350.86
  4813.3  349.59  4848.5   347.1  4862.7     347    4893  345.49  4912.6  343.09
  4926.4  341.06  4933.6  340.55  4976.1  340.44    5000  338.91  5004.3  338.32
  5004.5  337.82    5008  337.82  5011.9  339.77  5056.2  341.41  5072.8  342.75
  5085.3  342.78  5094.9  343.77  5117.1   344.7  5152.8  348.32  5175.3   349.8
#Mann= 4 ,-1 , 0
  4600.9     .11       0    4893     .17       0  4912.6     .09       0
  5072.8     .17       0
Bank Sta=4912.6,5072.8
XS Rating Curve= 0 ,0
Exp/Cntr=0.3,0.1

Type RM Length L Ch R = 1 ,25861   ,461,461,461
BEGIN DESCRIPTION:
LEE BRANCH 51.0
END DESCRIPTION:
XS GIS Cut Line= 3
      3736199.33     10233076.04      3736090.71     10232553.96
      3735896.37     10232395.36
#Sta/Elev= 30
  4479.9  360.23  4495.2  358.51  4576.9  353.44  4611.3   352.1  4638.2  349.69
  4699.5  347.41  4791.4  341.99  4842.5  340.06  4934.4  337.08  4951.6  337.88
  4985.5  337.31  4993.9  336.19  5012.1  337.59  5053.2  337.18  5059.6  339.64
  5067.6  339.83    5074  342.15  5088.4  342.99  5094.8  345.11  5102.7  345.34
  5109.2  347.11  5123.5  348.59  5131.5  348.41  5137.9  349.75  5166.6  350.55
  5173.1  351.69  5201.8  353.37  5209.7  352.59  5230.5  352.87    5264  355.26
#Mann= 3 ,-1 , 0
  4479.9     .11       0  4842.5     .09       0  5067.6     .17       0
Bank Sta=4842.5,5067.6
XS Rating Curve= 0 ,0
Exp/Cntr=0.3,0.1

Type RM Length L Ch R = 1 ,25400   ,466,466,466
BEGIN DESCRIPTION:
LEE BRANCH 50.0
END DESCRIPTION:
XS GIS Cut Line= 3
      3736767.81     10232661.05      3736478.23     10232476.84
      3736217.83     10232311.06
#Sta/Elev= 30
  4656.8  353.89  4706.7  350.96  4721.9  349.51  4743.1  349.05  4758.4  347.55
  4834.4  342.67  4867.6  340.78  4881.9  339.61  4894.7  337.88  4925.2  336.76
  4940.4  335.59    4953  333.74  4982.7  334.06  4986.7  333.22  4986.9  332.72
  5003.9  334.07  5040.3  334.38  5076.7   335.8  5083.4  335.38  5107.1  335.47
    5119  336.57  5128.4  336.49  5142.7  337.26  5170.7  339.11  5185.9  340.74
  5207.1  341.79  5222.3  343.33  5237.5  343.71  5273.1  346.57  5308.7  348.27
#Mann= 4 ,-1 , 0
  4656.8     .11       0  4834.4     .17       0  4925.2     .09       0
    5119     .17       0
Bank Sta=4925.2,5119
XS Rating Curve= 0 ,0
Exp/Cntr=0.3,0.1

Type RM Length L Ch R = 1 ,24934   ,517,517,517
BEGIN DESCRIPTION:
LEE BRANCH 49.0
END DESCRIPTION:
XS GIS Cut Line= 3
      3736967.86     10232161.07      3736524.86     10232069.14
      3736221.98     10232082.12
#Sta/Elev= 30
  4696.2  353.42  4706.4  352.31  4726.8  352.02  4766.3  347.71  4798.3   345.6
    4829  342.01  4896.5  336.29  4931.1  332.71  4961.7     333  4966.9  331.76
  5000.6  328.88  5000.8  328.38  5004.3  328.38  5011.9  330.16  5033.2  330.65
    5062  329.51  5094.5  330.49  5112.2  332.65  5117.3  332.99  5144.6  336.44
  5185.7  337.64  5225.7  336.12  5255.7     337  5285.8  339.32  5305.7  341.68
  5310.7  341.19  5345.8  345.65  5395.9  348.56  5435.9  349.76  5451.8   349.6
#Mann= 5 ,-1 , 0
  4696.2     .11       0  4896.5     .17       0  4961.7     .09       0
  5112.2     .12       0  5117.3     .17       0
#XS Ineff= 1 ,-1
  5185.7  5264.5  337.64
Permanent Ineff=
       F
Bank Sta=4961.7,5112.2
XS Rating Curve= 0 ,0
Exp/Cntr=0.3,0.1

Type RM Length L Ch R = 1 ,24417   ,492,492,492
BEGIN DESCRIPTION:
LEE BRANCH 48.0
END DESCRIPTION:
XS GIS Cut Line= 3
      3737067.86     10231911.08      3736878.23     10231696.84
      3736567.83     10231461.06
#Sta/Elev= 30
  4713.9  349.46  4777.9  345.65  4798.8  343.38    4813  343.41  4834.1   341.7
  4848.1  339.28  4878.3  335.78  4898.3  333.74  4912.6  331.19  4926.8  330.27
  4954.4  327.67  4982.8   326.8  4990.4  327.22  4994.8  325.78  5025.6  328.41
  5039.4  330.31  5053.9  331.39  5112.1  329.22  5147.5  331.27  5168.3  331.27
  5197.4     333  5232.8  333.85  5247.3  335.54  5268.1  336.13  5276.4   337.2
  5282.7  336.77  5297.2  338.99  5326.3   340.5  5332.6  340.14  5389.8  345.83
#Mann= 4 ,-1 , 0
  4713.9     .11       0  4878.3     .17       0  4926.8     .09       0
  5039.4     .17       0
Bank Sta=4926.8,5039.4
XS Rating Curve= 0 ,0
Exp/Cntr=0.3,0.1

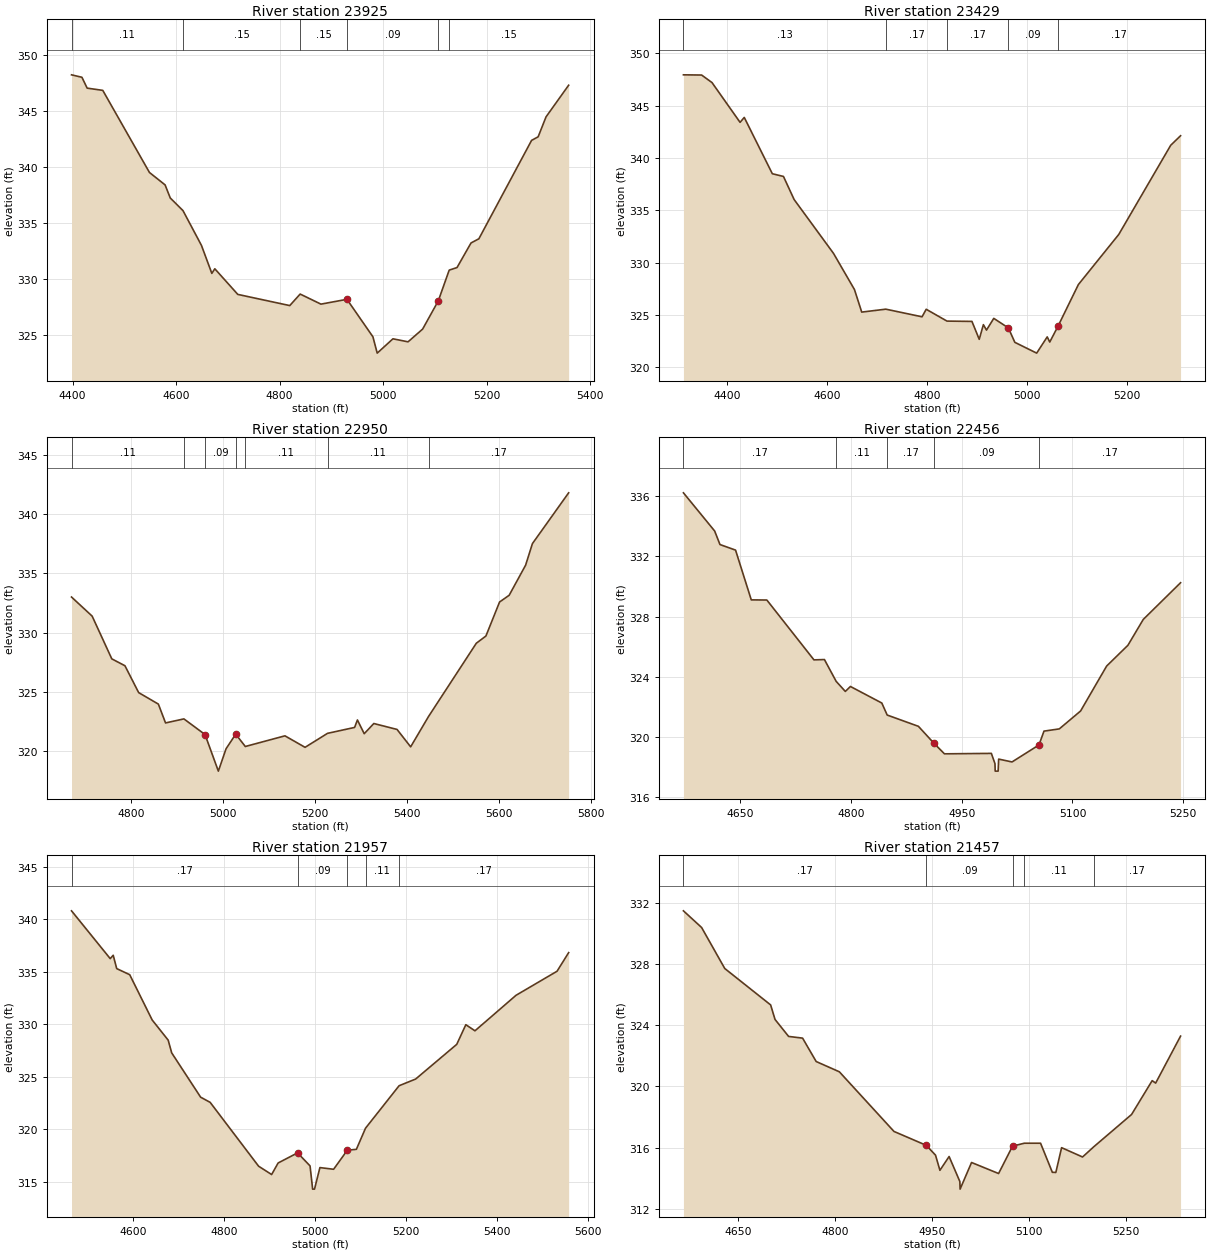
Type RM Length L Ch R = 1 ,23925   ,496,496,496
BEGIN DESCRIPTION:
LEE BRANCH 47.0
END DESCRIPTION:
XS GIS Cut Line= 3
      3737567.88     10231361.07      3736968.23     10231306.84
      3736667.89      10231111.1
#Sta/Elev= 30
  4397.9  348.27    4418  348.05  4428.1  347.08  4458.3  346.88  4548.5  339.54
  4578.7  338.43  4588.7  337.26  4613.3  336.13    4649  333.02    4669  330.52
  4674.8  330.93  4719.2  328.64  4819.6  327.64  4839.7  328.67  4879.9  327.77
  4930.1   328.2  4980.3  324.85  4988.6  323.39    5019  324.67  5048.2   324.4
  5076.4  325.54  5106.6  328.06  5127.7  330.81  5142.8  331.04  5169.9  333.24
    5185  333.61  5286.9  342.41  5299.6  342.73  5314.8  344.51  5358.5  347.34
#Mann= 6 ,-1 , 0
  4397.9     .11       0  4613.3     .15       0  4839.7     .15       0
  4930.1     .09       0  5106.6     .15       0  5127.7     .15       0
Bank Sta=4930.1,5106.6
XS Rating Curve= 0 ,0
Exp/Cntr=0.3,0.1

Type RM Length L Ch R = 1 ,23429   ,479,479,479
BEGIN DESCRIPTION:
LEE BRANCH 46.0
END DESCRIPTION:
XS GIS Cut Line= 3
      3737617.82     10231311.05      3737068.23     10230896.84
      3736767.82     10230961.08
#Sta/Elev= 30
  4311.8  347.96  4348.2  347.94    4369  347.22  4425.2  343.42  4433.6  343.89
  4489.8  338.51  4512.1  338.25  4533.5  336.04  4612.3   330.9  4654.2  327.45
  4668.8  325.29    4717  325.57  4789.6  324.84  4797.9  325.56  4839.5  324.43
  4889.5   324.4  4904.1  322.69  4912.4  324.09  4918.6  323.57  4933.2  324.69
  4962.4  323.78  4975.4   322.4  5019.1  321.37  5040.2  322.92  5045.3  322.43
  5061.7  323.93  5102.6  327.92  5183.5  332.71  5287.5  341.23  5307.2  342.14
#Mann= 5 ,-1 , 0
  4311.8     .13       0    4717     .17       0  4839.5     .17       0
  4962.4     .09       0  5061.7     .17       0
Bank Sta=4962.4,5061.7
XS Rating Curve= 0 ,0
Exp/Cntr=0.3,0.1

Type RM Length L Ch R = 1 ,22950   ,494,494,494
BEGIN DESCRIPTION:
LEE BRANCH 45.0
END DESCRIPTION:
XS GIS Cut Line= 3
      3737617.88     10231011.11      3737449.33     10230727.05
      3737017.83     10230111.04
#Sta/Elev= 30
  4669.7     333  4714.6  331.39  4757.4  327.78    4786   327.2  4815.9  324.93
  4858.8  323.96  4874.4  322.37  4914.4  322.71  4960.4  321.39  4989.4   318.3
  5006.2  320.19  5027.2  321.42  5048.1  320.38  5134.4  321.28  5178.2  320.31
  5227.1  321.49  5286.1  321.99  5292.2  322.62    5307  321.46  5327.9  322.32
  5378.5  321.82  5408.1  320.35    5447  322.91  5551.1   329.1    5572  329.71
  5601.7  332.58  5622.6  333.15  5658.4  335.69  5673.2  337.51  5752.1   341.8
#Mann= 7 ,-1 , 0
  4669.7     .11       0  4914.4     .17       0  4960.4     .09       0
  5027.2     .17       0  5048.1     .11       0  5227.1     .11       0
    5447     .17       0
Bank Sta=4960.4,5027.2
XS Rating Curve= 0 ,0
Exp/Cntr=0.3,0.1

Type RM Length L Ch R = 1 ,22456   ,499,499,499
BEGIN DESCRIPTION:
LEE BRANCH 44.0
END DESCRIPTION:
XS GIS Cut Line= 3
      3737817.84     10230661.06      3737510.58     10230364.55
      3737317.83     10230211.05
#Sta/Elev= 30
    4573  336.23  4615.3  333.69  4622.5  332.79  4643.6  332.42  4664.9  329.11
    4686   329.1  4749.8  325.12    4764  325.14  4779.9  323.69  4792.3  323.02
  4799.2  323.35  4841.7  322.25    4849  321.45  4891.3   320.7  4912.4  319.57
  4926.6  318.87  4990.1   318.9    4995  318.22  4995.3  317.72  4999.3  317.72
    5000  318.52  5018.1  318.33  5054.6  319.46  5061.4  320.38  5082.2  320.53
    5111  321.72  5146.3  324.71  5175.1  326.09  5195.9  327.81  5246.4  330.25
#Mann= 5 ,-1 , 0
    4573     .17       0  4779.9     .11       0    4849     .17       0
  4912.4     .09       0  5054.6     .17       0
Bank Sta=4912.4,5054.6
XS Rating Curve= 0 ,0
Exp/Cntr=0.3,0.1

Type RM Length L Ch R = 1 ,21957   ,500,500,500
BEGIN DESCRIPTION:
LEE BRANCH 43.0
END DESCRIPTION:
XS GIS Cut Line= 3
      3738067.83     10230261.06       3737659.1     10229915.86
      3737102.44     10229872.98
#Sta/Elev= 30
    4465   340.8  4550.1  336.25  4556.7  336.57  4564.4   335.3    4593  334.72
  4642.4  330.41  4677.6  328.49  4685.3  327.28    4749  323.06  4769.9  322.57
  4876.5  316.49  4905.1   315.7  4919.4   316.8  4962.2  317.76  4989.6  316.52
  4995.3  314.31  4999.4  314.31  5011.3  316.36  5041.4   316.2  5071.5  318.01
  5091.5   318.1  5111.6  320.11  5185.4  324.15  5221.9  324.79  5312.2  328.09
  5332.2  329.96  5352.3  329.38  5442.6  332.76  5532.8  335.05  5558.3  336.82
#Mann= 5 ,-1 , 0
    4465     .17       0  4962.2     .09       0  5071.5     .17       0
  5111.6     .11       0  5185.4     .17       0
Bank Sta=4962.2,5071.5
XS Rating Curve= 0 ,0
Exp/Cntr=0.3,0.1

Type RM Length L Ch R = 1 ,21457   ,497,497,497
BEGIN DESCRIPTION:
LEE BRANCH 42.0
END DESCRIPTION:
XS GIS Cut Line= 3
      3738267.87      10229911.1      3737976.44     10229588.69
      3737667.89     10229461.09
#Sta/Elev= 30
  4565.4  331.47  4593.5  330.38  4629.3   327.7  4700.2  325.32    4707  324.37
    4728  323.26  4749.6  323.15  4770.6  321.62  4806.4  320.95  4890.9  317.05
  4940.9  316.14  4955.1   315.5  4961.9  314.51  4976.1  315.41  4992.7  313.78
  4993.1  313.28  5010.8  315.02  5052.6   314.3  5074.2  316.09  5092.4  316.28
  5117.5  316.28  5135.7  314.38  5141.1  314.37    5150  315.99  5182.4  315.38
  5199.8  316.05  5258.2  318.16    5290  320.37  5295.4  320.21  5333.9  323.28
#Mann= 5 ,-1 , 0
  4565.4     .17       0  4940.9     .09       0  5074.2     .17       0
  5092.4     .11       0  5199.8     .17       0
Bank Sta=4940.9,5074.2
XS Rating Curve= 0 ,0
Exp/Cntr=0.3,0.1

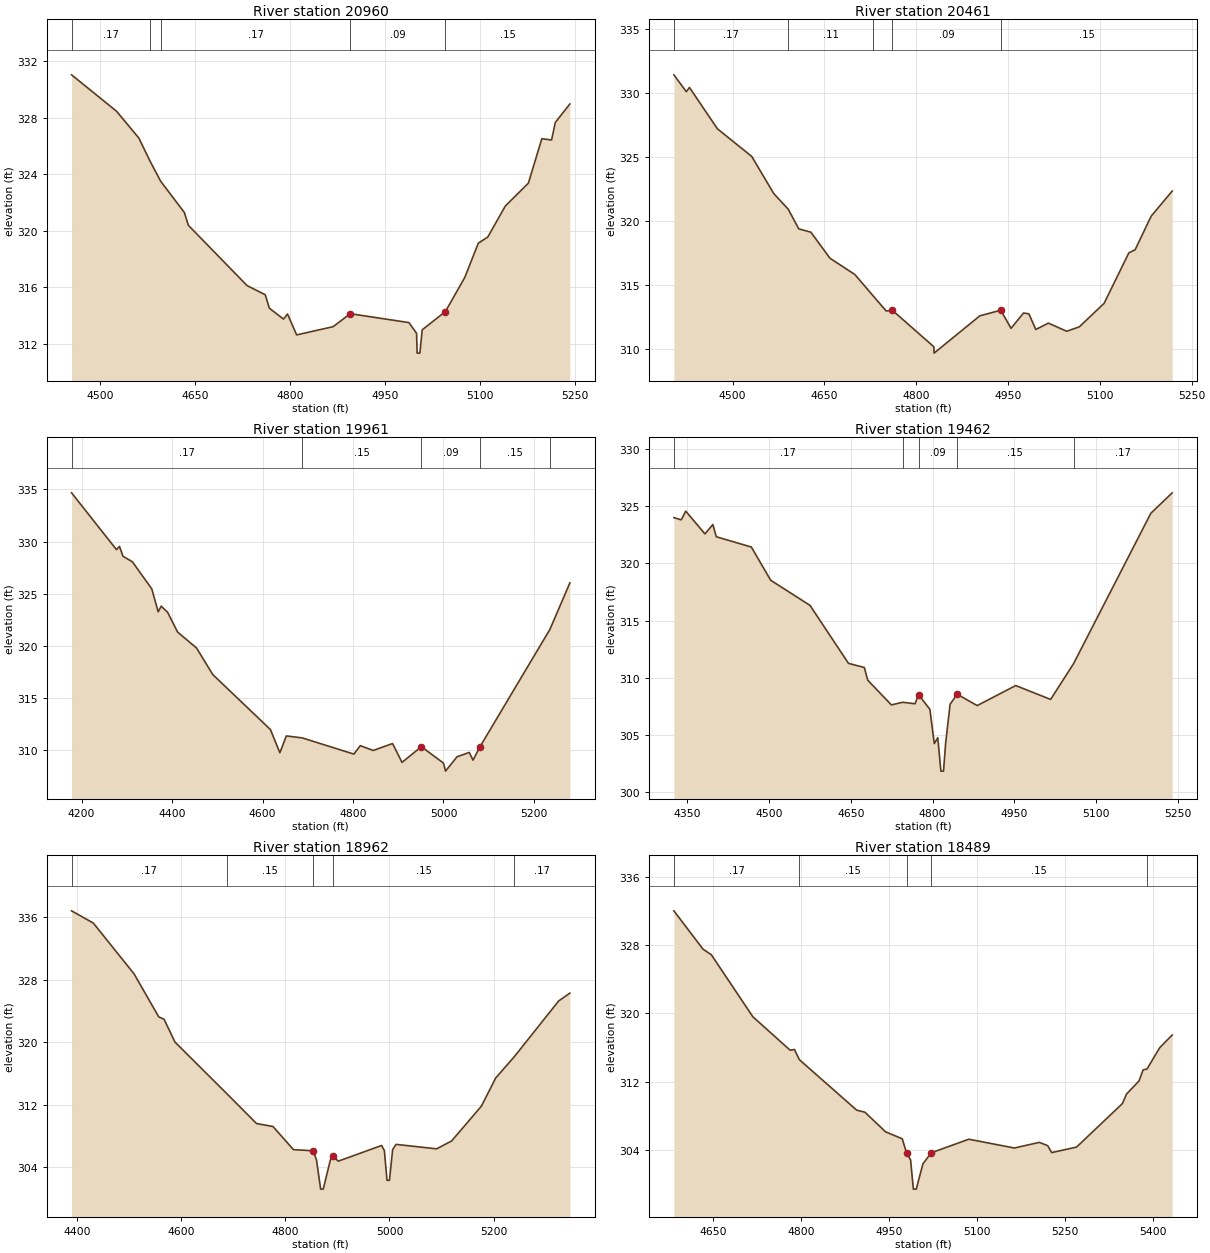
Type RM Length L Ch R = 1 ,20960   ,499,499,499
BEGIN DESCRIPTION:
LEE BRANCH 41.0
END DESCRIPTION:
XS GIS Cut Line= 3
      3738467.83     10229511.06      3738045.67      10229166.7
      3737917.86     10228961.09
#Sta/Elev= 30
  4455.2  331.03  4526.3  328.45  4561.4  326.56  4579.5  324.89  4595.9   323.5
  4633.3  321.29  4639.7  320.38  4732.3  316.12  4761.1  315.47  4767.5  314.52
  4789.8  313.75  4796.2  314.11  4810.6  312.63  4868.1  313.21  4895.3  314.13
    4988   313.5    5000  312.74  5000.9  311.34  5005.2  311.34  5008.9  312.99
  5045.5  314.28  5076.2   316.7  5097.5  319.12  5112.6  319.56    5140  321.74
  5176.6  323.37  5197.8  326.51  5213.2  326.42  5219.1  327.66  5242.1  328.97
#Mann= 5 ,-1 , 0
  4455.2     .17       0  4579.5     .11       0  4595.9     .17       0
  4895.3     .09       0  5045.5     .15       0
Bank Sta=4895.3,5045.5
XS Rating Curve= 0 ,0
Exp/Cntr=0.3,0.1

Type RM Length L Ch R = 1 ,20461   ,500,500,500
BEGIN DESCRIPTION:
LEE BRANCH 40.0
END DESCRIPTION:
XS GIS Cut Line= 3
      3738517.85     10229511.08      3738400.39     10228926.77
      3738367.86     10228711.11
#Sta/Elev= 30
    4404  331.44  4424.3  330.12  4429.4  330.45  4475.2  327.21  4531.2  325.05
  4567.2  322.14  4590.8  320.92    4608  319.38  4627.8  319.12    4659  317.08
  4699.8   315.8  4729.6  314.13  4750.8  312.95    4761     313  4828.7  310.15
  4829.1  309.65  4903.8  312.57  4938.1  313.01  4954.8  311.59  4975.2  312.79
  4983.9  312.73  4995.3   311.5  5015.9     312  5045.8  311.36  5066.4  311.71
  5106.9  313.55  5147.3   317.5  5157.5  317.74  5183.7  320.37  5218.1  322.34
#Mann= 5 ,-1 , 0
    4404     .17       0  4590.8     .11       0  4729.6     .15       0
    4761     .09       0  4938.1     .15       0
Bank Sta=4761,4938.1
XS Rating Curve= 0 ,0
Exp/Cntr=0.3,0.1

Type RM Length L Ch R = 1 ,19961   ,499,499,499
BEGIN DESCRIPTION:
LEE BRANCH 39.0
END DESCRIPTION:
XS GIS Cut Line= 3
      3739417.83     10229261.05      3738792.87     10228726.79
      3738567.81     10228561.04
#Sta/Elev= 30
  4177.8  334.66  4277.1  329.22  4283.7  329.53  4291.4  328.59  4312.2  328.06
  4355.1  325.47  4369.3  323.27  4375.9  323.81  4390.2  323.22  4412.2  321.33
    4454  319.81  4490.1  317.26  4617.4     312  4638.3  309.78  4652.6  311.39
  4687.9   311.2  4801.9  309.65  4816.1  310.46  4844.7     310  4887.5  310.66
  4908.3  308.86  4951.2  310.36    5000  308.79  5004.6  308.02  5029.9  309.39
    5057  309.81  5065.4  309.07    5080   310.3  5235.5   321.6  5279.5  326.04
#Mann= 5 ,-1 , 0
  4177.8     .17       0  4687.9     .15       0  4951.2     .09       0
    5080     .15       0  5235.5     .17       0
Bank Sta=4951.2,5080
XS Rating Curve= 0 ,0
Exp/Cntr=0.3,0.1

Type RM Length L Ch R = 1 ,19462   ,500,500,500
BEGIN DESCRIPTION:
LEE BRANCH 38.0
END DESCRIPTION:
XS GIS Cut Line= 3
      3739717.86     10228911.08      3739185.55     10228496.51
      3739007.49     10228336.49
#Sta/Elev= 30
  4325.3     324  4338.9  323.81    4347  324.57  4382.3  322.58  4396.8   323.4
  4403.1  322.33  4467.4  321.43  4502.8  318.53    4575  316.33  4645.6  311.26
  4674.6   310.9  4680.9  309.79  4724.3  307.63  4745.1  307.86  4767.7  307.73
  4774.1  308.53  4794.9  307.24    4803  304.25  4809.4  304.76  4815.1  301.84
  4819.9  301.84  4823.8  304.28    4832  307.69    4845  308.56  4881.7  307.57
  4952.3  309.32  5016.4  308.11  5058.4  311.23  5200.2  324.38  5239.4  326.17
#Mann= 5 ,-1 , 0
  4325.3     .17       0  4745.1     .15       0  4774.1     .09       0
    4845     .15       0  5058.4     .17       0
Bank Sta=4774.1,4845
XS Rating Curve= 0 ,0
Exp/Cntr=0.3,0.1

Type RM Length L Ch R = 1 ,18962   ,473,473,473
BEGIN DESCRIPTION:
LEE BRANCH 37.0
END DESCRIPTION:
XS GIS Cut Line= 3
      3740167.84     10228461.07      3739583.86     10228283.08
      3739317.83     10228061.06
#Sta/Elev= 30
  4389.5  336.85  4431.3  335.28  4509.6  328.77  4556.8  323.28  4567.2  322.96
  4588.1  320.04  4687.9  313.42  4744.7  309.61  4776.3  309.23  4815.6  306.27
  4853.6  306.12  4859.9  304.93  4867.9  301.21  4872.8  301.21  4886.4  304.91
  4891.7  305.41  4901.7  304.79  4984.9   306.8  4990.2  306.16  4995.3  302.34
    5000  302.34  5006.1  306.27  5012.6  306.94  5090.7  306.37  5119.4  307.38
  5176.6  311.84    5204  315.44  5239.4  318.14    5325  325.31  5346.5  326.31
#Mann= 5 ,-1 , 0
  4389.5     .17       0  4687.9     .15       0  4853.6     .09       0
  4891.7     .15       0  5239.4     .17       0
Bank Sta=4853.6,4891.7
XS Rating Curve= 0 ,0
Exp/Cntr=0.3,0.1

Type RM Length L Ch R = 1 ,18489   ,479,479,479
BEGIN DESCRIPTION:
LEE BRANCH 36.0
END DESCRIPTION:
XS GIS Cut Line= 3
      3740167.89      10228311.1      3739864.45     10228026.24
      3739567.84     10227711.06
#Sta/Elev= 30
  4583.8  332.01  4633.4  327.52  4647.6  326.86  4718.4  319.59  4781.9  315.67
  4789.2  315.76  4797.5  314.57  4895.2  308.65  4909.4   308.4  4944.6   306.1
  4972.9  305.29  4980.2  303.63  4987.1  302.81  4991.8  299.39  4996.7  299.39
  5008.1  302.35  5022.3  303.65  5086.3  305.24  5163.9  304.21  5206.4  304.87
  5220.6  304.49  5227.4  303.67  5269.9  304.32    5348  309.42  5354.9  310.53
  5376.4  312.08  5383.2  313.37  5389.9  313.47  5411.5  315.96  5432.8  317.46
#Mann= 5 ,-1 , 0
  4583.8     .17       0  4797.5     .15       0  4980.2     .09       0
  5022.3     .15       0  5389.9     .17       0
Bank Sta=4980.2,5022.3
XS Rating Curve= 0 ,0
Exp/Cntr=0.3,0.1

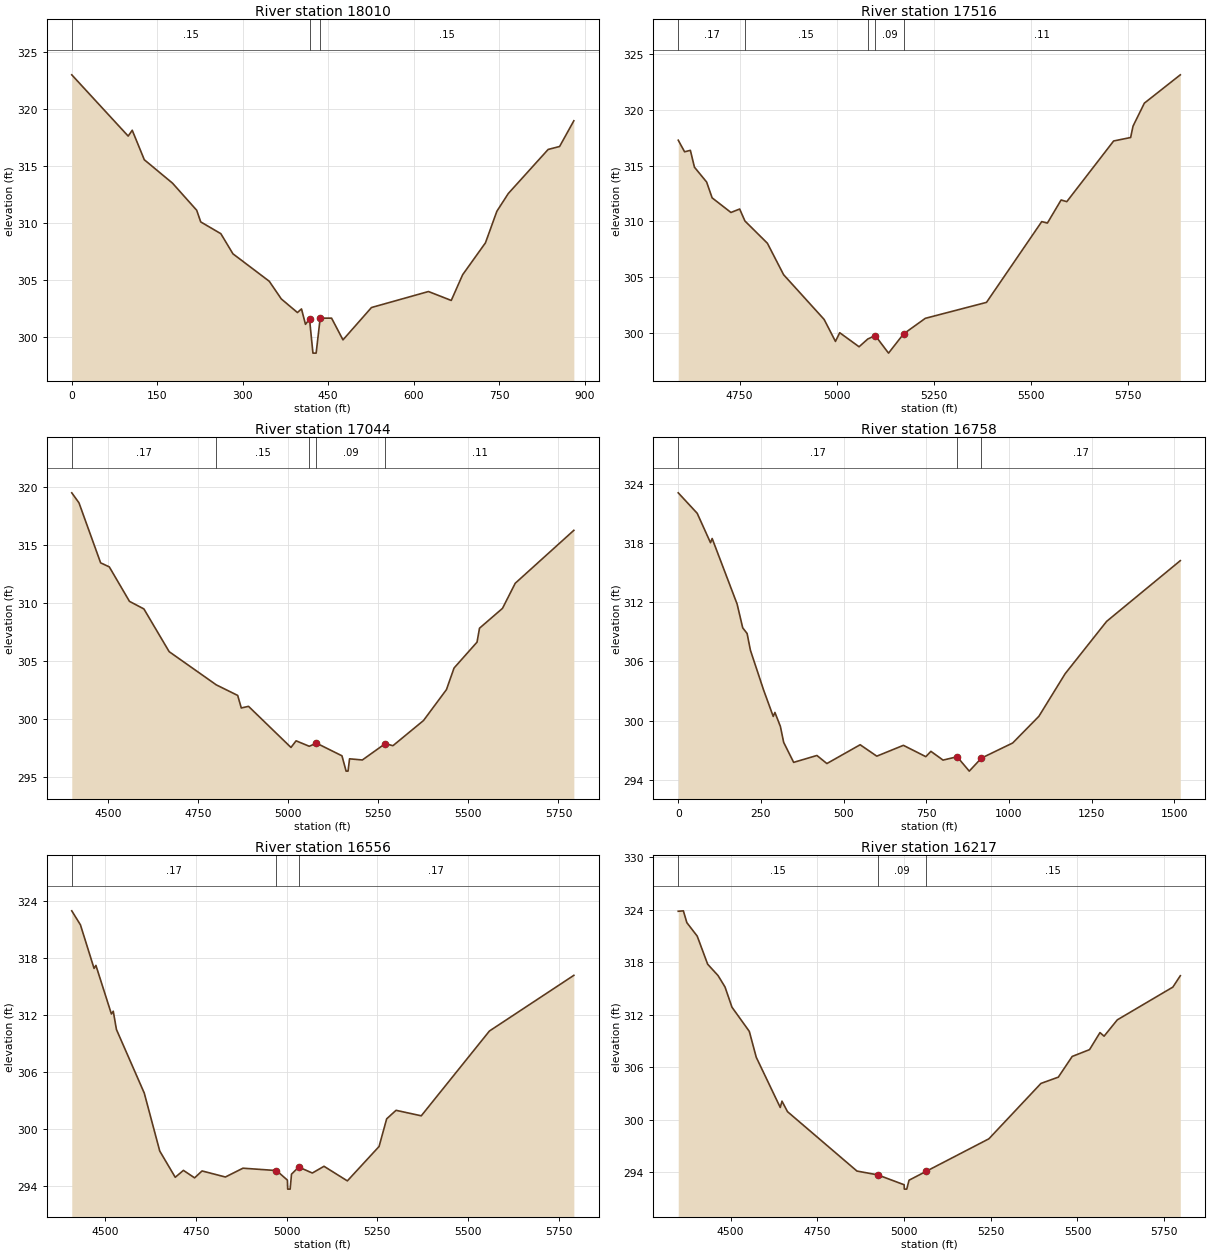
Type RM Length L Ch R = 1 ,18010   ,494,494,494
BEGIN DESCRIPTION:
LEE BRANCH 35.0
END DESCRIPTION:
XS GIS Cut Line= 3
      3740367.85     10227911.07      3740064.87     10227607.58
      3739612.81      10227598.4
#Sta/Elev= 30
       0  322.98      99  317.62   106.1  318.13   127.3  315.55   176.8   313.5
   219.2  311.13   226.3  310.11   261.6  309.08   282.8  307.32   346.5  304.92
   367.7  303.37     396  302.18   403.1   302.5   410.1  301.15   417.2  301.61
   423.2  298.63   428.8  298.63   435.9  301.69   455.9  301.69   475.9  299.79
   525.9  302.62   625.9  304.02   665.9  303.24   685.9  305.49   725.9  308.28
   745.9  311.04   765.9  312.59   835.9  316.45     856  316.71     881  318.96
#Mann= 3 , 0 , 0
       0     .15       0   417.2     .09       0   435.9     .15       0
Bank Sta=417.2,435.9
XS Rating Curve= 0 ,0
Exp/Cntr=0.3,0.1

Type RM Length L Ch R = 1 ,17516   ,472,472,472
BEGIN DESCRIPTION:
LEE BRANCH 34.0
END DESCRIPTION:
XS GIS Cut Line= 3
      3740517.85     10227711.07      3740399.11     10227320.31
      3739867.88     10226611.11
#Sta/Elev= 30
  4591.6  317.27    4608  316.23  4622.9  316.36  4633.4  314.85  4664.8  313.52
    4679   312.1  4727.5  310.79    4750   311.1  4763.5  310.03  4821.5  308.03
  4863.3  305.21  4967.8   301.2    4997  299.23  5007.9  300.01  5057.9  298.75
  5080.1  299.44  5099.5  299.76  5133.8  298.18  5172.5   299.9  5228.7   301.3
  5386.4  302.73  5528.8  309.97  5543.4  309.84  5578.8  311.91  5593.4  311.76
  5714.2   317.2    5758  317.51  5764.2  318.53  5793.4  320.59  5886.1  323.13
#Mann= 5 ,-1 , 0
  4591.6     .17       0  4763.5     .15       0  5080.1     .11       0
  5099.5     .09       0  5172.5     .11       0
Bank Sta=5099.5,5172.5
XS Rating Curve= 0 ,0
Exp/Cntr=0.3,0.1

Type RM Length L Ch R = 1 ,17044   ,286,286,286
BEGIN DESCRIPTION:
LEE BRANCH 33.0
END DESCRIPTION:
XS GIS Cut Line= 3
      3740867.85     10227761.07      3740838.76     10227160.97
      3740267.83     10226611.05
#Sta/Elev= 30
  4399.2  319.46  4419.2   318.6  4479.3  313.43  4503.4  313.08  4559.4  310.11
  4599.4  309.46  4669.5  305.78  4800.3  302.92  4859.7  302.01  4869.7  300.93
  4889.8  301.07  5007.6  297.53  5021.8   298.1  5058.4  297.63  5078.4   297.9
  5149.1  296.81  5160.6  295.49    5166  295.49  5170.2  296.55  5205.7  296.45
  5269.3  297.86  5290.6  297.68  5375.5  299.85  5439.1  302.51  5460.2  304.37
    5524   306.6  5530.9   307.8  5594.7  309.51    5630  311.67  5792.7  316.23
#Mann= 5 ,-1 , 0
  4399.2     .17       0  4800.3     .15       0  5058.4     .11       0
  5078.4     .09       0  5269.3     .11       0
Bank Sta=5078.4,5269.3
XS Rating Curve= 0 ,0
Exp/Cntr=0.3,0.1

Type RM Length L Ch R = 1 ,16758   ,202,202,202
XS GIS Cut Line= 3
      3741674.96     10227096.95      3740960.24     10227020.66
      3740278.99     10226601.74
#Sta/Elev= 30
       0  323.13    57.4  321.05    97.6  318.06   102.6  318.49   178.1  311.83
     195  309.42   208.3  308.84   218.3  307.14   258.6  303.06   287.3  300.42
   292.4  300.82   308.9  299.41   318.9  297.78   349.1  295.75   419.5  296.45
   449.6  295.63   550.2  297.54   600.5  296.38     681  297.48   748.8  296.33
   764.2  296.87   800.9  295.98   843.5  296.32   880.2  294.86   916.9  296.18
  1011.6  297.72  1090.8  300.43  1170.1  304.75  1295.6  310.07  1518.5  316.24
#Mann= 3 , 0 , 0
       0     .17       0   843.5     .09       0   916.9     .17       0
Bank Sta=843.5,916.9
XS Rating Curve= 0 ,0
Exp/Cntr=0.3,0.1

Type RM Length L Ch R = 1 ,16556   ,339,339,339
BEGIN DESCRIPTION:
LEE BRANCH 32.0
END DESCRIPTION:
XS GIS Cut Line= 3
      3741617.83     10226961.07      3741040.88     10226827.55
      3740286.05     10226587.13
#Sta/Elev= 30
  4407.8  323.01  4431.7  321.53  4469.3  316.93  4474.4  317.25  4517.1  312.12
  4522.2  312.41    4531  310.48  4607.7  303.77  4650.4  297.65  4693.1  294.88
  4715.7  295.61  4746.5  294.82    4767  295.55  4831.4  294.91  4879.9  295.84
  4972.3  295.59  5002.4  294.58  5003.2  293.63    5010  293.63  5013.7  295.21
  5033.6  295.96  5071.1  295.33  5103.3  296.04  5167.7   294.5  5255.1  298.13
  5276.1  301.05  5301.9  301.95  5371.5  301.37  5559.4  310.32  5792.2   316.2
#Mann= 3 ,-1 , 0
  4407.8     .17       0  4972.3     .09       0  5033.6     .17       0
Bank Sta=4972.3,5033.6
XS Rating Curve= 0 ,0
Exp/Cntr=0.3,0.1

Type RM Length L Ch R = 1 ,16217   ,94,94,94
BEGIN DESCRIPTION:
Mapping XS fd647a68
END DESCRIPTION:
XS GIS Cut Line= 2
      3741782.59     10226548.94      3740336.44     10226486.45
#Sta/Elev= 30
    4349  323.84  4363.8  323.89  4373.8  322.54  4403.8  320.99  4433.8  317.78
  4463.8  316.48  4483.9  315.17  4503.9  312.86  4553.9  310.09  4573.9  307.13
  4643.1  301.38  4648.1   302.1    4664   300.9  4864.2   294.1  4924.3  293.66
  5000.3  292.53  5000.8  292.03  5007.8  292.03  5014.4  293.05  5064.4  294.08
  5244.6  297.79  5394.7  304.13  5444.8  304.85  5484.8  307.22  5534.8     308
  5564.9  309.95  5576.7  309.54  5614.9  311.41  5775.1  315.16  5796.5  316.46
#Mann= 3 , 0 , 0
    4349     .15       0  4924.3     .09       0  5064.4     .15       0
Bank Sta=4924.3,5064.4
XS Rating Curve= 0 ,0
Exp/Cntr=0.3,0.1

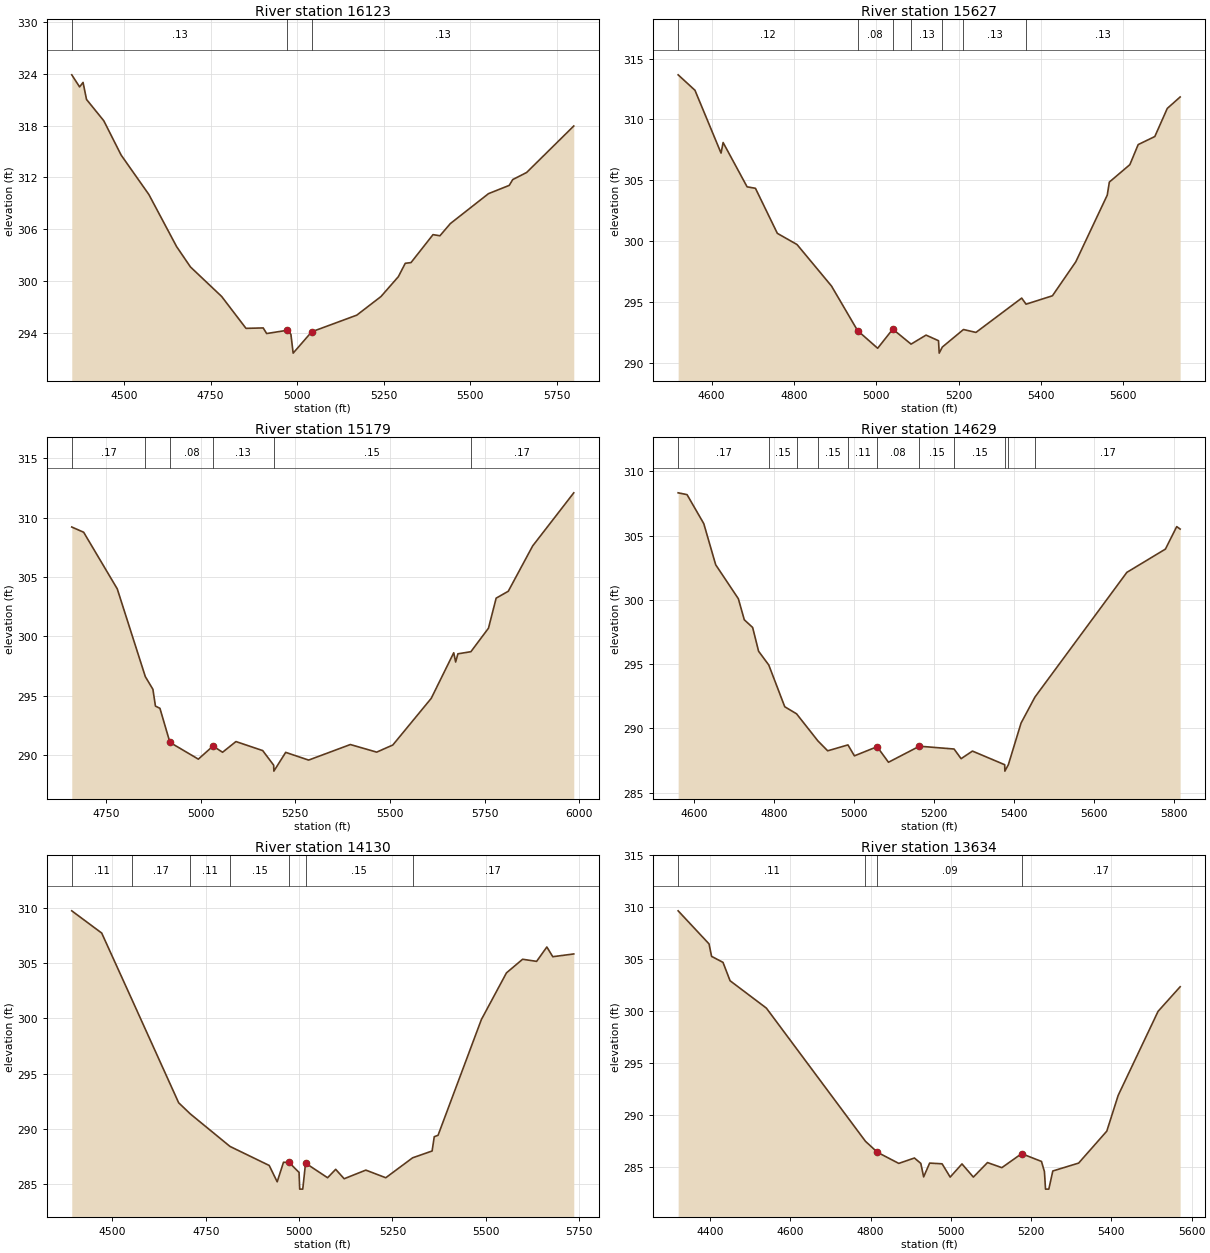
Type RM Length L Ch R = 1 ,16123   ,496,496,496
BEGIN DESCRIPTION:
LEE BRANCH 31.0
END DESCRIPTION:
XS GIS Cut Line= 3
       3741810.4     10226451.72      3741159.82     10226431.29
      3740361.77     10226394.48
#Sta/Elev= 30
  4349.1  323.88  4371.7  322.48  4381.7     323  4391.7  321.03  4441.7  318.55
  4491.7  314.58  4571.8  310.01  4651.8  303.98  4691.8  301.62  4781.9   298.2
  4852.3   294.5  4901.9  294.55  4911.9   293.9    4972  294.28    4982   293.8
  4988.5  291.63    5042   294.1  5172.2  296.03  5242.2  298.19  5292.3  300.49
  5312.3  302.04  5328.8  302.12  5392.4  305.36  5412.4  305.23  5442.4  306.64
  5552.6  310.11  5612.6  311.07  5622.6  311.74  5662.7  312.56  5798.9  317.95
#Mann= 3 , 0 , 0
  4349.1     .13       0    4972     .09       0    5042     .13       0
Bank Sta=4972,5042
XS Rating Curve= 0 ,0
Exp/Cntr=0.3,0.1

Type RM Length L Ch R = 1 ,15627   ,448,448,448
BEGIN DESCRIPTION:
LEE BRANCH 30.0
END DESCRIPTION:
XS GIS Cut Line= 3
      3741743.54     10226052.24      3741267.61     10225979.27
      3740536.94     10225869.95
#Sta/Elev= 30
  4518.5  313.66  4559.4  312.39  4622.8  307.23  4627.8   308.1  4686.1  304.46
  4706.4  304.34  4759.6  300.64  4807.5  299.72  4891.3  296.31  4954.7  292.65
  5003.5   291.2  5040.2  292.77  5084.7  291.54  5121.1  292.28  5151.4  291.82
  5153.1   290.8  5160.7   291.3  5212.1  292.74  5242.4   292.5  5353.6  295.32
  5364.2  294.82  5428.3  295.51  5485.1   298.3  5561.6  303.78  5566.7  304.85
  5616.5  306.28  5636.8  307.93  5677.2  308.59  5707.5   310.9  5738.8  311.84
#Mann= 7 ,-1 , 0
  4518.5     .12       0  4954.7     .08       0  5040.2     .12       0
  5084.7     .13       0  5160.7     .13       0  5212.1     .13       0
  5364.2     .13       0
Bank Sta=4954.7,5040.2
XS Rating Curve= 0 ,0
Exp/Cntr=0.3,0.1

Type RM Length L Ch R = 1 ,15179   ,550,550,550
BEGIN DESCRIPTION:
LEE BRANCH 29.0
END DESCRIPTION:
XS GIS Cut Line= 3
       3741687.1     10225674.63      3741470.11     10225600.85
      3740385.02     10225440.26
#Sta/Elev= 30
  4659.7  309.21  4691.1  308.77  4779.9     304    4854  296.61  4874.1  295.54
  4880.7  294.13  4892.6  293.94    4919  291.07  4994.1  289.66  5032.7  290.76
  5058.1  290.24  5093.4  291.14  5164.1  290.38  5193.1  289.15  5193.6  288.65
  5224.8  290.23  5285.4  289.58  5395.6  290.89  5465.2  290.25  5507.8  290.85
  5609.3  294.78  5668.7  298.62  5673.8  297.84  5679.7  298.53  5714.1  298.71
  5760.5  300.69  5780.8  303.22  5812.8   303.8  5877.3  307.62  5985.8  312.09
#Mann= 6 ,-1 , 0
  4659.7     .17       0    4854     .13       0    4919     .08       0
  5032.7     .13       0  5193.1     .15       0  5714.1     .17       0
Bank Sta=4919,5032.7
XS Rating Curve= 0 ,0
Exp/Cntr=0.3,0.1

Type RM Length L Ch R = 1 ,14629   ,499,499,499
BEGIN DESCRIPTION:
LEE BRANCH 28.0
END DESCRIPTION:
XS GIS Cut Line= 3
      3741817.87     10225511.09      3741567.03     10225148.62
      3741217.86      10224411.1
#Sta/Elev= 30
  4559.2  308.34  4581.5   308.2  4623.4  305.94  4653.2  302.74  4709.9   300.1
  4724.8  298.46  4745.7  297.86  4760.6  296.01  4786.1  294.94  4826.1  291.69
  4855.7  291.14  4908.9  289.04  4933.6  288.26  4984.3  288.72  5000.5  287.87
  5057.3  288.58  5085.8  287.37  5163.2  288.62    5250   288.4  5267.6  287.65
    5296  288.24  5376.7  287.18  5377.2  286.68  5385.9  287.18  5417.7  290.42
  5452.6  292.45  5682.6  302.15  5779.1  303.96  5807.4  305.71    5816  305.52
#Mann= 11 ,-1 , 0
  4559.2     .17       0  4786.1     .15       0  4855.7     .11       0
  4908.9     .15       0  4984.3     .11       0  5057.3     .08       0
  5163.2     .15       0    5250     .15       0  5376.7     .12       0
  5385.9     .15       0  5452.6     .17       0
Bank Sta=5057.3,5163.2
XS Rating Curve= 0 ,0
Exp/Cntr=0.3,0.1

Type RM Length L Ch R = 1 ,14130   ,496,496,496
BEGIN DESCRIPTION:
LEE BRANCH 27.0
END DESCRIPTION:
XS GIS Cut Line= 3
      3742043.04     10225336.14      3741828.44      10224766.2
      3741466.02     10224125.62
#Sta/Elev= 30
    4391  309.73  4471.2  307.72    4552  301.72  4677.4  292.37  4708.4  291.37
    4815  288.42    4920   286.7  4941.4  285.22  4958.3  286.99  4973.4  286.97
    5000  286.07  5001.7  284.56  5009.9  284.56  5017.4  286.91  5076.4  285.59
  5098.1  286.35  5120.8   285.5  5178.9  286.28  5232.3  285.59  5304.1  287.39
  5356.5  288.01  5362.2   289.3  5372.4  289.43  5488.5   299.9  5555.7  304.12
  5598.9  305.35  5636.5  305.16  5663.9  306.46  5679.8  305.58    5736  305.83
#Mann= 7 ,-1 , 0
    4391     .11       0    4552     .17       0  4708.4     .11       0
    4815     .15       0  4973.4     .09       0  5017.4     .15       0
  5304.1     .17       0
Bank Sta=4973.4,5017.4
XS Rating Curve= 0 ,0
Exp/Cntr=0.3,0.1

Type RM Length L Ch R = 1 ,13634   ,507,507,507
BEGIN DESCRIPTION:
LEE BRANCH 26.0
END DESCRIPTION:
XS GIS Cut Line= 3
      3742767.84     10224711.07      3742149.76     10224428.51
      3741766.35     10224004.85
#Sta/Elev= 30
  4320.4  309.65  4397.4  306.46  4403.7  305.26  4432.2  304.68  4449.8  302.91
  4540.3  300.27  4787.2  287.43  4817.1  286.37  4870.2   285.3  4909.2  285.82
  4925.1   285.3  4932.2     284  4947.1  285.33  4978.2  285.26  4998.3  283.98
  5027.7  285.25  5056.1  283.98  5091.3  285.38  5127.1  284.89  5176.4  286.24
  5225.8  285.49  5233.2  284.51  5235.9  282.82  5244.1  282.82  5254.1  284.57
  5318.4  285.33  5388.6  288.41    5417  291.86  5516.4  299.96  5571.4  302.33
#Mann= 4 ,-1 , 0
  4320.4     .11       0  4787.2     .15       0  4817.1     .09       0
  5176.4     .17       0
Bank Sta=4817.1,5176.4
XS Rating Curve= 0 ,0
Exp/Cntr=0.3,0.1