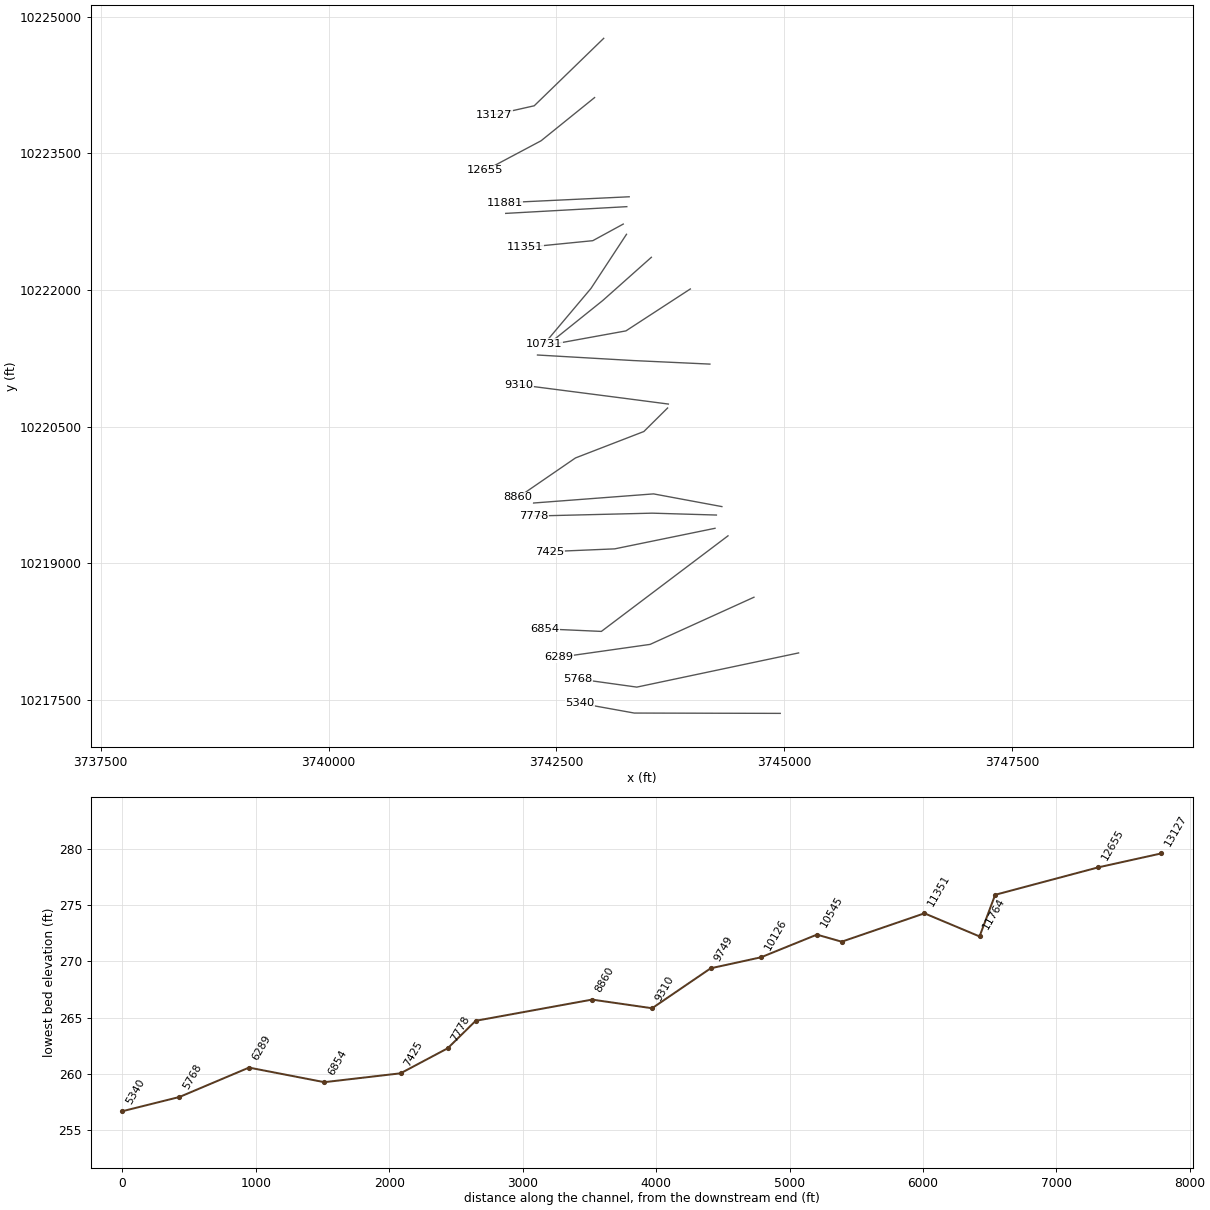
HEC-RAS study LEE BRANCH.prj: LEE BRANCH Base Level Engineering

--- LEE BRANCH.g01 (geometry) --- (continued)

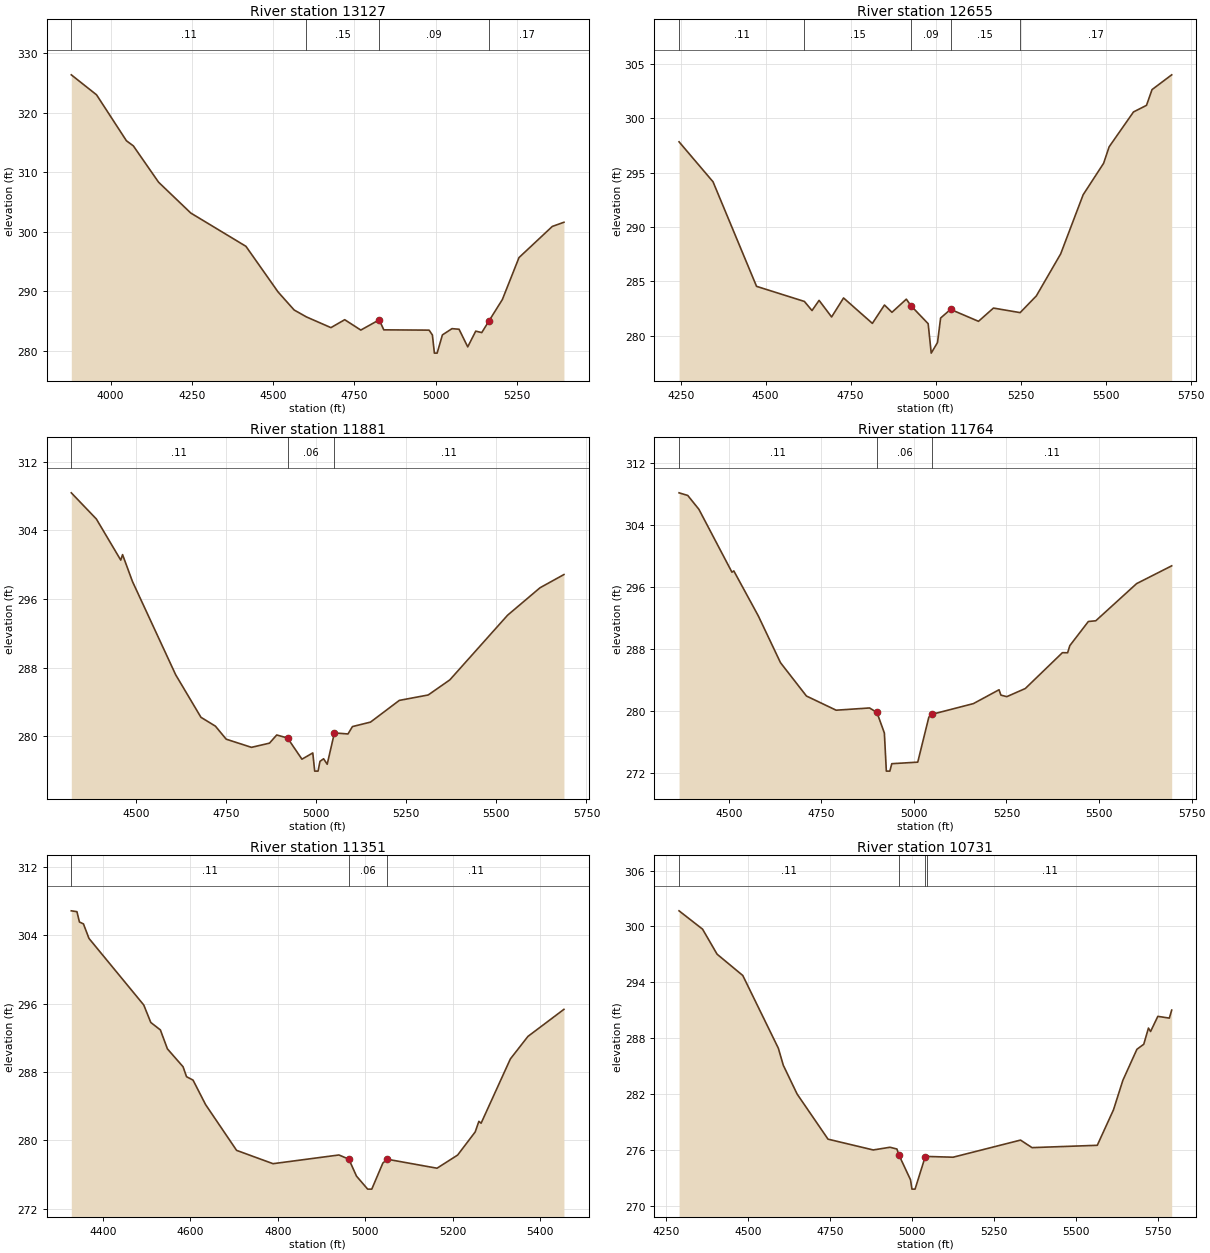
Type RM Length L Ch R = 1 ,13127   ,472,472,472
BEGIN DESCRIPTION:
LEE BRANCH 25.0
END DESCRIPTION:
XS GIS Cut Line= 3
      3743017.85     10224761.07       3742255.7     10224020.99
      3741812.97     10223921.16
#Sta/Elev= 30
  3878.8  326.35  3956.6  322.99  4048.5  315.28  4069.8  314.42  4147.5  308.32
  4246.5  303.15  4416.3  297.56  4515.3  289.89  4564.7  286.87  4602.4  285.71
  4677.9  283.91  4720.3  285.24  4769.9   283.5  4826.5  285.22  4840.6  283.54
    4980  283.49  4990.2  282.67  4996.3  279.63  5004.7  279.63    5021  282.69
  5050.5  283.74  5072.2  283.64  5098.9  280.68  5123.5  283.32  5142.1  283.08
  5164.5  285.05  5205.5  288.63  5256.7  295.67  5359.2   300.9    5395   301.6
#Mann= 4 ,-1 , 0
  3878.8     .11       0  4602.4     .15       0  4826.5     .09       0
  5164.5     .17       0
Bank Sta=4826.5,5164.5
XS Rating Curve= 0 ,0
Exp/Cntr=0.3,0.1

Type RM Length L Ch R = 1 ,12655   ,774,774,774
BEGIN DESCRIPTION:
LEE BRANCH 24.0
END DESCRIPTION:
XS GIS Cut Line= 3
      3742917.86     10224111.08       3742330.7     10223636.95
      3741717.85     10223311.07
#Sta/Elev= 30
  4245.3  297.85  4345.2  294.17  4473.2  284.54  4613.9  283.15  4636.3  282.31
  4657.1  283.25  4693.9  281.72  4729.1  283.47  4813.8  281.13  4849.4  282.82
  4871.4  282.15  4913.7  283.36  4927.4  282.75  4977.9   281.1  4986.9  278.39
  5005.4  279.37  5014.5  281.62  5043.7  282.42  5125.9  281.32  5169.9  282.54
  5248.4  282.12    5296  283.66  5367.6  287.53  5433.6  292.97  5493.8  295.87
  5510.1  297.39  5581.7   300.6    5620  301.21  5636.3  302.66  5694.1  304.02
#Mann= 5 ,-1 , 0
  4245.3     .11       0  4613.9     .15       0  4927.4     .09       0
  5043.7     .15       0  5248.4     .17       0
Bank Sta=4927.4,5043.7
XS Rating Curve= 0 ,0
Exp/Cntr=0.3,0.1

Type RM Length L Ch R = 1 ,11881   ,117,117,117
BEGIN DESCRIPTION:
LEE BRANCH 23.0
END DESCRIPTION:
XS GIS Cut Line= 2
      3743297.37     10223022.73      3741931.51     10222957.69
#Sta/Elev= 30
    4320  308.36  4389.6  305.31  4457.3  300.52  4462.3  301.16  4489.7  298.04
  4609.8  287.16  4679.9  282.21    4720  281.18    4750  279.66  4820.1  278.71
  4870.1   279.2  4890.2  280.15  4920.2   279.8  4960.2  277.33  4990.3  278.06
  4995.6  275.94  5004.9  275.94  5010.3  277.08  5020.3  277.38  5030.3  276.74
  5050.3  280.39    5088  280.27  5100.4  281.13  5150.5  281.65  5230.5  284.18
  5310.6  284.81  5370.7  286.57  5530.9   294.1    5621   297.3  5687.4  298.84
#Mann= 3 , 0 , 0
    4320     .11       0  4920.2     .06       0  5050.3     .11       0
Bank Sta=4920.2,5050.3
XS Rating Curve= 0 ,0
Exp/Cntr=0.3,0.1

Type RM Length L Ch R = 1 ,11764   ,413,413,413
BEGIN DESCRIPTION:
LEE BRANCH 22.0
END DESCRIPTION:
XS GIS Cut Line= 2
      3743271.36     10222914.22      3741943.21     10222840.44
#Sta/Elev= 30
  4365.9  308.18  4389.4  307.84  4419.5  306.05  4508.7  297.93  4513.8  298.09
  4579.7   292.3  4639.8  286.24  4709.9  281.93  4790.1   280.1  4880.2  280.39
  4900.2  279.81  4920.3  277.15  4925.6  272.23    4935  272.23  4940.3  273.19
  5010.4  273.39  5040.4  279.21  5049.6  279.58  5160.6  280.95  5229.9  282.74
  5234.9  282.05  5250.8  281.85  5300.8   282.9    5401  287.53  5415.1  287.52
    5421  288.44  5471.1  291.56  5491.1  291.65  5601.3  296.45  5696.1  298.75
#Mann= 3 ,-1 , 0
  4365.9     .11       0  4900.2     .06       0  5049.6     .11       0
Bank Sta=4900.2,5049.6
XS Rating Curve= 0 ,0
Exp/Cntr=0.3,0.1

Type RM Length L Ch R = 1 ,11351   ,620,620,620
BEGIN DESCRIPTION:
LEE BRANCH 21.0
END DESCRIPTION:
XS GIS Cut Line= 3
      3743232.27     10222723.25      3742898.06     10222540.96
      3742155.91     10222467.18
#Sta/Elev= 30
    4328  306.89  4340.9  306.79  4346.6  305.58  4355.8  305.36  4368.4  303.66
  4493.7  295.86  4509.8  293.81  4531.7  292.94  4547.8  290.72  4583.6  288.62
  4591.5  287.46  4606.4  287.06  4635.1  284.19    4706  278.83  4789.3  277.27
    4940  278.29  4962.7   277.8  4980.2  275.81  5005.7  274.29  5015.1  274.29
  5040.5  277.35  5050.6  277.79  5164.3  276.74  5211.4  278.28  5251.6  280.99
    5260  282.23  5265.1  282.01    5332  289.54  5372.2  292.18  5454.5  295.35
#Mann= 3 ,-1 , 0
    4328     .11       0  4962.7     .06       0  5050.6     .11       0
Bank Sta=4962.7,5050.6
XS Rating Curve= 0 ,0
Exp/Cntr=0.3,0.1

Type RM Length L Ch R = 1 ,10731   ,186,186,186
BEGIN DESCRIPTION:
LEE BRANCH 20.0
END DESCRIPTION:
XS GIS Cut Line= 3
      3743267.84     10222611.06      3742878.39     10222017.28
      3742367.82     10221411.04
#Sta/Elev= 30
  4289.9  301.67  4361.6   299.7  4405.9  297.01  4484.3  294.72  4592.8   286.9
  4607.9  285.07    4650  281.98  4744.3  277.13  4882.2  275.97  4933.4  276.26
  4954.5  276.07  4960.5  275.43  4995.9  272.77  5000.3  271.76  5009.8  271.76
  5040.2  275.18  5047.3  275.27  5125.8  275.19  5331.5  277.03  5366.6  276.22
  5565.6  276.47    5615  280.28  5643.6  283.45  5686.5  286.79  5707.4  287.33
  5721.7  289.07  5728.2   288.7  5750.3  290.33  5785.4  290.14  5792.6     291
#Mann= 4 ,-1 , 0
  4289.9     .11       0  4960.5     .06       0  5040.2     .11       0
  5047.3     .11       0
Bank Sta=4960.5,5040.2
XS Rating Curve= 0 ,0
Exp/Cntr=0.3,0.1

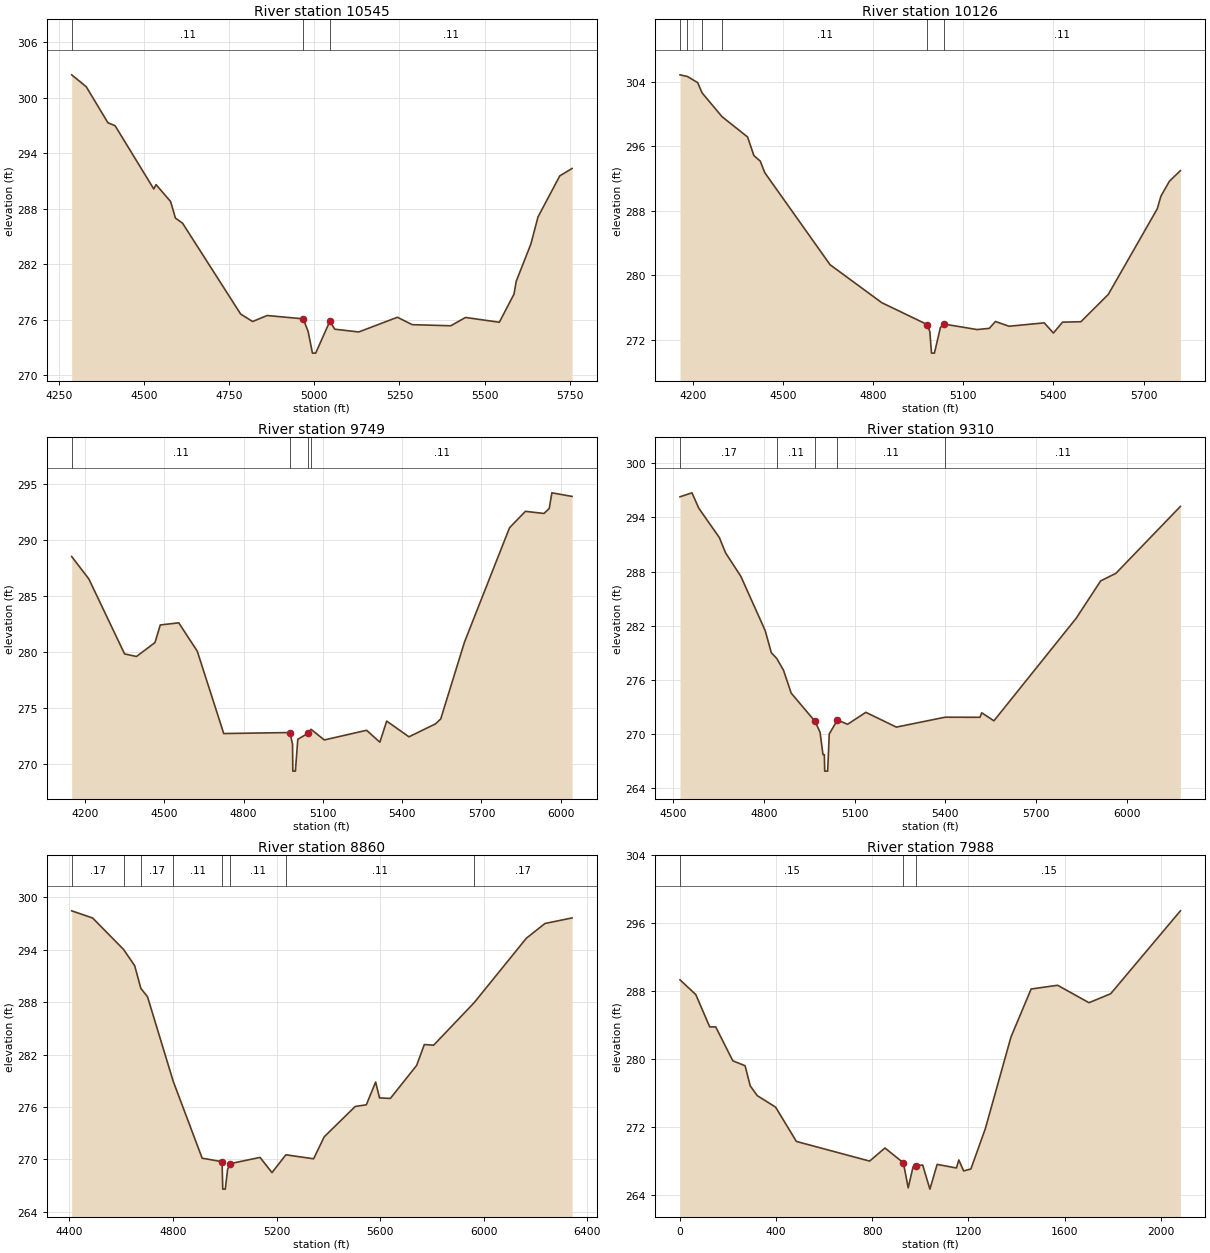
Type RM Length L Ch R = 1 ,10545   ,419,419,419
BEGIN DESCRIPTION:
LEE BRANCH 19.0
END DESCRIPTION:
XS GIS Cut Line= 3
      3743540.41     10222358.66      3743007.98     10221884.88
      3742417.85     10221411.07
#Sta/Elev= 30
  4287.3   302.5  4330.3   301.2  4393.8  297.31  4414.7     297  4528.4  290.15
  4535.1  290.62  4577.8  288.79    4592     287  4612.9  286.45  4783.5  276.62
  4818.6  275.81  4861.2  276.46  4967.4   276.1  4981.6  274.74  4994.4  272.39
  5003.9  272.39  5045.5  275.84  5059.9  274.98  5130.4  274.68    5244  276.27
  5287.2  275.47  5400.8  275.35    5444  276.25  5543.2  275.73  5586.4  278.78
  5592.8  280.16    5636  284.21  5656.8  287.13  5720.8  291.57  5756.8  292.37
#Mann= 3 , 0 , 0
  4287.3     .11       0  4967.4     .06       0  5045.5     .11       0
Bank Sta=4967.4,5045.5
XS Rating Curve= 0 ,0
Exp/Cntr=0.3,0.1

Type RM Length L Ch R = 1 ,10126   ,377,377,377
BEGIN DESCRIPTION:
LEE BRANCH 18.0
END DESCRIPTION:
XS GIS Cut Line= 3
      3743967.86     10222011.08       3743261.5     10221551.15
      3742451.97     10221403.98
#Sta/Elev= 30
  4157.1  304.85  4181.9  304.64    4216  303.88  4230.5  302.62  4296.8  299.67
    4382  297.15  4403.1  294.84  4424.2  294.16  4439.4  292.72  4656.7  281.32
  4828.7  276.62  4980.5   273.9  4988.7  273.03  4994.3  270.37    5004  270.37
  5023.7  273.51  5034.2  273.98    5146  273.29  5186.7  273.44    5207  274.29
  5252.4   273.7  5369.6  274.12  5400.1  272.86  5430.6  274.21  5491.6  274.26
  5582.7  277.64  5745.7  288.24  5758.1  289.83  5786.3  291.67  5822.8  292.98
#Mann= 6 ,-1 , 0
  4157.1     .17       0  4181.9     .11       0  4230.5     .17       0
  4296.8     .11       0  4980.5     .06       0  5034.2     .11       0
Bank Sta=4980.5,5034.2
XS Rating Curve= 0 ,0
Exp/Cntr=0.3,0.1

Type RM Length L Ch R = 1 ,9749    ,439,439,439
BEGIN DESCRIPTION:
LEE BRANCH 17.0
END DESCRIPTION:
XS GIS Cut Line= 3
      3744182.76     10221186.79      3743340.77     10221225.85
      3742291.62     10221286.55
#Sta/Elev= 30
  4149.1  288.52  4214.1  286.52  4349.3  279.84  4394.3  279.61  4464.3  280.85
  4484.4  282.42  4554.4  282.61  4624.5  280.08  4724.6  272.74  4974.9  272.83
  4984.9  271.81  4986.1  269.39  4995.8  269.39  5004.9  272.23    5045  272.78
    5055  273.12  5105.1  272.17  5265.4  273.03  5315.5  271.97  5341.3  273.85
  5425.6  272.45  5525.8   273.6  5545.8  274.04    5636  280.91  5806.3  291.09
  5866.4  292.55  5936.5  292.36  5956.5   292.8  5966.5   294.2  6042.9  293.88
#Mann= 4 ,-1 , 0
  4149.1     .11       0  4974.9     .06       0    5045     .11       0
    5055     .11       0
Bank Sta=4974.9,5045
XS Rating Curve= 0 ,0
Exp/Cntr=0.3,0.1

Type RM Length L Ch R = 1 ,9310    ,450,450,450
BEGIN DESCRIPTION:
LEE BRANCH 16.0
END DESCRIPTION:
XS GIS Cut Line= 3
      3743727.09     10220748.42      3743253.91     10220810.27
      3742086.42      10220961.1
#Sta/Elev= 30
  4522.8   296.3  4562.4  296.74  4584.7  295.04  4653.1  291.76  4673.3  290.08
  4723.7  287.48  4804.4  281.44  4824.6  278.99  4842.7  278.34  4864.9  277.04
  4890.3   274.5  4969.2  271.36  4985.9  270.14  4995.5  267.66    5000  267.66
  5001.2  265.83    5011  265.83  5016.2  269.96  5043.4  271.51  5076.7  271.03
  5137.2  272.36    5238  270.72  5399.4  271.82  5514.5  271.81  5520.4  272.31
  5560.7  271.42  5832.9  282.82  5913.6  286.96    5964   287.8  6177.2  295.23
#Mann= 5 ,-1 , 0
  4522.8     .17       0  4842.7     .11       0  4969.2     .06       0
  5043.4     .11       0  5399.4     .11       0
Bank Sta=4969.2,5043.4
XS Rating Curve= 0 ,0
Exp/Cntr=0.3,0.1

Type RM Length L Ch R = 1 ,8860    ,872,872,872
BEGIN DESCRIPTION:
LEE BRANCH 15.0
END DESCRIPTION:
XS GIS Cut Line= 4
      3743718.34     10220704.99      3743458.22     10220447.06
      3742708.12     10220157.15      3742079.13     10219725.07
#Sta/Elev= 30
  4408.5  298.45  4489.4  297.63    4609  294.03    4652  292.17  4675.7  289.58
  4701.6  288.61  4801.1  278.92  4912.7  270.14  4989.6  269.74  4992.3   266.6
  5002.1   266.6  5011.1  268.89  5021.8  269.52  5136.3  270.23  5182.6  268.49
  5236.2  270.53  5343.4  270.07  5384.4  272.59  5504.2  276.06  5547.1  276.25
  5583.1  278.86    5598  277.04    5640  276.98  5741.5  280.76  5771.3  283.15
  5807.1  283.07  5963.8  287.94  6165.7  295.32  6237.4     297  6342.1  297.64
#Mann= 8 ,-1 , 0
  4408.5     .17       0    4609     .11       0  4675.7     .17       0
  4801.1     .11       0  4989.6     .07       0  5021.8     .11       0
  5236.2     .11       0  5963.8     .17       0
Bank Sta=4989.6,5021.8
XS Rating Curve= 0 ,0
Exp/Cntr=0.3,0.1

Type RM Length L Ch R = 1 ,7988    ,210,210,210
XS GIS Cut Line= 3
      3744313.97     10219623.39      3743564.37     10219762.78
      3742248.55     10219662.71
#Sta/Elev= 30
       0  289.34    65.8   287.6   123.6   283.8   148.6   283.8   219.8  279.81
   270.7  279.23   292.1  276.87   321.5  275.71   397.7  274.36   484.3  270.32
     789  268.01   852.6  269.55   929.5  267.81   949.5  264.86   969.6  267.32
   983.7  267.45  1009.7  267.55  1039.8  264.71  1069.9  267.62  1150.1   267.2
  1160.1  268.14  1180.2  266.85  1210.3  267.08  1270.4  271.82  1377.1  282.61
    1461  288.26  1571.3   288.7  1701.7  286.65  1791.9   287.7  2082.1  297.46
#Mann= 3 , 0 , 0
       0     .15       0   929.5     .09       0   983.7     .15       0
Bank Sta=929.5,983.7
XS Rating Curve= 0 ,0
Exp/Cntr=0.3,0.1

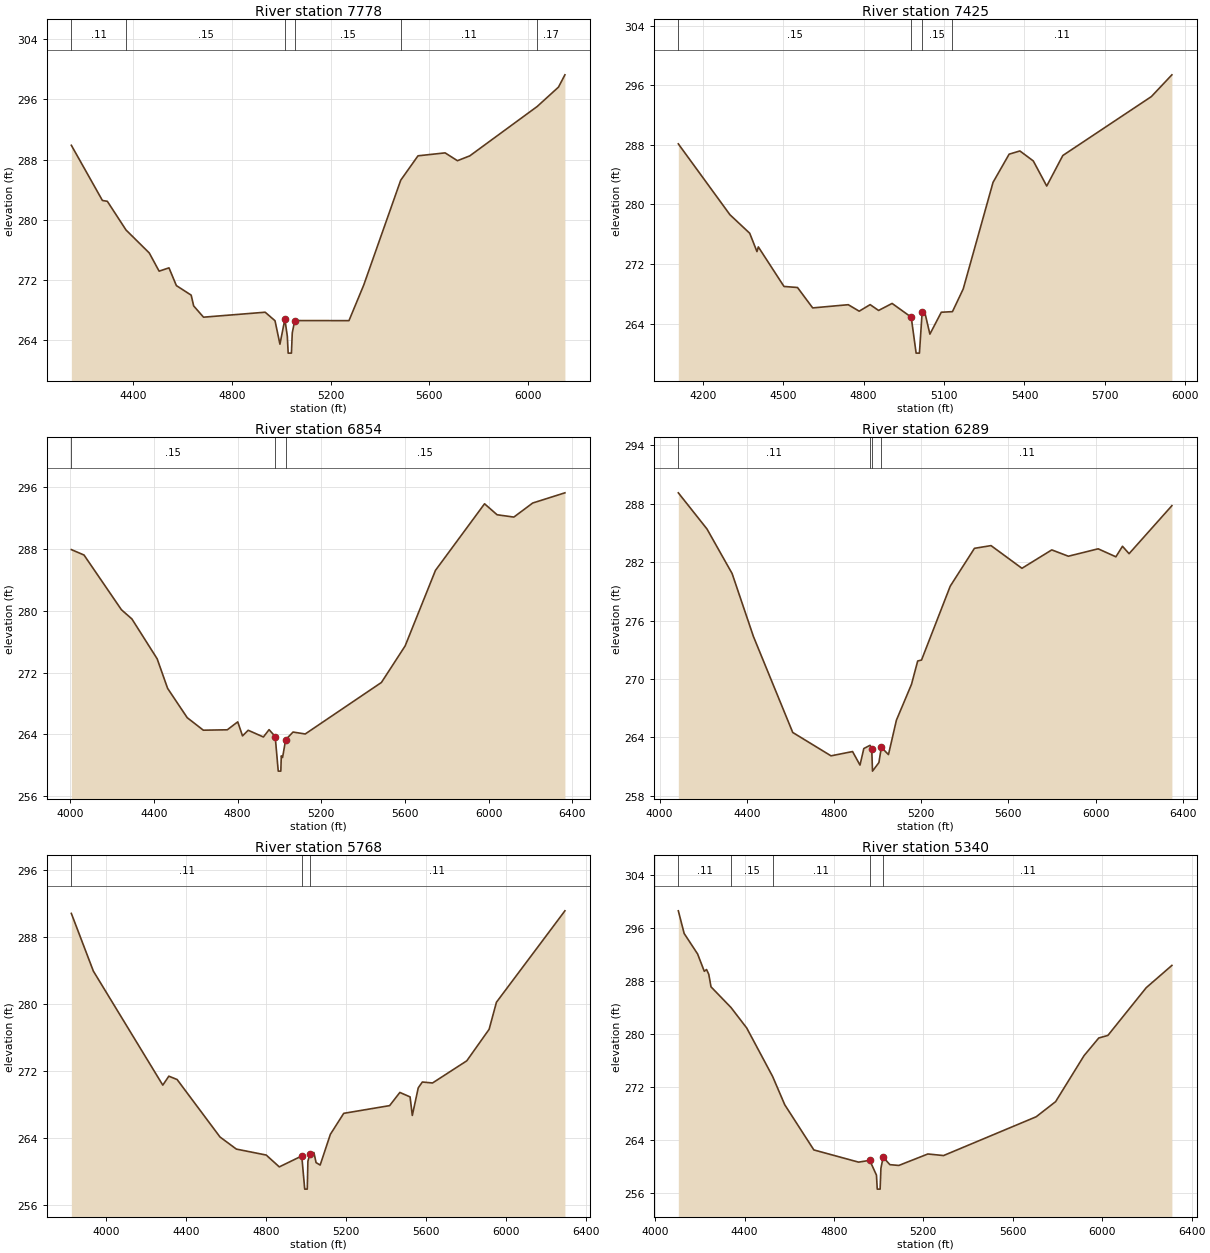
Type RM Length L Ch R = 1 ,7778    ,353,353,353
BEGIN DESCRIPTION:
LEE BRANCH 14.0
END DESCRIPTION:
XS GIS Cut Line= 3
       3744253.9     10219530.71      3743550.06     10219551.39
      3742251.88     10219519.89
#Sta/Elev= 30
  4148.2   289.9  4274.3  282.56  4294.3  282.45  4370.2  278.63  4464.4  275.58
  4504.4  273.16  4544.4   273.6  4574.4  271.24  4634.5  269.97  4644.5  268.54
  4684.5  267.04  4934.6   267.7  4974.6  266.57  4994.6  263.45  5014.6  266.77
  5024.6  264.49    5028  262.26  5041.2  262.26  5044.6  264.95  5054.6  266.59
  5274.7  266.58  5334.7  271.32  5484.6  285.25  5554.8   288.5  5664.8  288.89
  5714.8  287.85  5764.8  288.49  6038.5  295.06  6124.9  297.64  6150.9  299.27
#Mann= 6 ,-1 , 0
  4148.2     .11       0  4370.2     .15       0  5014.6     .09       0
  5054.6     .15       0  5484.6     .11       0  6038.5     .17       0
Bank Sta=5014.6,5054.6
XS Rating Curve= 0 ,0
Exp/Cntr=0.3,0.1

Type RM Length L Ch R = 1 ,7425    ,571,571,571
BEGIN DESCRIPTION:
LEE BRANCH 13.0
END DESCRIPTION:
XS GIS Cut Line= 3
      3744238.69     10219385.31      3743138.43     10219159.62
      3742421.44     10219129.29
#Sta/Elev= 30
  4109.1  288.12  4301.6  278.61  4375.4  276.12  4402.4  273.66  4407.5  274.29
  4503.2  268.98  4553.6  268.84  4610.2   266.1  4742.9  266.53  4783.7  265.66
  4824.5  266.54    4856  265.76  4906.4   266.7  4977.7  264.86    4996  260.03
  5008.3  260.03  5018.5  265.54  5028.7  265.45  5047.4  262.58  5089.9  265.52
  5131.5   265.6  5171.6  268.64  5282.9  282.96  5342.9  286.74    5383  287.17
    5433  285.83  5483.1  282.46  5543.1  286.56  5873.4  294.47  5949.9  297.39
#Mann= 4 ,-1 , 0
  4109.1     .15       0  4977.7     .09       0  5018.5     .15       0
  5131.5     .11       0
Bank Sta=4977.7,5018.5
XS Rating Curve= 0 ,0
Exp/Cntr=0.3,0.1

Type RM Length L Ch R = 1 ,6854    ,565,565,565
BEGIN DESCRIPTION:
LEE BRANCH 12.0
END DESCRIPTION:
XS GIS Cut Line= 3
      3744381.09     10219302.58      3742992.16     10218253.95
      3742374.12     10218281.72
#Sta/Elev= 30
  4005.1  287.92  4065.6  287.22  4244.6  280.13  4294.6  278.94  4415.3  273.78
  4465.3  269.95  4558.9  266.16  4635.9  264.54  4750.4  264.59  4800.4  265.62
  4823.2   263.8  4850.3  264.53  4923.1  263.66  4950.2  264.61  4979.4  263.72
    4994  259.24  5006.4  259.24  5008.5  261.22  5014.7     261  5029.3   263.3
  5064.7   264.3    5123  264.05  5487.2  270.72  5600.5  275.45  5745.4  285.23
    5980  293.85    6040  292.43  6120.1  292.13  6210.2  293.95  6364.1  295.27
#Mann= 3 , 0 , 0
  4005.1     .15       0  4979.4     .09       0  5029.3     .15       0
Bank Sta=4979.4,5029.3
XS Rating Curve= 0 ,0
Exp/Cntr=0.3,0.1

Type RM Length L Ch R = 1 ,6289    ,521,521,521
BEGIN DESCRIPTION:
LEE BRANCH 11.0
END DESCRIPTION:
XS GIS Cut Line= 3
      3744665.75     10218628.93      3743526.89     10218111.59
       3742523.4     10217969.22
#Sta/Elev= 30
    4086  289.12  4217.4  285.41  4332.8  280.83  4430.5  274.37  4610.9  264.51
  4786.6  262.11  4885.4  262.55  4919.5  261.16    4937  262.86  4965.6  263.19
  4973.3  262.85  4976.9  260.54  5006.3  261.42  5017.3  262.98  5050.2  262.24
  5086.5  265.77  5155.7  269.45  5184.2  271.85  5201.8  271.95  5333.6  279.54
  5444.6  283.42  5520.6   283.7  5662.5  281.37  5799.4  283.26  5875.4  282.61
  6012.2  283.37  6093.4  282.55  6123.7  283.63    6154  282.87  6350.4   287.8
#Mann= 4 ,-1 , 0
    4086     .11       0  4965.6     .11       0  4973.3     .07       0
  5017.3     .11       0
Bank Sta=4973.3,5017.3
XS Rating Curve= 0 ,0
Exp/Cntr=0.3,0.1

Type RM Length L Ch R = 1 ,5768    ,428,428,428
BEGIN DESCRIPTION:
LEE BRANCH 10.0
END DESCRIPTION:
XS GIS Cut Line= 3
      3745155.38     10218017.84      3743381.05     10217642.84
      3742732.32     10217733.03
#Sta/Elev= 30
  3827.5  290.77  3937.6   283.9  4284.9  270.31  4315.1  271.38  4356.5  270.98
  4571.1  264.13  4652.9  262.69  4802.2  261.98  4867.5  260.57  4979.9  261.87
  4994.7  257.92  5007.4  257.92  5010.6  261.23  5020.8  262.16  5040.6  262.28
  5051.5  261.08  5071.9  260.79    5123  264.45  5189.8  266.95  5419.4  267.87
  5470.5  269.44  5521.6  268.91  5532.8   266.7  5562.5  269.99    5583  270.68
  5634.1  270.57  5805.3  273.21  5916.9  276.96  5953.6  280.19    6296  291.08
#Mann= 3 , 0 , 0
  3827.5     .11       0  4979.9     .06       0  5020.8     .11       0
Bank Sta=4979.9,5020.8
XS Rating Curve= 0 ,0
Exp/Cntr=0.3,0.1

Type RM Length L Ch R = 1 ,5340    ,258,258,258
BEGIN DESCRIPTION:
LEE BRANCH 9.0
END DESCRIPTION:
XS GIS Cut Line= 3
      3744954.01     10217354.64      3743353.28     10217358.11
      3742756.03     10217465.76
#Sta/Elev= 30
    4104  298.61  4130.2  295.19  4190.2  292.11  4220.2  289.49  4230.2  289.76
  4240.2  289.04  4250.2  287.15  4339.7  284.03  4410.2  280.93  4525.9  273.63
  4580.2  269.36  4710.2  262.56  4910.2  260.72  4960.2  260.99  4990.2  258.76
  4993.8  256.65  5006.6  256.65  5010.2   259.8  5020.2  261.47  5050.2  260.34
  5090.2  260.22  5220.2  261.95  5290.2  261.71  5704.7  267.56  5791.5  269.84
  5918.6  276.77  5984.6  279.44  6025.2  279.82  6196.8  287.02  6311.6  290.38
#Mann= 5 ,-1 , 0
    4104     .11       0  4339.7     .15       0  4525.9     .11       0
  4960.2     .06       0  5020.2     .11       0
Bank Sta=4960.2,5020.2
XS Rating Curve= 0 ,0
Exp/Cntr=0.3,0.1