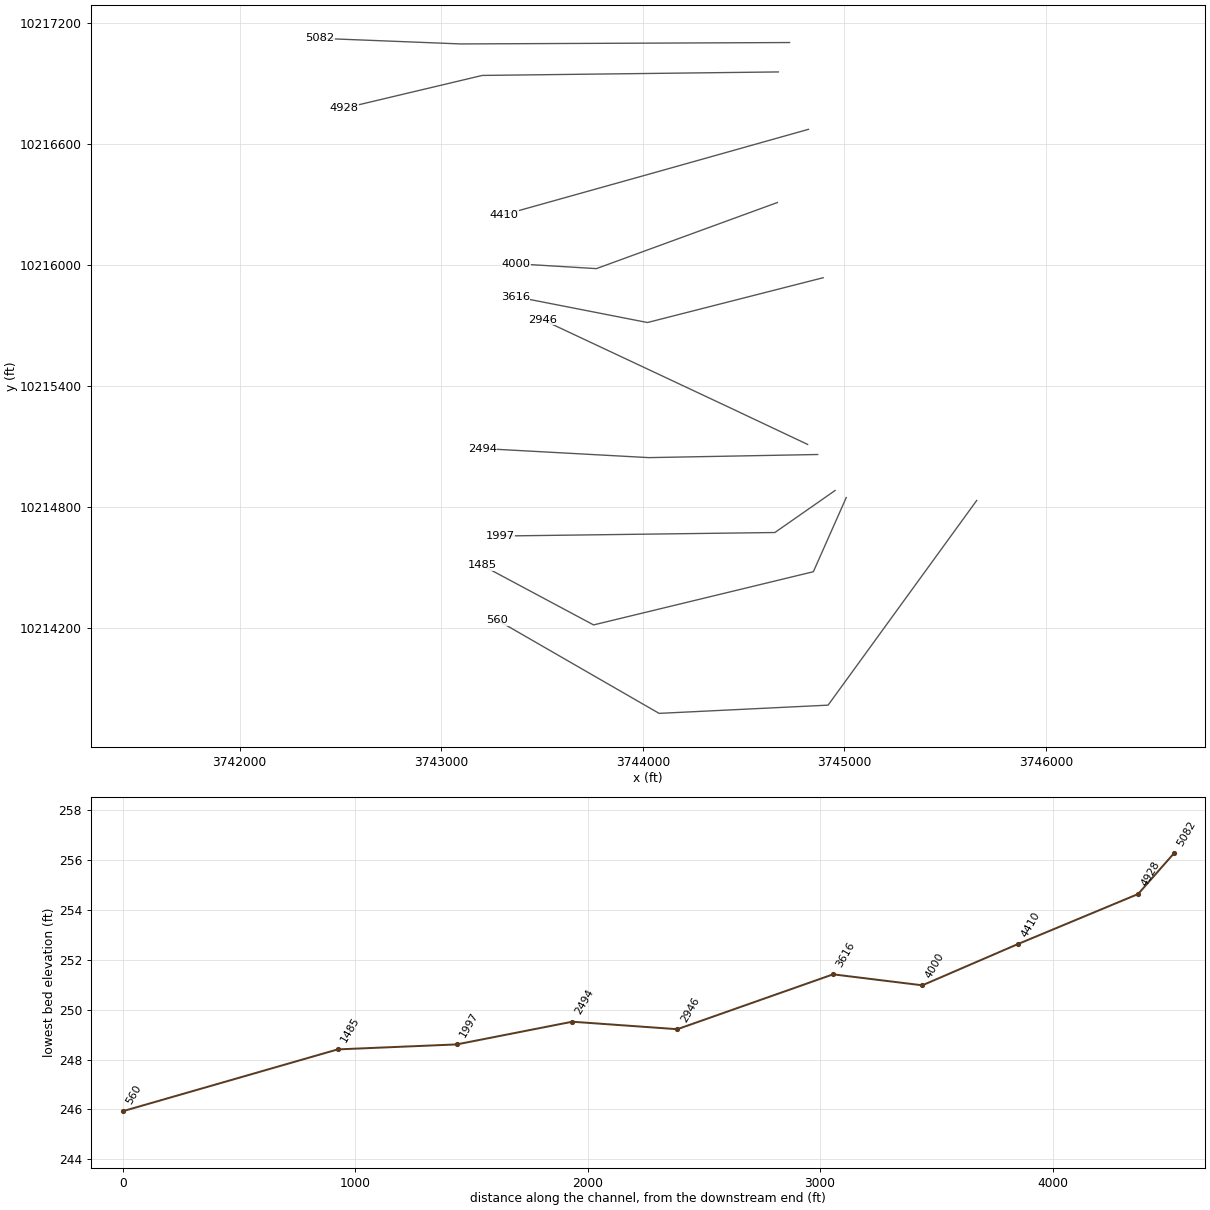
HEC-RAS study LEE BRANCH.prj: LEE BRANCH Base Level Engineering

--- LEE BRANCH.g01 (geometry) --- (continued)

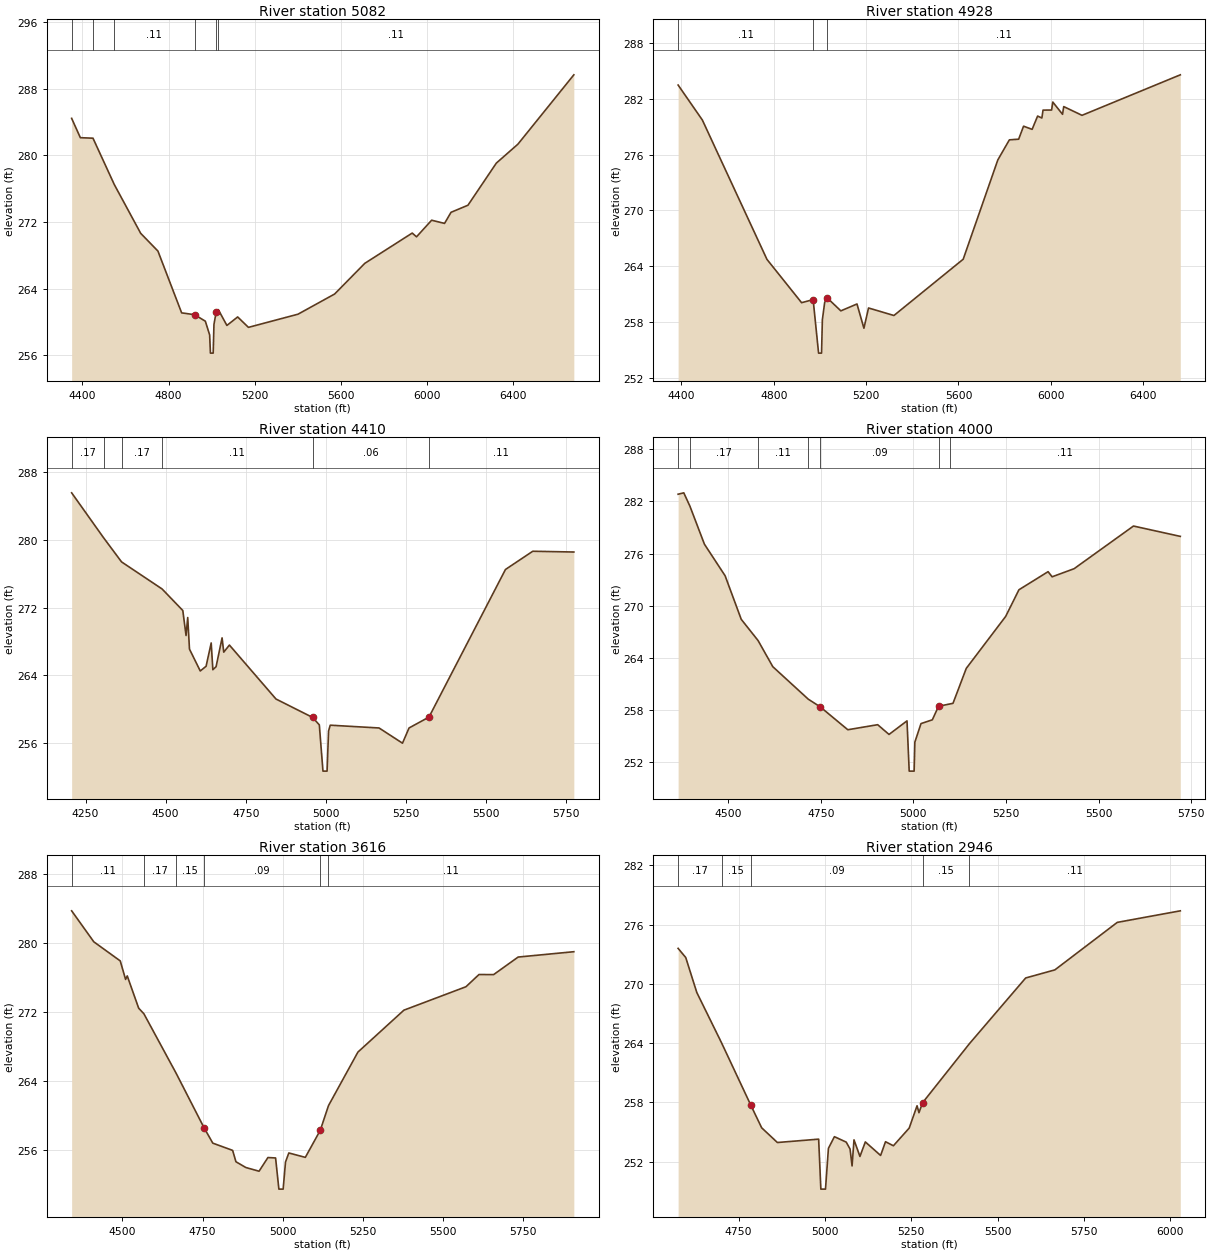
Type RM Length L Ch R = 1 ,5082    ,154,154,154
BEGIN DESCRIPTION:
Mapping XS 1a99942d
END DESCRIPTION:
XS GIS Cut Line= 3
      3744728.27     10217104.64      3743096.33      10217097.7
      3742398.43     10217125.47
#Sta/Elev= 30
  4350.1  284.43  4390.5  282.11  4449.1  282.05  4547.8   276.5  4670.5  270.64
  4750.5  268.51  4860.5   261.1  4920.5  260.88  4970.5   260.1  4990.5  258.45
  4994.1  256.27  5006.9  256.27  5010.5  259.71  5020.5  261.16  5030.5  261.49
  5070.5  259.59  5120.5  260.61  5170.5  259.36  5400.5  260.94  5570.5  263.36
  5710.5  267.04  5930.5  270.67  5950.5  270.22  6020.6  272.21  6080.6  271.83
  6110.6  273.16  6189.2  274.01  6320.8  279.06  6420.9  281.33  6680.5  289.65
#Mann= 6 ,-1 , 0
  4350.1     .11       0  4449.1     .15       0  4547.8     .11       0
  4920.5     .06       0  5020.5     .09       0  5030.5     .11       0
Bank Sta=4920.5,5020.5
XS Rating Curve= 0 ,0
Exp/Cntr=0.3,0.1

Type RM Length L Ch R = 1 ,4928    ,518,518,518
BEGIN DESCRIPTION:
LEE BRANCH 8.0
END DESCRIPTION:
XS GIS Cut Line= 3
      3744672.73     10216958.81      3743203.97     10216941.45
      3742516.44     10216778.24
#Sta/Elev= 30
  4385.5   283.5  4490.4  279.74  4770.4  264.73  4920.4  260.07  4970.4   260.4
    4994  254.64  5006.8  254.64  5010.4  258.23  5020.4  260.09  5030.4  260.61
  5090.4  259.19  5160.4  259.93  5190.4  257.32  5210.4   259.5  5320.4  258.69
  5620.5  264.75  5770.5  275.44  5820.5   277.6  5860.7  277.67    5882  279.07
  5919.1  278.73  5942.9  280.16  5961.3  279.95  5966.4   280.8  6003.5  280.81
  6008.6  281.67  6050.8  280.35    6056  281.18  6135.2  280.24    6561   284.6
#Mann= 3 ,-1 , 0
  4385.5     .11       0  4970.4     .06       0  5030.4     .11       0
Bank Sta=4970.4,5030.4
XS Rating Curve= 0 ,0
Exp/Cntr=0.3,0.1

Type RM Length L Ch R = 1 ,4410    ,410,410,410
BEGIN DESCRIPTION:
LEE BRANCH 7.0
END DESCRIPTION:
XS GIS Cut Line= 3
      3744822.02     10216674.08      3744058.05     10216459.25
      3743312.27     10216250.66
#Sta/Elev= 30
  4206.4  285.59  4305.9  280.28  4362.2  277.41  4488.9   274.2  4553.5  271.65
  4563.6  268.69  4568.8  270.82  4574.3  267.08    4608  264.49  4626.2  265.05
  4642.1  267.81  4647.3  264.64  4657.4     265  4676.1  268.41  4681.3  266.72
    4699  267.56  4844.4  261.17  4958.7  258.99  4979.7  258.11  4991.1  252.63
  5003.9  252.63  5008.6  257.39  5013.8  258.07  5166.3  257.74  5239.4  255.94
  5259.8  257.74  5322.1  259.03  5560.9  276.51  5646.1  278.67  5774.4  278.58
#Mann= 6 ,-1 , 0
  4206.4     .17       0  4305.9     .11       0  4362.2     .17       0
  4488.9     .11       0  4958.7     .06       0  5322.1     .11       0
Bank Sta=4958.7,5322.1
XS Rating Curve= 0 ,0
Exp/Cntr=0.3,0.1

Type RM Length L Ch R = 1 ,4000    ,384,384,384
BEGIN DESCRIPTION:
LEE BRANCH 6.0
END DESCRIPTION:
XS GIS Cut Line= 3
      3744667.83     10216311.06      3743769.94     10215983.11
      3743371.79     10216007.35
#Sta/Elev= 30
  4365.3  282.83  4380.6  282.99  4397.1  281.46  4436.3  277.08  4492.1  273.45
  4535.6  268.44    4581     266  4620.8  262.99  4716.6  259.25  4748.5  258.38
  4823.1  255.74  4903.7  256.32  4934.3   255.2  4982.8  256.76  4988.7  250.98
    5002  250.98    5004  254.32  5020.6  256.45  5051.1  256.88  5067.9  258.44
  5099.9  258.72  5106.9  258.78  5142.7   262.8  5248.9  268.77  5284.8  271.84
  5363.4  273.92  5374.2  273.33  5433.5  274.26  5593.8  279.17  5720.1  277.98
#Mann= 7 ,-1 , 0
  4365.3     .11       0  4397.1     .17       0    4581     .11       0
  4716.6     .15       0  4748.5     .09       0  5067.9     .15       0
  5099.9     .11       0
Bank Sta=4748.5,5067.9
XS Rating Curve= 0 ,0
Exp/Cntr=0.3,0.1

Type RM Length L Ch R = 1 ,3616    ,670,670,670
BEGIN DESCRIPTION:
LEE BRANCH 5.0
END DESCRIPTION:
XS GIS Cut Line= 3
      3744894.94     10215937.97      3744023.41     10215715.75
      3743367.18     10215844.22
#Sta/Elev= 30
  4341.4  283.75  4410.6  280.15  4493.2  277.93  4509.8  275.78    4515  276.19
  4550.7  272.44    4567  271.79  4667.8  264.87  4755.1  258.53  4782.2  256.76
  4844.1  255.92  4854.4   254.6  4885.4  253.93  4926.6   253.5  4954.3  255.09
  4978.2  255.04  4988.5  251.42  5001.8  251.42  5009.2  254.57  5019.5  255.62
  5071.1  255.11  5117.8  258.26  5143.4  261.12  5235.3  267.34  5378.9  272.21
  5572.6  274.93  5613.3  276.35    5659  276.34  5735.6  278.38  5909.5     279
#Mann= 6 ,-1 , 0
  4341.4     .11       0    4567     .17       0  4667.8     .15       0
  4755.1     .09       0  5117.8     .15       0  5143.4     .11       0
Bank Sta=4755.1,5117.8
XS Rating Curve= 0 ,0
Exp/Cntr=0.3,0.1

Type RM Length L Ch R = 1 ,2946    ,452,452,452
BEGIN DESCRIPTION:
LEE BRANCH 4.0
END DESCRIPTION:
XS GIS Cut Line= 3
      3744817.85     10215111.07      3744433.75     10215292.52
      3743502.73     10215729.57
#Sta/Elev= 30
  4575.2   273.6  4597.3  272.67  4629.3  269.13  4701.1  264.02  4785.3  257.74
    4817  255.43  4862.5  253.94  4981.9  254.28  4988.3  249.22  5001.7  249.22
  5010.2  253.35  5027.5  254.53  5061.7  253.98  5072.8  253.28  5078.6  251.57
  5084.2  254.21  5101.4  252.53    5117     254  5161.2  252.63  5175.4  254.02
  5198.2  253.61  5243.9   255.4  5266.7  257.66  5272.2  256.96  5282.7  257.97
  5418.3  263.95    5581   270.6  5665.5  271.42  5846.1  276.23  6028.5   277.4
#Mann= 5 ,-1 , 0
  4575.2     .17       0  4701.1     .15       0  4785.3     .09       0
  5282.7     .15       0  5418.3     .11       0
Bank Sta=4785.3,5282.7
XS Rating Curve= 0 ,0
Exp/Cntr=0.3,0.1

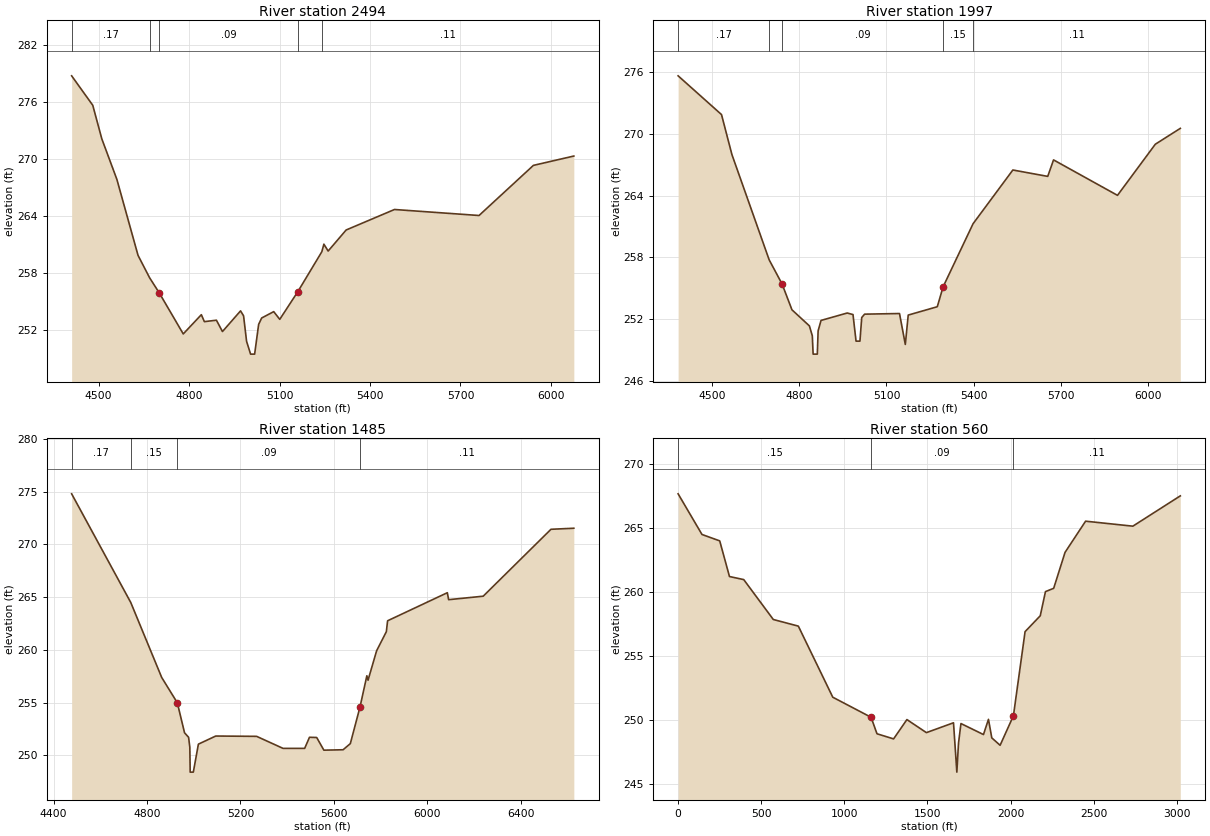
Type RM Length L Ch R = 1 ,2494    ,497,497,497
BEGIN DESCRIPTION:
LEE BRANCH 3.0
END DESCRIPTION:
XS GIS Cut Line= 3
      3744867.86     10215061.07      3744030.36     10215045.61
      3743203.94     10215090.75
#Sta/Elev= 30
  4410.6  278.73  4480.6  275.64  4510.6  272.12  4560.6  267.86  4630.7  259.89
    4669  257.54  4700.7  255.97  4780.7  251.64  4840.7  253.66  4850.7  252.93
  4890.7  253.08  4910.7  251.89  4970.7  254.06  4980.7  253.54  4990.7  250.86
    5004  249.52  5017.4  249.52  5030.7  252.64  5040.7  253.31  5080.7  253.98
  5100.7  253.17  5160.7  256.08  5240.3  260.27    5247  261.06  5261.2  260.34
  5320.9  262.55  5481.1   264.7  5761.5  264.07  5941.8  269.33  6075.9  270.31
#Mann= 5 ,-1 , 0
  4410.6     .17       0    4669     .15       0  4700.7     .09       0
  5160.7     .15       0  5240.3     .11       0
Bank Sta=4700.7,5160.7
XS Rating Curve= 0 ,0
Exp/Cntr=0.3,0.1

Type RM Length L Ch R = 1 ,1997    ,512,512,512
BEGIN DESCRIPTION:
LEE BRANCH 2.0
END DESCRIPTION:
XS GIS Cut Line= 3
        3744954.     10214882.44      3744655.36     10214674.09
      3743291.81     10214656.74
#Sta/Elev= 30
  4383.2  275.62  4532.5  271.86  4568.3  267.98  4696.5  257.76    4741  255.41
  4774.9  252.91  4834.9  251.35  4844.9  250.39  4847.7  248.61  4862.1  248.61
  4864.9  250.87  4874.9  251.88  4964.9   252.6  4984.9  252.45  4995.4  249.87
  5008.8  249.87  5014.9  252.16  5024.9  252.49  5144.9  252.55  5164.9  249.55
  5174.9   252.4  5274.9  253.21  5294.9  255.14  5398.1  261.27  5534.9  266.48
  5654.9  265.86  5674.9  267.46  5894.9  264.02    6025  268.98    6111  270.52
#Mann= 5 ,-1 , 0
  4383.2     .17       0  4696.5     .15       0    4741     .09       0
  5294.9     .15       0  5398.1     .11       0
Bank Sta=4741,5294.9
XS Rating Curve= 0 ,0
Exp/Cntr=0.3,0.1

Type RM Length L Ch R = 1 ,1485    ,925,925,925
BEGIN DESCRIPTION:
LEE BRANCH 1.0
END DESCRIPTION:
XS GIS Cut Line= 4
      3745009.54     10214847.72      3744846.33     10214479.64
      3743756.05     10214215.75      3743203.99     10214510.88
#Sta/Elev= 30
  4477.5  274.78  4730.5  264.49  4863.1  257.38    4930  254.98  4960.9  252.14
  4978.3  251.71  4983.5  250.77  4985.1  248.41  4998.5  248.41  5020.2  251.06
  5094.6  251.83  5269.6   251.8  5382.7  250.66  5475.3  250.66  5495.9  251.71
  5526.8  251.69  5557.6  250.49  5639.9  250.53  5670.8  251.11    5712  254.56
  5741.6  257.54  5746.7  257.12  5783.4  259.91  5825.1  261.72  5830.4  262.75
  6086.2  265.41  6091.8  264.75  6239.8  265.08    6530  271.42  6627.9  271.52
#Mann= 4 ,-1 , 0
  4477.5     .17       0  4730.5     .15       0    4930     .09       0
    5712     .11       0
Bank Sta=4930,5712
XS Rating Curve= 0 ,0
Exp/Cntr=0.3,0.1

Type RM Length L Ch R = 1 ,560     ,0,0,0
XS GIS Cut Line= 4
       3745656.6     10214833.11      3744919.43      10213817.8
      3744081.13     10213776.96      3743277.84     10214239.87
#Sta/Elev= 30
       0   267.7   143.6  264.52   250.3  264.02     309  261.23   394.8  260.99
   572.6  257.87   723.3  257.35   930.5  251.79  1160.9  250.22  1196.4  248.93
  1296.3  248.53  1376.4  250.04  1493.7  249.02  1656.7  249.79  1676.8  245.93
  1686.8  248.19  1701.5  249.73    1837  248.87    1867  250.06    1887  248.61
  1937.1  248.03  2017.2  250.34  2087.3  256.92  2178.6  258.16  2209.9  260.05
  2259.4  260.31  2327.7  263.12  2451.3  265.56  2735.7  265.17  3021.1  267.54
#Mann= 3 , 0 , 0
       0     .15       0  1160.9     .09       0  2017.2     .11       0
Bank Sta=1160.9,2017.2
XS Rating Curve= 0 ,0
Exp/Cntr=0.3,0.1

Chan Stop Cuts=-1
Use User Specified Reach Order=0
Composite Channel Slope=5