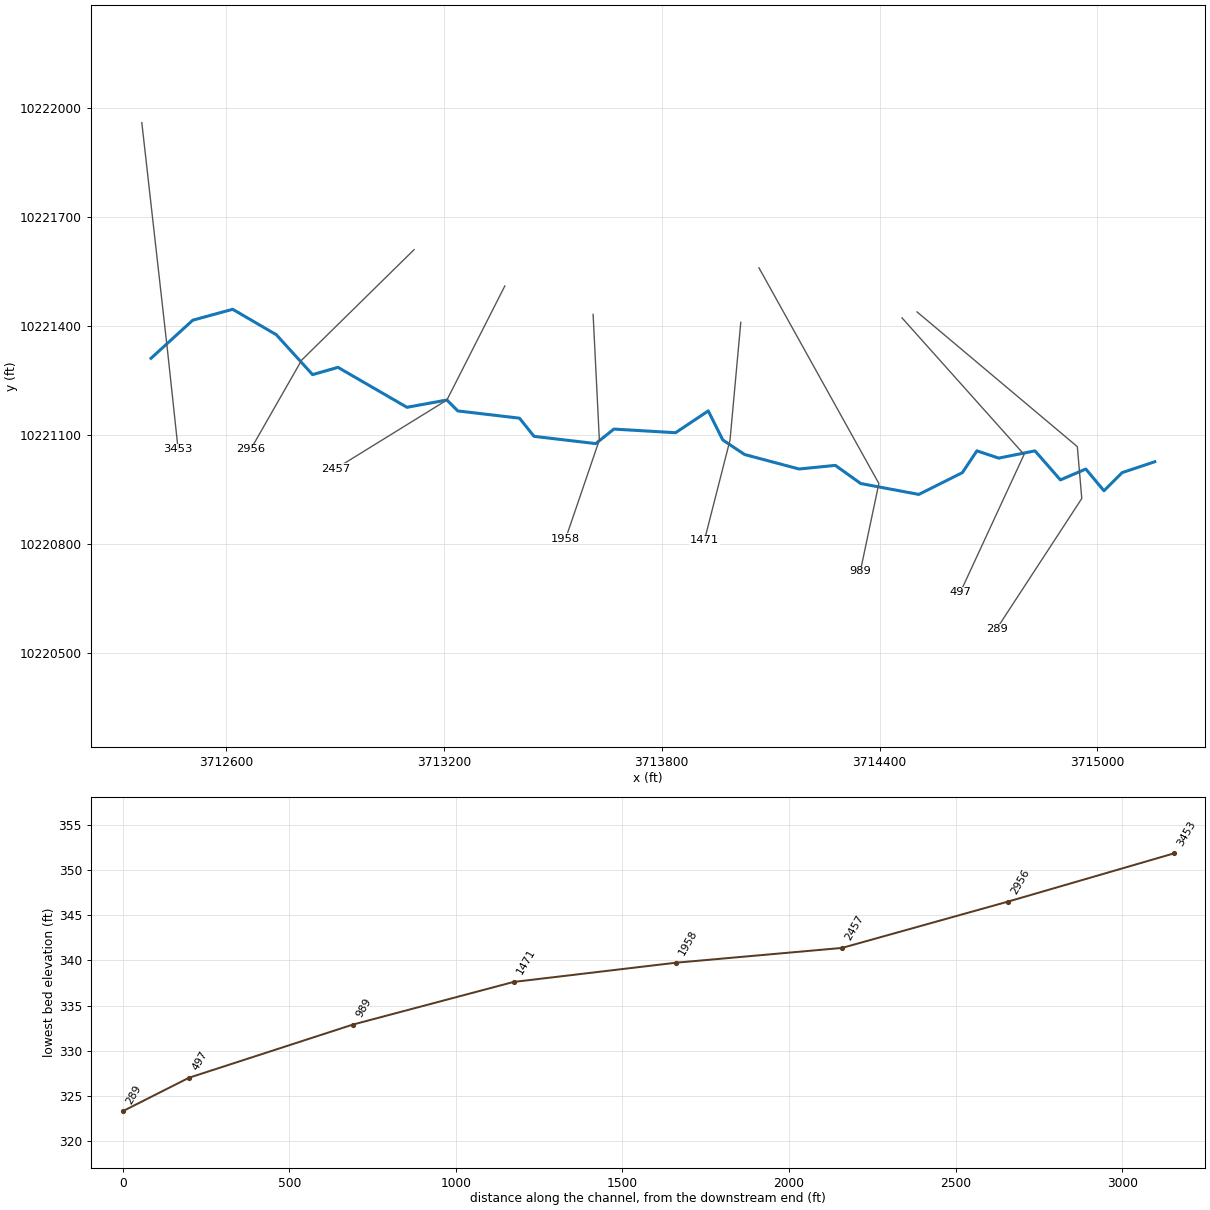
--- LUCAS BRANCH.prj (project) ---

Proj Title=LUCAS BRANCH Base Level Engineering
Current Plan=p01
Default Exp/Contr=0.3,0.1
English Units
Geom File=g01
Flow File=f01
Flow File=f02
Plan File=p01
Y Axis Title=Elevation
X Axis Title(PF)=Main Channel Distance
X Axis Title(XS)=Station
BEGIN DESCRIPTION:
LUCAS BRANCH
END DESCRIPTION:
DSS Export Rating Curves= 0
DSS Export Rating Curve Sorted= 0
DSS Export Volume Flow Curves= 0
DXF OffsetX= 0
DXF OffsetY= 0
DXF ScaleX= 1
DXF ScaleY= 10

--- LUCAS BRANCH.p01 (plan) ---

Plan Title=Multiple Run
Program Version=4.10
Short Identifier=Multiple
Geom File=g01
Flow File=f01
Subcritical Flow
K Sum by GR= 0
Std Step Tol= 0.01
Critical Tol= 0.01
Num of Std Step Trials= 20
Max Error Tol= 0.3
Flow Tol Ratio= 0.001
Split Flow NTrial= 30
Split Flow Tol= 0.02
Split Flow Ratio= 0.02
Log Output Level= 0
Friction Slope Method= 1
Unsteady Friction Slope Method= 2
Unsteady Bridges Friction Slope Method= 1
Parabolic Critical Depth
Global Vel Dist= 1 , 1 , 1
Global Log Level= 0
CheckData=True
Encroach Param=-1 ,0,0, 0
BEGIN DESCRIPTION:
Multiple Run
END DESCRIPTION:
Computation Interval=1HOUR
Output Interval=1HOUR
Run HTab= 0
Run UNet= 0
Run PostProcess= 0
Run WQNet= 0
UNET Theta= 1
UNET Theta Warmup= 1
UNET ZTol= 0.02
UNET ZSATol= 0.05
UNET MxIter= 20
UNET MaxInSteps= 0
UNET DtIC= 0
UNET DtMin= 0
UNET MaxCRTS= 20
UNET WFStab= 2
UNET SFStab= 1
UNET WFX= 1
UNET SFX= 1
UNET DSS MLevel= 4
UNET DZMax Abort= 100
UNET Convert EG Bridges= 0
UNET Use Existing IB Tables=-1
UNET Froude Reduction=False
UNET Froude Limit= 1
UNET Froude Power= 10
UNET Time Slicing=0,0, 5
UNET Junction Losses=0
Instantaneous Interval=1HOUR
Write IC File= 0
Write IC File at Sim End=0
Echo Input=False
Echo Parameters=False
Echo Output=False
Write Detailed= 0
WQ AD Non Conservative
WQ ULTIMATE=-1
WQ Max Comp Step=1HOUR
WQ Output Interval=15MIN
WQ Output Selected Increments= 0
WQ Output face flow=0
WQ Output face velocity=0
WQ Output face area=0
WQ Output face dispersion=0
WQ Output cell volume=0
WQ Output cell surface area=0
WQ Output cell continuity=0
WQ Output cumulative cell continuity=0
WQ Output face conc=0
WQ Output face dconc_dx=0
WQ Output face courant=0
WQ Output face peclet=0
WQ Output face adv mass=0
WQ Output face disp mass=0
WQ Output cell mass=0
WQ Output cell source sink temp=0
WQ Output cell source sink nsm=0
WQ Output MaxMinRange=-1
WQ Daily Max Min Mean=-1
WQ Daily Range=0
WQ Daily Time=0
WQ Create Restart=0
WQ Fixed Restart=0
WQ System Summary=0
WQ Use Fixed Temperature=0
Sorting and Armoring Iterations= 10
XS Update Threshold= 0.02
Hydraulics Update Threshold= 0.02
Energy Slope Method= 1
Volume Change Method= 0
XS Weighting Method= 0
Number of US Weighted Cross Sections= 1
Number of DS Weighted Cross Sections= 1
Upstream XS Weight=0.25
Main XS Weight=0.5
Downstream XS Weight=0.25
Number of DS XS's Weighted with US Boundary= 1
Upstream Boundary Weight= 1
Weight of XSs Associated with US Boundary= 0
Number of US XS's Weighted with DS Boundary= 1
Downstream Boundary Weight= 0.5
Weight of XSs Associated with DS Boundary= 0.5
Sediment Output Level= 4
Mass or Volume Output= 0
Output Increment Type= 1
Profile and TS Output Increment= 10
XS Output Flag= 0
XS Output Increment= 10
Disregard all LS=0
Disregard all Conn=0
Disregard all Breaches=0
Disregard all Pumps=0

--- LUCAS BRANCH.f01 (steady flow) ---

Flow Title=Multiple
Program Version=4.10
Number of Profiles= 7
Profile Names=10-year,25-year,50-year,1pct_min,100-year,1pct_plu,500-year
River Rch & RM=LUCAS BRANCH,Reach-1         ,3453
     700     969    1328     601    1814    5478    3490
Boundary for River Rch & Prof#=LUCAS BRANCH,Reach-1         , 1
Up Type= 0
Dn Type= 3
Dn Slope=0.02
Boundary for River Rch & Prof#=LUCAS BRANCH,Reach-1         , 2
Up Type= 0
Dn Type= 3
Dn Slope=0.02
Boundary for River Rch & Prof#=LUCAS BRANCH,Reach-1         , 3
Up Type= 0
Dn Type= 3
Dn Slope=0.02
Boundary for River Rch & Prof#=LUCAS BRANCH,Reach-1         , 4
Up Type= 0
Dn Type= 3
Dn Slope=0.02
Boundary for River Rch & Prof#=LUCAS BRANCH,Reach-1         , 5
Up Type= 0
Dn Type= 3
Dn Slope=0.02
Boundary for River Rch & Prof#=LUCAS BRANCH,Reach-1         , 6
Up Type= 0
Dn Type= 3
Dn Slope=0.02
Boundary for River Rch & Prof#=LUCAS BRANCH,Reach-1         , 7
Up Type= 0
Dn Type= 3
Dn Slope=0.02
DSS Import GetInterval= 0
DSS Import GetPeak= 0
DSS Import FillOption= 0

--- LUCAS BRANCH.f02 (steady flow) ---

Flow Title=Orig_BLE_Flow
Program Version=4.10
Number of Profiles= 7
Profile Names=10-year,25-year,50-year,1pct_min,100-year,1pct_plu,500-year
River Rch & RM=LUCAS BRANCH,Reach-1         ,3453
     700     950    1155     462    1395    4212    2029
Boundary for River Rch & Prof#=LUCAS BRANCH,Reach-1         , 1
Up Type= 0
Dn Type= 3
Dn Slope=0.019
Boundary for River Rch & Prof#=LUCAS BRANCH,Reach-1         , 2
Up Type= 0
Dn Type= 3
Dn Slope=0.019
Boundary for River Rch & Prof#=LUCAS BRANCH,Reach-1         , 3
Up Type= 0
Dn Type= 3
Dn Slope=0.019
Boundary for River Rch & Prof#=LUCAS BRANCH,Reach-1         , 4
Up Type= 0
Dn Type= 3
Dn Slope=0.019
Boundary for River Rch & Prof#=LUCAS BRANCH,Reach-1         , 5
Up Type= 0
Dn Type= 3
Dn Slope=0.019
Boundary for River Rch & Prof#=LUCAS BRANCH,Reach-1         , 6
Up Type= 0
Dn Type= 3
Dn Slope=0.019
Boundary for River Rch & Prof#=LUCAS BRANCH,Reach-1         , 7
Up Type= 0
Dn Type= 3
Dn Slope=0.019
DSS Import GetInterval= 0
DSS Import GetPeak= 0
DSS Import FillOption= 0

--- LUCAS BRANCH.g01 (geometry) ---

Geom Title=Existing Conditions
Program Version=4.10

River Reach=LUCAS BRANCH    ,Reach-1
Reach XY= 30
      3712393.23     10221311.84      3712508.23     10221416.84
      3712618.23     10221446.84      3712738.23     10221376.84
      3712838.23     10221266.84      3712908.23     10221286.84
      3713098.23     10221176.84      3713208.23     10221196.84
      3713238.23     10221166.84      3713408.23     10221146.84
      3713448.23     10221096.84      3713618.23     10221076.84
      3713668.23     10221116.84      3713838.23     10221106.84
      3713928.23     10221166.84      3713968.23     10221086.84
      3714028.23     10221046.84      3714178.23     10221006.84
      3714278.23     10221016.84      3714348.23     10220966.84
      3714508.23     10220936.84      3714628.23     10220996.84
      3714668.23     10221056.84      3714728.23     10221036.84
      3714828.23     10221056.84      3714898.23     10220976.84
      3714968.23     10221006.84      3715018.23     10220946.84
      3715068.23     10220996.84      3715158.23     10221026.84

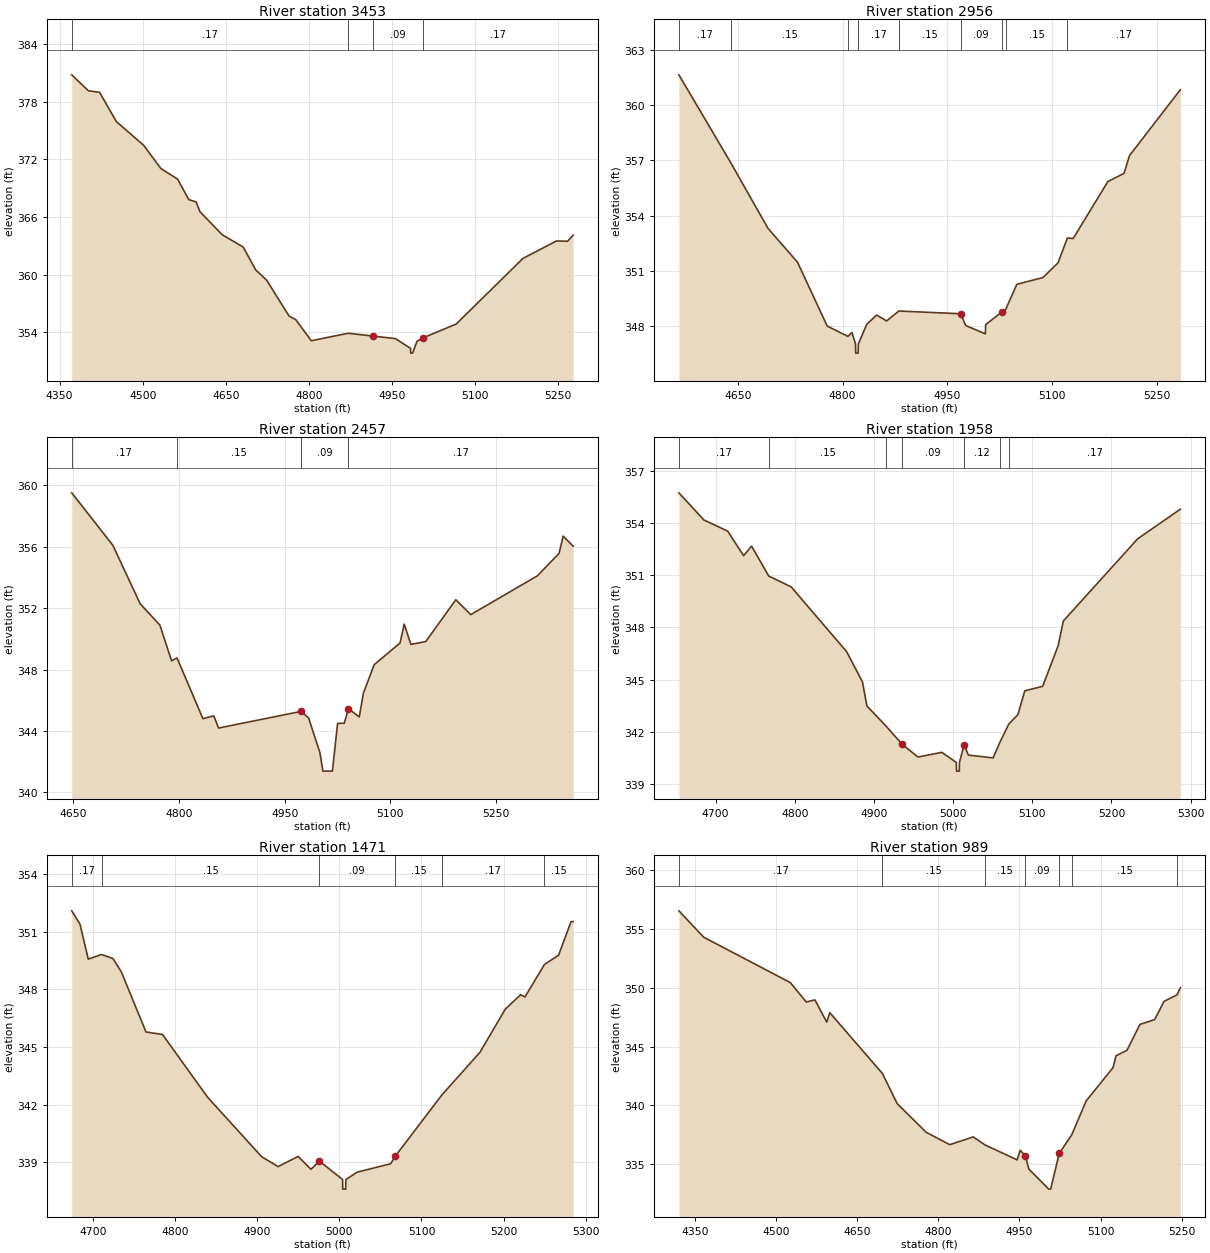
Type RM Length L Ch R = 1 ,3453    ,497,497,497
BEGIN DESCRIPTION:
LUCAS BRANCH 7.0
END DESCRIPTION:
XS GIS Cut Line= 3
      3712367.85     10221961.09      3712438.23     10221336.84
      3712467.86     10221061.03
#Sta/Elev= 30
  4371.8  380.81    4402  379.15  4422.1  378.99  4452.3  375.95  4501.7  373.48
  4532.8  371.06    4563  369.96  4583.1  367.83  4596.6  367.58  4603.3  366.57
  4643.5  364.17  4681.5  362.89  4703.9  360.52    4724  359.43  4764.3  355.71
  4776.4  355.33  4804.5  353.14    4871  353.92  4915.2  353.63  4956.3  353.36
  4983.7  352.35  4983.9  351.85  4987.4  351.85  4995.4  353.09  5005.8  353.43
  5066.2  354.88  5186.8  361.71  5247.2  363.52  5267.3  363.49  5277.4  364.14
#Mann= 4 ,-1 , 0
  4371.8     .17       0    4871     .15       0  4915.2     .09       0
  5005.8     .17       0
Bank Sta=4915.2,5005.8
XS Rating Curve= 0 ,0
Exp/Cntr=0.3,0.1

Type RM Length L Ch R = 1 ,2956    ,499,499,499
BEGIN DESCRIPTION:
LUCAS BRANCH 6.0
END DESCRIPTION:
XS GIS Cut Line= 3
      3713117.87     10221611.09      3712808.23     10221306.84
      3712667.87      10221061.1
#Sta/Elev= 30
  4565.9  361.65  4640.4  356.85  4693.2  353.31  4735.6  351.46    4778  347.99
  4807.6  347.43  4813.4  347.64  4818.5  347.02  4818.7  346.52  4822.2  346.52
  4822.5  347.02  4834.6  348.09  4848.7  348.59  4862.9  348.27  4880.5  348.81
    4969  348.66    4976  348.02  5004.1  347.57  5004.6  348.07  5027.5  348.75
  5033.2  348.89  5049.1  350.26  5086.5  350.63  5108.1  351.43  5121.5  352.78
  5129.7  352.75  5179.4  355.85  5202.4  356.29  5210.3  357.26    5283  360.84
#Mann= 9 ,-1 , 0
  4565.9     .17       0  4640.4     .15       0  4807.6     .17       0
  4822.5     .17       0  4880.5     .15       0    4969     .09       0
  5027.5     .12       0  5033.2     .15       0  5121.5     .17       0
Bank Sta=4969,5027.5
XS Rating Curve= 0 ,0
Exp/Cntr=0.3,0.1

Type RM Length L Ch R = 1 ,2457    ,499,499,499
BEGIN DESCRIPTION:
LUCAS BRANCH 5.0
END DESCRIPTION:
XS GIS Cut Line= 3
      3713367.83     10221511.03      3713208.23     10221196.84
       3712902.1     10221007.79
#Sta/Elev= 30
  4647.6  359.52    4706   356.1  4744.9  352.28  4772.8   350.9  4789.4  348.57
  4797.1  348.76  4833.9   344.8  4849.4  344.98  4856.2  344.19  4973.1  345.27
    4984  344.85    5000   342.6  5004.4  341.38  5017.8  341.38  5025.2  344.49
  5034.7   344.5  5040.6  345.45    5056  344.91  5061.8  346.46  5077.2  348.32
  5113.9  349.73  5119.8  350.96  5129.3  349.64  5150.5  349.83  5193.1  352.55
  5214.4  351.58  5308.9  354.11  5339.7  355.57  5345.6   356.7  5359.8  356.04
#Mann= 4 ,-1 , 0
  4647.6     .17       0  4797.1     .15       0  4973.1     .09       0
  5040.6     .17       0
Bank Sta=4973.1,5040.6
XS Rating Curve= 0 ,0
Exp/Cntr=0.3,0.1

Type RM Length L Ch R = 1 ,1958    ,487,487,487
BEGIN DESCRIPTION:
LUCAS BRANCH 4.0
END DESCRIPTION:
XS GIS Cut Line= 3
      3713611.04     10221432.72      3713628.23     10221086.84
       3713535.4     10220815.16
#Sta/Elev= 30
  4653.7  355.72  4685.3  354.16  4715.4  353.52  4735.4  352.11  4745.5  352.66
  4767.2  350.94  4795.5  350.32  4865.6   346.6  4885.6  344.86  4891.2  343.48
  4915.7  342.31  4935.7  341.28  4955.7  340.55  4985.8  340.82  5004.1  340.24
  5004.4  339.74  5007.9  339.74  5008.1  340.24    5014  341.26  5019.3  340.66
  5050.6   340.5  5058.9  341.37  5070.4  342.44  5081.9  342.98  5090.6  344.35
  5113.2  344.61  5132.9  346.96  5139.3  348.36  5233.2  353.08  5287.1  354.78
#Mann= 7 ,-1 , 0
  4653.7     .17       0  4767.2     .15       0  4915.7     .12       0
  4935.7     .09       0    5014     .12       0  5058.9     .15       0
  5070.4     .17       0
Bank Sta=4935.7,5014
XS Rating Curve= 0 ,0
Exp/Cntr=0.3,0.1

Type RM Length L Ch R = 1 ,1471    ,482,482,482
BEGIN DESCRIPTION:
LUCAS BRANCH 3.0
END DESCRIPTION:
XS GIS Cut Line= 3
      3714017.85     10221411.09      3713988.23     10221086.84
      3713917.85     10220811.08
#Sta/Elev= 30
  4674.4  352.08  4684.5  351.38  4694.5  349.57  4710.7  349.81  4724.5   349.6
  4734.7  348.91  4764.8  345.78  4784.9  345.65  4839.7  342.39  4905.4   339.3
  4925.5  338.78  4949.9  339.31  4965.6  338.64  4975.7  339.07    5004  338.11
  5004.2  337.61  5007.7  337.61    5008  338.11  5021.6  338.49  5062.5  338.93
  5067.9  339.31  5124.9  342.51  5171.1  344.72    5202  346.97  5220.7  347.72
  5225.9   347.6  5249.6  349.29  5266.8  349.77    5282  351.52  5284.6  351.52
#Mann= 6 ,-1 , 0
  4674.4     .17       0  4710.7     .15       0  4975.7     .09       0
  5067.9     .15       0  5124.9     .17       0  5249.6     .15       0
Bank Sta=4975.7,5067.9
XS Rating Curve= 0 ,0
Exp/Cntr=0.3,0.1

Type RM Length L Ch R = 1 ,989     ,492,492,492
BEGIN DESCRIPTION:
LUCAS BRANCH 2.0
END DESCRIPTION:
XS GIS Cut Line= 3
      3714067.85     10221561.08      3714398.23     10220966.84
      3714347.03      10220724.6
#Sta/Elev= 30
  4320.1  356.55  4365.9  354.31  4526.1  350.45  4555.7   348.8  4571.7  348.98
  4593.5  347.09  4599.2  347.89  4696.6  342.72  4723.8  340.16  4777.6  337.72
  4821.1  336.67  4864.5  337.33  4886.3  336.65  4945.7  335.38  4951.4  336.19
  4960.8  335.73  4967.5  334.59  5004.2  332.89  5007.7  332.89  5023.6  335.93
  5046.8  337.51  5073.4  340.39  5123.1  343.22  5128.6  344.22    5149   344.7
  5172.8  346.89  5200.1   347.3  5217.4  348.85  5241.5  349.41  5247.6  350.02
#Mann= 7 ,-1 , 0
  4320.1     .17       0  4696.6     .15       0  4886.3     .15       0
  4960.8     .09       0  5023.6     .15       0  5046.8     .15       0
  5241.5     .17       0
Bank Sta=4960.8,5023.6
XS Rating Curve= 0 ,0
Exp/Cntr=0.3,0.1

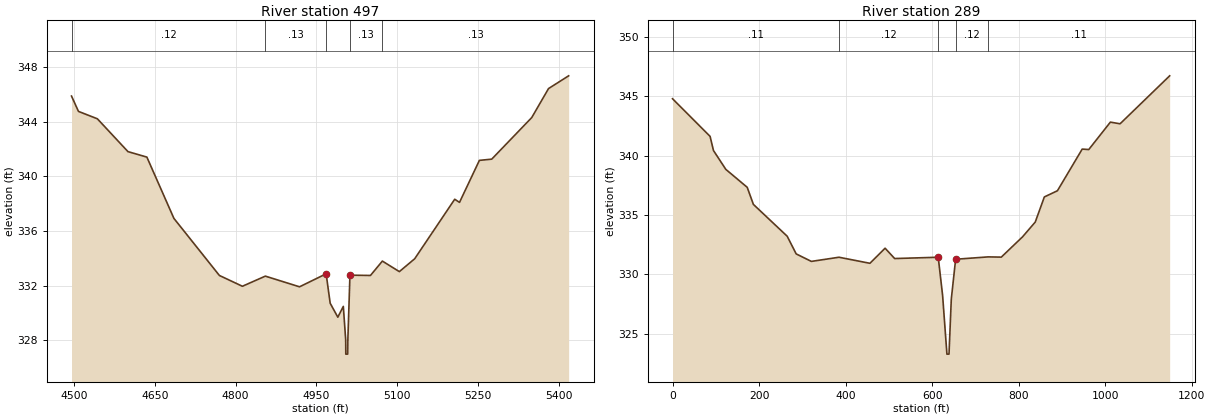
Type RM Length L Ch R = 1 ,497     ,199,199,199
BEGIN DESCRIPTION:
LUCAS BRANCH 1.0
END DESCRIPTION:
XS GIS Cut Line= 3
        3714462.      10221423.1      3714798.23     10221046.84
      3714622.58     10220667.21
#Sta/Elev= 30
  4495.4  345.86  4508.3  344.74  4543.4   344.2  4600.2   341.8  4635.3   341.4
  4685.5  336.92  4769.9  332.75  4812.6  331.96  4855.2   332.7  4918.7  331.92
  4968.1  332.87  4975.6  330.72  4989.8   329.7    5000  330.49  5004.4  328.05
  5004.6     327  5008.1     327  5008.4  328.05  5012.3  332.77  5050.4  332.75
  5072.5   333.8    5104  333.03  5132.5  333.97  5206.8  338.32  5215.7  338.09
  5252.6  341.16  5275.5  341.25  5349.8  344.29    5381  346.41  5418.3  347.34
#Mann= 5 ,-1 , 0
  4495.4     .12       0  4855.2     .13       0  4968.1     .08       0
  5012.3     .13       0  5072.5     .13       0
Bank Sta=4968.1,5012.3
XS Rating Curve= 0 ,0
Exp/Cntr=0.3,0.1

Type RM Length L Ch R = 1 ,289     ,0,0,0
XS GIS Cut Line= 4
      3714503.51     10221439.51      3714944.91     10221068.41
      3714957.16     10220925.55      3714722.26     10220565.81
#Sta/Elev= 30
       0   344.8    86.8  341.63    94.6  340.44   123.2  338.85   172.6  337.34
   186.9   335.9     265  333.22   285.8  331.73   320.9   331.1   384.7  331.45
   456.2  330.94   491.3  332.21   513.4  331.34   614.1  331.45   624.2  328.24
   634.2  323.29     639  323.29   644.3  327.92   654.3  331.28   729.7  331.48
   759.9  331.46     809  333.17   838.3  334.41   859.4  336.53   889.6  337.05
   946.9  340.56     962  340.52    1012  342.83  1034.4  342.69    1149  346.73
#Mann= 5 ,-1 , 0
       0     .11       0   384.7     .12       0   614.1     .06       0
   654.3     .12       0   729.7     .11       0
Bank Sta=614.1,654.3
XS Rating Curve= 0 ,0
Exp/Cntr=0.3,0.1

Chan Stop Cuts=-1
Use User Specified Reach Order=0
Composite Channel Slope=5