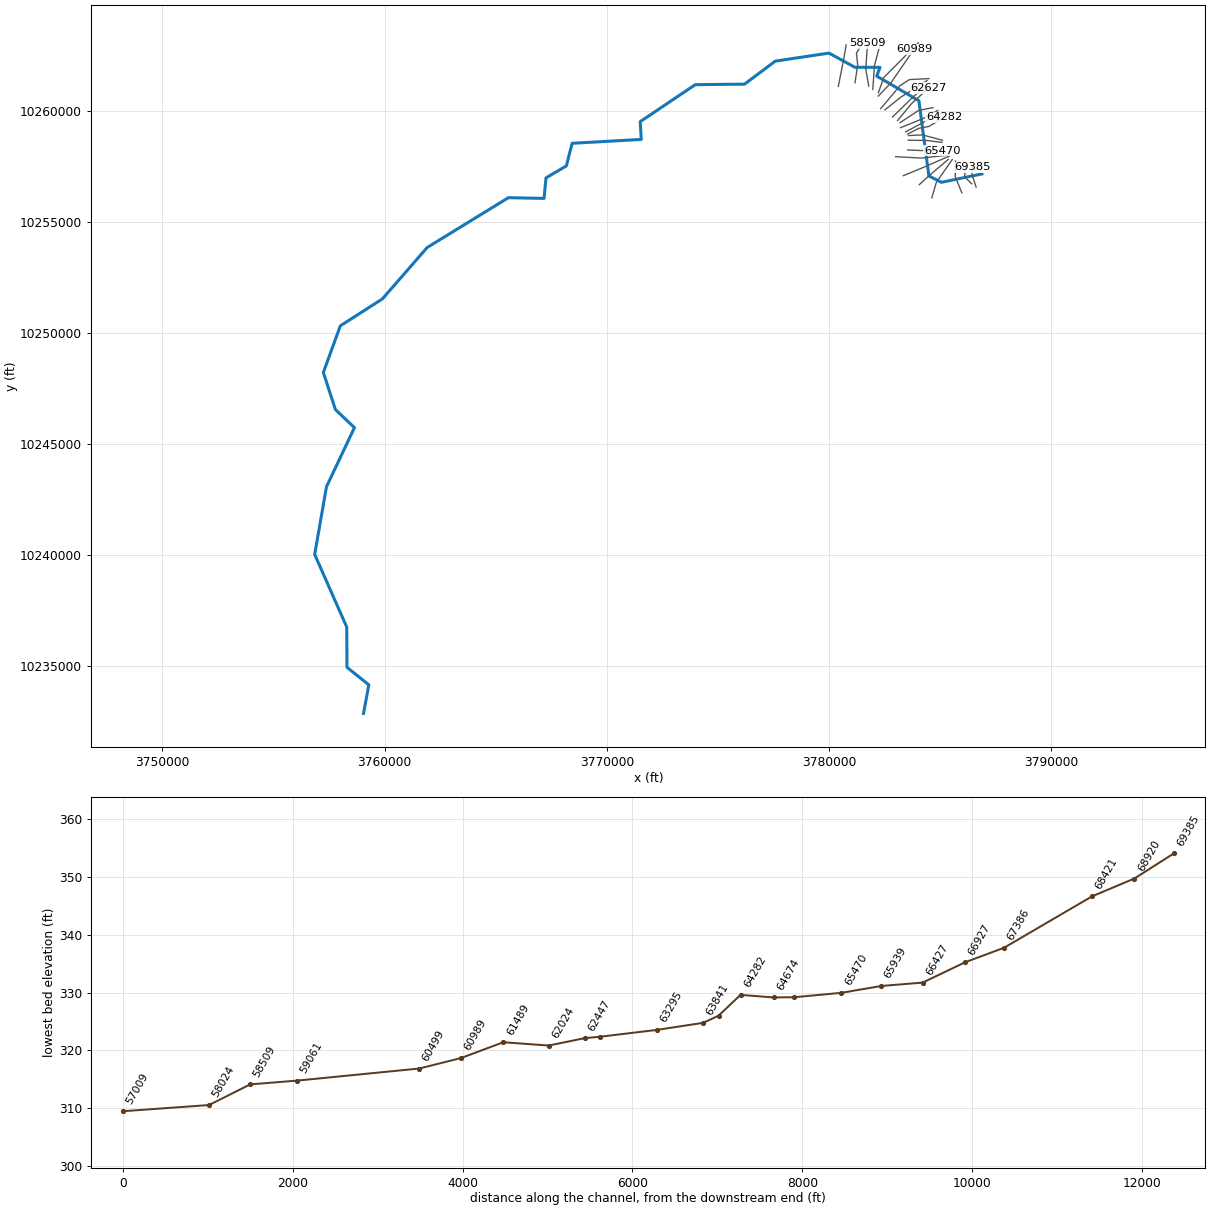
--- MCGARY CREEK.prj (project) ---

Proj Title=MCGARY CREEK Base Level Engineering
Current Plan=p01
Default Exp/Contr=0.3,0.1
English Units
Geom File=g01
Flow File=f01
Plan File=p01
Y Axis Title=Elevation
X Axis Title(PF)=Main Channel Distance
X Axis Title(XS)=Station
BEGIN DESCRIPTION:
MCGARY CREEK
END DESCRIPTION:
DSS Export Rating Curves= 0
DSS Export Rating Curve Sorted= 0
DSS Export Volume Flow Curves= 0
DXF OffsetX= 0
DXF OffsetY= 0
DXF ScaleX= 1
DXF ScaleY= 10

--- MCGARY CREEK.p01 (plan) ---

Plan Title=Multiple Run
Program Version=4.10
Short Identifier=Multiple
Geom File=g01
Flow File=f01
Subcritical Flow
K Sum by GR= 0
Std Step Tol= 0.01
Critical Tol= 0.01
Num of Std Step Trials= 20
Max Error Tol= 0.3
Flow Tol Ratio= 0.001
Split Flow NTrial= 30
Split Flow Tol= 0.02
Split Flow Ratio= 0.02
Log Output Level= 0
Friction Slope Method= 1
Unsteady Friction Slope Method= 2
Unsteady Bridges Friction Slope Method= 1
Parabolic Critical Depth
Global Vel Dist= 1 , 1 , 1
Global Log Level= 0
CheckData=True
Encroach Param=-1 ,0,0, 0
BEGIN DESCRIPTION:
Multiple Run
END DESCRIPTION:
Computation Interval=1HOUR
Output Interval=1HOUR
Run HTab= 0
Run UNet= 0
Run PostProcess= 0
Run WQNet= 0
UNET Theta= 1
UNET Theta Warmup= 1
UNET ZTol= 0.02
UNET ZSATol= 0.05
UNET MxIter= 20
UNET MaxInSteps= 0
UNET DtIC= 0
UNET DtMin= 0
UNET MaxCRTS= 20
UNET WFStab= 2
UNET SFStab= 1
UNET WFX= 1
UNET SFX= 1
UNET DSS MLevel= 4
UNET DZMax Abort= 100
UNET Convert EG Bridges= 0
UNET Use Existing IB Tables=-1
UNET Froude Reduction=False
UNET Froude Limit= 1
UNET Froude Power= 10
UNET Time Slicing=0,0, 5
UNET Junction Losses=0
Instantaneous Interval=1HOUR
Write IC File= 0
Write IC File at Sim End=0
Echo Input=False
Echo Parameters=False
Echo Output=False
Write Detailed= 0
WQ AD Non Conservative
WQ ULTIMATE=-1
WQ Max Comp Step=1HOUR
WQ Output Interval=15MIN
WQ Output Selected Increments= 0
WQ Output face flow=0
WQ Output face velocity=0
WQ Output face area=0
WQ Output face dispersion=0
WQ Output cell volume=0
WQ Output cell surface area=0
WQ Output cell continuity=0
WQ Output cumulative cell continuity=0
WQ Output face conc=0
WQ Output face dconc_dx=0
WQ Output face courant=0
WQ Output face peclet=0
WQ Output face adv mass=0
WQ Output face disp mass=0
WQ Output cell mass=0
WQ Output cell source sink temp=0
WQ Output cell source sink nsm=0
WQ Output MaxMinRange=-1
WQ Daily Max Min Mean=-1
WQ Daily Range=0
WQ Daily Time=0
WQ Create Restart=0
WQ Fixed Restart=0
WQ System Summary=0
WQ Use Fixed Temperature=0
Sorting and Armoring Iterations= 10
XS Update Threshold= 0.02
Hydraulics Update Threshold= 0.02
Energy Slope Method= 1
Volume Change Method= 0
XS Weighting Method= 0
Number of US Weighted Cross Sections= 1
Number of DS Weighted Cross Sections= 1
Upstream XS Weight=0.25
Main XS Weight=0.5
Downstream XS Weight=0.25
Number of DS XS's Weighted with US Boundary= 1
Upstream Boundary Weight= 1
Weight of XSs Associated with US Boundary= 0
Number of US XS's Weighted with DS Boundary= 1
Downstream Boundary Weight= 0.5
Weight of XSs Associated with DS Boundary= 0.5
Sediment Output Level= 4
Mass or Volume Output= 0
Output Increment Type= 1
Profile and TS Output Increment= 10
XS Output Flag= 0
XS Output Increment= 10
Disregard all LS=0
Disregard all Conn=0
Disregard all Breaches=0
Disregard all Pumps=0

--- MCGARY CREEK.f01 (steady flow) ---

Flow Title=Multiple
Program Version=4.10
Number of Profiles= 7
Profile Names=10-year,25-year,50-year,1pct_min,100-year,1pct_plu,500-year
River Rch & RM=MCGARY CREEK,Reach-1         ,69385
    1269    1785    2477    1129    3410   10298    6680
River Rch & RM=MCGARY CREEK,Reach-1         ,64282
    1289    1803    2491    1129    3409   10295    6608
River Rch & RM=MCGARY CREEK,Reach-1         ,60989
    2154    3092    4344    1999    6037   18231   12073
River Rch & RM=MCGARY CREEK,Reach-1         ,57009
    2154    3092    4344    1999    6037   18231   12073
River Rch & RM=MCGARY CREEK,Reach-1         ,53989
    2367    3382    4736    2170    6553   19790   12995
River Rch & RM=MCGARY CREEK,Reach-1         ,53723
    2367    3382    4736    2170    6553   19790   12995
River Rch & RM=MCGARY CREEK,Reach-1         ,48828
    2470    3545    4978    2288    6911   20871   13789
River Rch & RM=MCGARY CREEK,Reach-1         ,47232
    2485    3562    4999    2296    6933   20937   13808
River Rch & RM=MCGARY CREEK,Reach-1         ,45336
    2692    3864    5427    2494    7531   22743   15010
River Rch & RM=MCGARY CREEK,Reach-1         ,43083
    3497    5066    7159    3308    9989   30166   20129
River Rch & RM=MCGARY CREEK,Reach-1         ,41067
    3625    5233    7376    3398   10261   30988   20554
River Rch & RM=MCGARY CREEK,Reach-1         ,40293
    3625    5233    7376    3398   10261   30988   20554
River Rch & RM=MCGARY CREEK,Reach-1         ,35384
    3843    5550    7826    3605   10888   32881   21811
River Rch & RM=MCGARY CREEK,Reach-1         ,33206
    3843    5550    7826    3605   10888   32881   21811
River Rch & RM=MCGARY CREEK,Reach-1         ,31123
    4113    5965    8436    3897   11770   35545   23719
River Rch & RM=MCGARY CREEK,Reach-1         ,30061
    4113    5965    8436    3897   11770   35545   23719
River Rch & RM=MCGARY CREEK,Reach-1         ,27370
    4619    6692    9459    4365   13181   39806   26490
River Rch & RM=MCGARY CREEK,Reach-1         ,26794
    4619    6692    9459    4365   13181   39806   26490
River Rch & RM=MCGARY CREEK,Reach-1         ,25196
    4289    6170    8676    3982   12024   36312   23910
River Rch & RM=MCGARY CREEK,Reach-1         ,23515
    4812    6985    9882    4564   13783   41624   27754
River Rch & RM=MCGARY CREEK,Reach-1         ,21433
    4812    6985    9882    4564   13783   41624   27754
River Rch & RM=MCGARY CREEK,Reach-1         ,19740
    4685    6774    9558    4402   13293   40144   26612
River Rch & RM=MCGARY CREEK,Reach-1         ,17043
    4954    7171   10127    4668   14097   42572   28270
River Rch & RM=MCGARY CREEK,Reach-1         ,15815
    4643    6697    9435    4337   13099   39558   26134
River Rch & RM=MCGARY CREEK,Reach-1         ,8950
    4831    6952    9778    4488   13555   40935   26951
Boundary for River Rch & Prof#=MCGARY CREEK,Reach-1         , 1
Up Type= 0
Dn Type= 3
Dn Slope=0.001
Boundary for River Rch & Prof#=MCGARY CREEK,Reach-1         , 2
Up Type= 0
Dn Type= 3
Dn Slope=0.001
Boundary for River Rch & Prof#=MCGARY CREEK,Reach-1         , 3
Up Type= 0
Dn Type= 3
Dn Slope=0.001
Boundary for River Rch & Prof#=MCGARY CREEK,Reach-1         , 4
Up Type= 0
Dn Type= 3
Dn Slope=0.001
Boundary for River Rch & Prof#=MCGARY CREEK,Reach-1         , 5
Up Type= 0
Dn Type= 3
Dn Slope=0.001
Boundary for River Rch & Prof#=MCGARY CREEK,Reach-1         , 6
Up Type= 0
Dn Type= 3
Dn Slope=0.001
Boundary for River Rch & Prof#=MCGARY CREEK,Reach-1         , 7
Up Type= 0
Dn Type= 3
Dn Slope=0.001
DSS Import GetInterval= 0
DSS Import GetPeak= 0
DSS Import FillOption= 0

--- MCGARY CREEK.g01 (geometry) ---

Geom Title=Existing Conditions
Program Version=4.10

River Reach=MCGARY CREEK    ,Reach-1
Reach XY= 30
      3786883.23     10257156.84      3785058.23     10256776.84
       3784491.6     10257063.72      3784042.03     10260452.68
      3782146.33     10261559.84      3782289.77     10261953.71
      3781161.54     10261957.78      3779996.14     10262596.66
      3777579.88     10262235.15      3776195.07     10261197.81
      3773978.21     10261174.59      3771500.54     10259509.49
      3771548.05     10258708.97      3768437.66     10258534.26
       3768174.7     10257514.69      3767260.86     10256977.76
      3767172.22     10256051.52      3765568.22     10256084.58
      3761911.08     10253839.48       3759898.1     10251526.77
      3758004.63      10250313.1      3757238.66     10248211.49
      3757781.85     10246544.46      3758638.47     10245728.13
      3757379.64     10243064.31      3756849.54     10240017.19
      3758291.63     10236745.66      3758302.77     10234932.57
      3759285.84     10234144.81      3759048.08     10232859.27

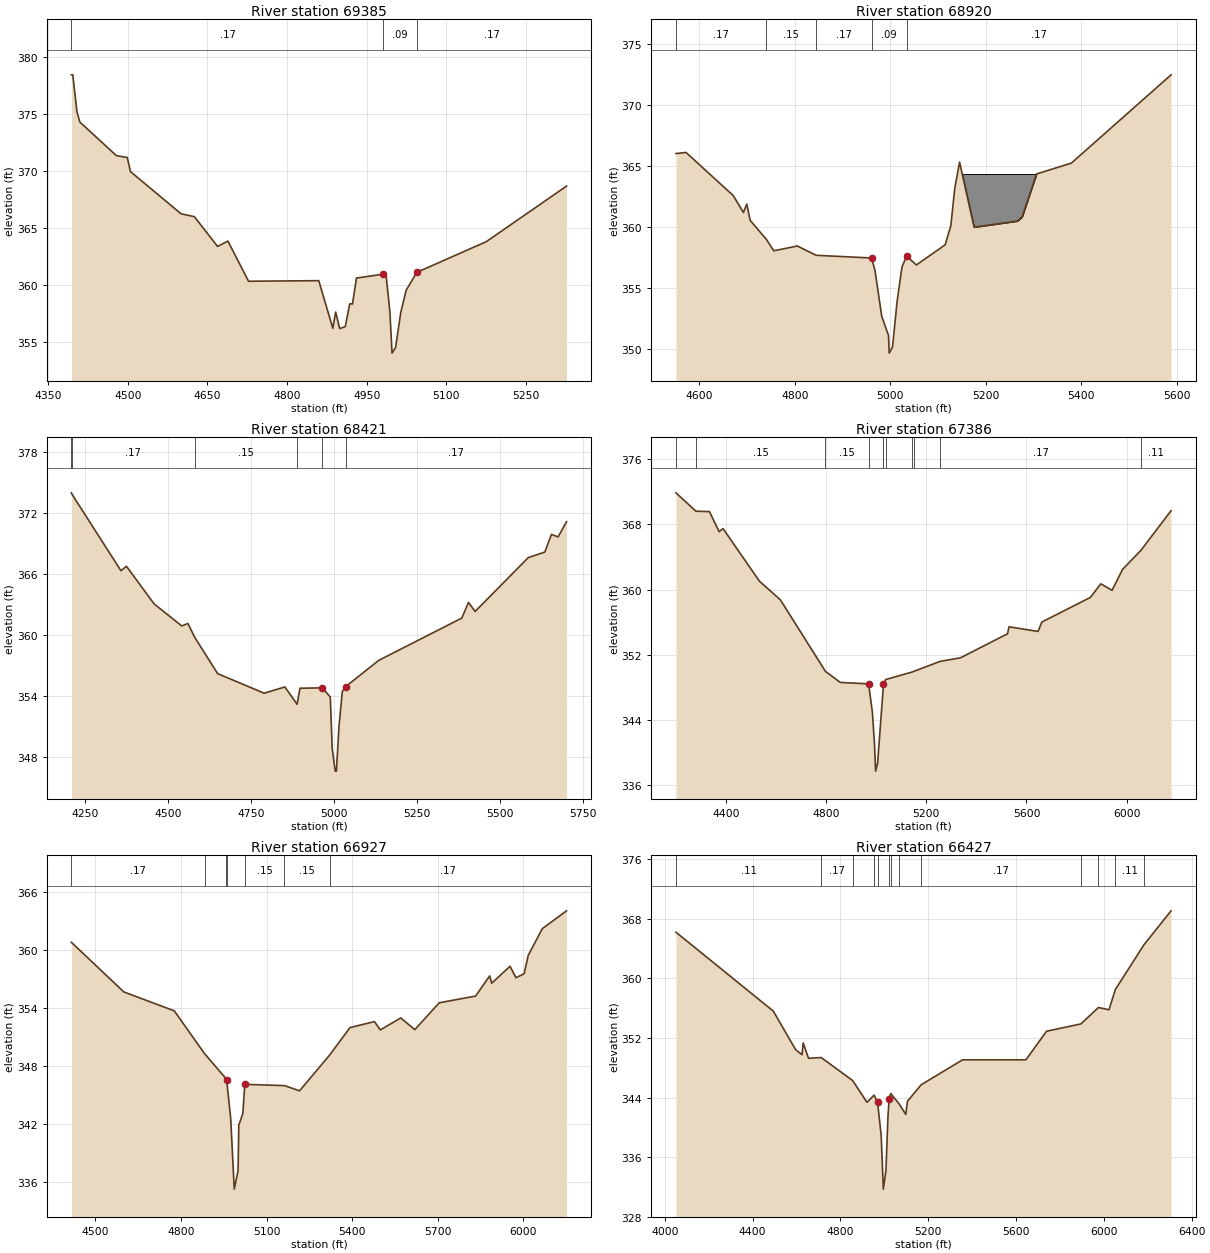
Type RM Length L Ch R = 1 ,69385   ,465,465,465
BEGIN DESCRIPTION:
MCGARY CREEK 106.0
END DESCRIPTION:
XS GIS Cut Line= 3
      3786617.85     10256561.07      3786428.23     10257136.84
      3786467.85     10257461.03
#Sta/Elev= 30
  4393.8  378.43  4396.4  378.43  4404.3  375.17  4409.7  374.29  4478.5  371.35
  4499.1  371.18    4505  369.95  4600.4  366.25  4625.4     366  4669.2  363.39
  4688.6  363.86  4727.5  360.34  4859.8  360.39  4886.3  356.21  4891.6  357.64
  4899.2  356.19  4909.7  356.36  4918.1  358.36  4923.4  358.35  4930.8  360.62
  4981.7  360.96  4986.9  360.76  4993.9  357.61  4997.8  354.04  5004.6  354.54
  5014.3  357.61  5024.4  359.55  5044.6  361.12  5175.5  363.81  5326.6  368.68
#Mann= 3 , 0 , 0
  4393.8     .17       0  4981.7     .09       0  5044.6     .17       0
Bank Sta=4981.7,5044.6
XS Rating Curve= 0 ,0
Exp/Cntr=0.3,0.1

Type RM Length L Ch R = 1 ,68920   ,499,499,499
BEGIN DESCRIPTION:
MCGARY CREEK 105.0
END DESCRIPTION:
XS GIS Cut Line= 3
      3786417.85     10256711.07      3786098.23     10257026.84
      3786167.86     10257611.11
#Sta/Elev= 30
  4550.7  366.02  4571.9  366.11  4670.9  362.58  4692.1   361.2  4699.2  361.89
  4706.2  360.56  4740.3     359  4755.8  358.07  4805.2  358.46  4844.8   357.7
  4960.8  357.48  4967.9  356.45  4982.1   352.7  4996.2  351.15  4997.7   349.7
  5004.6   350.2  5014.3  353.95  5024.4  356.74  5034.2  357.64  5054.6  356.91
    5115  358.56  5126.9  360.13  5135.2  363.22  5145.2  365.32  5175.5     360
  5266.1   360.5  5276.2  360.84  5306.4  364.35  5379.5  365.24  5588.4  372.46
#Mann= 5 ,-1 , 0
  4550.7     .17       0  4740.3     .15       0  4844.8     .17       0
  4960.8     .09       0  5034.2     .17       0
#Block Obstruct= 1 ,-1
    5150  5306.4  364.35
Bank Sta=4960.8,5034.2
XS Rating Curve= 0 ,0
Exp/Cntr=0.3,0.1

Type RM Length L Ch R = 1 ,68421   ,1035,1035,1035
BEGIN DESCRIPTION:
MCGARY CREEK 104.0
END DESCRIPTION:
XS GIS Cut Line= 3
      3785975.21     10256302.74      3785678.23     10257036.84
      3785690.47     10257736.44
#Sta/Elev= 30
  4208.1  374.02  4208.9  373.93  4357.3  366.35  4373.9  366.79  4457.1  363.09
  4540.7  360.91    4559  361.16    4579  359.83  4648.6  356.22  4788.8  354.29
  4851.2  354.91    4888   353.2  4896.7  354.78  4963.9  354.82    4988  353.92
  4993.8  348.82  5002.9  346.62  5006.4  346.62  5014.2  351.03  5024.2  354.46
  5034.2  354.94  5134.2  357.53  5384.3  361.69  5404.3  363.23  5424.3  362.34
  5584.3  367.64  5634.3  368.19  5654.3  369.93  5674.3  369.68  5699.7  371.18
#Mann= 6 ,-1 , 0
  4208.1     .11       0  4208.9     .17       0    4579     .15       0
    4888     .17       0  4963.9     .09       0  5034.2     .17       0
Bank Sta=4963.9,5034.2
XS Rating Curve= 0 ,0
Exp/Cntr=0.3,0.1

Type RM Length L Ch R = 1 ,67386   ,459,459,459
BEGIN DESCRIPTION:
MCGARY CREEK 103.0
END DESCRIPTION:
XS GIS Cut Line= 3
      3784624.52     10256080.58       3784823.9     10256765.52
      3785543.69     10257804.84
#Sta/Elev= 30
  4199.9  371.85  4279.7   369.6  4333.8  369.55  4372.5  367.08  4387.9  367.47
  4533.7  361.01    4617  358.74    4797  349.97  4856.6  348.61  4969.4  348.44
  4984.3     345    4993  341.07  4997.4  337.74  5005.3  338.68  5028.9  348.39
  5037.3  348.96  5144.7   349.9  5149.4  349.96    5255  351.19  5336.3  351.63
  5524.2  354.57  5530.2  355.43  5646.4  354.86  5661.3  356.01  5855.2  359.03
  5897.1   360.7  5941.7   359.9  5983.6  362.46  6057.4  364.81  6177.5  369.66
#Mann= 10 ,-1 , 0
  4199.9     .11       0  4279.7     .15       0    4797     .15       0
  4969.4     .09       0  5028.9     .17       0  5037.3     .15       0
  5144.7     .17       0  5149.4     .15       0    5255     .17       0
  6057.4     .11       0
Bank Sta=4969.4,5028.9
XS Rating Curve= 0 ,0
Exp/Cntr=0.3,0.1

Type RM Length L Ch R = 1 ,66927   ,500,500,500
BEGIN DESCRIPTION:
MCGARY CREEK 102.0
END DESCRIPTION:
XS GIS Cut Line= 3
      3784058.57     10256670.84      3784489.95      10257065.1
      3785367.82     10257811.05
#Sta/Elev= 30
  4415.6  360.76  4599.4  355.63  4776.4  353.67  4882.4  349.25    4957  346.69
  4960.1  346.51  4974.3   342.5  4986.7  335.23    5000  337.13  5002.7  341.86
  5016.9  343.06  5023.5  346.07  5162.8  345.94  5215.7   345.4  5322.3  349.14
  5392.5  351.94  5478.2  352.56  5499.1   351.7  5570.5  352.94  5619.9  351.73
  5705.6  354.51    5833   355.2  5882.4  357.29  5889.6  356.53  5953.8  358.29
  5974.7   357.1  6003.2  357.51  6017.5   359.4  6066.9  362.17    6152  364.02
#Mann= 7 ,-1 , 0
  4415.6     .17       0  4882.4     .17       0    4957     .12       0
  4960.1     .09       0  5023.5     .15       0  5162.8     .15       0
  5322.3     .17       0
Bank Sta=4960.1,5023.5
XS Rating Curve= 0 ,0
Exp/Cntr=0.3,0.1

Type RM Length L Ch R = 1 ,66427   ,488,488,488
BEGIN DESCRIPTION:
MCGARY CREEK 101.0
END DESCRIPTION:
XS GIS Cut Line= 3
      3783343.25     10257077.05      3784220.97     10257437.88
      3785417.82     10257961.06
#Sta/Elev= 30
    4051  366.21  4494.7  355.61    4596  350.45  4625.3  349.76  4630.7  351.35
  4654.7  349.29    4713  349.38  4856.1  346.29  4921.3  343.37  4953.4  344.34
  4969.3  343.41  4985.8  338.94  4995.7  331.72  5007.5  334.19  5016.7  341.47
  5022.2  343.87  5029.3  344.55    5069  343.11  5097.8  341.75  5105.7  343.52
    5168  345.73  5356.7  349.08  5645.3  349.08  5738.7  352.91  5895.7   353.9
  5975.4   356.1  6023.5   355.8  6052.3  358.51  6182.7  364.52  6306.2  369.08
#Mann= 13 ,-1 , 0
    4051     .11       0    4713     .17       0  4856.1     .17       0
  4953.4     .17       0  4969.3     .09       0  5022.2     .17       0
  5029.3     .17       0    5069     .17       0    5168     .17       0
  5895.7     .11       0  5975.4     .17       0  6052.3     .11       0
  6182.7     .17       0
Bank Sta=4969.3,5022.2
XS Rating Curve= 0 ,0
Exp/Cntr=0.3,0.1

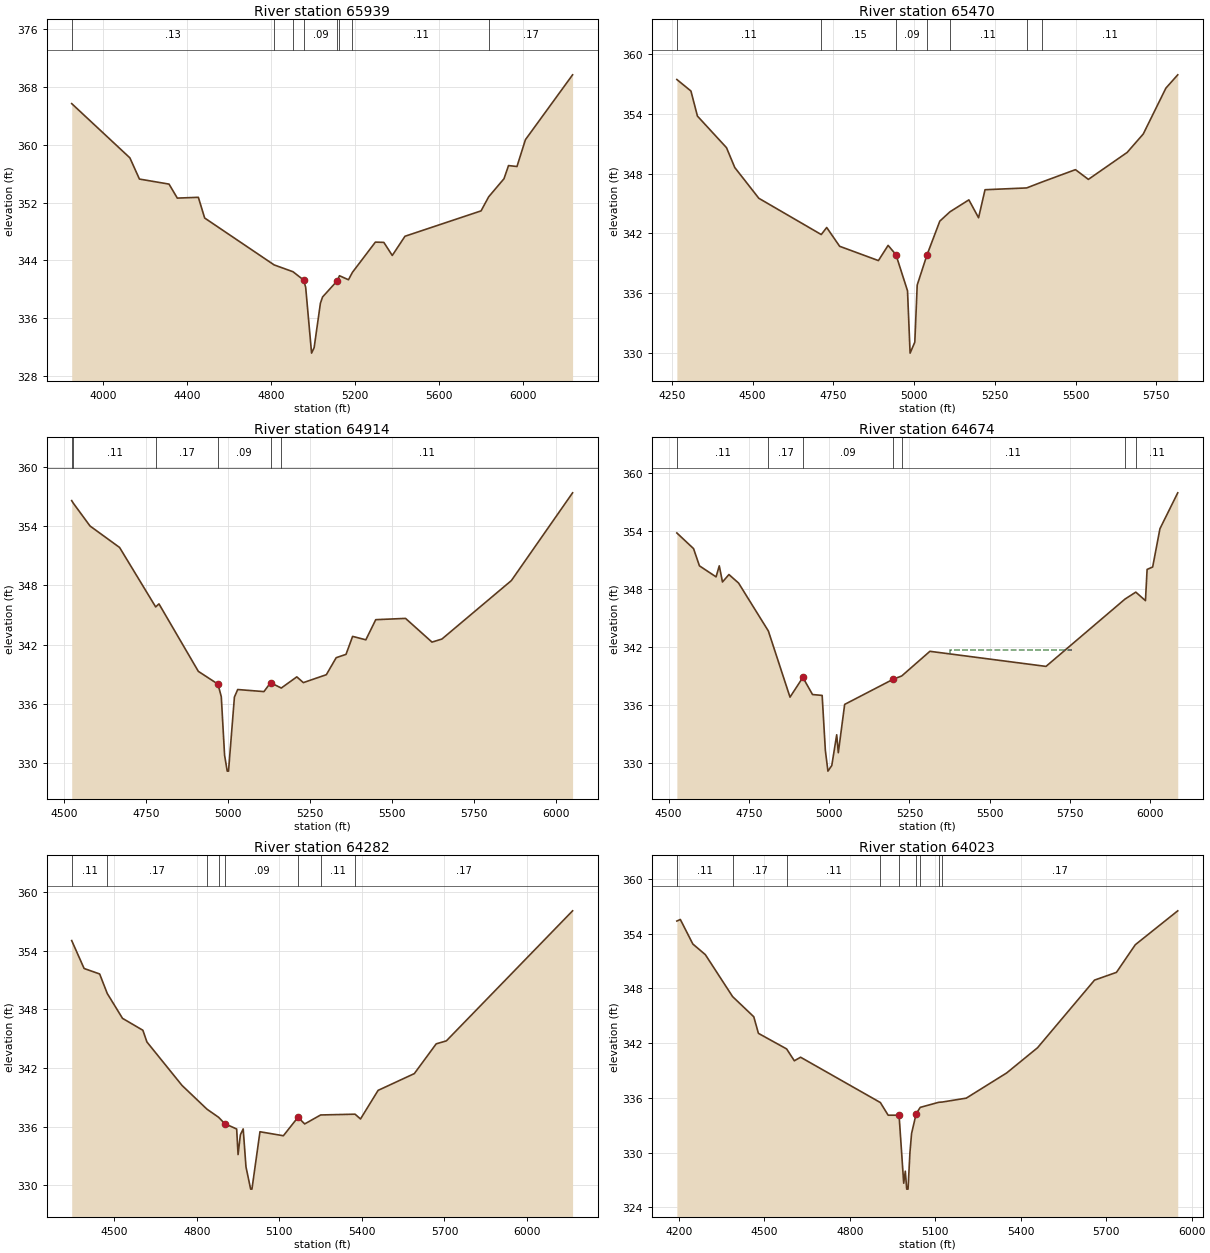
Type RM Length L Ch R = 1 ,65939   ,469,469,469
BEGIN DESCRIPTION:
MCGARY CREEK 100.0
END DESCRIPTION:
XS GIS Cut Line= 3
      3782996.03     10257931.22      3784143.11     10257868.26
      3785370.99     10258000.66
#Sta/Elev= 30
  3851.2  365.72  4128.1   358.2  4173.5  355.26  4314.4  354.56  4353.8  352.62
  4453.9  352.73    4484  349.86  4814.5  343.36  4904.6  342.41  4954.7  341.27
  4964.7  340.26  4992.8  331.13  5004.9  331.88  5034.9  338.05    5045  338.91
  5115.4  341.17  5125.5  341.86  5168.4   341.3    5187  342.32  5296.5  346.52
  5336.7  346.48  5376.9  344.67  5437.3  347.33  5799.4  350.85  5835.7   352.8
  5908.6  355.31  5930.1  357.13  5970.3     357  6010.6  360.72    6235  369.71
#Mann= 8 ,-1 , 0
  3851.2     .13       0  4814.5     .15       0  4904.6     .15       0
  4954.7     .09       0  5115.4     .15       0  5125.5     .15       0
    5187     .11       0  5835.7     .17       0
Bank Sta=4954.7,5115.4
XS Rating Curve= 0 ,0
Exp/Cntr=0.3,0.1

Type RM Length L Ch R = 1 ,65470   ,556,556,556
BEGIN DESCRIPTION:
MCGARY CREEK 99.0
END DESCRIPTION:
XS GIS Cut Line= 3
      3783534.25     10258233.31      3784268.05     10258203.78
      3785084.54     10258208.99
#Sta/Elev= 30
  4265.6  357.48  4309.2  356.32  4329.3   353.8  4419.3  350.62    4445  348.62
  4519.4  345.53  4712.7  341.88  4729.6  342.59  4769.6   340.7  4889.7  339.26
  4919.7  340.79  4943.9  339.86  4979.8  336.22  4987.8  329.95  5002.4  331.06
  5009.8   336.8  5039.8   339.8  5079.8  343.23  5111.3  344.17  5169.8  345.37
  5199.8  343.57  5219.8  346.39  5348.7  346.57  5397.4  347.18  5499.8  348.41
  5539.8  347.43  5659.8  350.14  5709.8     352  5779.8  356.61  5816.5  357.95
#Mann= 7 ,-1 , 0
  4265.6     .11       0  4712.7     .15       0  4943.9     .09       0
  5039.8     .15       0  5111.3     .11       0  5348.7     .17       0
  5397.4     .11       0
Bank Sta=4943.9,5039.8
XS Rating Curve= 0 ,0
Exp/Cntr=0.3,0.1

Type RM Length L Ch R = 1 ,64914   ,240,240,240
BEGIN DESCRIPTION:
MCGARY CREEK 98.0
END DESCRIPTION:
XS GIS Cut Line= 3
      3783561.98     10258674.28      3784409.23     10258660.39
       3785082.8     10258573.59
#Sta/Elev= 30
  4523.9  356.57    4529   356.3  4579.8     354  4669.8  351.83  4779.8  345.81
  4789.8  346.12  4909.8  339.29  4969.8  337.99  4979.8  336.71  4989.8  330.81
  4997.8  329.19  5001.8  329.19  5019.8  336.69  5029.8  337.45  5109.8  337.24
  5129.9  338.14  5162.6   337.6  5209.9  338.73  5229.9  338.15  5299.9  338.95
  5329.9  340.67  5359.9  341.01    5380  342.83  5420.3  342.48  5450.5  344.52
  5541.3  344.65  5621.9  342.25  5652.2  342.56  5863.9  348.48  6050.4  357.36
#Mann= 6 ,-1 , 0
  4523.9     .17       0    4529     .11       0  4779.8     .17       0
  4969.8     .09       0  5129.9     .17       0  5162.6     .11       0
Bank Sta=4969.8,5129.9
XS Rating Curve= 0 ,0
Exp/Cntr=0.3,0.1

Type RM Length L Ch R = 1 ,64674   ,392,392,392
BEGIN DESCRIPTION:
MCGARY CREEK 97.0
END DESCRIPTION:
XS GIS Cut Line= 3
      3783575.87     10258882.61      3784203.53     10258912.21
      3785103.28     10258670.91
#Sta/Elev= 30
  4525.6  353.78  4577.6  352.16  4595.9  350.38  4647.7  349.24  4657.7  350.38
  4667.7  348.71  4687.8  349.48  4717.8   348.6  4810.6  343.64    4878   336.8
    4918  338.84  4948.1  337.07  4978.1  336.98  4988.1  331.28  4996.1  329.15
  5008.1  329.73  5023.4  332.91  5028.4  331.05  5048.2  336.05  5199.8  338.66
  5225.9  338.99  5313.7  341.54  5675.2  339.98  5921.2  346.94  5954.9  347.66
    5985  346.78  5990.1  350.01  6007.4  350.26  6030.1  354.22  6085.5  357.93
#Mann= 7 ,-1 , 0
  4525.6     .11       0  4810.6     .17       0    4918     .09       0
  5199.8     .15       0  5225.9     .11       0  5921.2     .15       0
  5954.9     .11       0
#XS Ineff= 1 ,-1
  5375.9    5755  341.64
Permanent Ineff=
       F
Bank Sta=4918,5199.8
XS Rating Curve= 0 ,0
Exp/Cntr=0.3,0.1

Type RM Length L Ch R = 1 ,64282   ,259,259,259
BEGIN DESCRIPTION:
Mapping XS 5271fd90
END DESCRIPTION:
XS GIS Cut Line= 4
      3783537.73     10258952.07       3784037.7       10259209.
      3784492.56     10259292.34      3785173.01     10259705.46
#Sta/Elev= 30
  4345.2  355.06  4390.3   352.2  4446.8  351.64  4474.4  349.64  4529.9  347.09
  4603.9  345.87  4618.6  344.67  4746.1  340.22    4837  337.78  4879.2  336.95
  4901.4   336.3  4944.8  335.75  4949.9  333.13  4958.3  335.16  4968.5  335.76
  4978.6  331.88  4995.6  329.59  5000.3  329.59  5029.5  335.47  5114.5  335.06
  5167.6  336.95  5192.1  336.27    5250  337.19  5375.1  337.27  5394.9  336.78
  5458.9  339.71  5590.6  341.43  5670.1  344.48  5706.9  344.78  6165.8  358.11
#Mann= 8 ,-1 , 0
  4345.2     .11       0  4474.4     .17       0    4837     .11       0
  4879.2     .15       0  4901.4     .09       0  5167.6     .17       0
    5250     .11       0  5375.1     .17       0
Bank Sta=4901.4,5167.6
XS Rating Curve= 0 ,0
Exp/Cntr=0.3,0.1

Type RM Length L Ch R = 1 ,64023   ,182,182,182
BEGIN DESCRIPTION:
MCGARY CREEK 96.0
END DESCRIPTION:
XS GIS Cut Line= 3
      3783443.98     10259049.29      3784374.51     10259545.81
      3785013.14     10259840.83
#Sta/Elev= 30
    4193   355.4  4205.2  355.57  4249.1  352.88  4293.1  351.71  4388.7  347.11
    4463   344.9  4479.3  343.08  4578.3  341.37  4605.4  340.07  4627.3  340.46
  4907.3  335.49  4934.7   334.1    4973   334.1  4989.3  326.64  4994.9  327.96
  4999.8  325.99  5004.5  325.99  5011.2  330.02  5016.9  332.09  5033.2  334.28
  5047.5  334.96  5112.8  335.52  5123.9  335.54  5208.8  335.97  5350.5  338.73
  5459.1   341.5  5659.1  348.92  5736.1  349.77  5802.2   352.8  5951.2  356.52
#Mann= 9 ,-1 , 0
    4193     .11       0  4388.7     .17       0  4578.3     .11       0
  4907.3     .15       0    4973     .09       0  5033.2     .15       0
  5047.5     .17       0  5112.8     .15       0  5123.9     .17       0
Bank Sta=4973,5033.2
XS Rating Curve= 0 ,0
Exp/Cntr=0.3,0.1

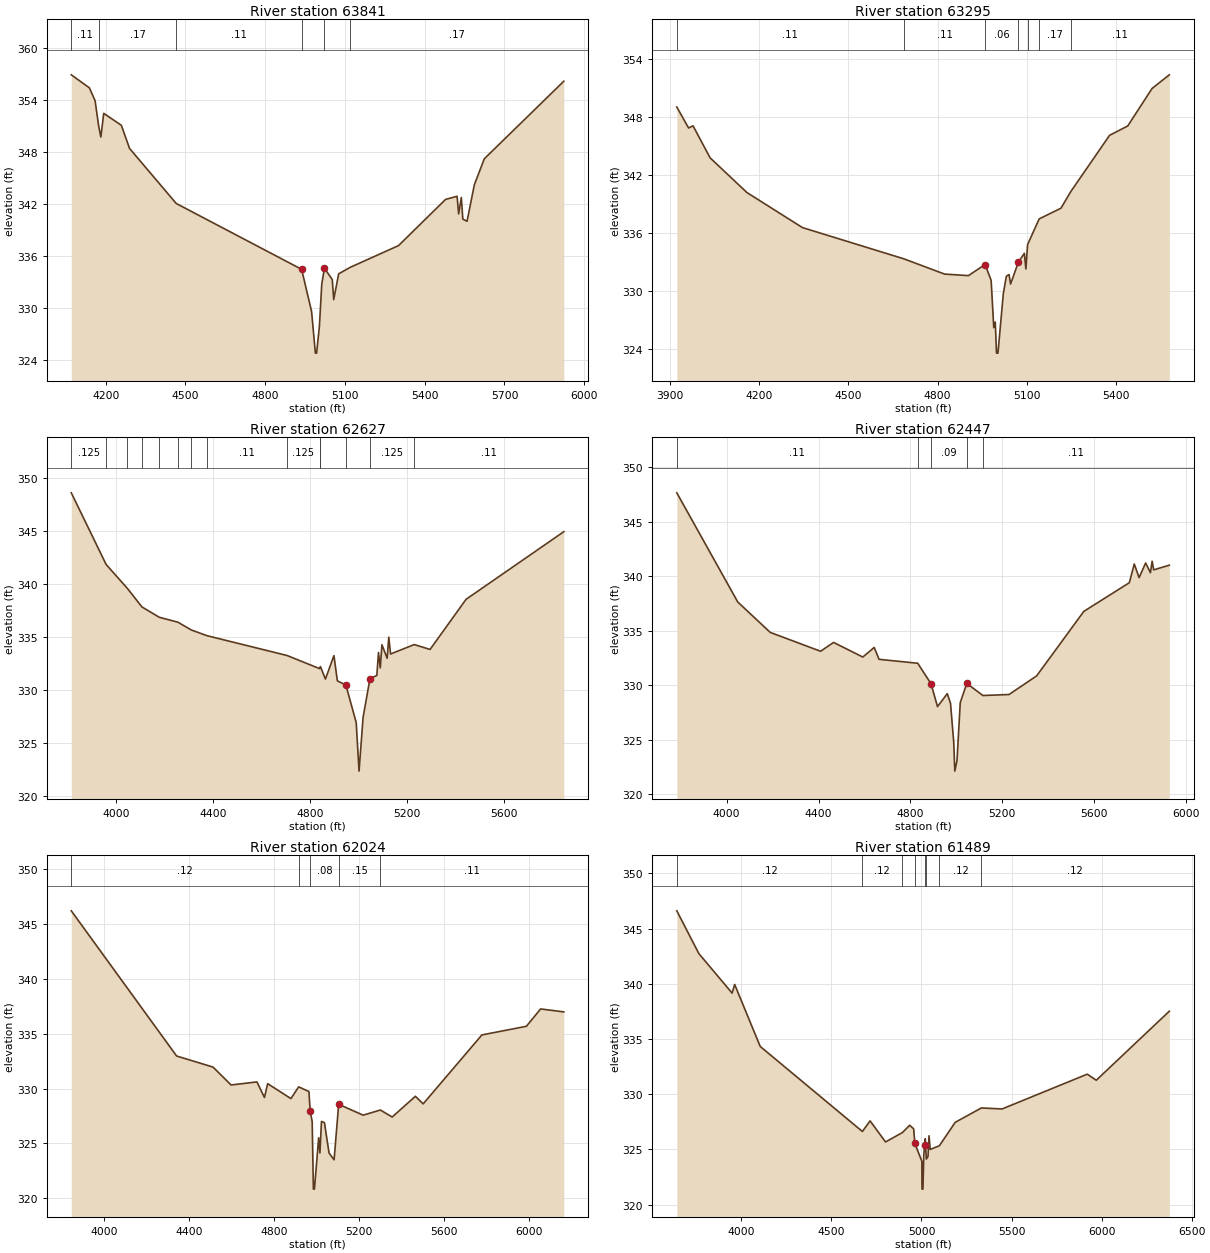
Type RM Length L Ch R = 1 ,63841   ,546,546,546
BEGIN DESCRIPTION:
MCGARY CREEK 95.0
END DESCRIPTION:
XS GIS Cut Line= 3
      3783214.81     10259236.79      3784294.65     10259674.28
      3784891.91     10260014.58
#Sta/Elev= 30
  4070.7  356.91  4138.7  355.41  4160.3  353.91  4173.8  350.97  4181.9  349.72
  4192.7  352.46    4259  351.08  4289.8  348.41  4465.3  342.05  4937.1  334.44
  4974.6  329.56  4988.7  324.76  4993.4  324.76  5004.1  327.92  5012.7   332.7
  5022.8  334.57  5052.3  333.26  5057.7  330.94  5076.4  333.92  5119.1  334.66
  5301.4  337.18  5478.6  342.52  5521.8  342.88  5527.6  340.84  5537.7  342.74
  5543.4  340.24  5559.3  339.99  5586.7  344.21  5624.1  347.21  5923.2  356.17
#Mann= 6 ,-1 , 0
  4070.7     .11       0  4173.8     .17       0  4465.3     .11       0
  4937.1     .09       0  5022.8     .11       0  5119.1     .17       0
Bank Sta=4937.1,5022.8
XS Rating Curve= 0 ,0
Exp/Cntr=0.3,0.1

Type RM Length L Ch R = 1 ,63295   ,668,668,668
BEGIN DESCRIPTION:
Mapping XS e733d847
END DESCRIPTION:
XS GIS Cut Line= 3
      3783197.38     10259465.92      3784023.81     10260011.09
      3784674.68     10260139.18
#Sta/Elev= 30
  3924.3  349.01  3963.8  346.84  3978.9  347.06  4036.1  343.75  4159.6  340.16
  4346.2  336.53  4686.4   333.3  4823.3  331.72  4903.2  331.56  4959.2  332.71
  4979.6  331.07  4988.3  326.18  4993.4  326.76  4997.6  323.54  5002.4  323.54
  5020.4  329.69  5030.6   331.5  5039.7  331.67  5044.8  330.69  5071.3  332.98
  5091.1  333.87  5096.2  332.25  5101.9  334.77  5140.8  337.43    5214  338.54
  5247.4  340.28  5377.1  346.08  5438.2  347.05  5519.8  350.93  5577.7  352.34
#Mann= 7 ,-1 , 0
  3924.3     .11       0  4686.4     .11       0  4959.2     .06       0
  5071.3     .11       0  5101.9     .15       0  5140.8     .17       0
  5247.4     .11       0
Bank Sta=4959.2,5071.3
XS Rating Curve= 0 ,0
Exp/Cntr=0.3,0.1

Type RM Length L Ch R = 1 ,62627   ,180,180,180
BEGIN DESCRIPTION:
MCGARY CREEK 94.0
END DESCRIPTION:
XS GIS Cut Line= 3
      3783082.87     10259559.73      3783721.73     10260330.53
      3784482.93     10261025.99
#Sta/Elev= 30
  3814.8  348.57  3958.6  341.82  4045.9  339.58  4106.5  337.82  4177.7  336.85
  4254.4  336.39  4309.5  335.66    4374  335.12  4704.9  333.25  4839.8  332.01
  4842.6  332.21  4863.4  331.03  4898.5  333.24  4912.7  330.86  4947.8  330.47
  4990.4  326.93  5002.1  322.36  5018.8  327.42  5047.1  331.07  5075.5  331.37
  5082.3  333.53  5089.7  332.08  5096.5  334.26  5118.1  332.99  5124.8  334.98
  5132.2  333.39  5229.8  334.28  5295.1  333.82  5443.7  338.54    5847  344.91
#Mann= 14 ,-1 , 0
  3814.8    .125       0  3958.6     .11       0  4045.9    .125       0
  4106.5     .11       0  4177.7    .125       0  4254.4     .11       0
  4309.5    .125       0    4374     .11       0  4704.9    .125       0
  4839.8     .15       0  4842.6    .125       0  4947.8     .09       0
  5047.1    .125       0  5229.8     .11       0
Bank Sta=4947.8,5047.1
XS Rating Curve= 0 ,0
Exp/Cntr=0.3,0.1

Type RM Length L Ch R = 1 ,62447   ,423,423,423
BEGIN DESCRIPTION:
MCGARY CREEK 93.0
END DESCRIPTION:
XS GIS Cut Line= 3
       3782860.6     10259722.88      3783746.04     10260587.47
      3784419.63      10261195.1
#Sta/Elev= 30
  3782.8  347.66  4048.3  337.64  4189.7  334.85  4408.9  333.12  4465.5  333.93
  4592.8  332.59  4642.4  333.47  4663.5  332.38  4831.9  332.02  4889.8  330.14
  4918.1  328.04  4960.5  329.23  4974.7  328.35  4988.8  324.75  4993.4  322.12
    5003   323.1  5017.1  328.41  5045.6  330.17  5115.7  329.06  5229.4  329.15
  5349.7  330.86  5555.2  336.78  5753.3  339.41  5774.9  341.13  5795.9  339.88
  5824.3  341.22  5845.2  340.33  5852.7  341.38  5859.4  340.59  5927.5  341.02
#Mann= 5 ,-1 , 0
  3782.8     .11       0  4831.9     .15       0  4889.8     .09       0
  5045.6     .15       0  5115.7     .11       0
Bank Sta=4889.8,5045.6
XS Rating Curve= 0 ,0
Exp/Cntr=0.3,0.1

Type RM Length L Ch R = 1 ,62024   ,535,535,535
BEGIN DESCRIPTION:
MCGARY CREEK 92.0
END DESCRIPTION:
XS GIS Cut Line= 3
      3782513.38     10260038.85      3783218.26     10260604.84
      3784409.19     10261361.76
#Sta/Elev= 30
  3847.4   346.2  4342.5  332.97  4513.7  331.96  4598.5  330.33  4720.1  330.61
  4755.3  329.19  4770.5  330.45  4879.7  329.09  4916.2  330.16  4964.4  329.73
 4970.28  327.95  4979.7     327  4985.4  320.84  4990.3  320.84  5010.2  325.52
  5016.1  324.14  5023.4  327.01  5037.3   326.9    5059  324.13  5082.7  323.51
  5104.2  328.57  5219.3  327.58  5300.1  328.05  5355.7  327.41  5464.9   329.3
  5501.4  328.61  5777.4  334.89  5986.6  335.68  6053.5  337.26  6162.5  336.99
#Mann= 5 ,-1 , 0
  3847.4     .12       0  4916.2     .12       0 4970.28     .08       0
  5104.2     .15       0  5300.1     .11       0
Bank Sta=4970.28,5104.2
XS Rating Curve= 0 ,0
Exp/Cntr=0.3,0.1

Type RM Length L Ch R = 1 ,61489   ,500,500,500
BEGIN DESCRIPTION:
MCGARY CREEK 91.0
END DESCRIPTION:
XS GIS Cut Line= 4
      3782322.42     10260094.42      3783197.06     10261133.64
      3783617.56     10261403.45       3784492.8     10261448.32
#Sta/Elev= 30
  3641.7  346.61  3764.1  342.74  3948.7  339.16    3963  339.94  4104.8  334.33
  4671.9  326.63  4714.8  327.59  4800.6  325.68  4893.9  326.53  4934.6  327.19
  4956.7  326.87  4963.2  325.55  5002.2  323.93  5002.7  321.91  5003.2  321.41
  5008.2  321.41  5012.8  324.52    5018 325.451  5020.9  325.97  5026.8  324.13
  5036.1  324.35    5042  326.24  5048.5     325  5099.5  325.34  5187.4  327.46
  5332.7  328.76  5447.7  328.67  5920.5  331.82  5970.5  331.27    6376  337.52
#Mann= 8 ,-1 , 0
  3641.7     .12       0  4671.9     .12       0  4893.9     .15       0
  4963.2     .09       0    5018     .12       0  5026.8     .15       0
  5099.5     .12       0  5332.7     .12       0
Bank Sta=4963.2,5018
XS Rating Curve= 0 ,0
Exp/Cntr=0.3,0.1

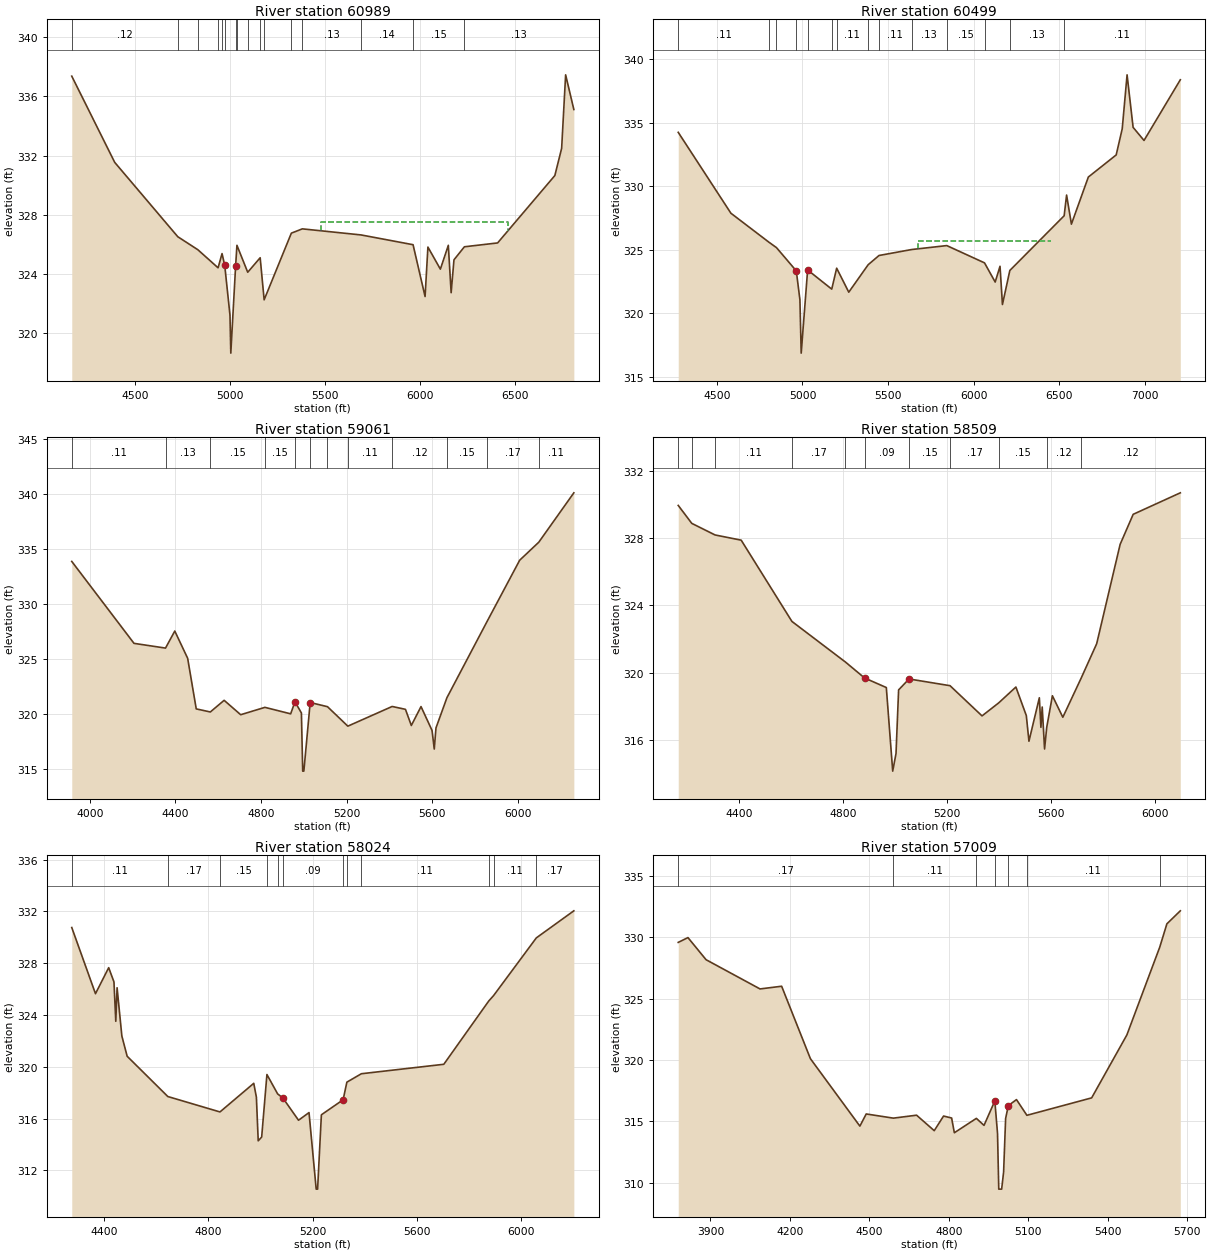
Type RM Length L Ch R = 1 ,60989   ,490,490,490
BEGIN DESCRIPTION:
MCGARY CREEK 90.0
END DESCRIPTION:
XS GIS Cut Line= 3
      3782217.83     10260661.05      3782791.98     10261267.06
      3783817.84     10262761.06
#Sta/Elev= 30
  4165.2  337.37  4391.6  331.55  4724.1  326.53  4830.1  325.65  4936.6  324.43
  4957.5  325.39  4971.6   324.6  4999.3  321.24  5003.7  318.67  5029.1  324.56
    5036  325.95  5092.9  324.13  5158.5  325.11  5179.5  322.27  5322.9  326.77
  5380.9  327.06  5690.4  326.65  5964.6  325.99    6028  322.49  6042.9  325.83
  6108.6  324.34  6150.5  325.95  6165.4  322.75  6180.3  324.97  6235.3  325.85
  6410.4  326.11  6712.2  330.66    6748   332.5    6769  337.46  6812.3  335.12
#Mann= 16 ,-1 , 0
  4165.2     .12       0  4724.1     .11       0  4830.1     .11       0
  4936.6     .13       0  4957.5     .13       0  4971.6     .08       0
  5029.1     .11       0    5036     .13       0  5092.9     .13       0
  5158.5     .13       0  5179.5     .13       0  5322.9     .14       0
  5380.9     .13       0  5690.4     .14       0  5964.6     .15       0
  6235.3     .13       0
#XS Ineff= 1 ,-1
  5481.3    6465  327.52
Permanent Ineff=
       F
Bank Sta=4971.6,5029.1
XS Rating Curve= 0 ,0
Exp/Cntr=0.3,0.1

Type RM Length L Ch R = 1 ,60499   ,1438,1438,1438
BEGIN DESCRIPTION:
MCGARY CREEK 89.0
END DESCRIPTION:
XS GIS Cut Line= 3
      3782217.84     10260811.04      3782461.05     10261494.99
      3784017.83     10263061.05
#Sta/Elev= 30
  4274.1  334.26  4581.9  327.89  4804.8   325.6  4848.2  325.18    4964  323.35
  4985.2  321.08  4992.7  316.87  5030.3  323.42  5171.2  321.91    5200  323.56
  5270.7  321.67  5383.9  323.83  5447.5  324.56  5638.4  325.03  5843.5  325.34
  6063.9  323.98  6126.3  322.47  6154.6  323.71  6168.8   320.7    6212  323.38
  6529.4  327.69  6543.6  329.32  6571.8  327.03  6670.8  330.74  6833.5  332.48
  6868.8  334.54  6897.1  338.79  6932.4  334.65  6996.1  333.62  7208.2   338.4
#Mann= 14 ,-1 , 0
  4274.1     .11       0  4804.8     .11       0  4848.2     .15       0
    4964     .09       0  5030.3     .15       0  5171.2     .11       0
    5200     .11       0  5383.9     .11       0  5447.5     .11       0
  5638.4     .13       0  5843.5     .15       0  6063.9     .15       0
    6212     .13       0  6529.4     .11       0
#XS Ineff= 1 ,-1
  5673.8    6450  325.67
Permanent Ineff=
       F
Bank Sta=4964,5030.3
XS Rating Curve= 0 ,0
Exp/Cntr=0.3,0.1

Type RM Length L Ch R = 1 ,59061   ,552,552,552
BEGIN DESCRIPTION:
MCGARY CREEK 88.0
END DESCRIPTION:
XS GIS Cut Line= 3
      3781967.85     10260961.08       3782043.2     10262042.26
      3782367.85     10263261.06
#Sta/Elev= 30
  3916.2  333.85  4206.9   326.4  4354.1  325.97  4397.4  327.52  4457.5  325.04
  4497.6  320.44  4563.4  320.16  4627.9  321.22  4705.2  319.91  4818.4  320.58
  4938.7  319.99  4958.7  321.09  4988.8  320.07  4994.9  314.78  5000.2  314.78
  5029.8  321.02  5110.6  320.64  5205.7  318.87  5412.7  320.66  5474.8   320.4
  5502.2  318.93  5547.5  320.65    5599  318.48  5609.3  316.79  5617.4  318.71
  5668.6  321.46  5856.8  328.42  6008.3  333.96  6097.6   335.6  6261.3  340.09
#Mann= 12 ,-1 , 0
  3916.2     .11       0  4354.1     .13       0  4563.4     .15       0
  4818.4     .15       0  4958.7     .09       0  5029.8     .15       0
  5110.6     .11       0  5205.7     .11       0  5412.7     .12       0
  5668.6     .15       0  5856.8     .17       0  6097.6     .11       0
Bank Sta=4958.7,5029.8
XS Rating Curve= 0 ,0
Exp/Cntr=0.3,0.1

Type RM Length L Ch R = 1 ,58509   ,485,485,485
BEGIN DESCRIPTION:
MCGARY CREEK 87.0
END DESCRIPTION:
XS GIS Cut Line= 3
      3781784.23     10261115.28      3781651.09     10261875.26
      3781728.67     10263031.91
#Sta/Elev= 30
  4166.8  329.96  4218.9  328.89  4308.4   328.2  4408.9  327.89  4603.9  323.05
  4809.7  320.63  4883.3  319.68    4967  319.11  4991.6  314.13  5004.3  315.18
  5014.3  318.97  5054.4  319.62    5212  319.22  5335.1  317.42  5399.5   318.2
  5465.3  319.14  5505.4  317.44  5515.5  315.91  5555.5   318.5  5561.5  316.74
  5566.5  317.95  5575.6  315.45  5583.9  316.74  5605.7  318.62  5645.8  317.34
  5716.3  319.67    5776  321.72  5866.2  327.64  5916.4  329.43  6097.6  330.71
#Mann= 11 ,-1 , 0
  4166.8     .11       0  4218.9     .17       0  4308.4     .11       0
  4603.9     .17       0  4809.7     .17       0  4883.3     .09       0
  5054.4     .15       0    5212     .17       0  5399.5     .15       0
  5583.9     .12       0  5716.3     .12       0
Bank Sta=4883.3,5054.4
XS Rating Curve= 0 ,0
Exp/Cntr=0.3,0.1

Type RM Length L Ch R = 1 ,58024   ,1015,1015,1015
BEGIN DESCRIPTION:
MCGARY CREEK 86.0
END DESCRIPTION:
XS GIS Cut Line= 4
      3781167.86     10261261.11       3781287.7     10262070.11
      3781232.15     10262594.42      3781537.26     10263086.77
#Sta/Elev= 30
  4276.4  330.76  4367.3  325.65  4417.9  327.66  4438.1  326.56  4445.1  323.52
  4450.1  326.11  4468.4  322.38  4488.7  320.82  4644.6  317.71  4844.4  316.52
  4973.9  318.73    4984  317.66    4991  314.29  5004.2  314.58  5024.4  319.41
  5065.5  317.91  5085.1  317.61  5145.5  315.88  5185.7  316.47  5213.2  310.56
  5218.6  310.56  5233.1   316.3  5316.4  317.46  5330.8  318.82  5386.3  319.47
  5702.3   320.2  5874.7  325.09  5892.9   325.5  6056.9  329.96  6200.7  332.05
#Mann= 12 ,-1 , 0
  4276.4     .11       0  4644.6     .17       0  4844.4     .15       0
  5024.4     .15       0  5065.5     .12       0  5085.1     .09       0
  5316.4     .12       0  5330.8     .15       0  5386.3     .11       0
  5874.7     .17       0  5892.9     .11       0  6056.9     .17       0
Bank Sta=5085.1,5316.4
XS Rating Curve= 0 ,0
Exp/Cntr=0.3,0.1

Type RM Length L Ch R = 1 ,57009   ,370,370,370
BEGIN DESCRIPTION:
MCGARY CREEK 85.0
END DESCRIPTION:
XS GIS Cut Line= 3
      3780416.18     10261097.94       3780662.7     10262351.36
      3780767.84     10262961.02
#Sta/Elev= 30
  3778.6  329.58  3815.3  329.97  3883.7  328.17  4087.5  325.79  4169.1  326.01
  4277.8  320.11  4464.6  314.62  4488.5  315.61  4591.1  315.27  4678.7  315.51
  4745.4  314.25  4780.6  315.44  4811.1  315.28  4821.3  314.08  4904.5  315.25
  4933.4  314.68  4974.2  316.67  4984.4  314.03  4989.1  309.49    5000  309.49
  5007.4  310.89    5015  315.24  5025.2  316.29    5056  316.78  5095.3   315.5
  5339.9  316.92  5472.8  322.04    5597  329.19    5624  331.09  5674.7  332.15
#Mann= 7 ,-1 , 0
  3778.6     .17       0  4591.1     .11       0  4904.5     .15       0
  4974.2     .09       0  5025.2     .15       0  5095.3     .11       0
    5597     .17       0
Bank Sta=4974.2,5025.2
XS Rating Curve= 0 ,0
Exp/Cntr=0.3,0.1