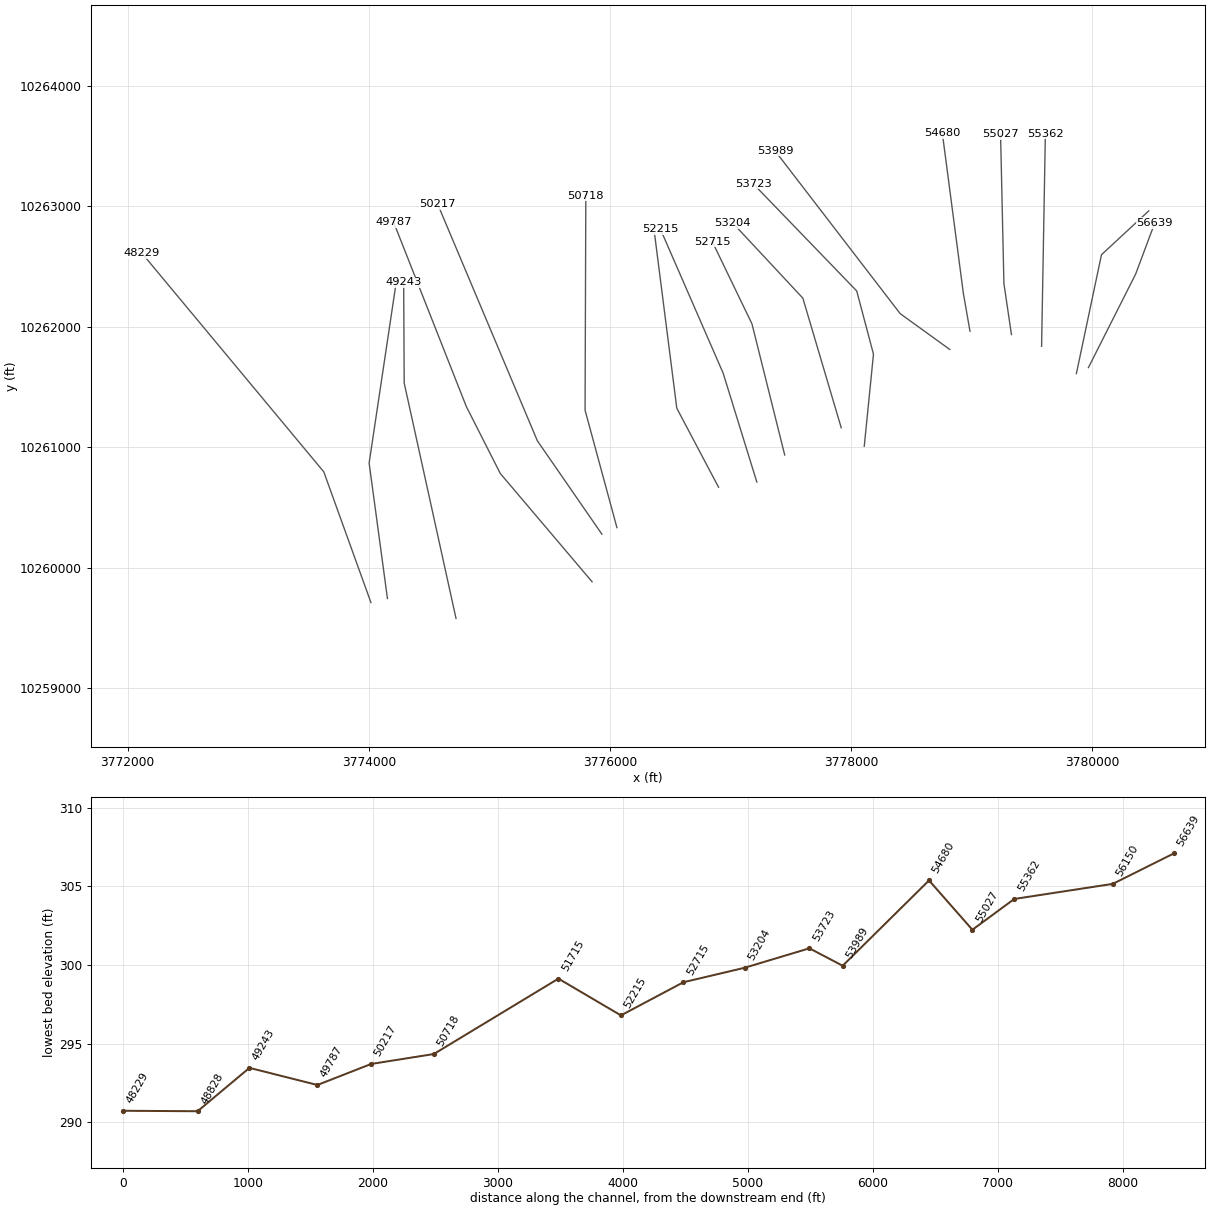
HEC-RAS study MCGARY CREEK.prj: MCGARY CREEK Base Level Engineering

--- MCGARY CREEK.g01 (geometry) --- (continued)

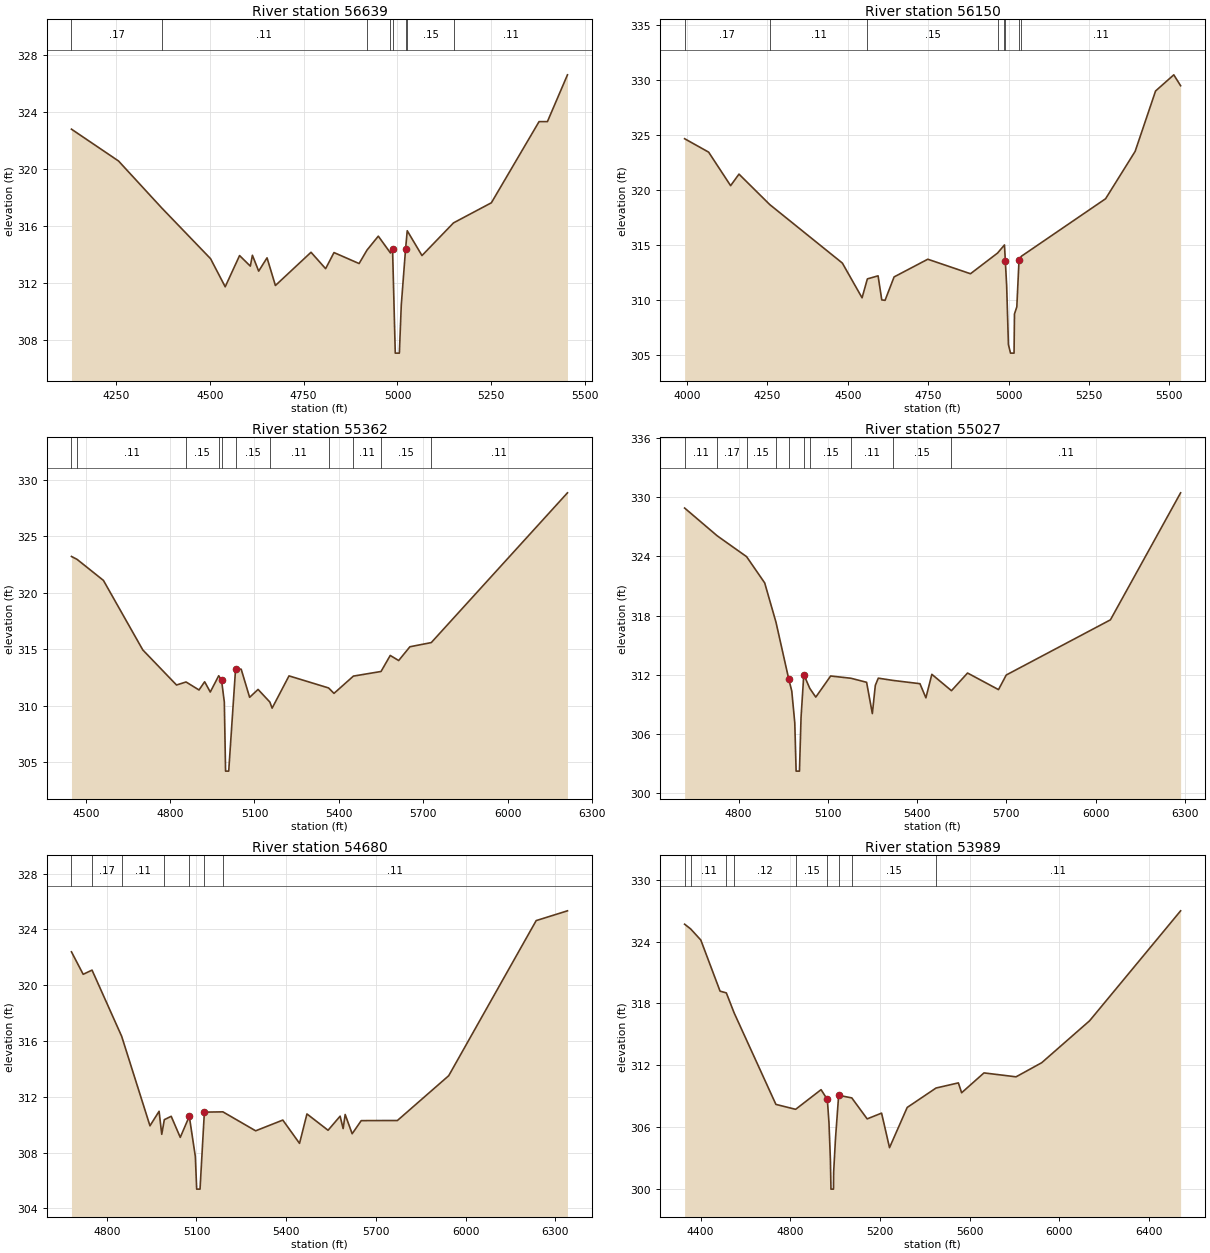
Type RM Length L Ch R = 1 ,56639   ,489,489,489
BEGIN DESCRIPTION:
MCGARY CREEK 84.0
END DESCRIPTION:
XS GIS Cut Line= 3
      3779967.87      10261661.1      3780359.24     10262436.64
      3780517.85     10262861.08
#Sta/Elev= 30
  4131.3   322.8  4256.7  320.57  4372.1  317.27    4502  313.72    4541  311.75
  4579.3  313.94  4607.9   313.2  4613.5  313.96  4630.2  312.85  4652.5  313.78
  4674.8  311.84  4769.7  314.17  4808.6  313.02  4830.9  314.15  4897.8  313.38
  4918.8  314.32    4949   315.3  4981.4  314.12    4987  314.38  4994.2   307.1
  5005.1   307.1  5010.2  310.46  5021.7 314.414  5026.1  315.68  5065.4  313.94
  5149.4  316.23  5250.3  317.64  5377.4  323.33  5399.7  323.33  5453.1  326.61
#Mann= 8 ,-1 , 0
  4131.3     .17       0  4372.1     .11       0  4918.8     .15       0
  4981.4     .12       0    4987     .09       0  5021.7     .12       0
  5026.1     .15       0  5149.4     .11       0
Bank Sta=4987,5021.7
XS Rating Curve= 0 ,0
Exp/Cntr=0.3,0.1

Type RM Length L Ch R = 1 ,56150   ,788,788,788
BEGIN DESCRIPTION:
MCGARY CREEK 83.0
END DESCRIPTION:
XS GIS Cut Line= 3
      3779867.85     10261611.08      3780075.81     10262596.99
      3780467.83     10262961.05
#Sta/Elev= 30
  3992.4  324.66  4067.1  323.44  4135.5  320.39  4161.5  321.44  4257.2  318.67
    4483  313.35  4544.3  310.19  4560.8  311.91  4594.1  312.19  4605.6     310
  4615.8  309.96  4643.9  312.09  4748.7   313.7  4881.5  312.38  4965.7  314.26
  4987.2     315  4989.9 313.523    4994  311.28  4999.5  305.94    5006  305.16
    5017  305.16  5018.3  308.72  5025.6  309.37  5032.5  313.65  5039.8  313.97
  5301.7   319.2  5393.6  323.51  5457.1     329  5513.8  330.47    5535  329.48
#Mann= 8 ,-1 , 0
  3992.4     .17       0  4257.2     .11       0  4560.8     .15       0
  4965.7     .11       0  4987.2     .08       0  4989.9     .06       0
  5032.5     .08       0  5039.8     .11       0
Bank Sta=4989.9,5032.5
XS Rating Curve= 0 ,0
Exp/Cntr=0.3,0.1

Type RM Length L Ch R = 1 ,55362   ,335,335,335
BEGIN DESCRIPTION:
Mapping XS 4f60312d
END DESCRIPTION:
XS GIS Cut Line= 2
      3779579.37     10261837.44      3779610.62     10263601.36
#Sta/Elev= 30
    4449  323.22  4468.6  322.97  4562.7   321.1  4702.7  314.94  4822.7  311.83
  4856.5   312.1  4902.7  311.39  4922.7  312.12  4942.7  311.21  4972.7  312.65
  4982.7  312.28  4992.7  310.32  4997.1   304.2  5008.3   304.2  5032.7  313.26
  5052.7  313.23  5082.7  310.74  5112.7  311.44  5154.7  310.32  5162.7  309.78
  5222.8  312.64  5363.6  311.57  5382.8  311.09  5451.8  312.62  5550.1  313.03
  5582.8  314.45  5612.8     314  5652.8  315.22  5728.8  315.59  6213.2  328.86
#Mann= 11 ,-1 , 0
    4449     .17       0  4468.6     .11       0  4856.5     .15       0
  4972.7     .12       0  4982.7     .09       0  5032.7     .15       0
  5154.7     .11       0  5363.6     .15       0  5451.8     .11       0
  5550.1     .15       0  5728.8     .11       0
Bank Sta=4982.7,5032.7
XS Rating Curve= 0 ,0
Exp/Cntr=0.3,0.1

Type RM Length L Ch R = 1 ,55027   ,347,347,347
BEGIN DESCRIPTION:
MCGARY CREEK 82.0
END DESCRIPTION:
XS GIS Cut Line= 3
      3779329.36     10261934.75      3779266.87     10262358.31
      3779239.11     10263596.95
#Sta/Elev= 30
  4618.5   328.9  4728.2  326.08  4826.9  323.97  4887.7  321.31  4925.7  317.32
  4968.6  311.56  4978.7  310.35  4988.8  307.13  4993.3  302.24  5004.5  302.24
  5009.9  307.71  5019.1  312.02  5039.3  310.62  5059.4  309.74  5109.4  311.88
  5177.8  311.65  5230.2  311.24  5249.5  308.07  5259.5  310.93  5269.5  311.66
  5319.1  311.43  5409.5   311.1  5429.5  309.67  5449.5  312.05  5515.4  310.39
  5569.5  312.18  5673.5   310.5  5699.6  311.98  6049.7  317.57  6285.6  330.44
#Mann= 10 ,-1 , 0
  4618.5     .11       0  4728.2     .17       0  4826.9     .15       0
  4925.7     .11       0  4968.6     .06       0  5019.1     .11       0
  5039.3     .15       0  5177.8     .11       0  5319.1     .15       0
  5515.4     .11       0
Bank Sta=4968.6,5019.1
XS Rating Curve= 0 ,0
Exp/Cntr=0.3,0.1

Type RM Length L Ch R = 1 ,54680   ,691,691,691
BEGIN DESCRIPTION:
MCGARY CREEK 81.0
END DESCRIPTION:
XS GIS Cut Line= 3
      3778985.62     10261962.48      3778930.72      10262275.7
      3778756.45     10263604.83
#Sta/Elev= 30
    4682  322.39  4721.2  320.78  4750.8  321.08  4849.8  316.34  4944.5  309.92
    4975  310.96  4983.9  309.31  4992.5  310.36  5015.5   310.6  5045.8  309.09
    5076   310.6  5096.2  307.72  5100.7  305.38  5111.9  305.38  5126.4   310.9
  5188.4  310.92  5297.9  309.56  5388.7  310.33  5444.6  308.66  5469.4  310.77
    5540   309.6  5580.3  310.61  5590.4  309.72  5597.2  310.73  5620.6  309.35
  5650.9  310.29  5771.9   310.3  5943.4  313.51  6235.9  324.63  6340.5  325.33
#Mann= 7 ,-1 , 0
    4682     .11       0  4750.8     .17       0  4849.8     .11       0
  4992.5     .15       0    5076     .09       0  5126.4     .15       0
  5188.4     .11       0
Bank Sta=5076,5126.4
XS Rating Curve= 0 ,0
Exp/Cntr=0.3,0.1

Type RM Length L Ch R = 1 ,53989   ,266,266,266
BEGIN DESCRIPTION:
MCGARY CREEK 80.0
END DESCRIPTION:
XS GIS Cut Line= 3
      3778817.86     10261811.06       3778406.6      10262108.6
      3777367.88     10263461.03
#Sta/Elev= 30
  4328.4  325.71  4355.4  325.25  4400.7  324.17  4486.6   319.2  4514.6  319.03
  4549.1   317.1  4735.7  308.19  4823.7  307.71  4937.2  309.62  4965.2  308.67
  4972.5   306.4  4978.8  302.83  4981.4  299.95  4992.6  299.95  4993.3  301.58
  5001.5  304.85  5015.7  309.07  5074.3  308.82  5142.9  306.78  5207.2  307.34
  5242.6  303.98  5321.4  307.89  5450.1  309.78  5549.8  310.28  5564.3  309.32
    5664  311.25  5807.2  310.87  5921.5  312.24  6135.3  316.32  6541.3  327.01
#Mann= 9 ,-1 , 0
  4328.4     .17       0  4355.4     .11       0  4514.6     .15       0
  4549.1     .12       0  4823.7     .15       0  4965.2     .09       0
  5015.7     .15       0  5074.3     .15       0  5450.1     .11       0
Bank Sta=4965.2,5015.7
XS Rating Curve= 0 ,0
Exp/Cntr=0.3,0.1

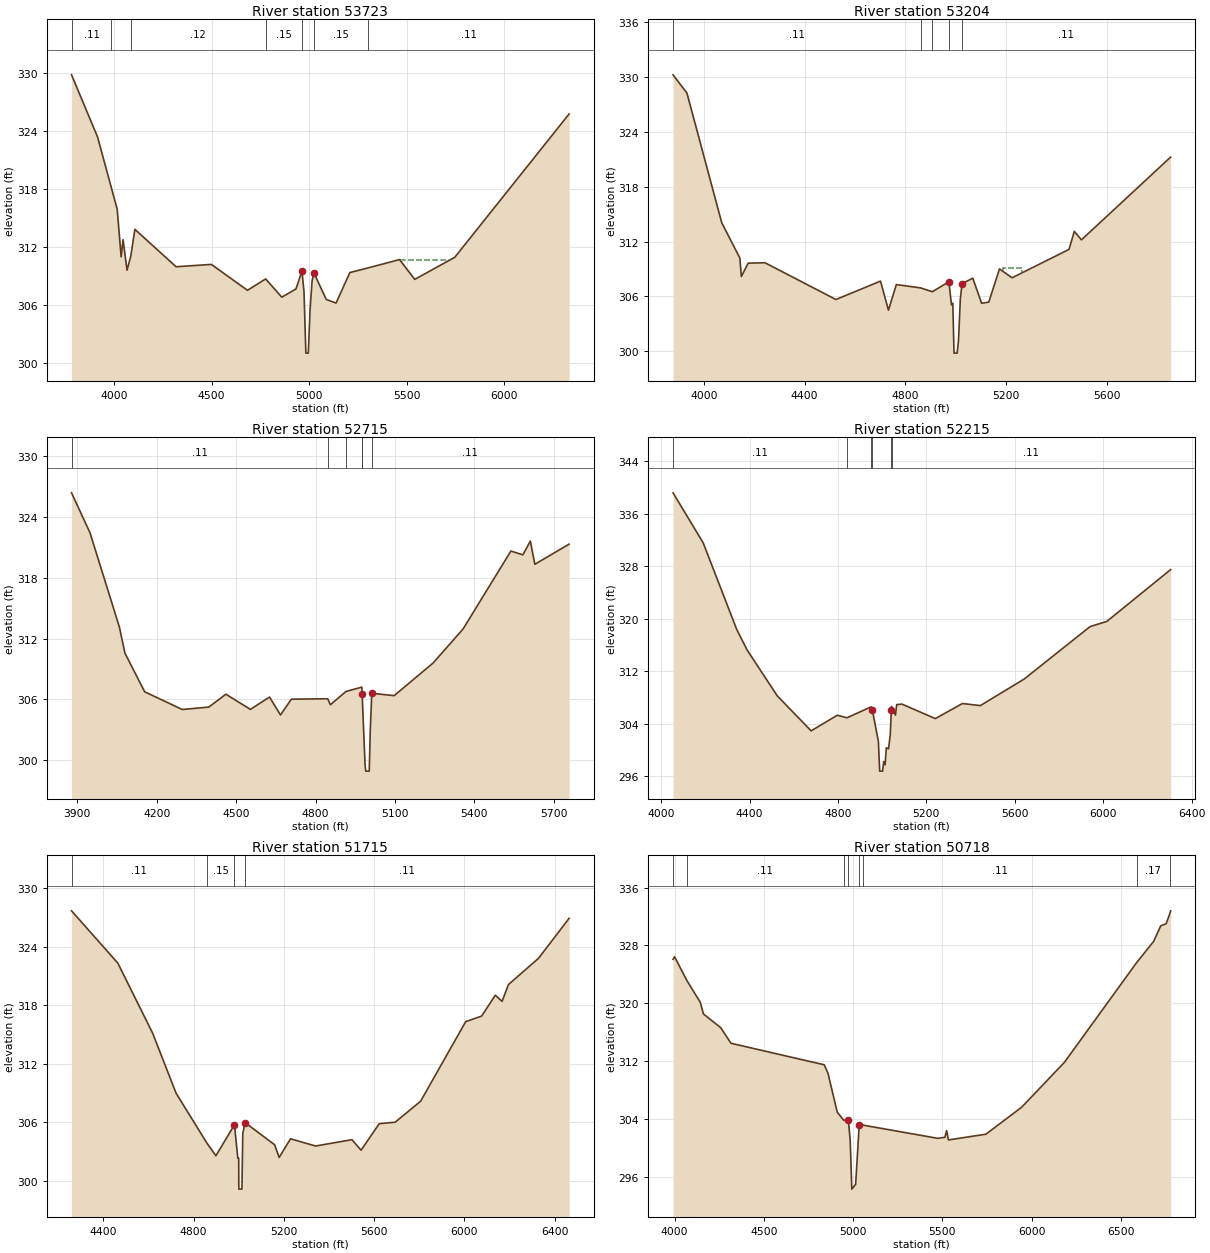
Type RM Length L Ch R = 1 ,53723   ,519,519,519
BEGIN DESCRIPTION:
MCGARY CREEK 79.0
END DESCRIPTION:
XS GIS Cut Line= 4
      3778108.78     10261008.37      3778185.17     10261772.25
      3778046.28     10262296.55      3777186.53      10263187.5
#Sta/Elev= 30
  3782.7  329.86  3916.1  323.42  3987.2  318.13  4016.6  315.95  4036.7  311.02
  4046.7   312.8  4066.8  309.64  4086.3   311.1    4107  313.87  4318.1     310
    4499  310.24  4683.7  307.56  4776.8  308.74  4859.5  306.85  4931.9   307.7
    4963  309.56  4973.3  307.38  4982.7  301.06  4995.2  301.06  5004.3  305.58
  5014.7  308.55    5024  309.36  5087.1  306.62  5137.4  306.24  5208.1   309.4
  5299.9  309.87  5462.5  310.74  5540.5  308.69  5745.5  310.98  6330.9  325.81
#Mann= 7 ,-1 , 0
  3782.7     .11       0  3987.2     .17       0  4086.3     .12       0
  4776.8     .15       0    4963     .09       0    5024     .15       0
  5299.9     .11       0
#XS Ineff= 2 ,-1
    4015    4107  313.87  5462.5    5720  310.74
Permanent Ineff=
       F       F
Bank Sta=4963,5024
XS Rating Curve= 0 ,0
Exp/Cntr=0.3,0.1

Type RM Length L Ch R = 1 ,53204   ,489,489,489
BEGIN DESCRIPTION:
MCGARY CREEK 78.0
END DESCRIPTION:
XS GIS Cut Line= 3
      3777917.85     10261161.07      3777599.57     10262237.08
      3777017.84     10262861.08
#Sta/Elev= 30
  3877.9  330.19    3933   328.2  4071.3  314.04  4143.1   310.2    4149  308.18
  4176.3  309.64  4242.9  309.68  4524.5  305.67  4701.5  307.68    4733  304.51
  4764.3   307.3  4860.5  306.94  4907.1  306.52  4972.9   307.6  4983.3  305.08
  4988.5  305.26  4993.2  299.82  5005.7  299.82  5011.1   301.2  5018.4  305.76
  5025.2   307.4  5067.7     308  5102.9  305.26  5131.3  305.39  5173.8  309.01
  5223.6  308.04  5449.8  311.14  5470.8  313.11  5499.1  312.18  5853.1  321.21
#Mann= 5 ,-1 , 0
  3877.9     .11       0  4860.5     .15       0  4907.1     .11       0
  4972.9     .06       0  5025.2     .11       0
#XS Ineff= 2 ,-1
    4140  4176.3  309.64  5187.9    5265  309.15
Permanent Ineff=
       F       F
Bank Sta=4972.9,5025.2
XS Rating Curve= 0 ,0
Exp/Cntr=0.3,0.1

Type RM Length L Ch R = 1 ,52715   ,500,500,500
BEGIN DESCRIPTION:
MCGARY CREEK 77.0
END DESCRIPTION:
XS GIS Cut Line= 3
      3777449.05     10260935.47      3777177.54     10262023.72
       3776848.4     10262706.19
#Sta/Elev= 30
  3878.4   326.4  3948.2  322.45  4059.4  313.11    4080  310.57  4154.6  306.74
  4296.4  304.99    4397  305.23  4461.3   306.5  4554.1     305  4626.2  306.22
  4667.5  304.45  4708.7  306.01  4845.9  306.05  4856.1  305.46  4914.8  306.77
  4974.8   307.2    4976 306.534    4987  299.53  4989.4   298.9  5002.8   298.9
  5006.7   302.9  5012.3  306.59    5097  306.36  5243.9  309.58    5357  312.94
  5537.9  320.65  5583.1  320.27  5611.3  321.63  5628.3  319.34  5757.7  321.33
#Mann= 6 ,-1 , 0
  3878.4     .11       0  4845.9     .15       0  4914.8     .11       0
  4974.8     .08       0    4976     .06       0  5012.3     .11       0
Bank Sta=4976,5012.3
XS Rating Curve= 0 ,0
Exp/Cntr=0.3,0.1

Type RM Length L Ch R = 1 ,52215   ,500,500,500
BEGIN DESCRIPTION:
MCGARY CREEK 76.0
END DESCRIPTION:
XS GIS Cut Line= 3
      3777217.85     10260711.07      3776938.57     10261614.69
      3776417.85     10262811.08
#Sta/Elev= 30
  4054.2  339.16  4190.3  331.56  4342.1  318.37  4389.1  315.24  4525.2  308.27
  4678.8  302.92  4797.3   305.3  4840.9  304.91  4950.4  306.58  4955.6  306.12
    4983  301.32  4988.8  296.79  5002.2  296.79    5007  298.23  5013.4  297.76
  5018.8  300.35  5028.8  300.18  5036.8  302.37  5041.7 306.166  5042.3  306.63
  5060.2  305.33  5065.7  306.91  5089.1     307  5240.6  304.79  5363.3  307.08
  5444.5  306.77  5642.9  310.82  5940.4  318.79  6016.2  319.58  6304.8  327.47
#Mann= 6 ,-1 , 0
  4054.2     .11       0  4840.9     .15       0  4950.4     .11       0
  4955.6     .06       0  5041.7     .08       0  5042.3     .11       0
Bank Sta=4955.6,5041.7
XS Rating Curve= 0 ,0
Exp/Cntr=0.3,0.1

Type RM Length L Ch R = 1 ,51715   ,997,997,997
BEGIN DESCRIPTION:
MCGARY CREEK 75.0
END DESCRIPTION:
XS GIS Cut Line= 3
      3776900.43     10260668.11      3776554.38     10261323.23
       3776369.2     10262775.67
#Sta/Elev= 30
  4259.1  327.66  4464.2   322.3  4618.3  315.13  4722.7  308.95  4858.8  303.86
  4898.8  302.55  4981.2  305.73    4996   302.3    5000   302.3  5000.3  299.63
  5000.8  299.13  5014.2  299.13    5018  304.82  5028.1  305.95  5159.1  303.68
  5179.3  302.38  5229.7  304.29  5340.6  303.55  5501.9   304.2  5542.2  303.12
  5622.8  305.84  5693.4  305.99  5806.1  308.14  6005.9   316.3  6076.5  316.87
    6137  319.01  6167.2  318.38  6195.3   320.1  6328.5  322.79  6464.2  326.89
#Mann= 4 ,-1 , 0
  4259.1     .11       0  4858.8     .15       0  4981.2     .09       0
  5028.1     .11       0
Bank Sta=4981.2,5028.1
XS Rating Curve= 0 ,0
Exp/Cntr=0.3,0.1

Type RM Length L Ch R = 1 ,50718   ,501,501,501
BEGIN DESCRIPTION:
MCGARY CREEK 74.0
END DESCRIPTION:
XS GIS Cut Line= 3
      3776057.71     10260332.89      3775793.62     10261306.82
      3775799.75     10263086.31
#Sta/Elev= 30
  3990.9  326.09  3999.4  326.44  4068.8  323.14  4144.4  320.11  4161.1  318.54
  4258.4  316.63  4315.3  314.49  4838.6  311.51  4859.3  310.33  4911.2  304.96
  4947.8  303.84  4973.3  303.88  4983.7   301.1  4992.8  294.33  5014.2  294.99
  5034.2  303.17  5054.2  303.18  5474.3  301.35  5514.3  301.49  5524.3  302.42
  5534.3  301.13  5744.3  301.92  5944.3  305.64  6184.3  311.85  6588.9  325.63
  6684.3  328.56  6724.3  330.72  6754.3  331.01  6776.1  332.46  6779.5  332.79
#Mann= 8 ,-1 , 0
  3990.9     .17       0  4068.8     .11       0  4947.8     .15       0
  4973.3     .09       0  5034.2     .15       0  5054.2     .11       0
  6588.9     .17       0  6776.1     .11       0
Bank Sta=4973.3,5034.2
XS Rating Curve= 0 ,0
Exp/Cntr=0.3,0.1

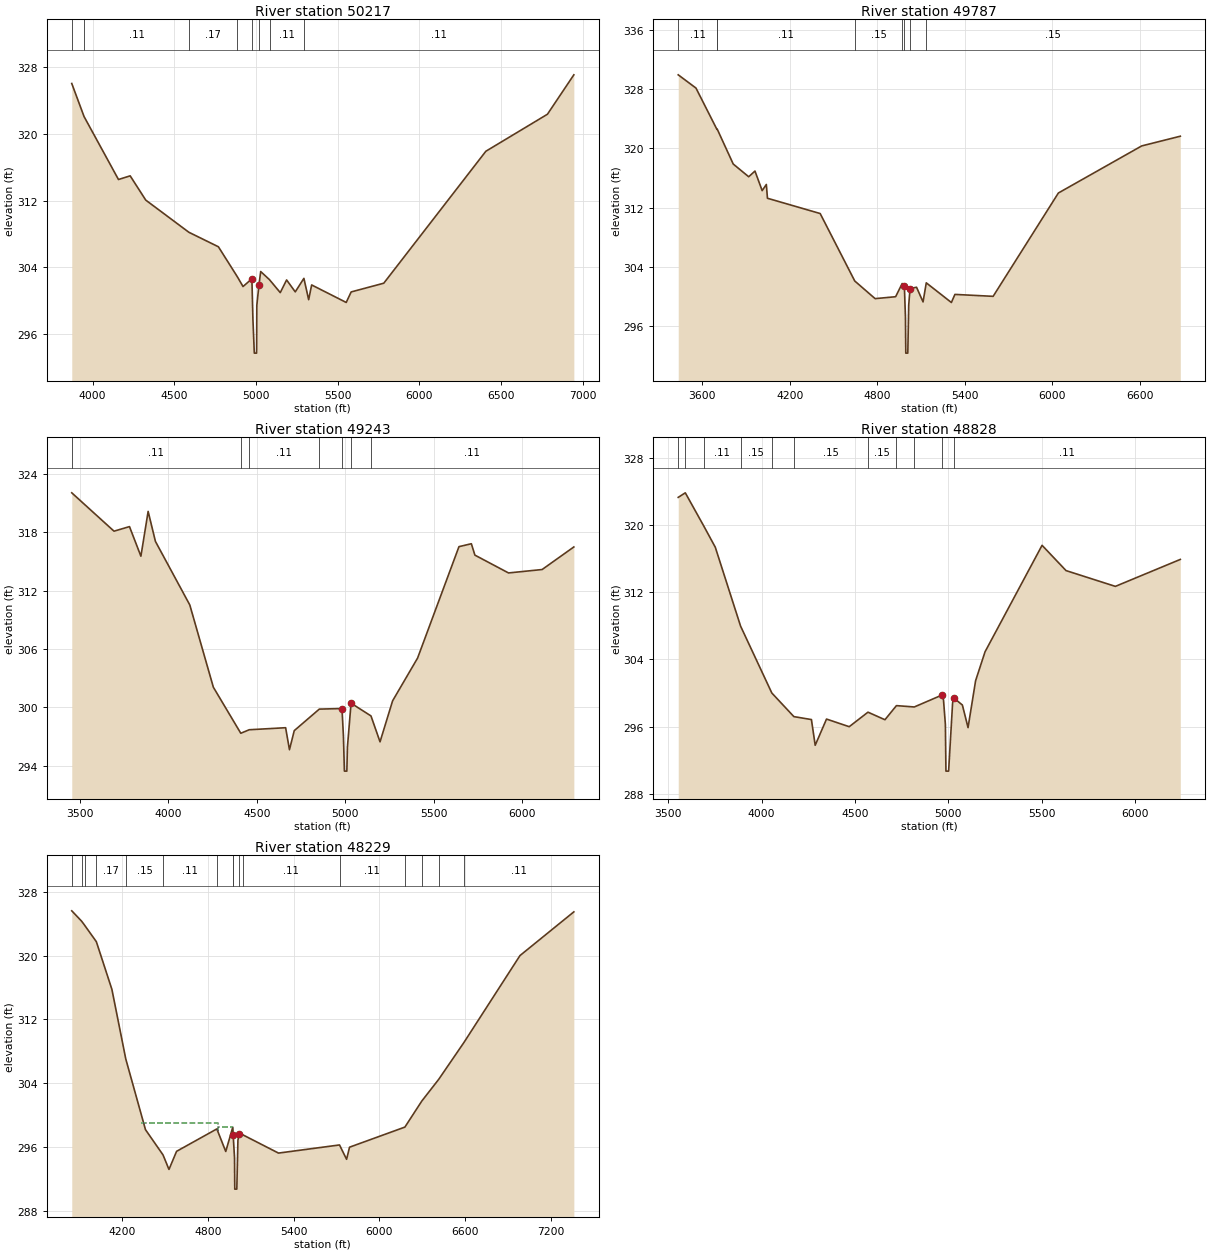
Type RM Length L Ch R = 1 ,50217   ,430,430,430
BEGIN DESCRIPTION:
MCGARY CREEK 73.0
END DESCRIPTION:
XS GIS Cut Line= 3
      3775933.42     10260278.05      3775397.94     10261053.19
      3774571.14     10263017.46
#Sta/Elev= 30
  3873.1  326.05  3948.4  322.08    4159  314.53  4230.6  314.97    4326  312.06
  4589.9   308.2  4770.7  306.46  4886.1  302.88  4921.4  301.69  4975.7  302.62
    4982  297.76  4990.5   293.7  5004.2   293.7  5004.7   294.2  5005.8  299.42
  5019.1   301.9  5029.5  303.49  5083.5  302.51  5149.3  300.96  5188.2  302.48
  5241.1  301.05    5294  302.67  5323.2  300.11  5341.5  301.88  5553.1  299.78
  5583.2  301.04    5783  302.09  6407.8  317.92  6784.7  322.36  6946.4  327.09
#Mann= 8 ,-1 , 0
  3873.1     .17       0  3948.4     .11       0  4589.9     .17       0
  4886.1     .15       0  4975.7     .09       0  5019.1     .15       0
  5083.5     .11       0    5294     .11       0
Bank Sta=4975.7,5019.1
XS Rating Curve= 0 ,0
Exp/Cntr=0.3,0.1

Type RM Length L Ch R = 1 ,49787   ,544,544,544
BEGIN DESCRIPTION:
MCGARY CREEK 72.0
END DESCRIPTION:
XS GIS Cut Line= 4
      3775851.81     10259883.38      3775090.15     10260782.64
       3774808.3     10261338.88      3774206.88     10262865.11
#Sta/Elev= 30
  3434.3   329.9  3556.1  328.11  3699.3  322.55    3702  322.56  3811.3  317.87
  3917.5  316.15  3960.4  316.92  4009.8  314.28  4038.4  315.11  4046.1  313.25
  4407.5  311.19  4644.6  302.09  4784.3  299.71  4924.9  299.97  4969.7  301.75
  4984.7  301.45  4992.2  297.24  4994.6  292.36  5008.3  292.36  5014.6  298.84
  5023.7  301.06  5068.2  301.25  5112.8  299.27    5135  301.84  5307.2  299.19
  5331.5  300.28  5593.4  300.02  6040.8  313.96  6612.1  320.31  6876.8  321.62
#Mann= 8 ,-1 , 0
  3434.3     .11       0  3699.3     .15       0    3702     .11       0
  4644.6     .15       0  4969.7     .11       0  4984.7     .06       0
  5023.7     .11       0    5135     .15       0
Bank Sta=4984.7,5023.7
XS Rating Curve= 0 ,0
Exp/Cntr=0.3,0.1

Type RM Length L Ch R = 1 ,49243   ,415,415,415
BEGIN DESCRIPTION:
MCGARY CREEK 71.0
END DESCRIPTION:
XS GIS Cut Line= 3
      3774723.37     10259579.52      3774293.68     10261532.66
      3774289.34      10262370.3
#Sta/Elev= 30
  3454.6  322.04  3693.3   318.1  3780.8  318.57  3845.3  315.53  3886.2  320.13
  3927.4  317.05  4121.7  310.52  4254.8  302.07  4409.8  297.34  4457.4   297.7
  4663.2  297.91  4684.9  295.65    4712  297.61  4853.5  299.82  4981.8  299.88
  4989.9  297.05  4995.4  293.45  5009.2  293.45  5012.5  295.92    5033  300.43
  5145.6  299.12  5196.8  296.46  5267.8  300.67  5409.2  305.07  5642.9  316.51
  5712.9  316.81  5732.9  315.64  5922.9  313.81  6112.9  314.16  6292.1  316.48
#Mann= 7 ,-1 , 0
  3454.6     .11       0  4409.8     .15       0  4457.4     .11       0
  4853.5     .11       0  4981.8     .06       0    5033     .11       0
  5145.6     .11       0
Bank Sta=4981.8,5033
XS Rating Curve= 0 ,0
Exp/Cntr=0.3,0.1

Type RM Length L Ch R = 1 ,48828   ,599,599,599
BEGIN DESCRIPTION:
MCGARY CREEK 70.0
END DESCRIPTION:
XS GIS Cut Line= 3
      3774154.79     10259744.45      3774002.88      10260868.6
      3774232.87     10262404.81
#Sta/Elev= 30
    3554  323.29  3591.8  323.83  3690.4  319.89  3752.4  317.35  3887.7  307.96
  4055.1  299.99  4173.1  297.18    4267  296.83  4287.2  293.77  4347.8  296.89
  4469.2  295.98  4569.8  297.71  4660.6  296.81  4722.1  298.49  4817.7  298.33
  4963.9  299.73    4974  299.19  4984.1  296.25  4987.1  290.69  5001.4  290.69
  5022.7  298.79  5027.7  299.43  5075.1  298.56  5105.4  295.87  5145.9  301.46
  5196.4   304.9  5501.7  317.58  5629.9  314.57  5894.1  312.69  6241.7   315.9
#Mann= 11 ,-1 , 0
    3554     .11       0  3591.8     .17       0  3690.4     .11       0
  3887.7     .15       0  4055.1     .15       0  4173.1     .15       0
  4569.8     .15       0  4722.1     .15       0  4817.7     .11       0
  4963.9     .06       0  5027.7     .11       0
Bank Sta=4963.9,5027.7
XS Rating Curve= 0 ,0
Exp/Cntr=0.3,0.1

Type RM Length L Ch R = 1 ,48229   ,498,498,498
BEGIN DESCRIPTION:
MCGARY CREEK 69.0
END DESCRIPTION:
XS GIS Cut Line= 3
      3774017.86     10259711.05      3773626.88     10260795.63
      3772117.86     10262611.06
#Sta/Elev= 30
  3847.1  325.62  3916.1  324.32  3937.1  323.81  4019.1  321.75    4128  315.77
  4225.1  307.04  4362.9  298.18  4485.8  295.01  4527.4  293.19  4580.6  295.46
  4862.4  298.27  4924.7  295.44  4973.9  298.49  4976.7 297.475  4986.1  294.66
  4987.8  290.72  5002.1  290.72  5009.9  296.84  5017.8  297.68  5046.3  297.51
  5293.8  295.24  5720.8  296.26  5770.3  294.46  5791.1  295.98  6178.4   298.5
  6296.9  301.77  6415.1  304.49  6591.2   309.1  6983.8  320.01  7360.7  325.49
#Mann= 16 ,-1 , 0
  3847.1     .11       0  3916.1     .17       0  3937.1     .11       0
  4019.1     .17       0  4225.1     .15       0  4485.8     .11       0
  4862.4     .13       0  4973.9     .11       0  4976.7     .08       0
  5017.8     .85       0  5046.3     .11       0  5720.8     .11       0
  6178.4     .17       0  6296.9     .11       0  6415.1     .17       0
  6591.2     .11       0
#XS Ineff= 2 ,-1
    4330  4868.7  298.99    4869  4973.9  298.49
Permanent Ineff=
       F       F
Bank Sta=4976.7,5017.8
XS Rating Curve= 0 ,0
Exp/Cntr=0.3,0.1