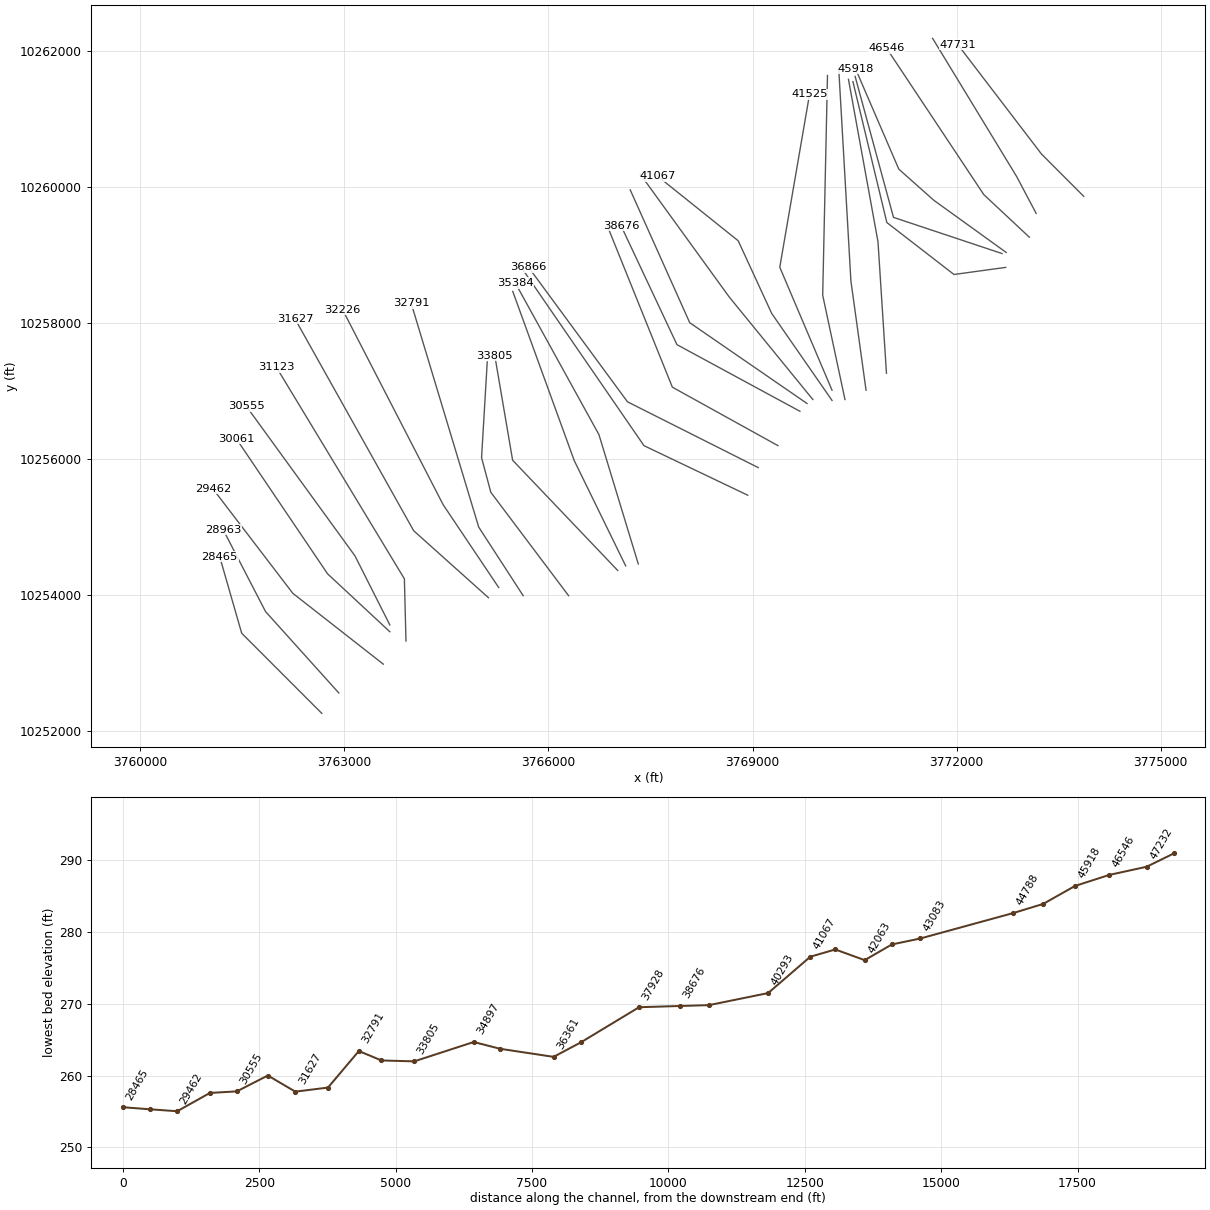
HEC-RAS study MCGARY CREEK.prj: MCGARY CREEK Base Level Engineering

--- MCGARY CREEK.g01 (geometry) --- (continued)

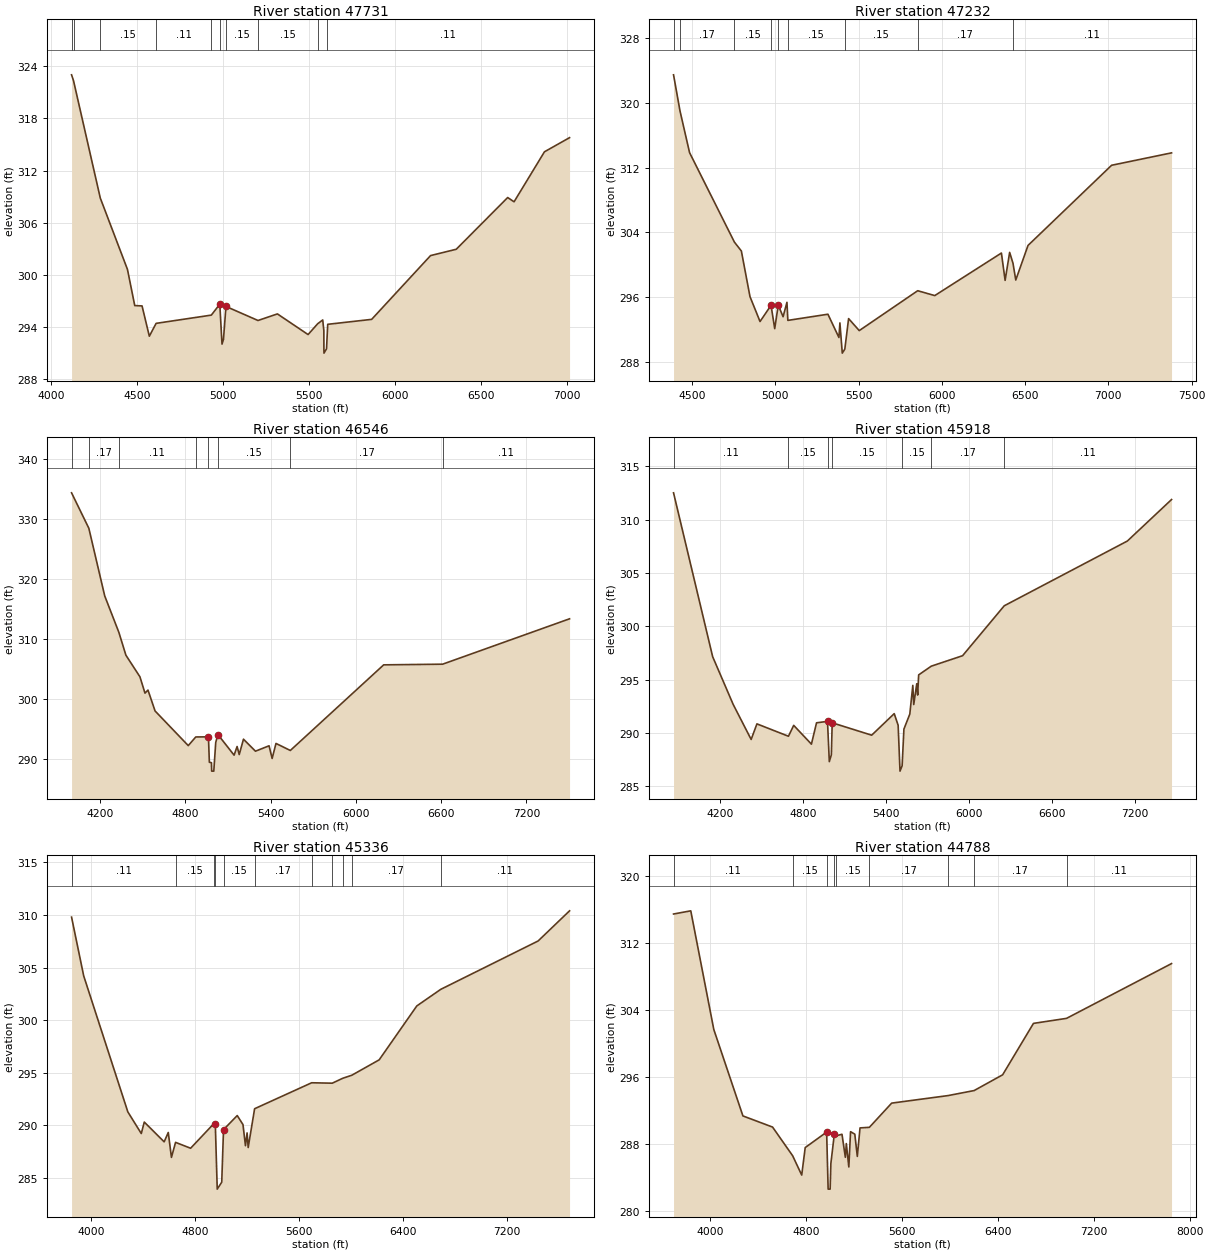
Type RM Length L Ch R = 1 ,47731   ,499,499,499
BEGIN DESCRIPTION:
MCGARY CREEK 68.0
END DESCRIPTION:
XS GIS Cut Line= 3
      3773867.88     10259861.05      3773245.52     10260484.33
      3772020.21     10262087.12
#Sta/Elev= 30
  4119.2  323.03  4130.5  322.36  4286.4  308.83  4444.5  300.61  4486.9  296.44
  4529.4   296.4  4571.8  292.91  4611.3  294.39  4932.6  295.34  4981.9   296.6
  4994.8     292  5003.3  292.55  5017.8  296.34  5204.3  294.72  5317.1  295.48
  5495.7   293.1  5551.8  294.35  5580.9  294.78  5587.5  293.55  5587.8  291.46
  5588.3  290.96  5603.1  291.46    5610  294.28  5865.7  294.85  6208.5   302.2
  6358.1  302.93  6657.4  308.89  6694.6   308.4  6871.4  314.16  7017.5  315.79
#Mann= 10 ,-1 , 0
  4119.2     .17       0  4130.5     .11       0  4286.4     .15       0
  4611.3     .11       0  4932.6     .15       0  4981.9     .09       0
  5017.8     .15       0  5204.3     .15       0  5551.8     .11       0
  5603.1     .11       0
Bank Sta=4981.9,5017.8
XS Rating Curve= 0 ,0
Exp/Cntr=0.3,0.1

Type RM Length L Ch R = 1 ,47232   ,686,686,686
BEGIN DESCRIPTION:
MCGARY CREEK 67.0
END DESCRIPTION:
XS GIS Cut Line= 3
      3773167.84     10259611.08      3772882.31     10260150.92
      3771646.09     10262183.74
#Sta/Elev= 30
  4389.3  323.44    4428  318.99  4485.5  313.84  4754.7   302.8  4796.5   301.7
  4848.3  296.07  4908.6     293  4974.7     295  4996.7  292.12    5018  295.02
    5047  293.59  5070.2  295.37  5075.6  293.14  5316.2   293.9  5382.2  291.03
  5388.1  292.83  5402.4   289.1  5417.7   289.6  5440.3  293.36  5504.3  291.88
  5855.3   296.8  5957.6   296.2  6357.8  301.45    6380  298.08  6407.2  301.53
  6427.3  300.19    6444  298.12  6517.6  302.39  7019.4  312.28  7379.2  313.81
#Mann= 9 ,-1 , 0
  4389.3     .11       0    4428     .17       0  4754.7     .15       0
  4974.7     .09       0    5018     .15       0  5075.6     .15       0
  5417.7     .15       0  5855.3     .17       0  6427.3     .11       0
Bank Sta=4974.7,5018
XS Rating Curve= 0 ,0
Exp/Cntr=0.3,0.1

Type RM Length L Ch R = 1 ,46546   ,628,628,628
BEGIN DESCRIPTION:
MCGARY CREEK 66.0
END DESCRIPTION:
XS GIS Cut Line= 3
      3773067.88     10259261.04      3772399.36     10259885.81
      3770967.08     10262042.04
#Sta/Elev= 30
  3999.7  334.31  4121.2  328.41    4233  317.14  4332.4  311.08    4382  307.27
  4480.7  303.67  4516.3  300.95  4537.3  301.46  4587.2  297.98  4820.7  292.21
  4873.6  293.65  4962.8  293.67  4969.1  289.44  4983.9  289.36  4985.5  287.96
  5000.3  287.96    5014  292.73    5029  294.06  5143.2  290.62  5164.3  292.06
  5179.3  290.72  5209.2  293.28  5293.6  291.28  5389.2  292.18  5410.8  290.07
  5437.9  292.57  5538.8   291.4  6195.6  305.66  6610.2  305.77  7503.3  313.33
#Mann= 8 ,-1 , 0
  3999.7     .11       0  4121.2     .17       0  4332.4     .11       0
  4873.6     .15       0  4962.8     .09       0    5029     .15       0
  5538.8     .17       0  6610.2     .11       0
Bank Sta=4962.8,5029
XS Rating Curve= 0 ,0
Exp/Cntr=0.3,0.1

Type RM Length L Ch R = 1 ,45918   ,582,582,582
BEGIN DESCRIPTION:
MCGARY CREEK 65.0
END DESCRIPTION:
XS GIS Cut Line= 4
      3772727.52     10259036.82      3771664.98     10259802.47
      3771149.36     10260260.81      3770513.95     10261734.73
#Sta/Elev= 30
  3861.4  312.51  4144.5  297.15  4293.2  292.67  4423.2  289.39    4465  290.85
  4693.1  289.69  4731.2  290.71  4859.4  288.95  4896.4  290.95  4975.8 291.084
  4988.9  287.31  5003.6  287.95  5009.8  290.95  5295.6  289.79  5458.7  291.81
  5487.1  290.72  5500.6  286.42  5515.9  286.92  5528.9  290.36  5571.6  291.77
  5593.3  294.46    5600  292.66  5621.7  294.61  5628.4  293.55  5635.5  295.44
  5726.9  296.26  5953.5  297.24  6255.1  301.92  7146.2  307.99    7466  311.88
#Mann= 7 ,-1 , 0
  3861.4     .11       0  4693.1     .15       0  4975.8     .09       0
  5009.8     .15       0  5515.9     .15       0  5726.9     .17       0
  6255.1     .11       0
Bank Sta=4975.8,5009.8
XS Rating Curve= 0 ,0
Exp/Cntr=0.3,0.1

Type RM Length L Ch R = 1 ,45336   ,548,548,548
BEGIN DESCRIPTION:
MCGARY CREEK 64.0
END DESCRIPTION:
XS GIS Cut Line= 3
      3772666.39     10259020.27       3771071.3     10259551.97
      3770507.06     10261624.46
#Sta/Elev= 30
  3850.3   309.8  3943.6  304.21    4283  291.27  4386.4  289.21  4409.5   290.3
  4562.3  288.42  4593.9  289.31  4618.3  286.94    4650  288.37  4765.8  287.81
  4941.8  290.12  4955.6   290.1  4970.4  283.92    5005  284.58  5018.8  289.58
  5124.2  290.92  5168.4  290.06  5187.5  288.05    5200  289.27  5208.5  287.88
  5257.8  291.57  5696.5  294.04  5854.9     294  5935.8  294.47  6005.8  294.76
  6215.5  296.22    6505  301.35  6689.2  302.93  7437.7  307.53  7679.6   310.4
#Mann= 11 ,-1 , 0
  3850.3     .11       0    4650     .15       0  4941.8     .12       0
  4955.6     .09       0  5018.8     .15       0  5257.8     .17       0
  5696.5     .11       0  5854.9     .17       0  5935.8     .11       0
  6005.8     .17       0  6689.2     .11       0
Bank Sta=4955.6,5018.8
XS Rating Curve= 0 ,0
Exp/Cntr=0.3,0.1

Type RM Length L Ch R = 1 ,44788   ,1705,1705,1705
BEGIN DESCRIPTION:
Mapping XS 8172d54d
END DESCRIPTION:
XS GIS Cut Line= 4
      3772719.88     10258816.65      3771960.34     10258712.49
      3770973.65     10259476.01       3770474.8     10261547.32
#Sta/Elev= 30
  3698.5   315.5  3841.9  315.88  4033.6  301.71  4275.9  291.39  4522.6  290.06
    4690  286.63  4765.3  284.33  4794.3  287.61  4972.7  289.46  4985.2  282.65
  5001.8  282.65    5008  285.72  5036.9  289.24  5049.9  289.01  5100.5   289.2
  5128.4  286.45  5136.5  288.09  5157.4   285.3  5171.8  289.51  5207.2  289.21
    5228  286.56  5250.6  289.96  5328.5  290.03  5514.1  292.92  5983.8  293.82
  6200.5  294.42  6437.5   296.3  6694.2  302.44  6969.5  303.04  7843.3  309.58
#Mann= 9 ,-1 , 0
  3698.5     .11       0    4690     .15       0  4972.7     .09       0
  5036.9     .12       0  5049.9     .15       0  5328.5     .17       0
  5983.8     .11       0  6200.5     .17       0  6969.5     .11       0
Bank Sta=4972.7,5036.9
XS Rating Curve= 0 ,0
Exp/Cntr=0.3,0.1

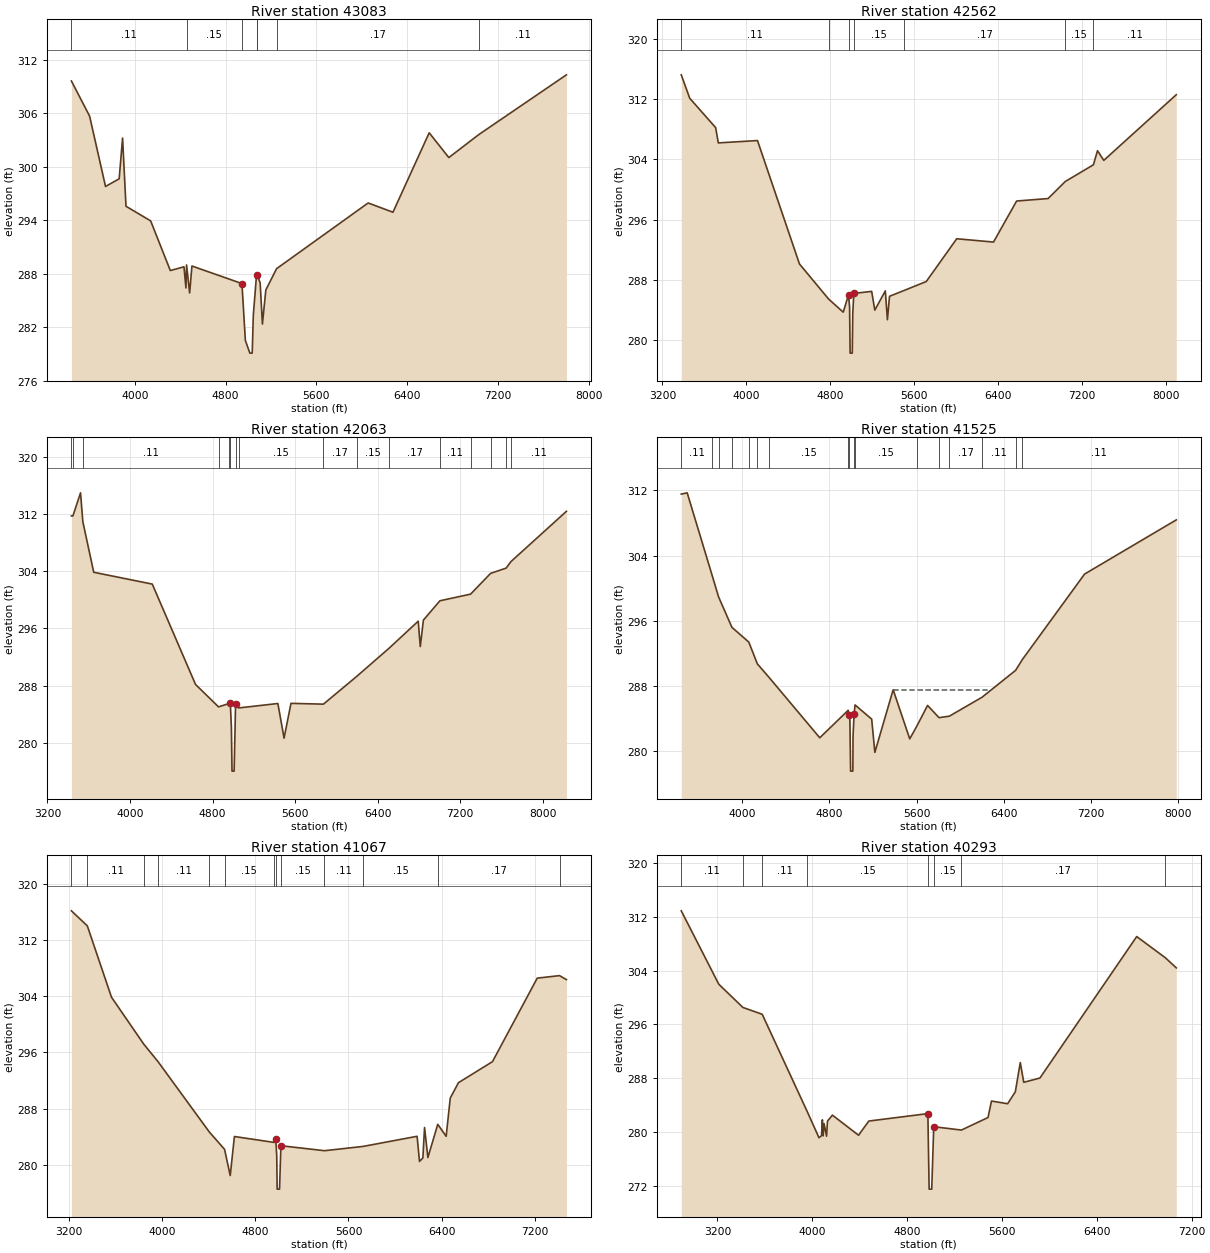
Type RM Length L Ch R = 1 ,43083   ,521,521,521
BEGIN DESCRIPTION:
MCGARY CREEK 63.0
END DESCRIPTION:
XS GIS Cut Line= 3
      3770967.85     10257261.08      3770843.44     10259193.89
      3770409.41     10261581.05
#Sta/Elev= 30
  3441.8  309.62  3602.1  305.68  3742.4  297.79  3862.7  298.65  3892.7  303.22
  3922.8  295.57  4140.3  293.93  4313.6  288.36  4433.8  288.78  4451.3  286.41
  4456.5  288.99  4483.9  285.85    4504  288.87  4944.9   286.9    4975  280.52
  5014.8   279.1  5035.3   279.1  5045.1  283.35  5073.3  287.85  5078.3   287.9
  5105.2  286.99  5125.3  282.36  5155.3  286.18  5250.2  288.57  6057.3  295.94
  6275.8   294.9  6595.4  303.81  6768.2  301.03  7033.7  303.62  7804.9  310.31
#Mann= 7 ,-1 , 0
  3441.8     .11       0  4456.5     .15       0  4944.9     .09       0
  5073.3     .12       0  5078.3     .15       0  5250.2     .17       0
  7033.7     .11       0
Bank Sta=4944.9,5073.3
XS Rating Curve= 0 ,0
Exp/Cntr=0.3,0.1

Type RM Length L Ch R = 1 ,42562   ,499,499,499
BEGIN DESCRIPTION:
MCGARY CREEK 62.0
END DESCRIPTION:
XS GIS Cut Line= 3
      3770667.85     10257011.05      3770445.34      10258616.4
      3770267.85     10261711.12
#Sta/Elev= 30
  3379.3  315.23  3460.1  312.12  3707.2  308.22  3732.7  306.19  4106.2   306.5
  4506.6  290.11  4785.4  285.44  4923.9  283.71  4974.4  286.02  4984.5  284.41
  4989.6  278.27  5010.1  278.27  5014.7   283.5  5024.7   286.2    5195  286.47
    5225  283.98  5325.2  286.54  5345.2  282.71  5365.3  285.82  5504.4  286.59
  5715.8  287.78  6006.3  293.46  6356.9  293.02  6577.3  298.47  6877.7   298.8
    7041  301.06  7309.6  303.28  7348.5  305.15  7408.6  303.87  8099.8  312.59
#Mann= 7 ,-1 , 0
  3379.3     .11       0  4785.4     .15       0  4974.4     .09       0
  5024.7     .15       0  5504.4     .17       0    7041     .15       0
  7309.6     .11       0
Bank Sta=4974.4,5024.7
XS Rating Curve= 0 ,0
Exp/Cntr=0.3,0.1

Type RM Length L Ch R = 1 ,42063   ,538,538,538
BEGIN DESCRIPTION:
MCGARY CREEK 61.0
END DESCRIPTION:
XS GIS Cut Line= 3
      3770358.04     10256874.58      3770030.59      10258407.7
      3770101.06     10261637.23
#Sta/Elev= 30
  3432.3  311.71  3446.6   311.7  3520.7  314.93    3543   310.9  3648.6  303.84
  4216.1  302.19  4635.3  288.18  4858.2  285.05  4962.5  285.53  4972.8  285.54
    4983  282.08  4988.9  276.08  5009.5  276.08  5023.4  285.41  5053.4   284.9
  5433.5  285.52  5493.5  280.68  5560.3  285.54  5875.1  285.43  6197.3   289.3
  6512.2  293.25  6793.8  297.01  6813.8  293.47  6843.8  297.16    7004  299.86
  7301.5  300.79  7495.7  303.69    7646  304.42  7692.4  305.33  8230.3  312.35
#Mann= 16 ,-1 , 0
  3432.3     .11       0  3446.6     .17       0    3543     .11       0
  4858.2     .15       0  4962.5     .12       0  4972.8     .09       0
  5023.4     .12       0  5053.4     .15       0  5875.1     .17       0
  6197.3     .15       0  6512.2     .17       0    7004     .11       0
  7301.5     .15       0  7495.7     .11       0    7646     .15       0
  7692.4     .11       0
Bank Sta=4972.8,5023.4
XS Rating Curve= 0 ,0
Exp/Cntr=0.3,0.1

Type RM Length L Ch R = 1 ,41525   ,458,458,458
BEGIN DESCRIPTION:
MCGARY CREEK 60.0
END DESCRIPTION:
XS GIS Cut Line= 3
      3770167.87     10257011.03       3769399.7     10258819.02
      3769837.21     10261360.73
#Sta/Elev= 30
  3439.9  311.55  3494.3  311.71  3722.5  301.62  3782.3  298.95    3905  295.21
  4059.9   293.4  4138.1  290.73  4243.1  289.11  4711.2  281.66  4971.9  285.03
  4982.2  284.45  4987.7  283.82  4994.2  277.57  5014.8  277.57  5016.7  281.93
  5026.3  284.56    5035  285.69  5187.7  283.95  5216.8  279.87  5384.8  287.55
    5537  281.53  5599.3  283.02  5700.7  285.63  5805.6  284.13  5900.3  284.31
  6201.4  286.64  6508.5  289.93  6571.8  291.28  7141.5  301.74  7983.4  308.39
#Mann= 17 ,-1 , 0
  3439.9     .11       0  3722.5     .17       0  3782.3     .11       0
    3905     .17       0  4059.9     .11       0  4138.1     .17       0
  4243.1     .15       0  4971.9     .12       0  4982.2     .09       0
  5026.3     .12       0    5035     .15       0  5599.3     .11       0
  5805.6     .15       0  5900.3     .17       0  6201.4     .11       0
  6508.5     .15       0  6571.8     .11       0
#XS Ineff= 1 ,-1
  5384.8    6275  287.55
Permanent Ineff=
       F
Bank Sta=4982.2,5026.3
XS Rating Curve= 0 ,0
Exp/Cntr=0.3,0.1

Type RM Length L Ch R = 1 ,41067   ,774,774,774
BEGIN DESCRIPTION:
MCGARY CREEK 59.0
END DESCRIPTION:
XS GIS Cut Line= 4
      3770167.83      10256861.1      3769281.65     10258138.47
      3768788.59     10259207.91      3767601.96     10260158.61
#Sta/Elev= 30
  3219.7  316.12  3356.4  313.98  3564.1  303.84  3840.8  297.18  3964.8  294.66
  4404.6  284.68  4535.3  282.22  4584.1  278.49  4619.9  284.04  4960.7   283.2
  4975.4  283.67  4983.7  281.28  4987.2  276.56  5007.8  276.56  5019.5  282.73
  5393.5  282.02  5725.3  282.63  6189.5  284.07  6210.3   280.5  6239.1  280.99
  6253.5  285.32  6282.3  281.05    6367  285.77  6439.2  284.07  6474.4   289.5
  6544.8  291.69  6837.1  294.68  7221.5  306.55    7413  306.91  7472.5  306.34
#Mann= 13 ,-1 , 0
  3219.7     .17       0  3356.4     .11       0  3840.8     .17       0
  3964.8     .11       0  4404.6     .17       0  4535.3     .15       0
  4960.7     .12       0  4975.4     .09       0  5019.5     .15       0
  5393.5     .11       0  5725.3     .15       0    6367     .17       0
    7413     .11       0
Bank Sta=4975.4,5019.5
XS Rating Curve= 0 ,0
Exp/Cntr=0.3,0.1

Type RM Length L Ch R = 1 ,40293   ,1084,1084,1084
BEGIN DESCRIPTION:
MCGARY CREEK 58.0
END DESCRIPTION:
XS GIS Cut Line= 3
       3769885.8     10256874.59      3768656.65     10258381.52
      3767348.01     10260187.48
#Sta/Elev= 30
    2895  312.91  3211.4  301.99  3414.8  298.53  3577.8  297.51  3957.2  283.04
  4056.5  279.14  4077.7  279.44  4085.2   281.8  4091.6  279.41  4099.6  281.24
  4120.4  279.37  4128.3  281.62  4169.9   282.5  4390.3  279.51  4476.5  281.62
  4974.9  282.73  4985.5  271.49  5007.5  271.49  5024.3  280.78  5257.8  280.28
  5482.1  282.15  5511.5   284.6  5647.5   284.2  5712.5  285.97  5754.2  290.33
  5783.6  287.39  5919.7  288.02  6736.3  309.08  6976.7  305.94  7069.9  304.42
#Mann= 8 ,-1 , 0
    2895     .11       0  3414.8     .17       0  3577.8     .11       0
  3957.2     .15       0  4974.9     .09       0  5024.3     .15       0
  5257.8     .17       0  6976.7     .11       0
Bank Sta=4974.9,5024.3
XS Rating Curve= 0 ,0
Exp/Cntr=0.3,0.1

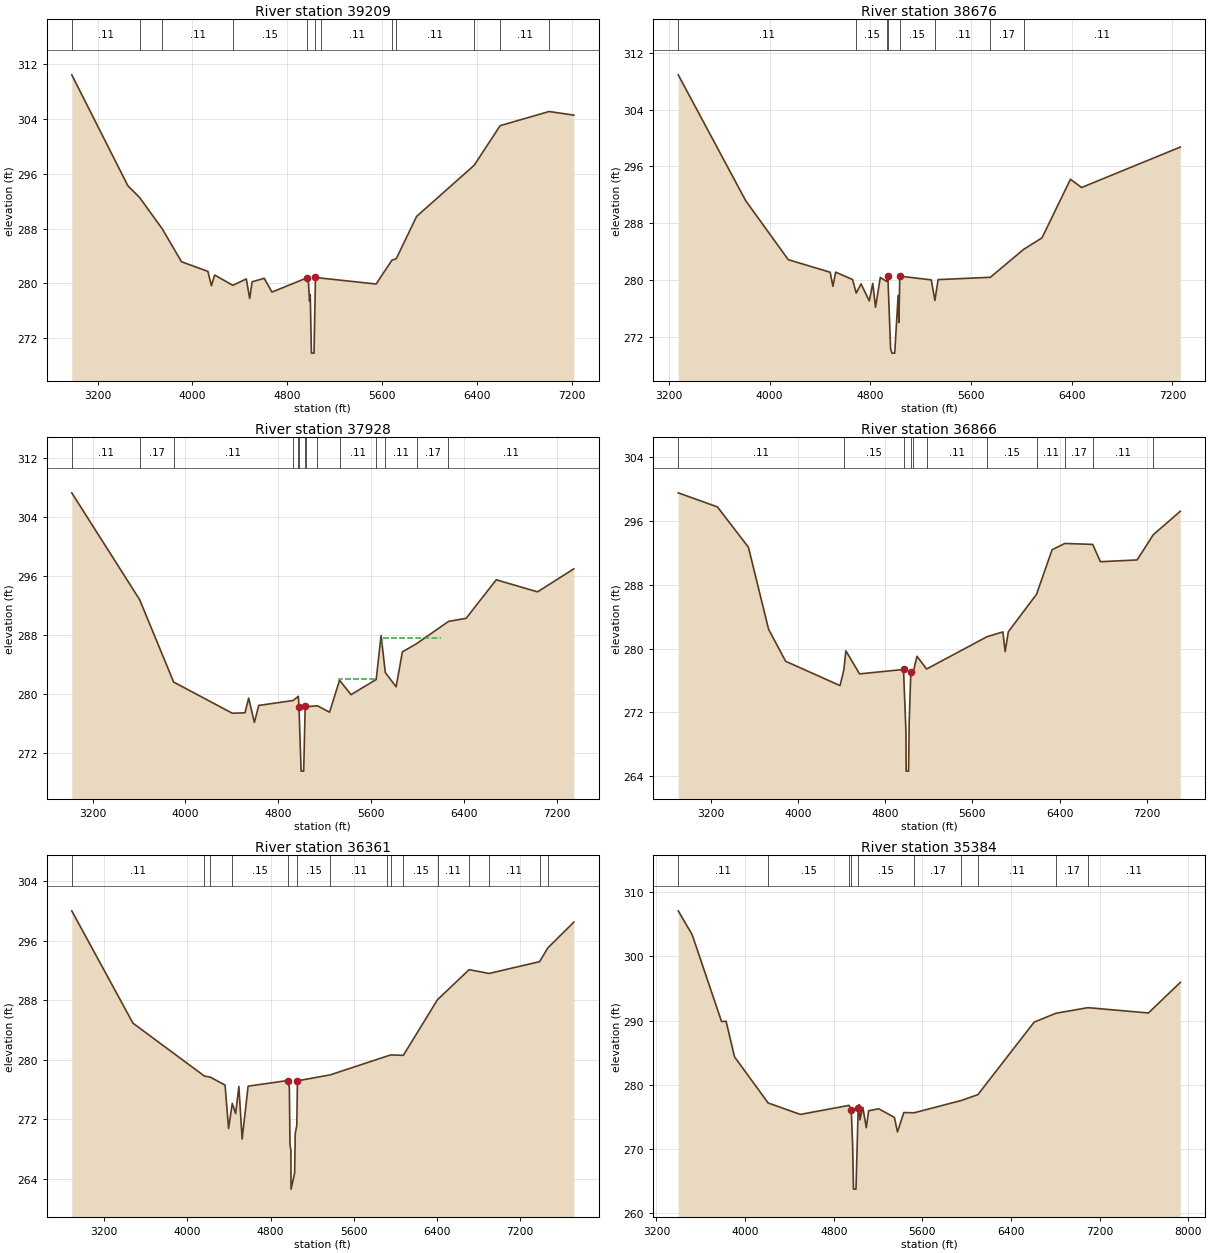
Type RM Length L Ch R = 1 ,39209   ,533,533,533
BEGIN DESCRIPTION:
MCGARY CREEK 57.0
END DESCRIPTION:
XS GIS Cut Line= 3
      3769799.92     10256816.39      3768075.92     10258003.92
      3767201.12      10259956.6
#Sta/Elev= 30
  2982.6  310.48  3455.3  294.28  3554.2  292.56  3745.6  287.97    3908  283.16
  4130.2  281.76    4160  279.67  4187.2  281.22  4340.8  279.72  4454.4  280.65
  4482.6   277.8  4503.5  280.24    4605  280.74  4670.6  278.73  4964.4   280.8
  4978.3  280.11  4987.1  277.43  4993.2  278.36  5003.1  269.81  5025.2  269.81
  5037.2  280.88  5086.4  280.77  5548.9  279.91  5681.6  283.39  5718.5  283.61
    5890  289.79  6375.9  297.27  6594.2  303.05  7007.2  305.12  7215.7  304.59
#Mann= 12 ,-1 , 0
  2982.6     .11       0  3554.2     .17       0  3745.6     .11       0
  4340.8     .15       0  4964.4     .09       0  5037.2     .15       0
  5086.4     .11       0  5681.6     .17       0  5718.5     .11       0
  6375.9     .17       0  6594.2     .11       0  7007.2     .17       0
Bank Sta=4964.4,5037.2
XS Rating Curve= 0 ,0
Exp/Cntr=0.3,0.1

Type RM Length L Ch R = 1 ,38676   ,748,748,748
BEGIN DESCRIPTION:
MCGARY CREEK 56.0
END DESCRIPTION:
XS GIS Cut Line= 3
      3769695.73     10256701.83      3767888.42       10257681.
      3767065.52     10259430.96
#Sta/Elev= 30
  3273.9  308.91  3809.7  291.18  4148.2  282.86  4481.1  281.09  4502.9  279.11
  4524.8   281.1    4659  280.06  4688.1  278.15  4726.4  279.45    4792  277.05
  4819.6  279.52  4841.5  276.16  4879.5  280.36    4932  279.78  4939.4  280.59
  4961.3  270.32  4972.1  269.69  4994.2  269.69  5021.2  277.83  5026.9  274.01
  5034.4  280.54  5284.6  280.01  5313.3  277.12  5338.8  280.05  5754.1  280.38
  6017.4   284.3  6164.4  285.94  6390.3  294.19  6478.7  293.03  7263.2  298.73
#Mann= 8 ,-1 , 0
  3273.9     .11       0  4688.1     .15       0    4932     .12       0
  4939.4     .09       0  5034.4     .15       0  5313.3     .11       0
  5754.1     .17       0  6017.4     .11       0
Bank Sta=4939.4,5034.4
XS Rating Curve= 0 ,0
Exp/Cntr=0.3,0.1

Type RM Length L Ch R = 1 ,37928   ,1062,1062,1062
BEGIN DESCRIPTION:
MCGARY CREEK 55.0
END DESCRIPTION:
XS GIS Cut Line= 3
      3769372.78     10256196.64      3767820.71       10257056.
       3766867.6     10259420.54
#Sta/Elev= 30
  3020.9  307.26  3605.2  292.78  3898.3   281.6  4403.4  277.37  4512.5  277.43
  4544.2  279.42  4593.5  276.13  4631.3  278.43  4927.6   279.1    4972  279.67
  4977.4  278.25  4995.9  269.52    5018  269.52  5031.1  278.41  5037.7  278.25
  5136.2  278.38  5240.6  277.51  5326.9  281.84  5425.8  279.89  5642.4  281.95
  5684.6  287.91  5720.9  282.89    5814  280.96  5867.9  285.69    5990   286.8
  6264.9  289.82  6416.6  290.24  6676.5  295.47  7031.5  293.83  7344.4  296.95
#Mann= 14 ,-1 , 0
  3020.9     .11       0  3605.2     .17       0  3898.3     .11       0
  4927.6     .15       0    4972     .12       0  4977.4     .09       0
  5031.1     .12       0  5037.7     .15       0  5136.2     .17       0
  5326.9     .11       0  5642.4     .17       0  5720.9     .11       0
    5990     .17       0  6264.9     .11       0
#XS Ineff= 2 ,-1
  5323.8    5650  281.98  5694.3    6200  287.58
Permanent Ineff=
       F       F
Bank Sta=4977.4,5031.1
XS Rating Curve= 0 ,0
Exp/Cntr=0.3,0.1

Type RM Length L Ch R = 1 ,36866   ,505,505,505
BEGIN DESCRIPTION:
MCGARY CREEK 54.0
END DESCRIPTION:
XS GIS Cut Line= 3
       3769082.9     10255873.69      3767161.39     10256840.49
      3765708.73     10258815.95
#Sta/Elev= 30
  2903.8  299.55  3263.6  297.78  3547.5  292.72  3732.3  282.43  3888.5  278.42
  4387.1  275.37  4421.6   277.3  4440.9  279.73  4566.2  276.84  4969.2  277.39
  4991.6  269.54  4993.4  264.64  5015.6  264.64  5021.2  270.74  5036.4  277.12
    5054  276.82  5092.8  279.04    5181  277.45  5734.5   281.5  5880.2   282.1
  5901.1  279.64  5930.4  282.13  6188.6  286.82  6331.5  292.41  6448.1   293.2
  6703.7  293.08  6774.4  290.91  7110.8  291.13  7258.1  294.28  7506.9  297.24
#Mann= 11 ,-1 , 0
  2903.8     .11       0  4421.6     .15       0  4969.2     .09       0
  5036.4     .12       0    5054     .15       0    5181     .11       0
  5734.5     .15       0  6188.6     .11       0  6448.1     .17       0
  6703.7     .11       0  7258.1     .17       0
Bank Sta=4969.2,5036.4
XS Rating Curve= 0 ,0
Exp/Cntr=0.3,0.1

Type RM Length L Ch R = 1 ,36361   ,977,977,977
BEGIN DESCRIPTION:
MCGARY CREEK 53.0
END DESCRIPTION:
XS GIS Cut Line= 3
      3768929.21     10255467.47      3767403.17     10256196.63
      3765622.37     10258784.52
#Sta/Elev= 30
  2886.8  300.01  3475.7  284.91  4163.5   277.8  4220.3  277.65  4362.3  276.58
  4396.2  270.76  4431.8  274.13  4464.2  272.75  4495.3   276.4  4526.7  269.34
  4584.1  276.44  4966.3   277.2  4981.2  276.23  4987.3  268.59  4996.1  267.78
  4997.2   262.6  5031.9  264.76    5038  270.07  5052.9   271.2    5059  277.16
  5374.6  277.96  5921.7  280.48  5958.1  280.64    6078  280.58  6407.3  288.07
  6711.5   292.1  6903.2  291.59  7390.3  293.18  7468.1  295.01  7719.5  298.49
#Mann= 15 ,-1 , 0
  2886.8     .11       0  4163.5     .15       0  4220.3     .11       0
  4431.8     .15       0  4966.3     .09       0    5059     .15       0
  5374.6     .11       0  5921.7     .15       0  5958.1     .11       0
    6078     .15       0  6407.3     .11       0  6711.5     .17       0
  6903.2     .11       0  7390.3     .17       0  7468.1     .11       0
Bank Sta=4966.3,5059
XS Rating Curve= 0 ,0
Exp/Cntr=0.3,0.1

Type RM Length L Ch R = 1 ,35384   ,487,487,487
BEGIN DESCRIPTION:
MCGARY CREEK 52.0
END DESCRIPTION:
XS GIS Cut Line= 3
      3767319.83     10254457.07      3766741.72     10256358.09
      3765513.02     10258586.41
#Sta/Elev= 30
  3396.4  307.12  3522.1   303.4  3787.3  289.86  3828.4   289.9  3904.5  284.35
  4207.7  277.16  4498.1  275.37  4937.5  276.78    4958   276.1  4970.3  270.72
    4978  263.72  5000.6  263.72  5020.7  276.35  5030.8  276.91  5036.1  274.51
  5062.5  276.47  5093.8   273.3  5114.7  275.94  5205.6  276.25  5347.5  274.91
  5375.1  272.64  5432.5  275.66  5526.4  275.63  5950.8  277.54  6100.6  278.45
  6608.7  289.76  6806.3  291.15  7093.6  292.02  7640.3  291.19    7928  295.96
#Mann= 10 ,-1 , 0
  3396.4     .11       0  4207.7     .15       0  4937.5     .12       0
    4958     .09       0  5020.7     .15       0  5526.4     .17       0
  5950.8     .15       0  6100.6     .11       0  6806.3     .17       0
  7093.6     .11       0
Bank Sta=4958,5020.7
XS Rating Curve= 0 ,0
Exp/Cntr=0.3,0.1

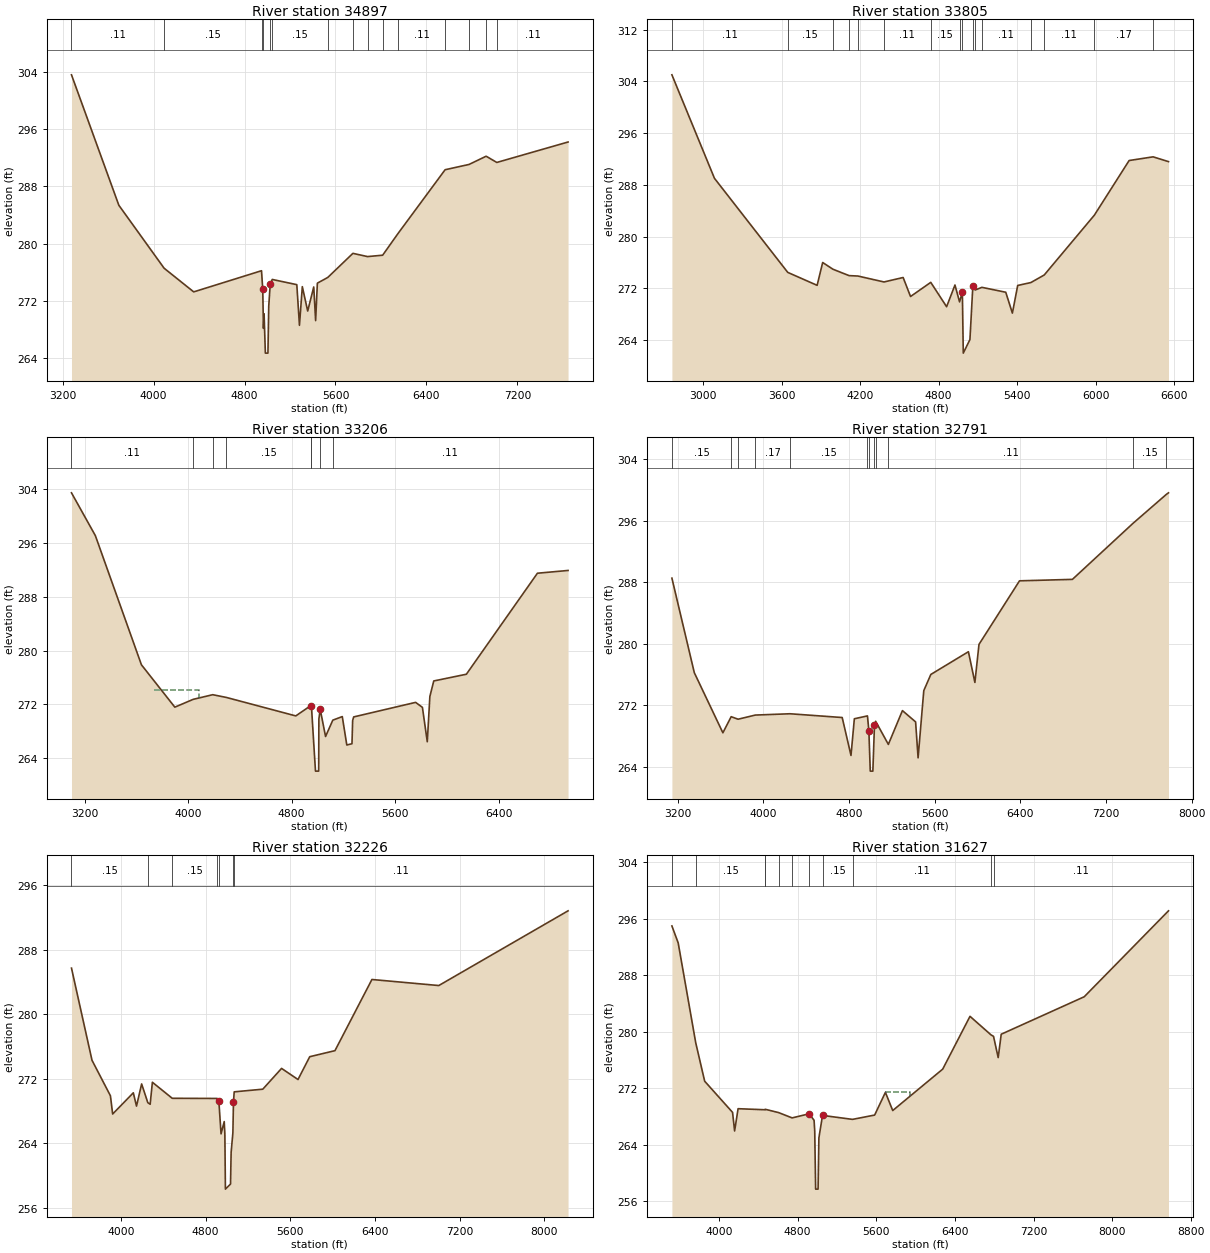
Type RM Length L Ch R = 1 ,34897   ,1092,1092,1092
BEGIN DESCRIPTION:
MCGARY CREEK 51.0
END DESCRIPTION:
XS GIS Cut Line= 3
      3767134.47     10254429.39      3766378.39     10255976.86
      3765474.54     10258463.81
#Sta/Elev= 30
  3277.7  303.61  3694.2  285.36  4092.5  276.55  4352.8  273.24  4949.4   276.2
  4960.2  273.58  4966.4  268.13    4972  270.17  4983.2  264.67  5005.8  264.67
    5013  271.26  5025.8  274.28  5043.6  274.98  5259.8  274.25  5283.1  268.56
  5308.3  273.97  5355.6  270.56  5408.8  273.93  5425.4  269.22  5440.7  274.46
  5532.4  275.26  5753.3  278.63  5881.9  278.18    6015  278.37  6148.5  281.37
  6564.4  290.33  6774.9  291.07  6925.5  292.22  7019.3  291.35  7646.1  294.21
#Mann= 15 ,-1 , 0
  3277.7     .11       0  4092.5     .15       0  4949.4     .12       0
  4960.2     .09       0  5025.8     .12       0  5043.6     .15       0
  5532.4     .11       0  5753.3     .15       0  5881.9     .11       0
    6015     .17       0  6148.5     .11       0  6564.4     .17       0
  6774.9     .11       0  6925.5     .17       0  7019.3     .11       0
Bank Sta=4960.2,5025.8
XS Rating Curve= 0 ,0
Exp/Cntr=0.3,0.1

Type RM Length L Ch R = 1 ,33805   ,599,599,599
BEGIN DESCRIPTION:
MCGARY CREEK 50.0
END DESCRIPTION:
XS GIS Cut Line= 3
      3767017.82     10254361.11      3765472.66     10255982.45
      3765210.93      10257517.7
#Sta/Elev= 30
  2760.3  305.03  3085.6  289.02  3646.2  274.46  3870.7  272.46  3913.2  275.99
  3991.8  274.95  4115.2  273.96  4182.2   273.9  4382.1  272.98  4528.4  273.67
    4585  270.73  4739.6  272.92  4860.8  269.15  4924.7  272.51  4959.9   269.9
  4981.3  271.41  4988.3  261.97  5039.2  264.07  5061.5  272.38  5079.8  271.74
  5130.5  272.15  5313.1  271.39  5363.8  268.16  5404.4  272.44  5505.4  272.89
  5607.3  274.06  5990.8  283.32  6256.5  291.77  6439.9  292.34  6557.4   291.6
#Mann= 16 ,-1 , 0
  2760.3     .11       0  3646.2     .15       0  3991.8     .17       0
  4115.2     .15       0  4182.2     .17       0  4382.1     .11       0
  4739.6     .15       0  4959.9     .12       0  4981.3     .09       0
  5061.5     .12       0  5079.8     .15       0  5130.5     .11       0
  5505.4     .15       0  5607.3     .11       0  5990.8     .17       0
  6439.9     .11       0
#XS Ineff= 1 ,-1
    3530  3913.2  275.99
Permanent Ineff=
       F
Bank Sta=4981.3,5061.5
XS Rating Curve= 0 ,0
Exp/Cntr=0.3,0.1

Type RM Length L Ch R = 1 ,33206   ,415,415,415
BEGIN DESCRIPTION:
MCGARY CREEK 49.0
END DESCRIPTION:
XS GIS Cut Line= 4
      3766295.55     10253990.88      3765152.43     10255510.66
       3765016.2     10256019.38      3765099.45     10257427.58
#Sta/Elev= 30
  3098.3  303.43  3282.9  297.07    3639  277.89  3897.2   271.6  4039.1  272.76
  4190.2  273.45  4296.4  273.04  4832.3   270.3  4946.8  271.81  4953.1  271.82
  4984.6   262.1  5008.9   262.1  5009.4   262.6  5010.8  269.84  5021.1  271.28
  5062.5  267.24  5118.4  269.67  5191.8   270.2  5226.7  265.98  5266.7  266.17
  5271.9  269.61  5279.9  270.15  5758.7  272.31  5811.3  271.57  5848.9  266.46
  5868.9  273.19    5899  275.49  6151.1  276.49  6700.4  291.49  6937.3   291.9
#Mann= 8 ,-1 , 0
  3098.3     .11       0  4039.1     .15       0  4190.2     .17       0
  4296.4     .15       0  4946.8     .12       0  4953.1     .09       0
  5021.1     .15       0  5118.4     .11       0
#XS Ineff= 1 ,-1
    3740  4082.6   274.1
Permanent Ineff=
       F
Bank Sta=4953.1,5021.1
XS Rating Curve= 0 ,0
Exp/Cntr=0.3,0.1

Type RM Length L Ch R = 1 ,32791   ,565,565,565
BEGIN DESCRIPTION:
MCGARY CREEK 48.0
END DESCRIPTION:
XS GIS Cut Line= 3
      3765627.33     10253991.58      3764974.54     10254998.55
      3763981.49     10258290.17
#Sta/Elev= 30
  3145.3  288.54  3354.5  276.23  3621.4   268.4  3698.9   270.5  3763.4  270.17
  3924.3  270.71  4247.6  270.88  4735.9  270.39    4818  265.45  4849.4  270.23
  4971.9   270.6  4985.1  268.64    4998  263.41  5022.3  263.41  5037.4  269.45
  5048.3   269.9    5167  266.89  5298.5  271.29  5421.5  269.82  5444.7  265.14
  5497.9  273.89  5563.9     276  5914.8  278.96  5975.3  274.96  6013.5  279.91
    6392  288.19  6886.2  288.38  7450.8  295.66  7761.3  299.42  7783.5  299.65
#Mann= 12 ,-1 , 0
  3145.3     .15       0  3698.9     .11       0  3763.4     .15       0
  3924.3     .17       0  4247.6     .15       0  4971.9     .12       0
  4985.1     .09       0  5037.4     .12       0  5048.3     .15       0
    5167     .11       0  7450.8     .15       0  7761.3     .17       0
Bank Sta=4985.1,5037.4
XS Rating Curve= 0 ,0
Exp/Cntr=0.3,0.1

Type RM Length L Ch R = 1 ,32226   ,599,599,599
BEGIN DESCRIPTION:
MCGARY CREEK 47.0
END DESCRIPTION:
XS GIS Cut Line= 3
      3765267.86     10254111.05      3764451.49     10255328.35
      3762974.53     10258193.01
#Sta/Elev= 30
  3534.3  285.74  3727.9  274.31    3902   269.9    3923  267.64  4118.1  270.27
  4148.1  268.62  4196.6  271.37  4254.9  269.05  4277.1  268.85  4298.1  271.58
  4485.5  269.59  4910.4  269.57  4925.4   269.3  4946.4  265.18  4976.4   266.7
  4982.4  265.16  4987.6  258.32  5035.9  258.95  5041.6  262.89  5058.1  265.29
  5063.7  269.11  5070.6  270.39  5340.6  270.72  5517.9   273.3    5673  271.92
  5783.8  274.75    6022   275.5  6370.9  284.33  7002.4  283.58    8223  292.85
#Mann= 7 ,-1 , 0
  3534.3     .15       0  4254.9     .17       0  4485.5     .15       0
  4910.4     .12       0  4925.4     .09       0  5063.7     .12       0
  5070.6     .11       0
Bank Sta=4925.4,5063.7
XS Rating Curve= 0 ,0
Exp/Cntr=0.3,0.1

Type RM Length L Ch R = 1 ,31627   ,504,504,504
BEGIN DESCRIPTION:
MCGARY CREEK 46.0
END DESCRIPTION:
XS GIS Cut Line= 3
      3765117.84     10253961.08      3764017.75     10254946.33
      3762273.16     10258061.03
#Sta/Elev= 30
  3523.2  294.99  3587.1  292.59  3765.6  278.44  3856.3  273.02  4139.6  268.61
  4160.5  265.98  4195.7  269.13  4470.3  268.98  4471.5  269.05  4607.5  268.58
  4744.8  267.83  4918.6  268.41    4968  267.49  4974.7     266    4984  257.75
  5008.7  257.75  5016.9  264.99    5054  268.18    5359  267.62  5583.6  268.23
  5693.1  271.44  5767.4  268.87  6275.4  274.73  6552.8   282.2    6766  279.58
  6791.9  279.37  6839.3  276.36  6870.1  279.67  7713.7  284.97    8570  297.13
#Mann= 11 ,-1 , 0
  3523.2     .17       0  3765.6     .15       0  4470.3     .17       0
  4471.5     .15       0  4607.5     .17       0  4744.8     .15       0
  4918.6     .09       0    5054     .15       0    5359     .11       0
    6766     .17       0  6791.9     .11       0
#XS Ineff= 1 ,-1
  5693.1    5940  271.44
Permanent Ineff=
       F
Bank Sta=4918.6,5054
XS Rating Curve= 0 ,0
Exp/Cntr=0.3,0.1

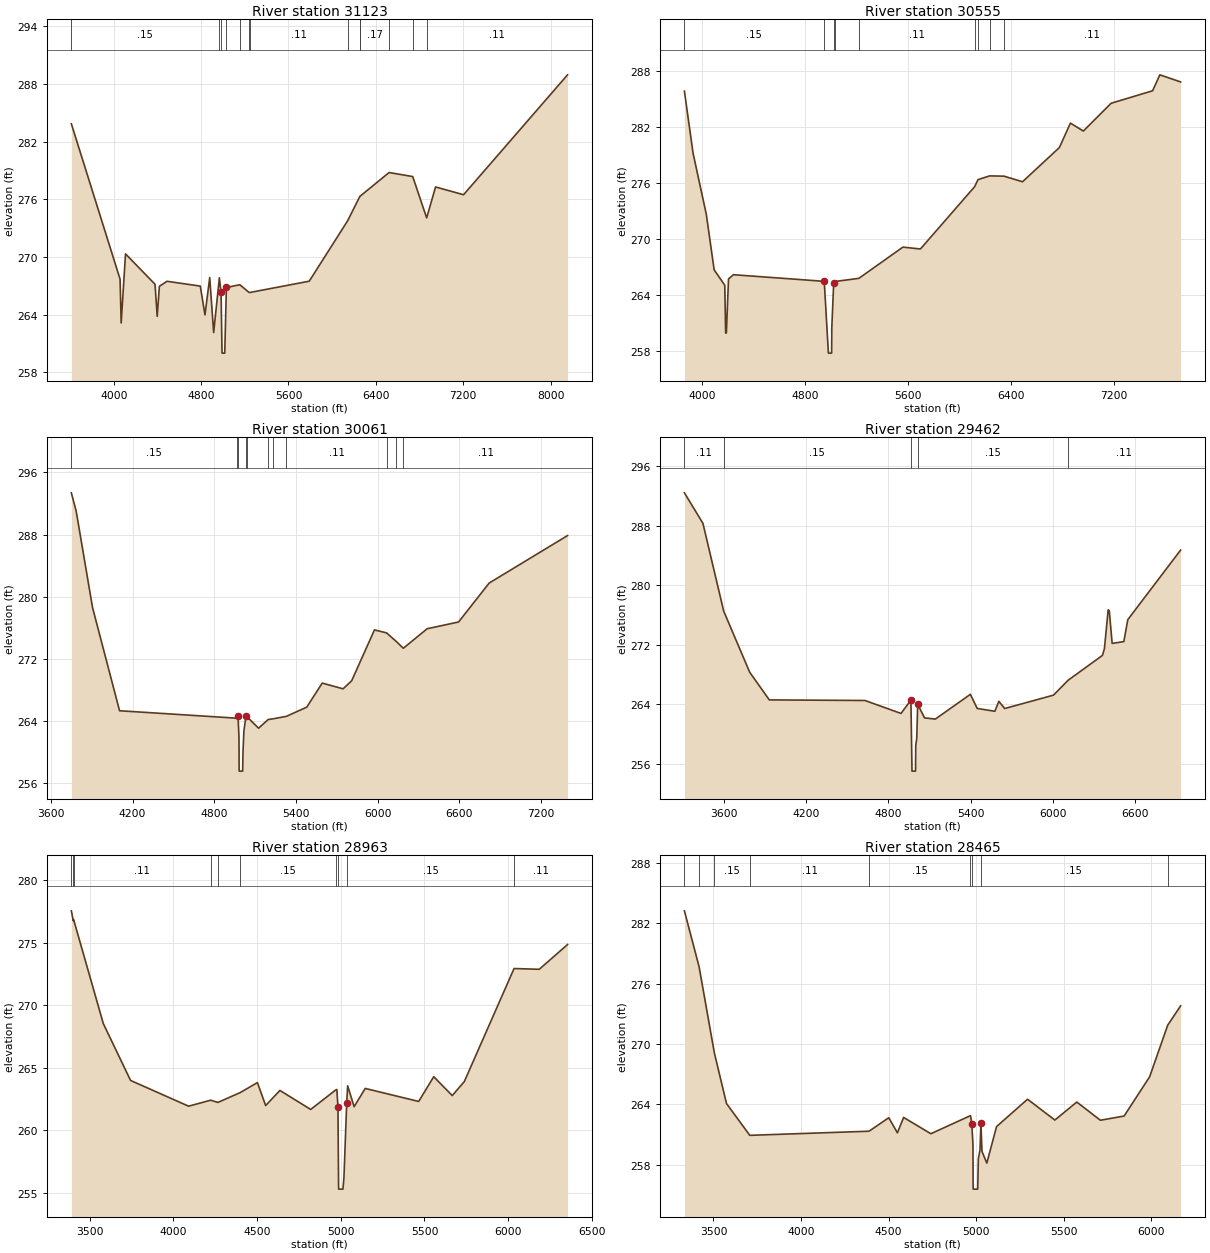
Type RM Length L Ch R = 1 ,31123   ,568,568,568
BEGIN DESCRIPTION:
MCGARY CREEK 45.0
END DESCRIPTION:
XS GIS Cut Line= 3
      3763905.09     10253324.91      3763881.64     10254239.18
      3762002.56     10257345.36
#Sta/Elev= 30
  3611.2  283.85  4057.5  267.69  4067.5  263.14  4107.5  270.32  4377.6  267.16
  4397.6  263.83  4417.6  266.95  4487.7  267.47  4792.4  266.97  4835.1  263.98
  4878.6  267.86  4914.7  262.14    4967  267.83  4982.5  266.31  4991.4     260
  5016.3     260  5031.1  266.83  5154.4  267.11  5236.1  266.34  5244.1   266.3
  5790.2  267.48  6141.8  273.76    6254   276.3  6254.3   276.3  6521.6  278.78
    6738  278.36  6865.7  274.06  6947.3  277.28  7203.7  276.47  8156.1  288.94
#Mann= 13 ,-1 , 0
  3611.2     .15       0    4967     .12       0  4982.5     .09       0
  5031.1     .15       0  5154.4     .11       0  5236.1     .15       0
  5244.1     .11       0  6141.8     .17       0    6254     .11       0
  6254.3     .17       0  6521.6     .11       0    6738     .17       0
  6865.7     .11       0
#XS Ineff= 1 ,-1
    3975  4107.5  270.32
Permanent Ineff=
       F
Bank Sta=4982.5,5031.1
XS Rating Curve= 0 ,0
Exp/Cntr=0.3,0.1

Type RM Length L Ch R = 1 ,30555   ,494,494,494
BEGIN DESCRIPTION:
MCGARY CREEK 44.0
END DESCRIPTION:
XS GIS Cut Line= 3
      3763667.85     10253561.07      3763154.96     10254576.49
      3761557.96      10256776.2
#Sta/Elev= 30
  3862.4  285.89  3929.6  279.24  4032.4  272.69  4093.7  266.72  4176.1  265.07
  4182.9  259.94  4188.5  259.96  4205.2  265.75  4243.3   266.2  4949.1  265.49
  4981.4  257.79  5006.4  257.79  5007.7  260.48  5022.4   265.3  5030.4  265.47
    5218  265.81  5560.4  269.16  5696.5  268.96  6118.3  275.65  6143.7   276.4
  6234.7   276.8  6346.5  276.77  6489.6  276.17  6776.4  279.84  6862.2  282.46
  6962.7  281.61  7178.4  284.59  7500.7  285.93  7557.1  287.64  7718.3  286.88
#Mann= 9 ,-1 , 0
  3862.4     .15       0  4949.1     .09       0  5022.4     .12       0
  5030.4     .15       0    5218     .11       0  6118.3     .17       0
  6143.7     .11       0  6234.7     .17       0  6346.5     .11       0
Bank Sta=4949.1,5022.4
XS Rating Curve= 0 ,0
Exp/Cntr=0.3,0.1

Type RM Length L Ch R = 1 ,30061   ,599,599,599
BEGIN DESCRIPTION:
MCGARY CREEK 43.0
END DESCRIPTION:
XS GIS Cut Line= 3
      3763667.88     10253461.04      3762752.87     10254312.08
      3761412.82       10256296.
#Sta/Elev= 30
  3750.4  293.38  3785.9  291.02  3906.1  278.61  4104.4  265.34  4967.3  264.38
  4974.6   264.6  4981.4  261.91  4982.3  258.07  4982.8  257.57  5008.3  257.57
  5010.9  260.02  5017.4   262.7  5032.4  264.62  5038.4   264.6  5125.3  263.09
  5195.7  264.21  5228.3  264.29  5329.6  264.62  5478.9   265.8  5592.9   268.9
  5745.7  268.16  5808.7  269.19  5976.3  275.74  6065.1  275.36  6137.8  274.23
  6188.3  273.38  6363.1  275.89  6593.9  276.76  6818.6  281.77  7394.1  287.88
#Mann= 11 ,-1 , 0
  3750.4     .15       0  4967.3     .12       0  4974.6     .09       0
  5032.4     .12       0  5038.4     .15       0  5195.7     .17       0
  5228.3     .15       0  5329.6     .11       0  6065.1     .17       0
  6137.8     .15       0  6188.3     .11       0
Bank Sta=4974.6,5032.4
XS Rating Curve= 0 ,0
Exp/Cntr=0.3,0.1

Type RM Length L Ch R = 1 ,29462   ,499,499,499
BEGIN DESCRIPTION:
MCGARY CREEK 42.0
END DESCRIPTION:
XS GIS Cut Line= 3
      3763571.73     10252984.69      3762241.51     10254026.12
      3761067.87     10255561.04
#Sta/Elev= 30
  3310.6  292.45  3445.7  288.35  3597.3  276.54  3787.5  268.31  3930.4   264.6
  4628.4  264.52  4891.5  262.78  4963.8  264.57  4971.7  255.02  4997.5  255.02
  4999.1  258.51  5006.3  259.39  5013.4  264.01  5063.3  262.18  5142.2  262.02
  5397.8  265.35  5447.7  263.45  5576.5  263.07  5605.6  264.41  5648.2  263.44
  6004.5  265.24  6110.4  267.23  6361.9  270.59  6376.4  271.52  6403.5  276.71
  6411.7  276.59  6432.6   272.2  6517.8  272.44  6546.8  275.39  6932.2  284.75
#Mann= 5 ,-1 , 0
  3310.6     .11       0  3597.3     .15       0  4963.8     .09       0
  5013.4     .15       0  6110.4     .11       0
Bank Sta=4963.8,5013.4
XS Rating Curve= 0 ,0
Exp/Cntr=0.3,0.1

Type RM Length L Ch R = 1 ,28963   ,498,498,498
BEGIN DESCRIPTION:
MCGARY CREEK 41.0
END DESCRIPTION:
XS GIS Cut Line= 3
      3762917.85     10252561.07      3761840.77      10253757.6
      3761217.87     10254961.04
#Sta/Elev= 30
  3390.1  277.57  3401.3  276.78  3403.6  276.87  3581.1  268.54    3744  263.99
  4090.8  261.93  4222.8  262.41    4266  262.23  4400.8  263.03  4501.9  263.82
  4551.2  261.98  4636.4  263.19  4820.3  261.67    4969  263.22  4976.5  263.27
  4983.2  261.86  4987.1  255.29    5013  255.29    5019  256.23  5035.5  262.19
  5041.2  263.56  5079.8  261.89  5146.2  263.35  5465.6  262.31  5555.6  264.29
  5666.2  262.78  5738.3   263.9  6035.5  272.95  6186.2  272.89  6355.1  274.87
#Mann= 10 ,-1 , 0
  3390.1     .11       0  3401.3     .17       0  3403.6     .11       0
  4222.8     .15       0    4266     .11       0  4400.8     .15       0
    4969     .12       0  4983.2     .09       0  5035.5     .15       0
  6035.5     .11       0
Bank Sta=4983.2,5035.5
XS Rating Curve= 0 ,0
Exp/Cntr=0.3,0.1

Type RM Length L Ch R = 1 ,28465   ,498,498,498
BEGIN DESCRIPTION:
MCGARY CREEK 40.0
END DESCRIPTION:
XS GIS Cut Line= 3
      3762667.87     10252261.06      3761490.08     10253439.21
      3761167.86     10254561.05
#Sta/Elev= 30
  3334.1  283.26  3417.9   277.7  3505.2  269.12  3574.5  264.09  3707.5  260.93
  4388.4  261.34  4500.8  262.68  4550.3  261.18  4585.7  262.71  4741.3  261.09
  4967.5  262.89  4974.6   262.1  4981.7  260.01  4982.4  256.08  4982.9  255.58
  5008.8  255.58  5012.3  258.58  5021.9  259.48  5027.1  262.16  5033.1  259.33
  5060.8  258.17  5116.4   261.8  5293.3  264.52  5449.3  262.45  5574.5  264.24
  5709.3  262.43  5844.7  262.85  5990.3  266.75  6093.7  271.89  6167.2  273.81
#Mann= 9 ,-1 , 0
  3334.1     .11       0  3417.9     .17       0  3505.2     .15       0
  3707.5     .11       0  4388.4     .15       0  4967.5     .12       0
  4974.6     .09       0  5027.1     .15       0  6093.7     .11       0
Bank Sta=4974.6,5027.1
XS Rating Curve= 0 ,0
Exp/Cntr=0.3,0.1