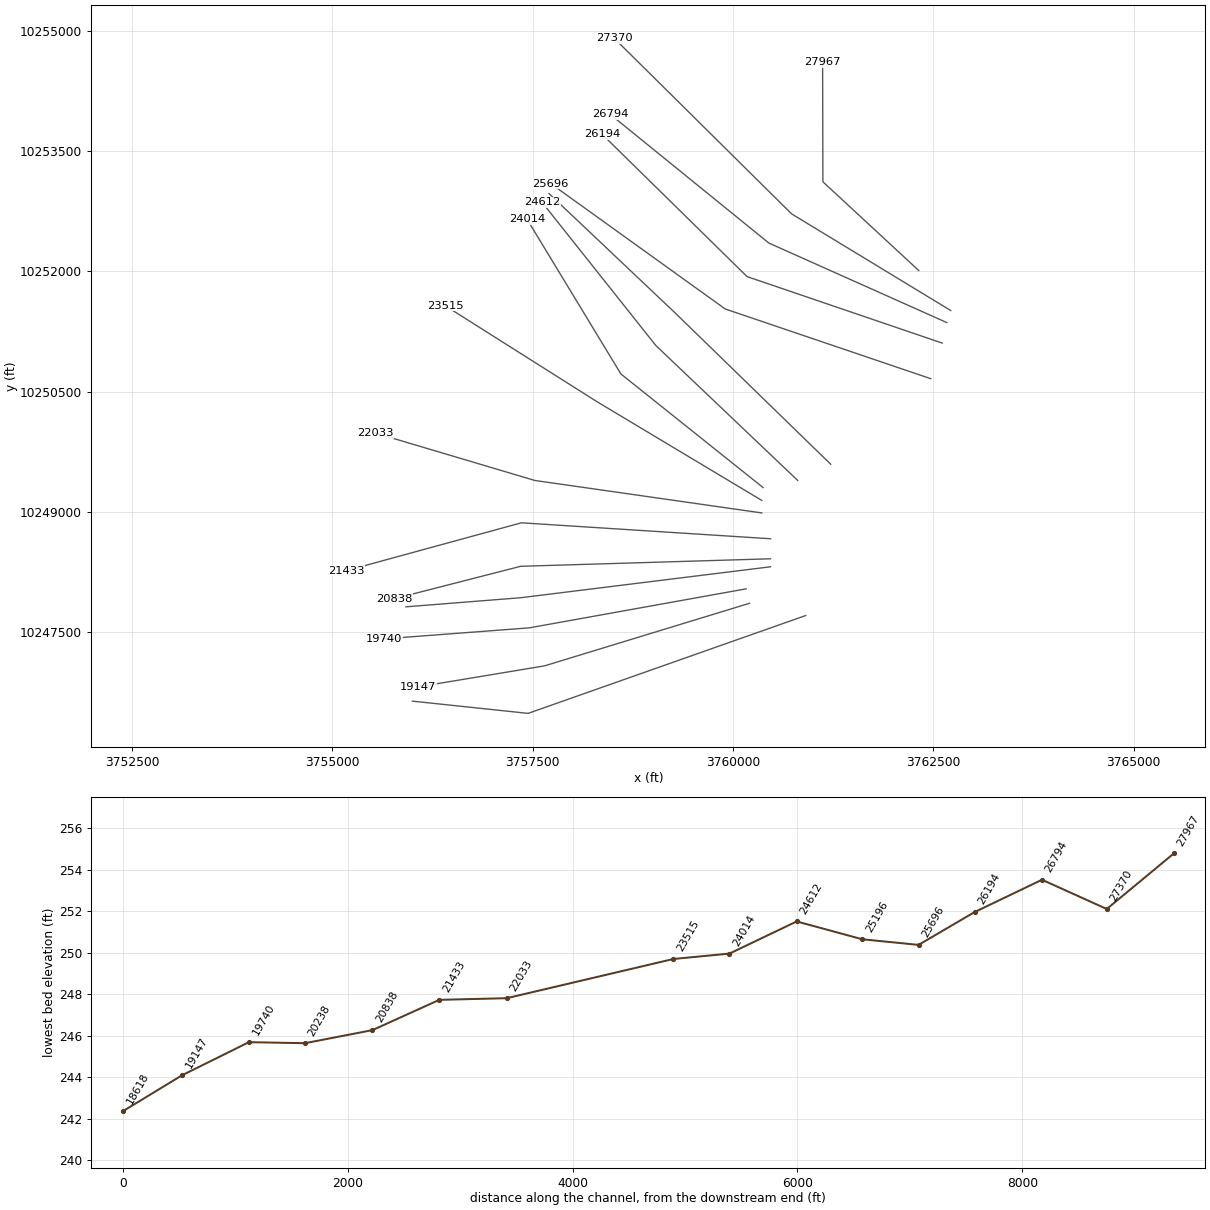
HEC-RAS study MCGARY CREEK.prj: MCGARY CREEK Base Level Engineering

--- MCGARY CREEK.g01 (geometry) --- (continued)

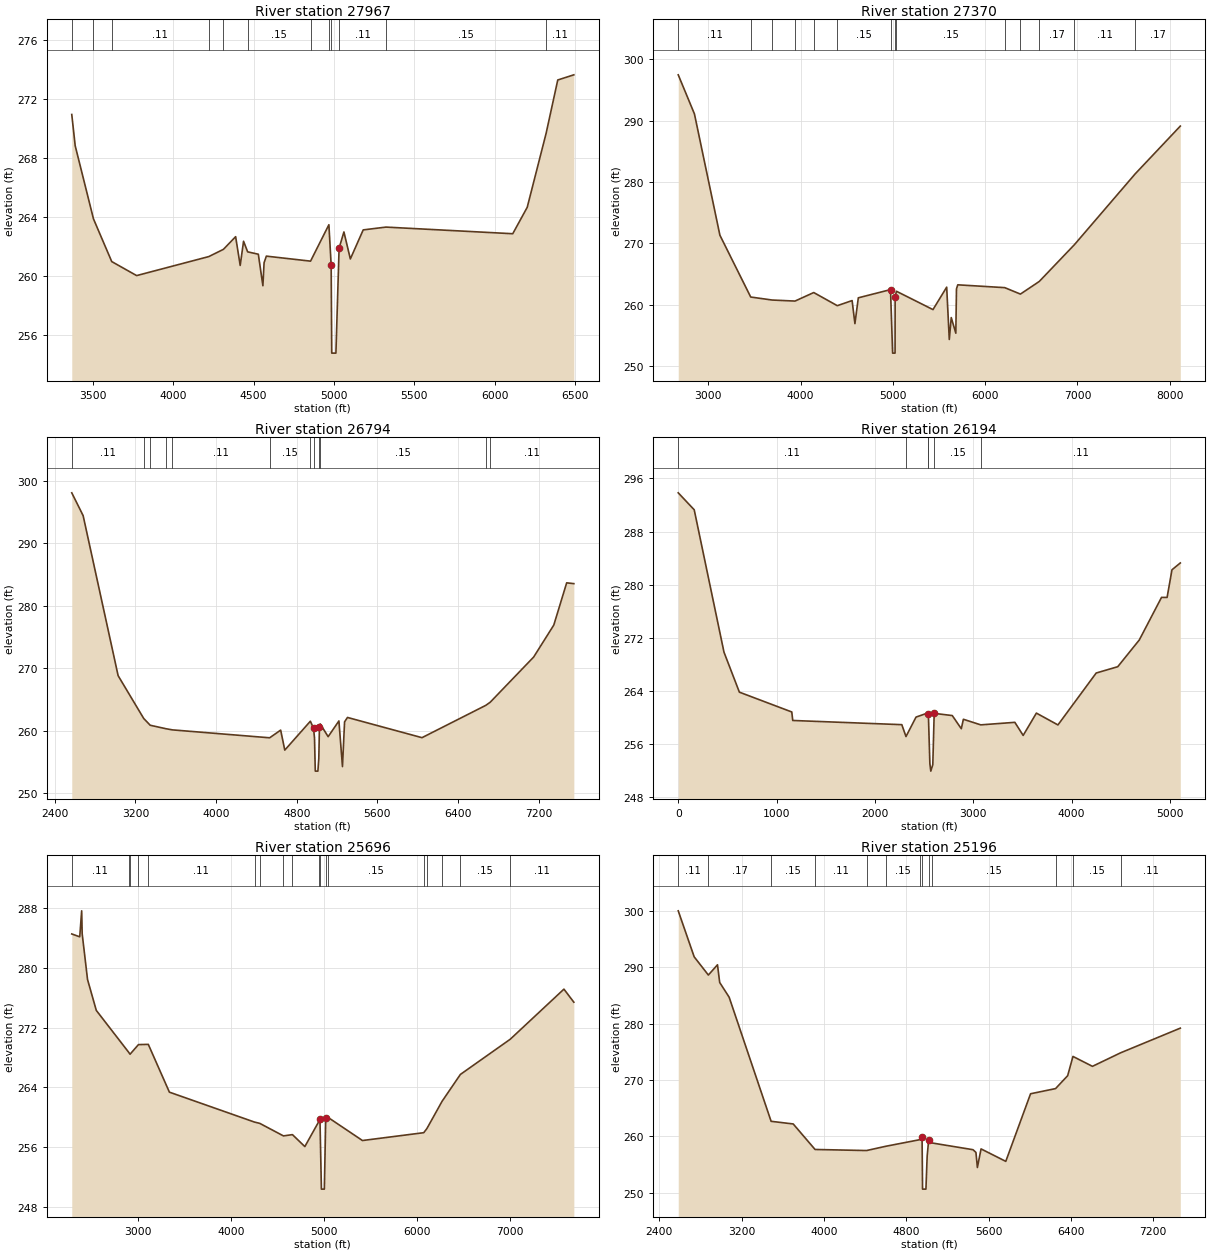
Type RM Length L Ch R = 1 ,27967   ,597,597,597
BEGIN DESCRIPTION:
MCGARY CREEK 39.0
END DESCRIPTION:
XS GIS Cut Line= 3
      3762317.86     10252011.06      3761121.44     10253119.26
      3761117.85     10254611.06
#Sta/Elev= 30
  3369.2  270.98  3390.5  268.86  3504.1   263.9  3617.8     261  3772.6  260.05
  4221.5  261.34  4312.3  261.83  4388.3  262.69  4416.7  260.74  4437.7  262.38
  4463.1  261.66  4529.5   261.5  4557.9  259.36  4565.2  260.92  4579.4  261.37
  4854.3  261.03  4968.3   263.5  4982.5  260.75  4986.1  254.79    5012  254.79
  5031.8  261.91  5061.8  263.01  5101.8  261.18  5181.8  263.15  5323.2  263.34
  6111.8  262.89  6201.8  264.68  6319.1  269.69  6391.8  273.32  6491.8  273.67
#Mann= 12 ,-1 , 0
  3369.2     .11       0  3504.1     .15       0  3617.8     .11       0
  4221.5     .17       0  4312.3     .11       0  4463.1     .15       0
  4854.3     .11       0  4968.3     .09       0  4982.5     .06       0
  5031.8     .11       0  5323.2     .15       0  6319.1     .11       0
Bank Sta=4982.5,5031.8
XS Rating Curve= 0 ,0
Exp/Cntr=0.3,0.1

Type RM Length L Ch R = 1 ,27370   ,576,576,576
BEGIN DESCRIPTION:
MCGARY CREEK 38.0
END DESCRIPTION:
XS GIS Cut Line= 3
      3762717.85     10251511.07      3760730.34     10252719.04
      3758517.85     10254911.07
#Sta/Elev= 30
  2674.2   297.5  2849.7  291.13  3125.7  271.34  3459.5  261.26  3690.9  260.77
  3939.3   260.6  4142.5  261.99  4397.6  259.85  4558.2  260.68  4588.7  256.92
  4625.5  261.13  4974.3  262.47  4997.3  252.11  5023.2  252.11  5023.7  252.61
  5024.4  261.31  5038.6   262.2  5434.5  259.21    5583  262.87  5611.3  254.34
  5632.5  257.91    5682  255.36  5689.1  262.59  5703.3  263.25  6211.9  262.79
  6382.1  261.74  6586.3   263.8  6967.2   269.8  7625.8  281.35  8114.5  289.14
#Mann= 14 ,-1 , 0
  2674.2     .11       0  3459.5     .15       0  3690.9     .11       0
  3939.3     .17       0  4142.5     .11       0  4397.6     .15       0
  4974.3     .09       0  5024.4     .12       0  5038.6     .15       0
  6211.9     .17       0  6382.1     .15       0  6586.3     .17       0
  6967.2     .11       0  7625.8     .17       0
Bank Sta=4974.3,5024.4
XS Rating Curve= 0 ,0
Exp/Cntr=0.3,0.1

Type RM Length L Ch R = 1 ,26794   ,600,600,600
BEGIN DESCRIPTION:
MCGARY CREEK 37.0
END DESCRIPTION:
XS GIS Cut Line= 3
      3762667.89     10251361.06      3760447.58     10252353.95
      3758467.88     10253961.05
#Sta/Elev= 30
  2567.8  298.11  2680.5  294.46  3027.9  268.81    3282  261.95  3346.2  260.87
  3503.5  260.31  3566.3  260.13  4531.5  258.86  4640.7  260.09  4681.6  256.89
  4935.6  261.52  4966.8  260.38  4976.5  258.84  4984.2  253.52  5010.1  253.52
  5019.1  255.55  5025.5  260.54  5033.5  261.08  5111.8  259.04  5218.6  261.56
    5254  254.25  5274.8  261.41  5303.6  262.12    6043  258.88  6676.4  264.06
    6720  264.56  7151.2   271.8  7350.9  276.92  7478.8  283.69  7549.9  283.56
#Mann= 12 ,-1 , 0
  2567.8     .11       0    3282     .15       0  3346.2     .11       0
  3503.5     .15       0  3566.3     .11       0  4531.5     .15       0
  4935.6     .12       0  4966.8     .09       0  5025.5     .12       0
  5033.5     .15       0  6676.4     .17       0    6720     .11       0
Bank Sta=4966.8,5025.5
XS Rating Curve= 0 ,0
Exp/Cntr=0.3,0.1

Type RM Length L Ch R = 1 ,26194   ,498,498,498
XS GIS Cut Line= 3
       3762610.3     10251104.89      3760175.13     10251935.26
      3758367.85     10253711.07
#Sta/Elev= 30
       0  293.83   162.5  291.28   465.3  269.86     622  263.84  1154.8  260.86
  1164.8  259.58  2274.1  258.95  2316.4  257.16  2418.6  260.09  2538.3  260.71
    2544  260.58  2559.4  253.11  2568.8  251.96  2589.2  252.94  2603.3  260.65
  2787.2  260.32  2879.1  258.34  2900.3  259.76  3077.1  258.92  3423.7   259.3
  3508.4  257.33  3642.8  260.69    3862  258.91    4251  266.72  4470.2  267.67
  4689.3  271.69  4915.6   278.1  4972.2  278.09  5021.8  282.25  5106.6  283.28
#Mann= 6 ,-1 , 0
       0     .11       0  2316.4     .15       0  2538.3     .12       0
    2544     .09       0  2603.3     .15       0  3077.1     .11       0
Bank Sta=2544,2603.3
XS Rating Curve= 0 ,0
Exp/Cntr=0.3,0.1

Type RM Length L Ch R = 1 ,25696   ,500,500,500
BEGIN DESCRIPTION:
MCGARY CREEK 35.0
END DESCRIPTION:
XS GIS Cut Line= 3
      3762468.48     10250660.09      3759902.42      10251530.9
      3757724.69     10253096.86
#Sta/Elev= 30
  2290.2  284.56  2375.8  284.18  2396.5  287.66    2402  284.59  2459.5  278.46
  2553.7  274.32  2900.9  268.72  2916.2  268.45  3006.5  269.74  3112.2  269.77
  3338.7  263.37    4253  259.36  4309.2  259.19  4563.6  257.51  4660.2  257.68
  4793.3  256.08  4941.5  259.39  4955.6  259.83  4971.2  250.38  5002.7  250.38
  5017.9  259.94  5039.8  260.01  5412.1  256.89  6070.3  257.94    6104  258.49
  6266.9  262.14  6463.6  265.74  6999.4  270.46  7575.9  277.17  7682.3  275.42
#Mann= 18 ,-1 , 0
  2290.2     .11       0  2900.9     .17       0  2916.2     .11       0
  3006.5     .17       0  3112.2     .11       0    4253     .15       0
  4309.2     .11       0  4563.6     .17       0  4660.2     .15       0
  4941.5     .12       0  4955.6     .09       0  5017.9     .12       0
  5039.8     .15       0  6070.3     .17       0    6104     .15       0
  6266.9     .17       0  6463.6     .15       0  6999.4     .11       0
Bank Sta=4955.6,5017.9
XS Rating Curve= 0 ,0
Exp/Cntr=0.3,0.1

Type RM Length L Ch R = 1 ,25196   ,584,584,584
BEGIN DESCRIPTION:
MCGARY CREEK 34.0
END DESCRIPTION:
XS GIS Cut Line= 3
      3761218.48     10249592.37      3759268.74     10251489.87
      3757702.82     10252972.61
#Sta/Elev= 30
  2585.3  300.06  2740.3  291.89    2878  288.66  2966.7  290.48    2988  287.34
  3079.8  284.73  3487.5  262.69  3702.3  262.22  3914.5  257.69  4414.3   257.5
  4602.2  258.26  4932.6  259.43  4953.9  259.92  4958.6  250.65  4991.4  250.65
  5003.3  256.46  5017.5   259.3  5045.7  258.86  5448.8  257.65  5477.2  257.17
  5491.3  254.49  5526.9  257.79  5767.2  255.58  6007.9  267.58  6250.8   268.5
  6368.3  270.79  6419.7  274.21    6609  272.45  6882.5  274.85  7462.5  279.23
#Mann= 13 ,-1 , 0
  2585.3     .11       0    2878     .17       0  3487.5     .15       0
  3914.5     .11       0  4414.3     .17       0  4602.2     .15       0
  4932.6     .12       0  4953.9     .09       0  5017.5     .12       0
  5045.7     .15       0  6250.8     .17       0  6419.7     .15       0
  6882.5     .11       0
Bank Sta=4953.9,5017.5
XS Rating Curve= 0 ,0
Exp/Cntr=0.3,0.1

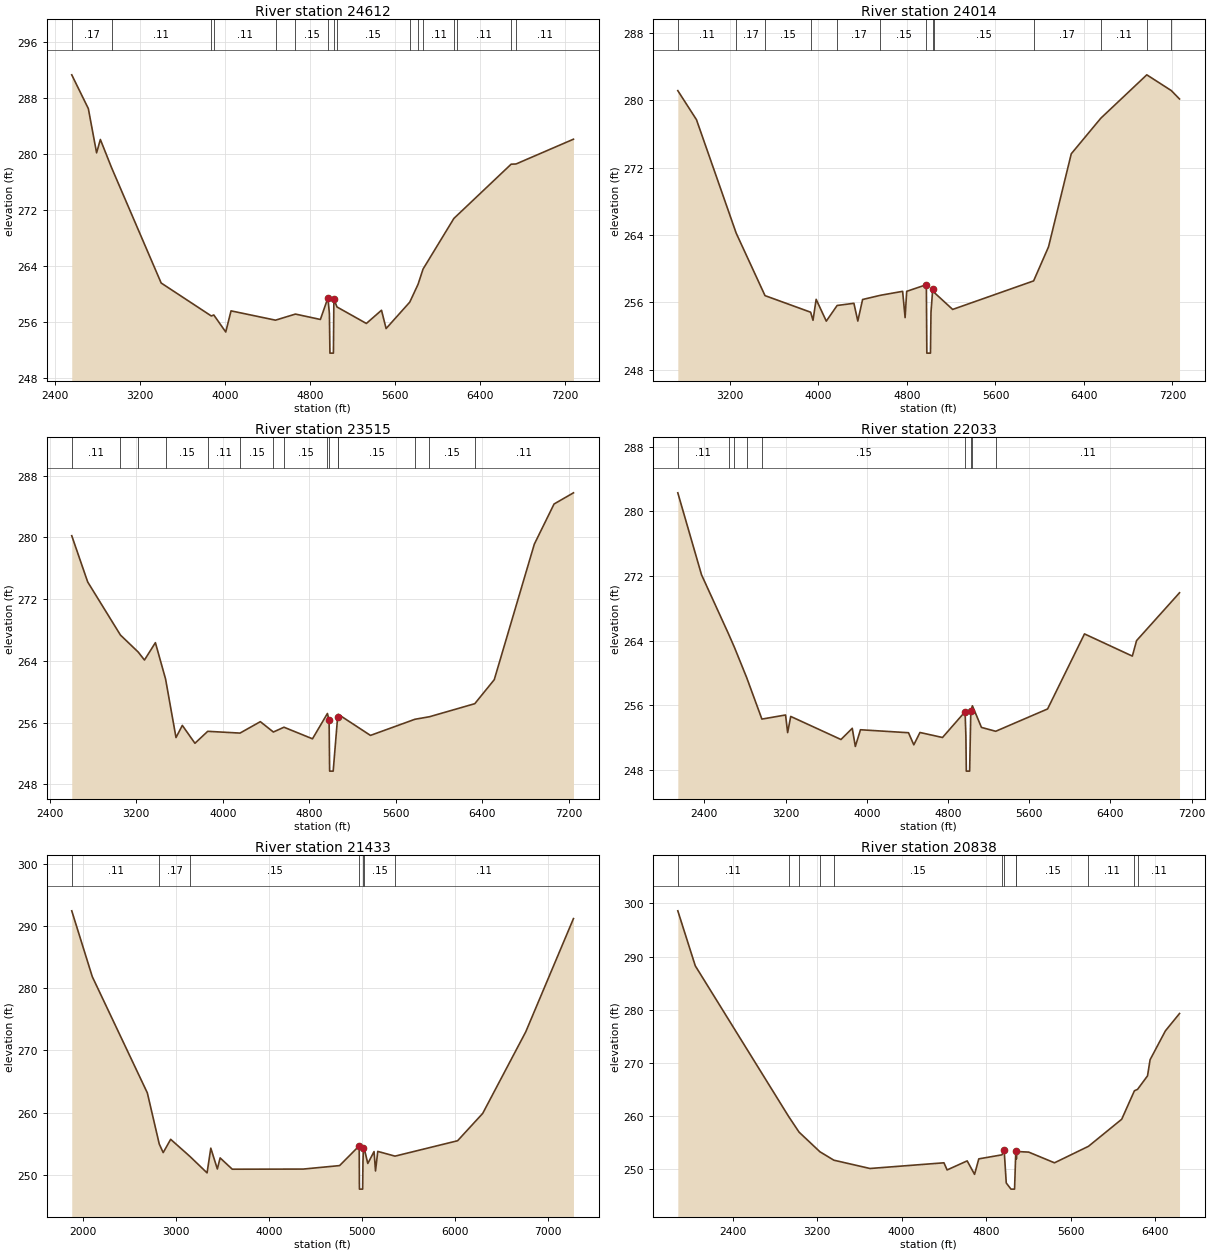
Type RM Length L Ch R = 1 ,24612   ,598,598,598
BEGIN DESCRIPTION:
MCGARY CREEK 33.0
END DESCRIPTION:
XS GIS Cut Line= 3
      3760807.02     10249389.24      3759036.27     10251074.63
      3757617.83     10252861.09
#Sta/Elev= 30
  2555.4  291.28  2711.7  286.45  2789.4  280.13  2824.9  282.04  2930.3  278.02
  3397.7  261.53    3870  256.82  3893.5  256.96    4006  254.53  4055.7  257.55
  4474.6  256.22  4662.6  257.09  4897.4  256.32  4968.2   259.4  4982.3  257.16
  4987.3  251.51  5020.1  251.51  5024.5  259.25  5053.3  258.11  5330.5  255.75
  5473.1  257.64  5516.4  255.02  5739.3   258.8  5817.5  261.35  5864.3  263.52
  6154.9  270.76  6181.4  271.14  6694.2  278.51  6740.4  278.54  7281.1  282.08
#Mann= 16 ,-1 , 0
  2555.4     .17       0  2930.3     .11       0    3870     .15       0
  3893.5     .11       0  4474.6     .17       0  4662.6     .15       0
  4968.2     .09       0  5024.5     .12       0  5053.3     .15       0
  5739.3     .11       0  5817.5     .15       0  5864.3     .11       0
  6154.9     .17       0  6181.4     .11       0  6694.2     .15       0
  6740.4     .11       0
Bank Sta=4968.2,5024.5
XS Rating Curve= 0 ,0
Exp/Cntr=0.3,0.1

Type RM Length L Ch R = 1 ,24014   ,499,499,499
BEGIN DESCRIPTION:
MCGARY CREEK 32.0
END DESCRIPTION:
XS GIS Cut Line= 3
      3760374.71     10249300.72       3758600.3     10250719.04
      3757426.77     10252654.92
#Sta/Elev= 30
  2728.4  281.14  2897.2  277.69  3255.9  264.22  3516.7  256.79  3929.2  254.82
  3950.6  253.86    3979  256.35  4070.7  253.76  4168.7  255.62  4320.4  255.88
  4355.6  253.77  4398.8  256.33  4559.9  256.83  4760.7   257.3  4783.1  254.18
  4797.5   257.3  4975.2  258.09  4979.6  249.96  5012.4  249.96  5017.1  254.82
  5032.6  257.54  5048.1  257.14    5213  255.15  5944.8  258.54  6079.7  262.59
  6285.2  273.64  6551.9  277.86    6968  283.02  7189.4  281.15  7263.8  280.15
#Mann= 13 ,-1 , 0
  2728.4     .11       0  3255.9     .17       0  3516.7     .15       0
  3929.2     .11       0  4168.7     .17       0  4559.9     .15       0
  4975.2     .09       0  5032.6     .12       0  5048.1     .15       0
  5944.8     .17       0  6551.9     .11       0    6968     .15       0
  7189.4     .11       0
Bank Sta=4975.2,5032.6
XS Rating Curve= 0 ,0
Exp/Cntr=0.3,0.1

Type RM Length L Ch R = 1 ,23515   ,1482,1482,1482
BEGIN DESCRIPTION:
MCGARY CREEK 31.0
END DESCRIPTION:
XS GIS Cut Line= 3
      3760358.57     10249139.95        3758303.     10250372.14
      3756408.87     10251570.54
#Sta/Elev= 30
  2603.4  280.21  2750.7  274.22  3053.4  267.34    3218  265.13  3275.6   264.1
  3376.7  266.35  3470.9  261.63  3567.2  254.05  3625.6  255.63  3742.2  253.31
  3860.6  254.86  4158.8  254.63  4346.8  256.11  4467.3  254.77  4565.3  255.39
  4828.9  253.89    4967  257.17  4982.5  256.29  4987.4   249.7  5020.2   249.7
  5061.4  256.73  5067.3  257.06  5364.9  254.33  5775.9  256.42  5910.3  256.75
  6329.1  258.44  6509.2  261.55  6879.7  279.12    7062  284.32  7241.4  285.77
#Mann= 15 ,-1 , 0
  2603.4     .11       0  3053.4     .17       0    3218     .11       0
  3470.9     .15       0  3860.6     .11       0  4158.8     .15       0
  4467.3     .17       0  4565.3     .15       0    4967     .12       0
  4982.5     .09       0  5061.4     .12       0  5067.3     .15       0
  5775.9     .11       0  5910.3     .15       0  6329.1     .11       0
Bank Sta=4982.5,5061.4
XS Rating Curve= 0 ,0
Exp/Cntr=0.3,0.1

Type RM Length L Ch R = 1 ,22033   ,600,600,600
BEGIN DESCRIPTION:
MCGARY CREEK 30.0
END DESCRIPTION:
XS GIS Cut Line= 3
      3760358.59      10248983.7      3757526.35     10249389.03
      3755532.52     10249981.87
#Sta/Elev= 30
  2138.9  282.31  2372.2  272.16  2639.6  264.79    2697  263.14  2816.7  259.42
  2967.1  254.26  3200.3  254.77  3220.5  252.58  3250.9  254.59  3745.8  251.73
    3857  253.12  3887.3  250.87  3937.8  252.94    4411  252.57  4463.1  251.07
  4523.7   252.6  4745.9  251.98  4968.2  255.18  4976.2  252.16  4980.3  247.81
  5013.1  247.81  5024.6  255.26  5040.2  255.91  5129.4  253.23  5269.7  252.75
  5780.9  255.52  6144.2  264.82  6615.5  262.07  6657.2  263.99  7080.1  269.92
#Mann= 9 ,-1 , 0
  2138.9     .11       0  2639.6     .17       0    2697     .11       0
  2816.7     .17       0  2967.1     .15       0  4968.2     .09       0
  5024.6     .12       0  5040.2     .15       0  5269.7     .11       0
Bank Sta=4968.2,5024.6
XS Rating Curve= 0 ,0
Exp/Cntr=0.3,0.1

Type RM Length L Ch R = 1 ,21433   ,595,595,595
BEGIN DESCRIPTION:
MCGARY CREEK 29.0
END DESCRIPTION:
XS GIS Cut Line= 3
      3760467.82     10248661.07       3757358.2     10248860.32
      3755167.89     10248261.08
#Sta/Elev= 30
    1884  292.43  2104.4  281.86  2695.6  263.19  2823.7  254.97    2866   253.6
  2946.1  255.73  3150.9  253.01  3336.9  250.34    3377  254.31  3447.2  250.97
  3477.2  252.74  3607.5  250.93  4369.1  250.95  4759.9  251.51  4970.3  254.68
  4972.5  248.23  4973.3  247.73  5007.4  247.73  5010.7  252.15    5016  254.35
  5021.2  254.46  5062.6  251.85  5129.9  253.76  5145.5  250.65  5169.6  253.79
  5354.9  253.03  6026.7   255.5  6296.3  259.89  6758.5  272.99  7270.8  291.18
#Mann= 7 ,-1 , 0
    1884     .11       0  2823.7     .17       0  3150.9     .15       0
  4970.3     .09       0    5016     .12       0  5021.2     .15       0
  5354.9     .11       0
Bank Sta=4970.3,5016
XS Rating Curve= 0 ,0
Exp/Cntr=0.3,0.1

Type RM Length L Ch R = 1 ,20838   ,600,600,600
BEGIN DESCRIPTION:
MCGARY CREEK 28.0
END DESCRIPTION:
XS GIS Cut Line= 3
      3760467.81     10248411.07      3757348.93     10248317.06
      3755767.83     10247911.06
#Sta/Elev= 30
  1879.7   298.6  2045.2  288.26  2929.6  259.93  3028.3  256.99  3225.6   253.3
    3358  251.71  3700.4  250.15  4400.8  251.22  4430.8  249.88  4620.9  251.58
  4690.9  249.05    4731  251.96  4951.1  252.72  4971.1  253.66  4991.1  247.43
  5035.7  246.27  5069.8  246.27  5081.5  253.42  5086.6  251.93    5094  253.34
  5203.7  253.23  5448.2  251.22  5769.9  254.32  6084.8  259.41  6205.3  264.77
  6234.9  265.03  6329.3  267.57  6353.6   270.6  6498.2  276.02  6632.4  279.29
#Mann= 12 ,-1 , 0
  1879.7     .11       0  2929.6     .17       0  3028.3     .15       0
  3225.6     .17       0    3358     .15       0  4951.1     .12       0
  4971.1     .09       0  5081.5     .12       0  5086.6     .15       0
  5769.9     .11       0  6205.3     .17       0  6234.9     .11       0
Bank Sta=4971.1,5081.5
XS Rating Curve= 0 ,0
Exp/Cntr=0.3,0.1

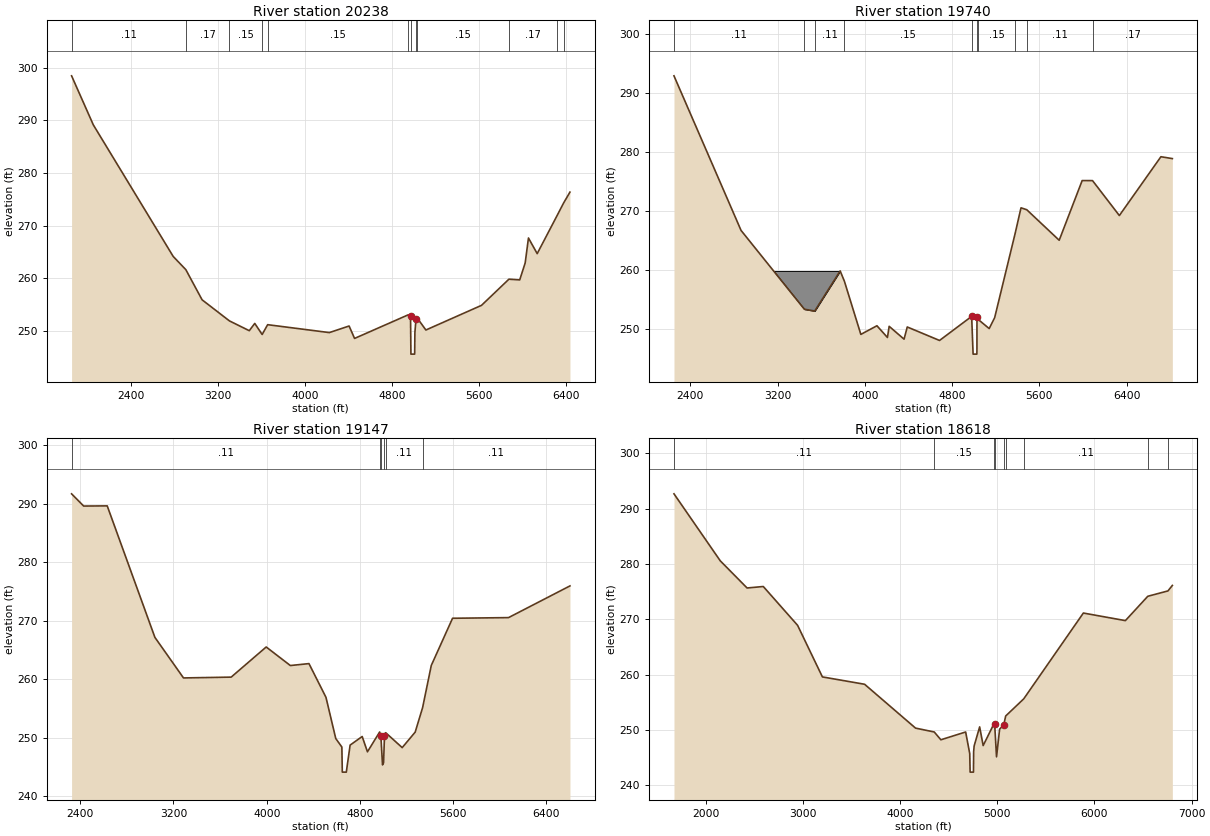
Type RM Length L Ch R = 1 ,20238   ,498,498,498
BEGIN DESCRIPTION:
MCGARY CREEK 27.0
END DESCRIPTION:
XS GIS Cut Line= 3
      3760467.86     10248311.07      3757350.11     10247924.67
      3755917.81     10247811.07
#Sta/Elev= 30
  1858.4  298.48  2058.3  289.16  2791.9  264.19  2908.2  261.67  3057.5  255.95
  3308.5  251.95  3490.8  250.09  3541.2  251.47  3609.2  249.37  3659.6  251.23
  4226.4  249.73  4407.8  250.98  4458.1  248.62  4951.9  253.11  4972.1  252.96
  4975.8  245.64  5010.1  245.64  5012.3  249.74  5022.3  252.26  5032.4  252.53
  5113.2  250.22  5624.2   254.9  5876.2  259.87  5975.3  259.73  6025.5  262.96
  6055.6  267.69  6135.8  264.72    6318  271.92  6378.6  274.34  6436.8   276.4
#Mann= 12 ,-1 , 0
  1858.4     .11       0  2908.2     .17       0  3308.5     .15       0
  3609.2     .11       0  3659.6     .15       0  4951.9     .12       0
  4972.1     .09       0  5022.3     .12       0  5032.4     .15       0
  5876.2     .17       0    6318     .11       0  6378.6     .17       0
Bank Sta=4972.1,5022.3
XS Rating Curve= 0 ,0
Exp/Cntr=0.3,0.1

Type RM Length L Ch R = 1 ,19740   ,593,593,593
BEGIN DESCRIPTION:
MCGARY CREEK 26.0
END DESCRIPTION:
XS GIS Cut Line= 3
       3760164.1     10248035.78      3757456.82     10247548.38
      3755643.33     10247410.79
#Sta/Elev= 30
  2249.2  292.96  2864.3   266.7  3444.4  253.32  3539.8  253.01    3773  259.82
  3811.6  258.08  3962.6  249.04    4110  250.51  4206.4  248.52  4222.3  250.41
  4358.8  248.23  4388.2   250.3    4684  248.01  4978.6   252.1  4991.8  245.69
  5026.1  245.69  5026.9  246.19  5027.3  251.96  5039.1  251.57  5139.4  250.03
  5189.5  251.88    5376  266.09  5431.1  270.54  5483.4  270.22  5781.2  265.03
  5991.8  275.17  6086.9  275.16  6332.8  269.23  6713.9  279.22  6818.7   278.9
#Mann= 10 ,-1 , 0
  2249.2     .11       0  3444.4     .17       0  3539.8     .11       0
  3811.6     .15       0  4978.6     .09       0  5027.3     .12       0
  5039.1     .15       0    5376     .17       0  5483.4     .11       0
  6086.9     .17       0
#Block Obstruct= 1 ,-1
    2950    3773  259.82
Bank Sta=4978.6,5027.3
XS Rating Curve= 0 ,0
Exp/Cntr=0.3,0.1

Type RM Length L Ch R = 1 ,19147   ,529,529,529
BEGIN DESCRIPTION:
MCGARY CREEK 25.0
END DESCRIPTION:
XS GIS Cut Line= 3
      3760205.83     10247855.25      3757648.34     10247073.87
      3756067.84     10246811.07
#Sta/Elev= 30
  2325.8  291.67  2429.6  289.58  2631.6  289.61  3040.8  267.13  3286.1   260.2
  3695.3  260.34  3995.7  265.49    4203  262.32  4362.7  262.65  4508.6  256.89
  4592.7  249.84    4645  248.39  4648.8   244.1  4683.1   244.1  4715.8  248.72
  4819.4  250.19  4864.6  247.57  4969.1  250.96  4979.6  250.32  4993.9  245.34
  5002.8   245.7  5010.6  250.22  5020.8  250.84  5162.7  248.29  5274.2  250.94
    5338  255.14  5412.2  262.33  5594.9   270.4    6075  270.51  6602.2  275.93
#Mann= 6 ,-1 , 0
  2325.8     .11       0  4969.1     .12       0  4979.6     .09       0
  5010.6     .12       0  5020.8     .11       0    5338     .11       0
Bank Sta=4979.6,5010.6
XS Rating Curve= 0 ,0
Exp/Cntr=0.3,0.1

Type RM Length L Ch R = 1 ,18618   ,446,446,446
BEGIN DESCRIPTION:
MCGARY CREEK 24.0
END DESCRIPTION:
XS GIS Cut Line= 3
      3760907.15     10247702.45       3757441.9     10246480.23
      3755997.43     10246633.01
#Sta/Elev= 30
  1674.4  292.69  2150.8  280.57  2426.5  275.66  2593.2  275.93  2946.1  268.91
  3201.3  259.58  3635.4  258.25  4159.5  250.32  4351.7  249.62    4420  248.21
  4674.9  249.62  4716.9  245.72    4721  242.36  4755.3  242.36  4757.1  246.02
  4762.4   247.1    4819  250.54  4855.2  247.16  4968.3  251.18  4973.6     251
  4992.6  245.12  5024.4  250.13  5066.9  250.91  5086.8  252.51  5272.4  255.61
  5885.9  271.13  6318.3  269.76  6548.7  274.16  6756.1  275.13  6801.4  276.12
#Mann= 9 ,-1 , 0
  1674.4     .11       0  4351.7     .15       0  4968.3     .12       0
  4973.6     .09       0  5066.9     .12       0  5086.8     .15       0
  5272.4     .11       0  6548.7     .17       0  6756.1     .11       0
Bank Sta=4973.6,5066.9
XS Rating Curve= 0 ,0
Exp/Cntr=0.3,0.1