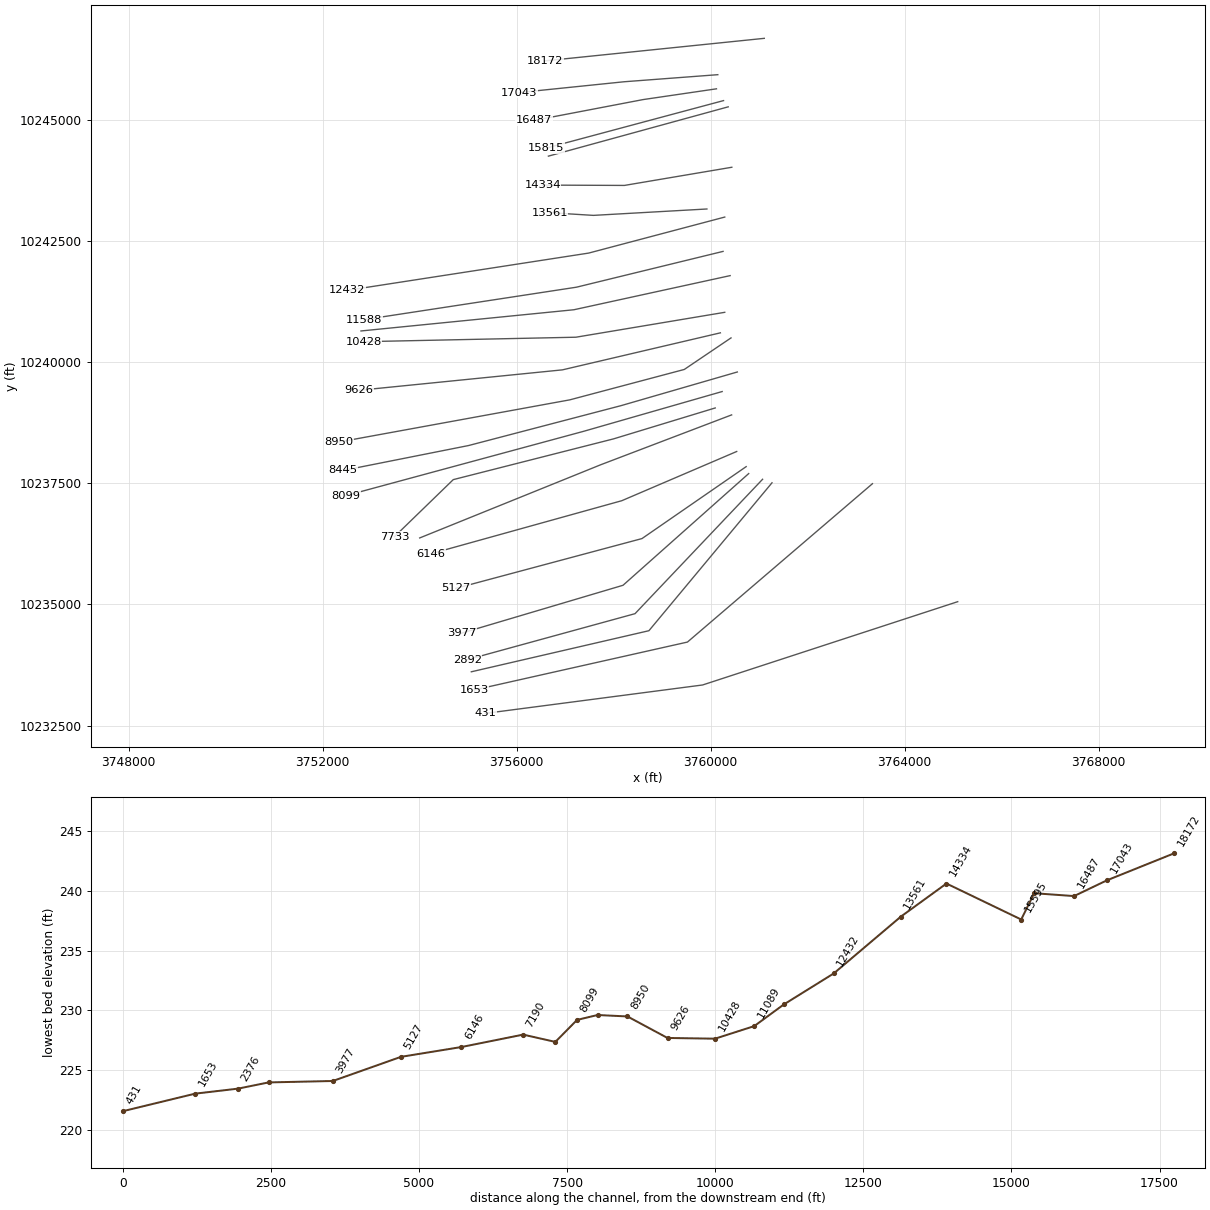
HEC-RAS study MCGARY CREEK.prj: MCGARY CREEK Base Level Engineering

--- MCGARY CREEK.g01 (geometry) --- (continued)

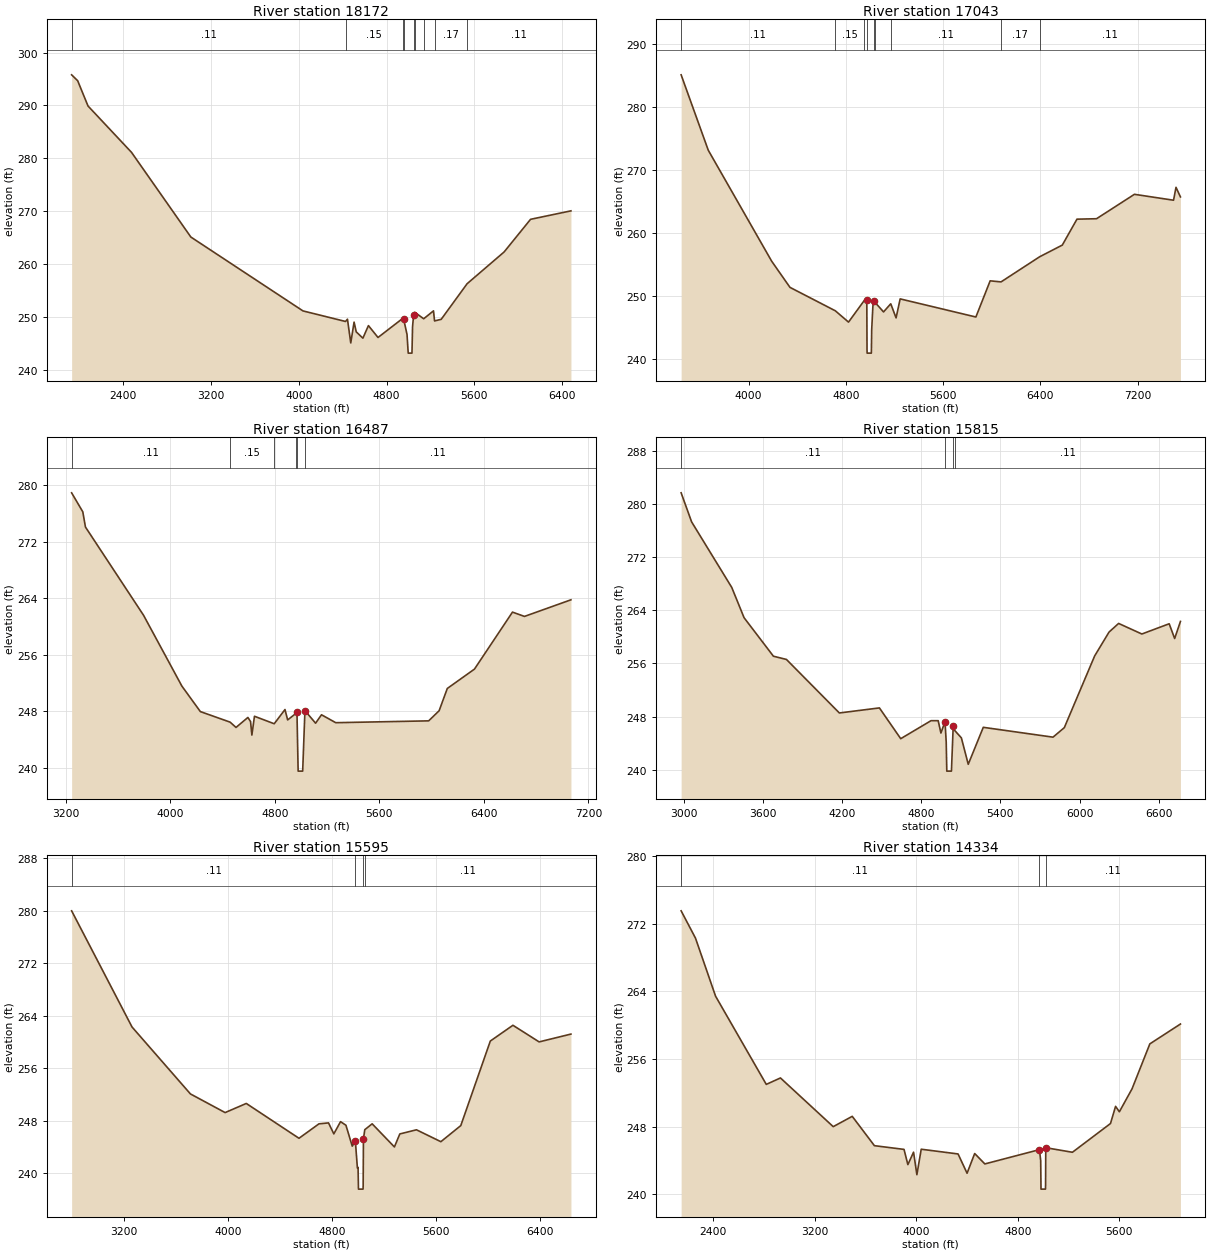
Type RM Length L Ch R = 1 ,18172   ,1129,1129,1129
BEGIN DESCRIPTION:
MCGARY CREEK 23.0
END DESCRIPTION:
XS GIS Cut Line= 3
      3761108.56     10246681.62      3759553.01      10246521.9
       3756581.8     10246216.45
#Sta/Elev= 30
    1929  295.79  1984.2  294.67  2078.4  289.89  2475.2  281.11  3015.4   265.1
  4037.2  251.12  4425.1  249.12  4442.9  249.55    4473  245.06  4503.2     249
  4522.9  247.15  4583.6  245.96  4633.9  248.34  4721.2  246.09  4945.5  249.68
  4955.6   249.5  4985.7  246.66  4996.5  243.13  5030.8  243.13    5036   248.1
    5046  250.39  5056.1  250.86  5137.7  249.63    5227  251.13  5236.6  249.22
  5297.3  249.53  5533.2  256.26  5870.4  262.27  6111.6  268.45  6479.6  270.05
#Mann= 9 ,-1 , 0
    1929     .11       0  4425.1     .15       0  4945.5     .12       0
  4955.6     .09       0    5046     .12       0  5056.1     .15       0
  5137.7     .11       0  5236.6     .17       0  5533.2     .11       0
Bank Sta=4955.6,5046
XS Rating Curve= 0 ,0
Exp/Cntr=0.3,0.1

Type RM Length L Ch R = 1 ,17043   ,556,556,556
BEGIN DESCRIPTION:
MCGARY CREEK 22.0
END DESCRIPTION:
XS GIS Cut Line= 3
      3760150.23     10245931.62      3758219.67     10245785.79
      3756061.42     10245563.72
#Sta/Elev= 30
  3445.9  285.11  3668.9  273.13  4190.4  255.49  4340.8  251.33  4713.6  247.61
  4822.2  245.81  4952.6  249.27  4972.6  249.25  4974.4  241.38  4975.3  240.88
    5010  240.88  5012.7  244.57  5022.8   248.4  5032.8  249.14  5042.8  248.89
  5110.3  247.43  5169.5  248.72  5213.3  246.48  5246.9   249.5  5869.5  246.62
    5987  252.37  6076.5   252.2  6393.4  256.19  6580.1  258.05  6700.7  262.17
  6861.5  262.24  7173.2  266.12  7494.9  265.18    7515  267.23  7551.6  265.71
#Mann= 9 ,-1 , 0
  3445.9     .11       0  4713.6     .15       0  4952.6     .11       0
  4972.6     .07       0  5032.8     .11       0  5042.8     .15       0
  5169.5     .11       0  6076.5     .17       0  6393.4     .11       0
Bank Sta=4972.6,5032.8
XS Rating Curve= 0 ,0
Exp/Cntr=0.3,0.1

Type RM Length L Ch R = 1 ,16487   ,672,672,672
BEGIN DESCRIPTION:
MCGARY CREEK 21.0
END DESCRIPTION:
XS GIS Cut Line= 3
      3760122.49     10245639.96      3758608.56     10245417.73
      3756358.54     10244987.17
#Sta/Elev= 30
  3245.3  278.92  3330.8  276.23  3351.1  274.08  3795.8   261.6  4088.9  251.59
  4230.4  247.98  4457.8  246.49  4503.3  245.74  4594.2  247.15  4614.5  246.57
  4624.6  244.66  4644.5  247.32  4795.5  246.26    4878  248.27  4898.4   246.8
  4959.4  247.69  4969.6  247.93  4978.7  239.56  5013.4  239.56  5030.7  248.12
  5112.2  246.34  5157.4  247.53  5266.6  246.41  5977.6  246.67  6057.6   248.1
  6120.1  251.25  6328.1  253.99    6619  262.05  6710.7  261.44  7066.3  263.79
#Mann= 6 ,-1 , 0
  3245.3     .11       0  4457.8     .15       0  4795.5     .11       0
  4959.4     .09       0  4969.6     .06       0  5030.7     .11       0
Bank Sta=4969.6,5030.7
XS Rating Curve= 0 ,0
Exp/Cntr=0.3,0.1

Type RM Length L Ch R = 1 ,15815   ,220,220,220
BEGIN DESCRIPTION:
MCGARY CREEK 20.0
END DESCRIPTION:
XS GIS Cut Line= 2
      3760268.32     10245396.91      3756615.49     10244417.73
#Sta/Elev= 30
  2981.9  281.67  3061.2   277.3  3365.5  267.43  3458.6  262.88  3680.8  257.09
  3779.6   256.6  4180.3  248.55  4483.6  249.31    4645  244.68  4874.7  247.39
  4928.8  247.39  4949.5  245.53  4980.5  247.26  4989.6  244.15    4994   239.8
  5029.1   239.8  5042.6  246.58    5053  245.94  5104.5   244.8  5156.5  240.83
  5270.4  246.39  5798.4  244.91  5884.1  246.34  6113.9  257.13  6222.9  260.72
  6295.4  262.02  6471.4  260.43  6678.4  261.97  6719.8  259.75  6763.7  262.32
#Mann= 4 ,-1 , 0
  2981.9     .11       0  4980.5     .07       0  5042.6     .11       0
    5053     .11       0
Bank Sta=4980.5,5042.6
XS Rating Curve= 0 ,0
Exp/Cntr=0.3,0.1

Type RM Length L Ch R = 1 ,15595   ,1261,1261,1261
BEGIN DESCRIPTION:
MCGARY CREEK 19.0
END DESCRIPTION:
XS GIS Cut Line= 2
      3760364.59      10245268.2      3756657.19     10244251.07
#Sta/Elev= 30
  2795.1  279.96  3260.1  262.28  3709.8  252.09  3976.9  249.25  4139.8  250.64
  4545.6  245.34  4699.7  247.54    4773  247.68  4813.8  246.01  4865.6  247.87
  4907.1  247.32  4955.7  244.14  4979.7  244.92  4995.3  240.81  5000.5   240.9
  5003.6   237.6  5038.8   237.6  5039.7   238.1  5041.9  245.25  5052.3  246.65
    5109  247.54  5280.4  244.02  5321.9     246  5450.2  246.63    5638  244.82
  5791.4  247.27  6018.8  260.14  6192.9  262.54  6394.5  260.01  6639.5   261.2
#Mann= 4 ,-1 , 0
  2795.1     .11       0  4979.7     .07       0  5041.9     .11       0
  5052.3     .11       0
Bank Sta=4979.7,5041.9
XS Rating Curve= 0 ,0
Exp/Cntr=0.3,0.1

Type RM Length L Ch R = 1 ,14334   ,773,773,773
BEGIN DESCRIPTION:
MCGARY CREEK 18.0
END DESCRIPTION:
XS GIS Cut Line= 3
      3760439.38     10244021.56      3758224.07     10243646.55
      3756536.61      10243653.5
#Sta/Elev= 30
  2147.1  273.53  2260.2   270.3  2418.5  263.43    2818     253  2929.6  253.76
  3345.4     248  3495.3  249.22    3670  245.75  3903.3  245.31  3933.7  243.51
  3978.4  244.98  4004.7  242.32  4038.8  245.33  4329.2  244.77  4400.1  242.49
  4460.1  244.82  4540.1  243.59  4970.2  245.28  4980.2  243.99  4982.6  240.61
  5017.8  240.61  5018.7  241.11  5020.2  245.51  5230.2  244.97  5530.2  248.37
  5570.2   250.4  5600.2  249.76  5700.2  252.48  5840.2  257.79  6081.4  260.14
#Mann= 3 ,-1 , 0
  2147.1     .11       0  4970.2     .06       0  5020.2     .11       0
Bank Sta=4970.2,5020.2
XS Rating Curve= 0 ,0
Exp/Cntr=0.3,0.1

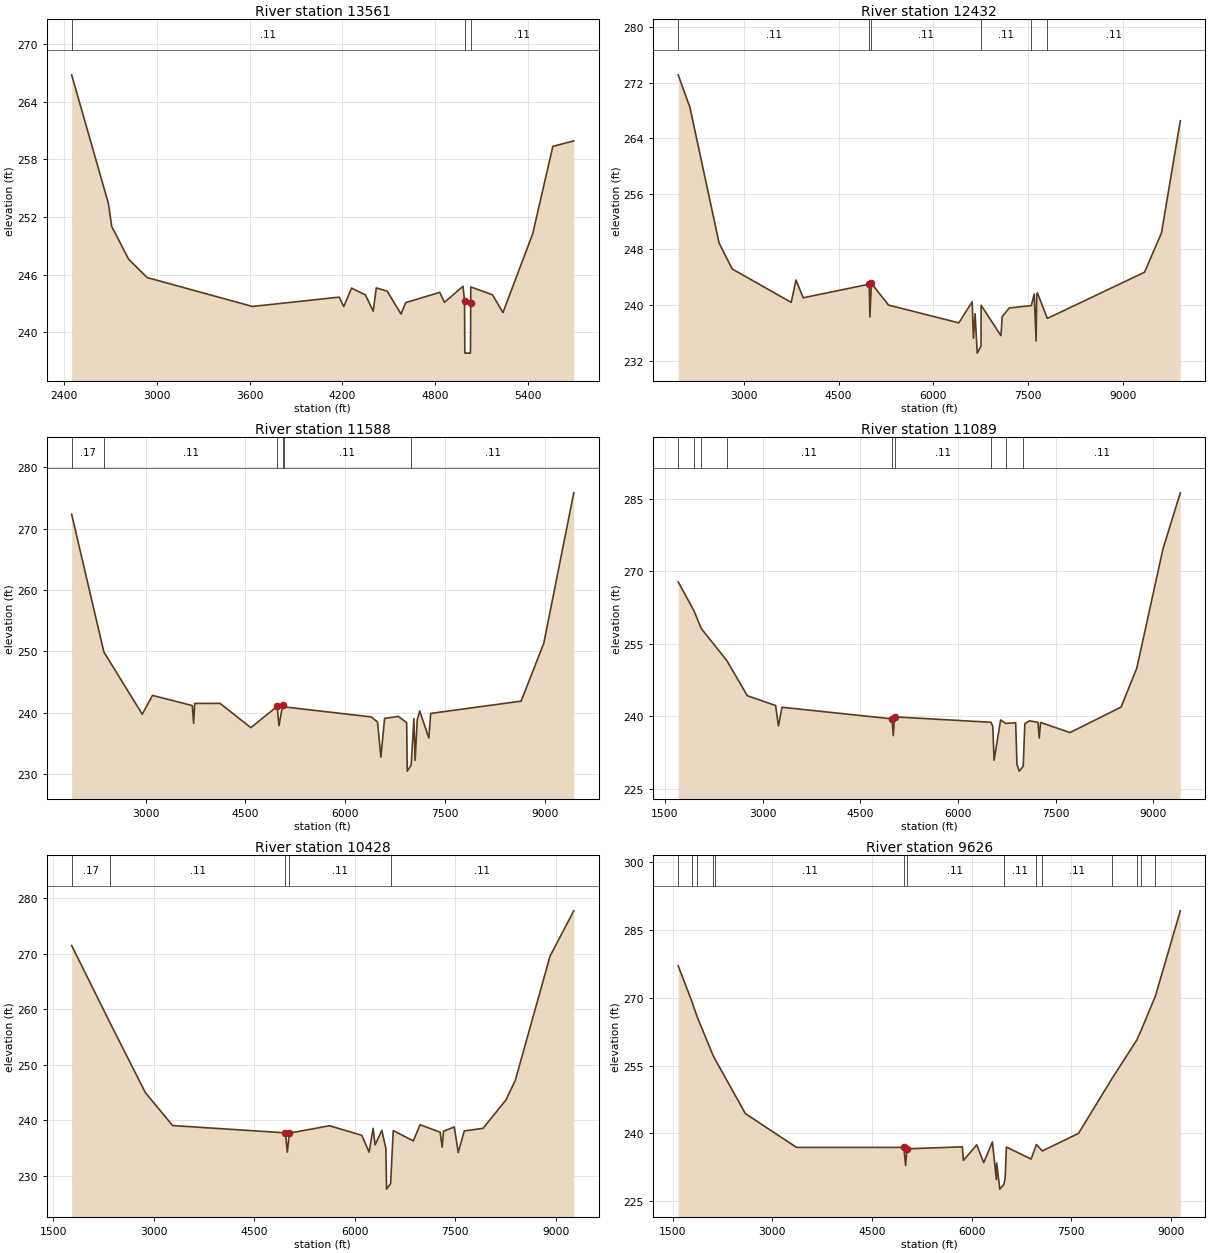
Type RM Length L Ch R = 1 ,13561   ,1129,1129,1129
BEGIN DESCRIPTION:
MCGARY CREEK 17.0
END DESCRIPTION:
XS GIS Cut Line= 3
      3759925.44     10243160.44      3757585.18      10243028.5
      3756682.67     10243084.04
#Sta/Elev= 30
  2448.3  266.81  2686.3   253.4  2707.4  251.03  2816.5  247.62  2936.7   245.7
  3617.7  242.69  4178.6  243.66  4208.7  242.68  4258.8   244.6  4348.9  243.89
    4399   242.2    4419  244.62  4489.1  244.29  4579.3   241.9  4609.3  243.09
  4829.7  244.16  4859.7  243.12    4980  244.79    4990  243.24  4991.5  238.33
  4992.4  237.83  5027.7  237.83  5028.6  238.33  5029.7 243.017  5030.1  244.72
  5170.3  243.91  5238.3  242.05  5430.8  250.26  5561.1  259.36  5696.5  259.93
#Mann= 3 ,-1 , 0
  2448.3     .11       0    4990     .06       0  5029.7     .11       0
Bank Sta=4990,5029.7
XS Rating Curve= 0 ,0
Exp/Cntr=0.3,0.1

Type RM Length L Ch R = 1 ,12432   ,844,844,844
BEGIN DESCRIPTION:
Mapping XS 74fd091b
END DESCRIPTION:
XS GIS Cut Line= 3
      3760293.55     10242993.78      3757487.96     10242250.72
      3752502.31     10241479.96
#Sta/Elev= 30
  1960.7  273.11  2147.3   268.4    2608  248.94  2815.5  245.19  3749.8  240.39
    3825   243.6  3940.5  241.05  4984.6  243.01  4994.7  238.29    5019  243.13
  5289.7     240  6402.6  237.44  6613.7  240.47  6633.9  235.22  6659.9  238.77
  6693.6  233.09    6754  234.09  6755.3  239.97    7069  235.61  7089.3  238.34
  7200.6  239.58  7550.3  239.93  7595.2   241.6  7625.6  234.84  7635.7   241.5
  7646.7  241.74  7803.8  238.08  9342.5  244.73    9610  250.37  9907.9   266.5
#Mann= 6 ,-1 , 0
  1960.7     .11       0  4984.6     .06       0    5019     .11       0
    6754     .11       0  7550.3     .15       0  7803.8     .11       0
Bank Sta=4984.6,5019
XS Rating Curve= 0 ,0
Exp/Cntr=0.3,0.1

Type RM Length L Ch R = 1 ,11588   ,499,499,499
BEGIN DESCRIPTION:
MCGARY CREEK 16.0
END DESCRIPTION:
XS GIS Cut Line= 3
      3760258.78     10242285.44      3757236.11     10241546.84
      3752852.11     10240876.18
#Sta/Elev= 30
  1888.4  272.38  2372.9  249.91  2949.7  239.77  3103.2  242.84  3701.8  241.18
  3721.7  238.28  3738.3  241.53  4118.3  241.54  4581.6  237.58  4977.6  241.05
  5004.2  237.89 5058.99 241.217  5072.7  240.98  6391.5  239.33  6485.3   238.5
  6535.9  232.77  6591.9  239.09  6798.9  239.41  6924.1  238.38  6931.4  230.49
  6991.8  231.49  7031.6  239.07  7050.9  232.26  7082.2  238.85  7119.4  240.31
  7256.4  235.89  7284.5   239.9  8643.7   241.9  8984.1  251.33    9435  275.87
#Mann= 6 ,-1 , 0
  1888.4     .17       0  2372.9     .11       0  4977.6     .06       0
 5058.99     .09       0  5072.7     .11       0  6991.8     .11       0
Bank Sta=4977.6,5058.99
XS Rating Curve= 0 ,0
Exp/Cntr=0.3,0.1

Type RM Length L Ch R = 1 ,11089   ,661,661,661
BEGIN DESCRIPTION:
MCGARY CREEK 15.0
END DESCRIPTION:
XS GIS Cut Line= 3
      3760404.68     10241785.45       3757183.3     10241081.46
      3752792.58     10240643.63
#Sta/Elev= 30
  1702.6  267.86  1945.2  261.86  2056.8   258.2  2449.2  251.58  2763.9  244.29
  3198.7  242.26  3242.6  238.03  3296.7   241.9  4985.1   239.5  5005.5  236.03
  5025.6  239.91  6504.3  238.79    6533  237.96  6553.1  230.93  6653.6  239.27
  6731.2  238.55  6884.8  238.71  6904.9  230.01  6940.2  228.68  7000.6  229.68
  7025.4   238.5  7095.8  239.09  7226.4  238.78  7246.5  235.52  7266.6  238.76
  7718.9  236.66  8502.7  241.93  8743.9  249.97  9145.9  274.65  9412.5  286.28
#Mann= 9 ,-1 , 0
  1702.6     .17       0  1945.2     .11       0  2056.8     .17       0
  2449.2     .11       0  4985.1     .06       0  5025.6     .11       0
  6504.3     .15       0  6731.2     .11       0  7000.6     .11       0
Bank Sta=4985.1,5025.6
XS Rating Curve= 0 ,0
Exp/Cntr=0.3,0.1

Type RM Length L Ch R = 1 ,10428   ,802,802,802
BEGIN DESCRIPTION:
MCGARY CREEK 14.0
END DESCRIPTION:
XS GIS Cut Line= 3
      3760293.52      10241028.5      3757224.07     10240514.61
      3752844.41     10240422.25
#Sta/Elev= 30
  1777.1  271.52  2356.5  257.42  2877.3  245.01  3283.4  239.08  4965.5  237.77
  4995.5   234.3  5025.5  237.72  5625.6  239.04  6105.8  237.33  6215.8   234.3
  6275.8  238.57  6305.8  235.61  6405.8  238.21  6465.8  234.96  6476.3  227.63
  6536.8  228.63  6575.9  238.18  6875.9  236.31  6975.9  239.23    7276  237.88
    7306  235.19    7326  238.05  7486.1  238.83  7546.1  234.23  7636.1  238.12
  7916.2  238.58  8256.2  243.67  8396.3  247.19  8916.4  269.62  9269.9  277.76
#Mann= 5 ,-1 , 0
  1777.1     .17       0  2356.5     .11       0  4965.5     .06       0
  5025.5     .11       0  6536.8     .11       0
Bank Sta=4965.5,5025.5
XS Rating Curve= 0 ,0
Exp/Cntr=0.3,0.1

Type RM Length L Ch R = 1 ,9626    ,676,676,676
BEGIN DESCRIPTION:
MCGARY CREEK 13.0
END DESCRIPTION:
XS GIS Cut Line= 3
      3760203.23     10240604.88       3756946.3       10239841.
      3752753.23     10239419.64
#Sta/Elev= 30
    1584  277.05  1787.5   269.3  1874.4  265.61  2109.7  257.24  2142.7  256.31
  2596.1  244.38  3366.5  236.91  4980.8  236.91  5008.2  232.93  5028.3   236.6
  5862.4  237.04  5878.1  234.04  6078.6  237.48    6184  233.54  6314.7  238.12
  6374.4  229.79  6379.4  233.46  6425.9  227.69  6486.4  228.69  6505.7  229.99
  6525.8  236.99  6897.6  234.33  6977.1  237.55  7065.9  236.13  7611.2  240.01
  8108.4  251.97  8490.2  260.69  8557.3  262.91    8769  270.39  9143.5  289.21
#Mann= 14 ,-1 , 0
    1584     .11       0  1787.5     .17       0  1874.4     .11       0
  2109.7     .17       0  2142.7     .11       0  4980.8     .06       0
  5028.3     .11       0  6486.4     .11       0  6977.1     .15       0
  7065.9     .11       0  8108.4     .17       0  8490.2     .11       0
  8557.3     .17       0    8769     .11       0
Bank Sta=4980.8,5028.3
XS Rating Curve= 0 ,0
Exp/Cntr=0.3,0.1

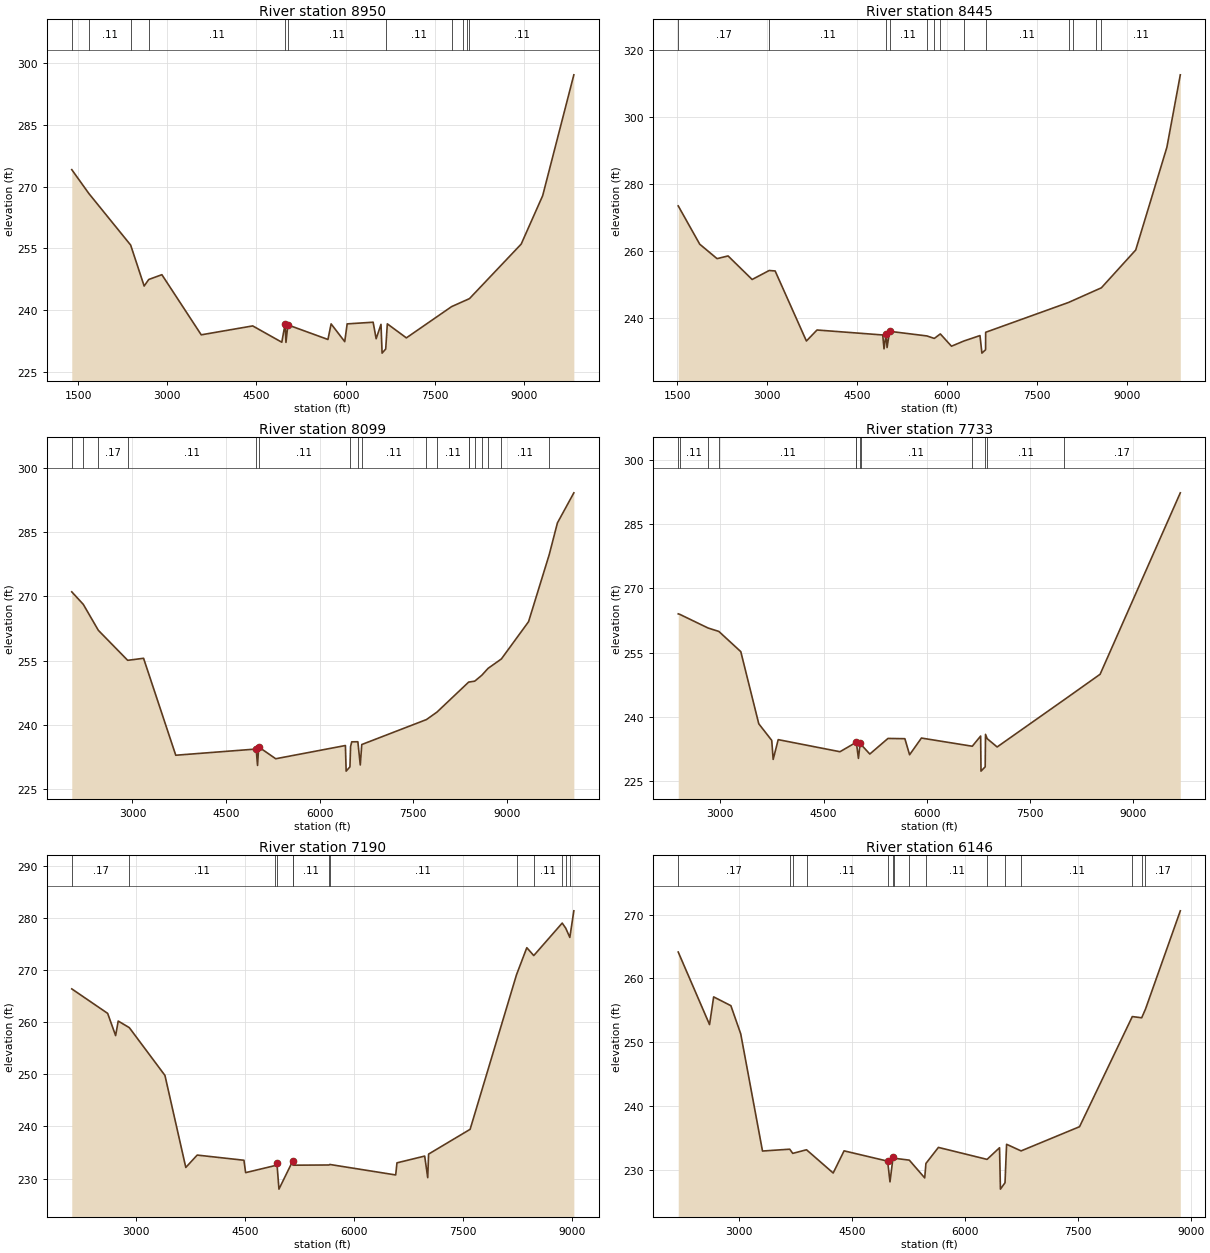
Type RM Length L Ch R = 1 ,8950    ,505,505,505
BEGIN DESCRIPTION:
MCGARY CREEK 12.0
END DESCRIPTION:
XS GIS Cut Line= 4
      3760422.48     10240500.35      3759458.97     10239849.33
       3757097.8     10239222.05      3752336.56     10238351.93
#Sta/Elev= 30
  1394.1  274.12  1680.8  268.33  2384.8  255.77  2611.8  245.81  2689.1   247.4
  2909.9  248.57  3572.1  233.94  4437.6  236.11  4927.5  232.14 4983.66236.6718
  4997.4   232.1  5029.3  236.36  5703.6  232.81  5756.8   236.6    5986  232.28
  6026.7   236.6  6463.8  237.01  6514.6  232.99    6596  236.49  6614.5  229.49
  6675.1  230.49  6702.4  236.61  7022.9   233.2  7783.3   240.8  7982.6  242.09
  8048.2  242.51  8084.6  242.75  8954.4  256.01  9315.8  267.79  9840.1  297.18
#Mann= 11 ,-1 , 0
  1394.1     .17       0  1680.8     .11       0  2384.8     .17       0
  2689.1     .11       0 4983.66     .06       0  5029.3     .11       0
  6675.1     .11       0  7783.3     .15       0  7982.6     .11       0
  8048.2     .15       0  8084.6     .11       0
Bank Sta=4983.66,5029.3
XS Rating Curve= 0 ,0
Exp/Cntr=0.3,0.1

Type RM Length L Ch R = 1 ,8445    ,346,346,346
BEGIN DESCRIPTION:
MCGARY CREEK 11.0
END DESCRIPTION:
XS GIS Cut Line= 4
       3760552.7     10239797.24      3758156.83     10239103.13
      3755011.17     10238279.52      3752427.89     10237766.03
#Sta/Elev= 30
  1515.8  273.48  1874.5  262.07    2164  257.76  2347.5  258.57  2749.4  251.55
  3033.9  254.23  3133.3  254.09  3655.1  233.22  3832.1   236.5  4929.1  235.02
  4950.5  230.89 4984.68 235.415  5001.5  231.28 5043.16236.1083    5667  234.73
  5789.2  233.99  5890.3  235.33  6076.5  231.67  6283.1  233.22  6552.1  234.84
  6584.4  229.61  6645.2  230.61    6647  235.82  8030.4  244.71  8107.2  245.32
  8486.6  248.34  8578.3  249.07  9151.5  260.34  9671.4  290.93  9895.7  312.53
#Mann= 13 ,-1 , 0
  1515.8     .17       0  3033.9     .11       0 4984.68     .06       0
 5043.16     .11       0    5667     .15       0  5789.2     .11       0
  5890.3     .15       0  6283.1     .11       0  6645.2     .11       0
  8030.4     .15       0  8107.2     .11       0  8486.6     .17       0
  8578.3     .11       0
Bank Sta=4984.68,5043.16
XS Rating Curve= 0 ,0
Exp/Cntr=0.3,0.1

Type RM Length L Ch R = 1 ,8099    ,366,366,366
BEGIN DESCRIPTION:
MCGARY CREEK 10.0
END DESCRIPTION:
XS GIS Cut Line= 3
      3760240.17     10239393.59      3757382.53     10238572.75
      3752482.98     10237246.02
#Sta/Elev= 30
  2026.8  271.06    2212  268.13  2452.8  262.08  2923.2  255.07  3177.9  255.55
  3693.9  232.91  4983.4  234.36    5005  230.53    5023  234.85  5296.7  232.09
  6413.8  235.18  6425.6   229.2  6486.4   230.2  6496.7  234.94    6515  236.04
  6613.4  236.06  6652.1  230.63  6676.1  235.41  7713.2  241.24  7882.2  242.99
  8388.9  249.98  8400.1  250.01  8487.3  250.21  8599.5  251.57  8700.7  253.19
  8914.8   255.4  9349.9  264.09  9681.1  279.74  9812.6  287.15   10076  294.18
#Mann= 18 ,-1 , 0
  2026.8     .17       0    2212     .11       0  2452.8     .17       0
  2923.2     .11       0  4983.4     .06       0    5023     .11       0
  6486.4     .11       0  6613.4     .15       0  6676.1     .11       0
  7713.2     .17       0  7882.2     .11       0  8388.9     .17       0
  8400.1     .11       0  8487.3     .17       0  8599.5     .11       0
  8700.7     .17       0  8914.8     .11       0  9681.1     .17       0
Bank Sta=4983.4,5023
XS Rating Curve= 0 ,0
Exp/Cntr=0.3,0.1

Type RM Length L Ch R = 1 ,7733    ,543,543,543
BEGIN DESCRIPTION:
MCGARY CREEK 9.0
END DESCRIPTION:
XS GIS Cut Line= 4
      3760096.96     10239055.05      3758000.64     10238417.04
      3754695.28      10237576.1      3753482.63     10236399.02
#Sta/Elev= 30
  2388.7  264.07  2413.2  263.94  2821.3  260.77  2978.5  259.97  3297.2  255.25
  3558.5  238.41  3746.6  234.54  3767.6   230.1  3840.7  234.71  4737.6  231.89
  4974.9   234.1 4975.39234.0876  5005.9  230.33  5030.9  233.95  5036.9  233.69
    5171  231.35  5434.9  234.99  5680.4  234.93  5748.8  231.18  5920.7  235.08
  6659.3  233.17  6780.7  235.55    6786  227.36  6846.8  228.36  6851.4  235.94
  6875.9  234.93  7020.3     233  7987.9  243.95  8515.8  249.97  9680.6  292.32
#Mann= 12 ,-1 , 0
  2388.7     .17       0  2413.2     .11       0  2821.3     .17       0
  2978.5     .11       0  4974.9     .09       0 4975.39     .06       0
  5030.9     .09       0  5036.9     .11       0  6659.3     .15       0
  6846.8     .15       0  6875.9     .11       0  7987.9     .17       0
Bank Sta=4975.39,5030.9
XS Rating Curve= 0 ,0
Exp/Cntr=0.3,0.1

Type RM Length L Ch R = 1 ,7190    ,1044,1044,1044
BEGIN DESCRIPTION:
MCGARY CREEK 8.0
END DESCRIPTION:
XS GIS Cut Line= 3
      3760435.56     10238911.84       3757739.3     10237884.38
      3754003.21     10236372.76
#Sta/Elev= 30
  2114.6  266.38    2609  261.68  2718.7  257.42  2754.2  260.21  2907.5  258.94
  3398.1  249.78  3685.3  232.13  3842.1   234.5  4486.1  233.51  4509.3  231.13
  4916.1  232.49  4940.9   232.9  4968.4  227.97  5156.7  233.32  5163.4  232.56
  5658.1   232.6    5669   232.7  6576.5  230.69    6594  233.01  6975.7  234.31
  7017.6  230.17  7029.6  234.69  7601.3  239.44  8240.8   269.1  8382.5  274.28
  8478.4  272.77    8870     279  8918.7  278.02  8974.9  276.25  9030.3  281.35
#Mann= 13 ,-1 , 0
  2114.6     .17       0  2907.5     .11       0  4916.1     .09       0
  4940.9     .06       0  5156.7     .09       0  5163.4     .11       0
  5658.1     .15       0    5669     .11       0  8240.8     .17       0
  8478.4     .11       0    8870     .17       0  8918.7     .11       0
  8974.9     .17       0
Bank Sta=4940.9,5156.7
XS Rating Curve= 0 ,0
Exp/Cntr=0.3,0.1

Type RM Length L Ch R = 1 ,6146    ,1019,1019,1019
BEGIN DESCRIPTION:
MCGARY CREEK 7.0
END DESCRIPTION:
XS GIS Cut Line= 3
      3760539.71     10238156.63      3758169.91       10237141.
      3754237.65     10236047.26
#Sta/Elev= 30
  2198.2  264.15  2613.6  252.76    2668  257.11  2896.5  255.73  3027.1  251.31
    3316  232.91  3677.3   233.2  3717.2  232.54  3899.7  233.11  4253.5  229.46
  4397.9  232.94  4975.8  231.32    5007  228.07  5048.5  232.02  5054.9  231.79
  5263.5  231.48  5467.7  228.69  5483.7  230.96  5649.2  233.48  6294.8   231.6
  6460.1  233.43    6472  226.93  6532.8  227.93  6553.7  233.97  6745.6  232.93
  7521.5  236.73  8221.2  254.02  8345.8  253.83  8396.1  255.19    8858  270.62
#Mann= 15 ,-1 , 0
  2198.2     .17       0  3677.3     .11       0  3717.2     .15       0
  3899.7     .11       0  4975.8     .06       0  5048.5     .09       0
  5054.9     .11       0  5263.5     .15       0  5483.7     .11       0
  6294.8     .15       0  6532.8     .15       0  6745.6     .11       0
  8221.2     .17       0  8345.8     .11       0  8396.1     .17       0
Bank Sta=4975.8,5048.5
XS Rating Curve= 0 ,0
Exp/Cntr=0.3,0.1

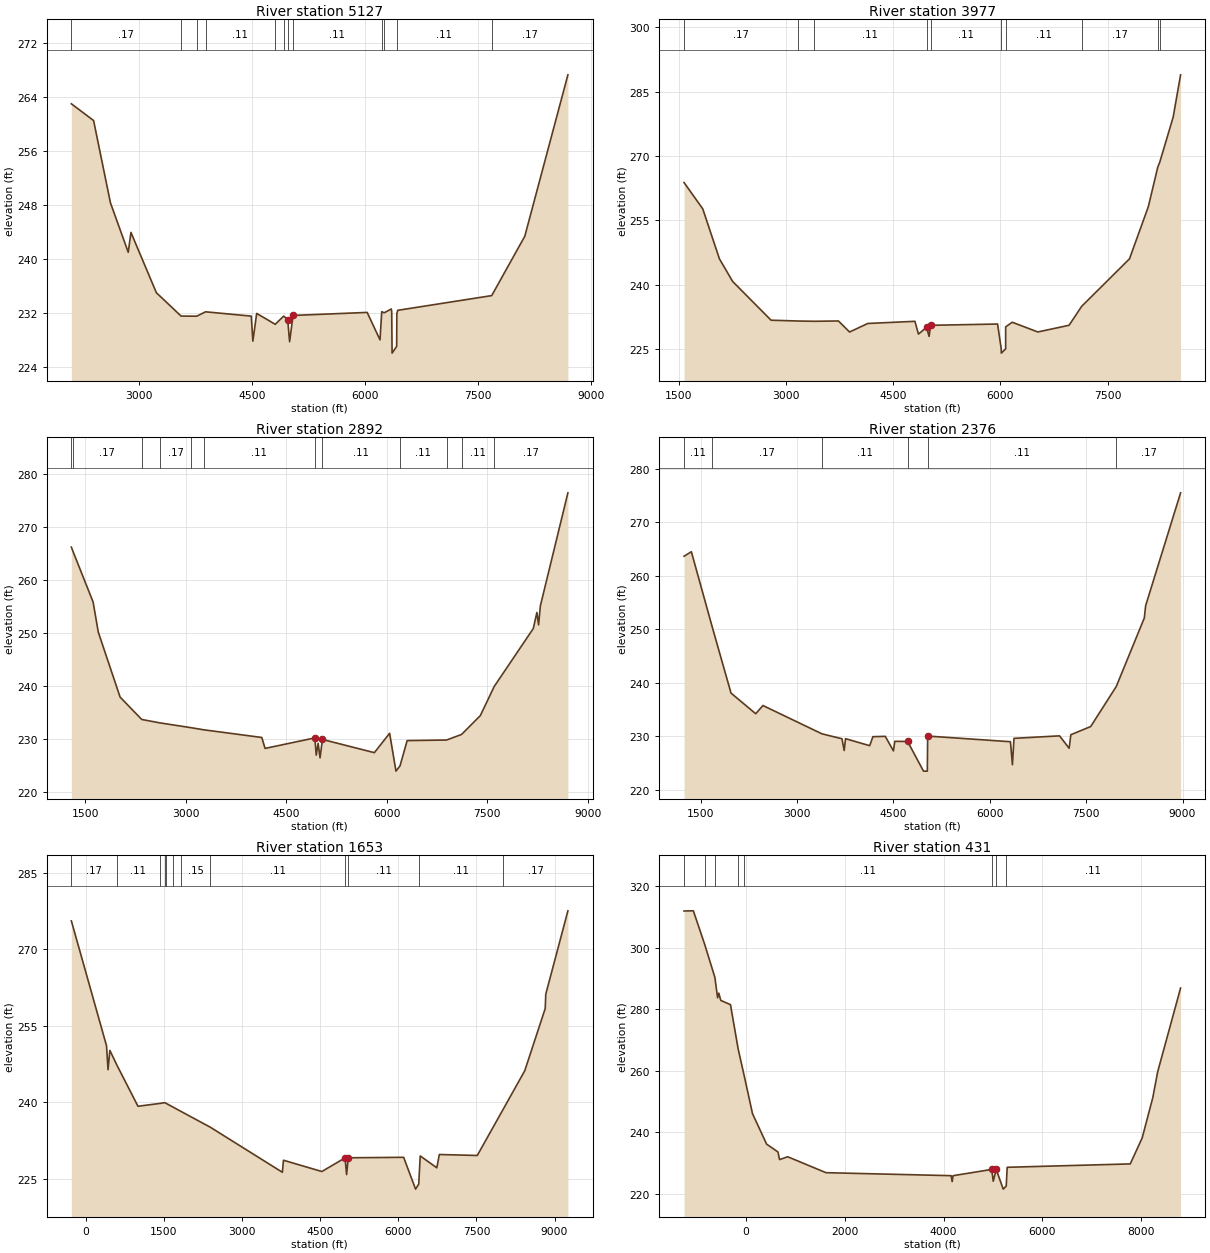
Type RM Length L Ch R = 1 ,5127    ,1150,1150,1150
BEGIN DESCRIPTION:
MCGARY CREEK 6.0
END DESCRIPTION:
XS GIS Cut Line= 3
      3760735.04     10237844.14      3758586.57     10236359.75
      3754745.41      10235331.1
#Sta/Elev= 30
    2101  263.04    2396  260.56  2619.8  248.36  2855.7  241.05  2891.5  243.99
  3228.8  235.06  3556.6   231.6  3764.6  231.58  3881.5  232.23  4488.1  231.59
    4509  227.88  4559.7  231.99  4805.9  230.38  4917.8  231.59 4971.02  231.08
  4996.5   227.8  5042.3  231.69  6025.8  232.14  6196.1  228.07  6218.9  232.26
  6250.7  232.08  6345.9  232.65  6351.1  232.27  6356.2  226.11  6417.1  227.11
  6419.2  231.94  6431.1  232.45  7678.1  234.63    8117  243.42  8688.9  267.33
#Mann= 12 ,-1 , 0
    2101     .17       0  3556.6     .15       0  3764.6     .17       0
  3881.5     .11       0  4805.9     .15       0  4917.8     .11       0
 4971.02     .06       0  5042.3     .11       0  6218.9     .15       0
  6250.7     .11       0  6417.1     .11       0  7678.1     .17       0
Bank Sta=4971.02,5042.3
XS Rating Curve= 0 ,0
Exp/Cntr=0.3,0.1

Type RM Length L Ch R = 1 ,3977    ,1085,1085,1085
BEGIN DESCRIPTION:
MCGARY CREEK 5.0
END DESCRIPTION:
XS GIS Cut Line= 3
      3760787.08     10237700.88      3758195.95     10235396.21
      3754862.71     10234406.65
#Sta/Elev= 30
  1575.1  263.83  1836.6  257.71  2069.9  246.06  2254.7  240.79  2792.4  231.76
  3173.1  231.57    3396  231.51  3734.7  231.58  3890.3  229.01  4145.3     231
  4804.2   231.5  4853.6  228.52  4967.3  230.11  5002.4  227.99  5024.1  230.57
  5960.5  230.87  6011.1  225.09  6012.6  224.09  6073.5  225.09  6073.6   230.2
    6165  231.29  6523.2  229.02  6960.3  230.58  7136.3  234.99  7805.2  246.06
  8068.2  258.18  8201.4  267.46  8227.2   268.5    8416  279.06  8519.9  288.93
#Mann= 10 ,-1 , 0
  1575.1     .17       0  3173.1     .15       0    3396     .11       0
  4967.3     .06       0  5024.1     .11       0  6011.1     .11       0
  6073.5     .11       0  7136.3     .17       0  8201.4     .11       0
  8227.2     .17       0
Bank Sta=4967.3,5024.1
XS Rating Curve= 0 ,0
Exp/Cntr=0.3,0.1

Type RM Length L Ch R = 1 ,2892    ,516,516,516
BEGIN DESCRIPTION:
MCGARY CREEK 4.0
END DESCRIPTION:
XS GIS Cut Line= 3
      3761073.53     10237583.68      3758443.34     10234810.27
      3754981.31     10233860.16
#Sta/Elev= 30
    1294  266.17  1317.7  265.38  1618.1  255.85  1696.1  250.15  2021.4  237.92
  2344.4   233.7    2616  233.06    3078  232.16  3267.6  231.76  4136.5  230.31
  4185.9  228.25  4928.6  230.23  4949.8  226.99  4977.9  229.22  5006.3  226.47
  5041.8  229.94  5817.1  227.45  6044.9   231.1  6139.6  223.97  6200.5  224.97
  6306.4  229.72  6894.1  229.83  7119.1  230.88  7398.7  234.43  7606.9  239.93
  8189.5  250.83  8243.3  253.86  8268.8  251.53  8295.1   255.1  8706.3   276.4
#Mann= 12 ,-1 , 0
    1294     .11       0  1317.7     .17       0  2344.4     .15       0
    2616     .17       0    3078     .15       0  3267.6     .11       0
  4928.6     .06       0  5041.8     .11       0  6200.5     .11       0
  6894.1     .17       0  7119.1     .11       0  7606.9     .17       0
Bank Sta=4928.6,5041.8
XS Rating Curve= 0 ,0
Exp/Cntr=0.3,0.1

Type RM Length L Ch R = 1 ,2376    ,723,723,723
BEGIN DESCRIPTION:
MCGARY CREEK 3.0
END DESCRIPTION:
XS GIS Cut Line= 3
      3761267.82     10237511.04       3758729.8     10234458.71
      3755067.89     10233611.08
#Sta/Elev= 30
  1241.3  263.65  1355.2  264.49  1683.9  250.25  1972.3  238.05  2356.4  234.19
  2469.7  235.72  3386.8  230.43  3698.7  229.51  3733.9  227.31  3754.7  229.52
    4131  228.21  4180.5  229.89  4373.1  229.96  4500.7  227.23  4521.6  229.02
  4720.8     229  4968.4  223.45  5027.8  223.45  5033.2  230.01  6321.5  228.95
  6352.3  224.65  6376.8  229.58  7085.7  230.05  7235.1  227.73  7261.6  230.26
  7570.8  231.79  7968.6  239.28  8405.2   252.1  8425.7  254.39  8969.7  275.51
#Mann= 6 ,-1 , 0
  1241.3     .11       0  1683.9     .17       0  3386.8     .11       0
  4720.8     .06       0  5033.2     .11       0  7968.6     .17       0
Bank Sta=4720.8,5033.2
XS Rating Curve= 0 ,0
Exp/Cntr=0.3,0.1

Type RM Length L Ch R = 1 ,1653    ,1222,1222,1222
BEGIN DESCRIPTION:
MCGARY CREEK 2.0
END DESCRIPTION:
XS GIS Cut Line= 3
      3763339.15     10237492.54      3759524.07     10234224.33
        3755123.     10233234.74
#Sta/Elev= 30
  -277.6  275.57   397.8   251.1   426.3  246.43   461.5   250.2   601.4  247.23
  1001.4  239.26  1417.9  239.81  1517.6  239.96  1543.8  239.82  1675.8  239.09
  1829.5  238.24  2388.4  235.17    3774  226.33  3794.9  228.69  4532.5  226.48
  4977.8  229.15  5007.5  225.88  5039.3  229.17  6102.8  229.26  6331.8  223.03
  6392.7  224.03  6421.3  229.53  6739.7  227.21  6788.1  229.81  7516.6  229.62
  8020.1  238.78  8428.6  246.22  8821.4  258.41  8831.7   261.2  9256.9  277.54
#Mann= 12 ,-1 , 0
  -277.6     .17       0   601.4     .11       0  1417.9     .15       0
  1517.6     .11       0  1543.8     .15       0  1675.8     .11       0
  1829.5     .15       0  2388.4     .11       0  4977.8     .06       0
  5039.3     .11       0  6392.7     .11       0  8020.1     .17       0
Bank Sta=4977.8,5039.3
XS Rating Curve= 0 ,0
Exp/Cntr=0.3,0.1

Type RM Length L Ch R = 1 ,431     ,0,0,0
BEGIN DESCRIPTION:
MCGARY CREEK 1.0
END DESCRIPTION:
XS GIS Cut Line= 3
      3765097.01     10235057.67      3759836.57     10233338.91
      3755357.44     10232752.98
#Sta/Elev= 30
 -1255.1  311.88 -1066.6  311.93  -834.6  300.91  -631.6  290.35  -575.6  283.69
  -551.1  285.19  -511.8  282.84  -315.3  281.46  -159.3  267.05   -36.1  258.28
     131  246.04   416.7  236.17   646.3  233.62   678.2  231.15   842.9  232.07
  1618.5   226.9  4151.4  225.93  4172.5     224  4189.9  225.92  4973.6  227.96
  5003.9  224.11  5064.4  227.96  5206.1  221.56    5267  222.56  5286.2  228.65
  7777.3  229.75  8019.3   238.2  8234.5  251.32    8332  259.63  8796.3  286.86
#Mann= 8 ,-1 , 0
 -1255.1     .11       0  -834.6     .17       0  -631.6     .11       0
  -159.3     .17       0   -36.1     .11       0  4973.6     .06       0
  5064.4     .11       0    5267     .11       0
Bank Sta=4973.6,5064.4
XS Rating Curve= 0 ,0
Exp/Cntr=0.3,0.1

Chan Stop Cuts=-1
Use User Specified Reach Order=0
Composite Channel Slope=5