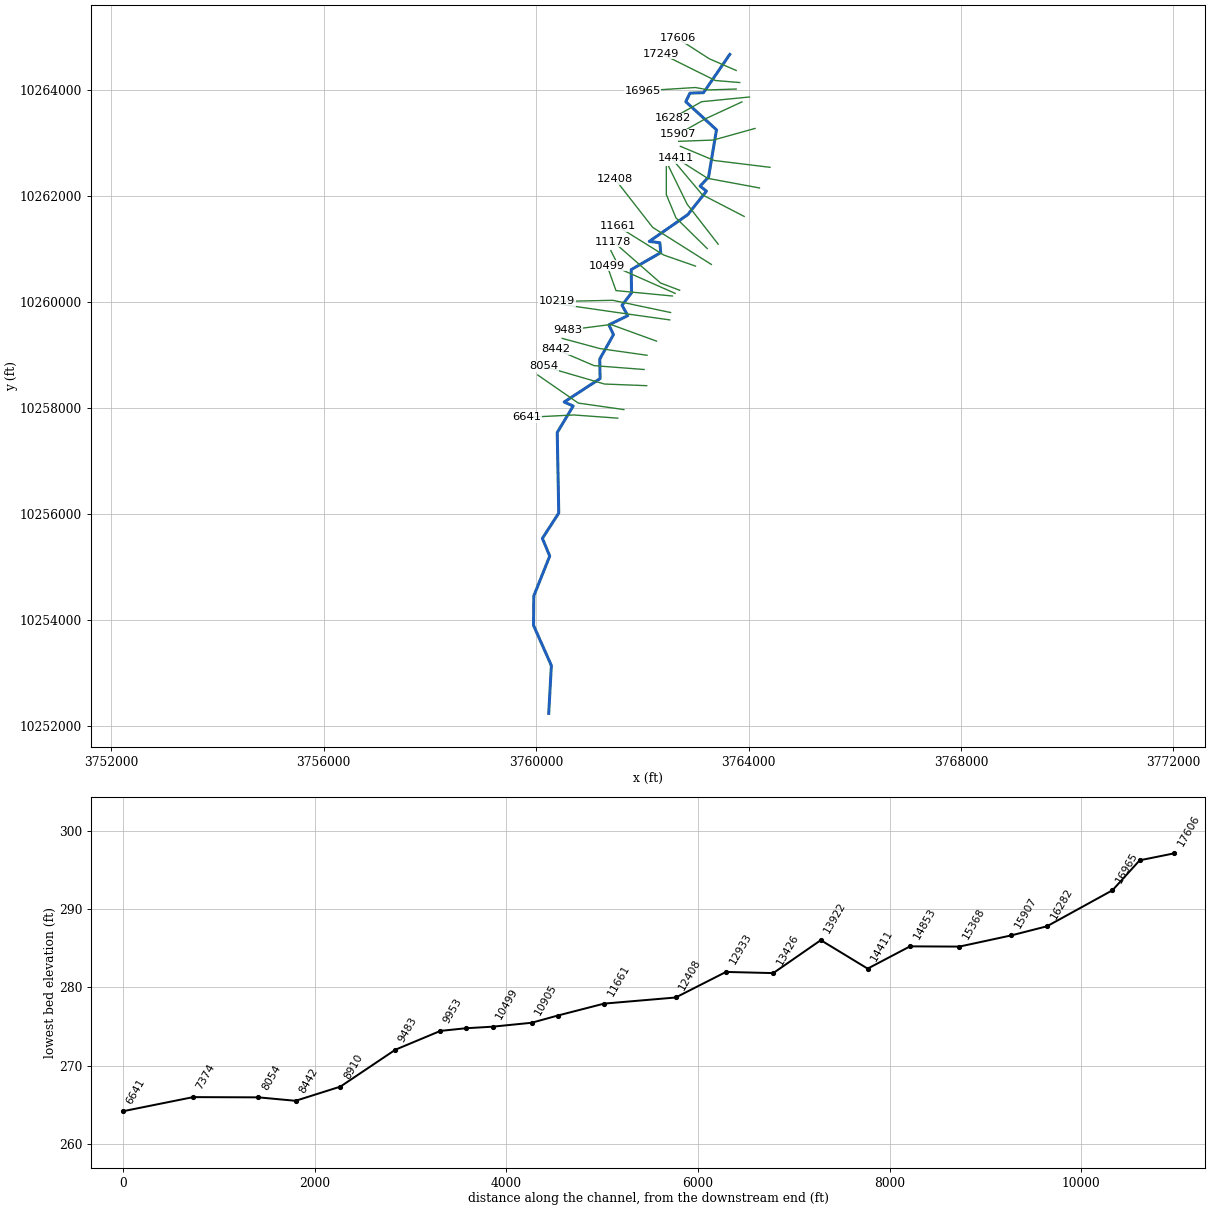
--- MOCK BRANCH.prj (project) ---

Proj Title=MOCK BRANCH Base Level Engineering
Current Plan=p01
Default Exp/Contr=0.3,0.1
English Units
Geom File=g01
Flow File=f01
Flow File=f02
Plan File=p01
Y Axis Title=Elevation
X Axis Title(PF)=Main Channel Distance
X Axis Title(XS)=Station
BEGIN DESCRIPTION:
MOCK BRANCH
END DESCRIPTION:
DSS Export Rating Curves= 0
DSS Export Rating Curve Sorted= 0
DSS Export Volume Flow Curves= 0
DXF OffsetX= 0
DXF OffsetY= 0
DXF ScaleX= 1
DXF ScaleY= 10

--- MOCK BRANCH.p01 (plan) ---

Plan Title=Multiple Run
Program Version=4.10
Short Identifier=Multiple
Geom File=g01
Flow File=f01
Subcritical Flow
K Sum by GR= 0
Std Step Tol= 0.01
Critical Tol= 0.01
Num of Std Step Trials= 20
Max Error Tol= 0.3
Flow Tol Ratio= 0.001
Split Flow NTrial= 30
Split Flow Tol= 0.02
Split Flow Ratio= 0.02
Log Output Level= 0
Friction Slope Method= 1
Unsteady Friction Slope Method= 2
Unsteady Bridges Friction Slope Method= 1
Parabolic Critical Depth
Global Vel Dist= 1 , 1 , 1
Global Log Level= 0
CheckData=True
Encroach Param=-1 ,0,0, 0
BEGIN DESCRIPTION:
Multiple Run
END DESCRIPTION:
Computation Interval=1HOUR
Output Interval=1HOUR
Run HTab= 0
Run UNet= 0
Run PostProcess= 0
Run WQNet= 0
UNET Theta= 1
UNET Theta Warmup= 1
UNET ZTol= 0.02
UNET ZSATol= 0.05
UNET MxIter= 20
UNET MaxInSteps= 0
UNET DtIC= 0
UNET DtMin= 0
UNET MaxCRTS= 20
UNET WFStab= 2
UNET SFStab= 1
UNET WFX= 1
UNET SFX= 1
UNET DSS MLevel= 4
UNET DZMax Abort= 100
UNET Convert EG Bridges= 0
UNET Use Existing IB Tables=-1
UNET Froude Reduction=False
UNET Froude Limit= 1
UNET Froude Power= 10
UNET Time Slicing=0,0, 5
UNET Junction Losses=0
Instantaneous Interval=1HOUR
Write IC File= 0
Write IC File at Sim End=0
Echo Input=False
Echo Parameters=False
Echo Output=False
Write Detailed= 0
WQ AD Non Conservative
WQ ULTIMATE=-1
WQ Max Comp Step=1HOUR
WQ Output Interval=15MIN
WQ Output Selected Increments= 0
WQ Output face flow=0
WQ Output face velocity=0
WQ Output face area=0
WQ Output face dispersion=0
WQ Output cell volume=0
WQ Output cell surface area=0
WQ Output cell continuity=0
WQ Output cumulative cell continuity=0
WQ Output face conc=0
WQ Output face dconc_dx=0
WQ Output face courant=0
WQ Output face peclet=0
WQ Output face adv mass=0
WQ Output face disp mass=0
WQ Output cell mass=0
WQ Output cell source sink temp=0
WQ Output cell source sink nsm=0
WQ Output MaxMinRange=-1
WQ Daily Max Min Mean=-1
WQ Daily Range=0
WQ Daily Time=0
WQ Create Restart=0
WQ Fixed Restart=0
WQ System Summary=0
WQ Use Fixed Temperature=0
Sorting and Armoring Iterations= 10
XS Update Threshold= 0.02
Hydraulics Update Threshold= 0.02
Energy Slope Method= 1
Volume Change Method= 0
XS Weighting Method= 0
Number of US Weighted Cross Sections= 1
Number of DS Weighted Cross Sections= 1
Upstream XS Weight=0.25
Main XS Weight=0.5
Downstream XS Weight=0.25
Number of DS XS's Weighted with US Boundary= 1
Upstream Boundary Weight= 1
Weight of XSs Associated with US Boundary= 0
Number of US XS's Weighted with DS Boundary= 1
Downstream Boundary Weight= 0.5
Weight of XSs Associated with DS Boundary= 0.5
Sediment Output Level= 4
Mass or Volume Output= 0
Output Increment Type= 1
Profile and TS Output Increment= 10
XS Output Flag= 0
XS Output Increment= 10
Disregard all LS=0
Disregard all Conn=0
Disregard all Breaches=0
Disregard all Pumps=0

--- MOCK BRANCH.f01 (steady flow) ---

Flow Title=Multiple
Program Version=4.10
Number of Profiles= 7
Profile Names=10-year,25-year,50-year,1pct_min,100-year,1pct_plu,500-year
River Rch & RM=MOCK BRANCH,Reach-1         ,17606
     522     693     922     405    1222    3690    2217
River Rch & RM=MOCK BRANCH,Reach-1         ,16965
     890    1213    1646     733    2214    6686    4143
River Rch & RM=MOCK BRANCH,Reach-1         ,10219
    1151    1580    2152     960    2900    8758    5456
River Rch & RM=MOCK BRANCH,Reach-1         ,8910
    1151    1580    2152     960    2900    8758    5456
River Rch & RM=MOCK BRANCH,Reach-1         ,3711
    1530    2128    2923    1315    3972   11995    7589
River Rch & RM=MOCK BRANCH,Reach-1         ,2974
    1530    2128    2923    1315    3972   11995    7589
Boundary for River Rch & Prof#=MOCK BRANCH,Reach-1         , 1
Up Type= 0
Dn Type= 3
Dn Slope=0.005
Boundary for River Rch & Prof#=MOCK BRANCH,Reach-1         , 2
Up Type= 0
Dn Type= 3
Dn Slope=0.005
Boundary for River Rch & Prof#=MOCK BRANCH,Reach-1         , 3
Up Type= 0
Dn Type= 3
Dn Slope=0.005
Boundary for River Rch & Prof#=MOCK BRANCH,Reach-1         , 4
Up Type= 0
Dn Type= 3
Dn Slope=0.005
Boundary for River Rch & Prof#=MOCK BRANCH,Reach-1         , 5
Up Type= 0
Dn Type= 3
Dn Slope=0.005
Boundary for River Rch & Prof#=MOCK BRANCH,Reach-1         , 6
Up Type= 0
Dn Type= 3
Dn Slope=0.005
Boundary for River Rch & Prof#=MOCK BRANCH,Reach-1         , 7
Up Type= 0
Dn Type= 3
Dn Slope=0.005
DSS Import GetInterval= 0
DSS Import GetPeak= 0
DSS Import FillOption= 0

--- MOCK BRANCH.f02 (steady flow) ---

Flow Title=Orig_BLE_Flow
Program Version=4.10
Number of Profiles= 7
Profile Names=10-year,25-year,50-year,1pct_min,100-year,1pct_plu,500-year
River Rch & RM=MOCK BRANCH,Reach-1         ,17606
     522     679     802     311     940    2840    1289
River Rch & RM=MOCK BRANCH,Reach-1         ,16965
     890    1189    1431     564    1703    5143    2409
River Rch & RM=MOCK BRANCH,Reach-1         ,10219
    1151    1549    1871     739    2231    6739    3172
River Rch & RM=MOCK BRANCH,Reach-1         ,8910
    1151    1549    1871     739    2231    6739    3172
River Rch & RM=MOCK BRANCH,Reach-1         ,3711
    1530    2086    2542    1011    3055    9225    4412
River Rch & RM=MOCK BRANCH,Reach-1         ,2974
    1530    2086    2542    1011    3055    9225    4412
Boundary for River Rch & Prof#=MOCK BRANCH,Reach-1         , 1
Up Type= 0
Dn Type= 3
Dn Slope=0.003
Boundary for River Rch & Prof#=MOCK BRANCH,Reach-1         , 2
Up Type= 0
Dn Type= 3
Dn Slope=0.003
Boundary for River Rch & Prof#=MOCK BRANCH,Reach-1         , 3
Up Type= 0
Dn Type= 3
Dn Slope=0.003
Boundary for River Rch & Prof#=MOCK BRANCH,Reach-1         , 4
Up Type= 0
Dn Type= 3
Dn Slope=0.003
Boundary for River Rch & Prof#=MOCK BRANCH,Reach-1         , 5
Up Type= 0
Dn Type= 3
Dn Slope=0.003
Boundary for River Rch & Prof#=MOCK BRANCH,Reach-1         , 6
Up Type= 0
Dn Type= 3
Dn Slope=0.003
Boundary for River Rch & Prof#=MOCK BRANCH,Reach-1         , 7
Up Type= 0
Dn Type= 3
Dn Slope=0.003
DSS Import GetInterval= 0
DSS Import GetPeak= 0
DSS Import FillOption= 0

--- MOCK BRANCH.g01 (geometry) ---

Geom Title=Existing Conditions
Program Version=4.10

River Reach=MOCK BRANCH     ,Reach-1
Reach XY= 30
      3763647.51     10264663.99      3763152.64     10263941.92
      3762898.17     10263934.62      3762818.75     10263771.52
      3763397.46     10263242.55      3763247.35     10262350.27
      3763088.52     10262181.43      3763208.23     10262086.84
       3762855.6      10261643.8      3762132.17     10261139.98
      3762331.37     10261114.26      3762346.82     10260928.28
      3761791.17      10260608.4      3761797.64     10260170.86
      3761618.28     10259936.45       3761727.6     10259741.17
      3761370.75     10259567.48      3761457.99     10259383.94
      3761199.22     10258923.38      3761205.39     10258555.19
      3760529.21     10258113.48      3760698.63     10258037.88
      3760398.51      10257538.9      3760427.52     10256021.88
      3760119.24      10255544.2      3760257.52     10255211.96
      3759958.03     10254462.21      3759952.62     10253904.36
       3760288.2     10253147.84      3760238.23     10252246.84

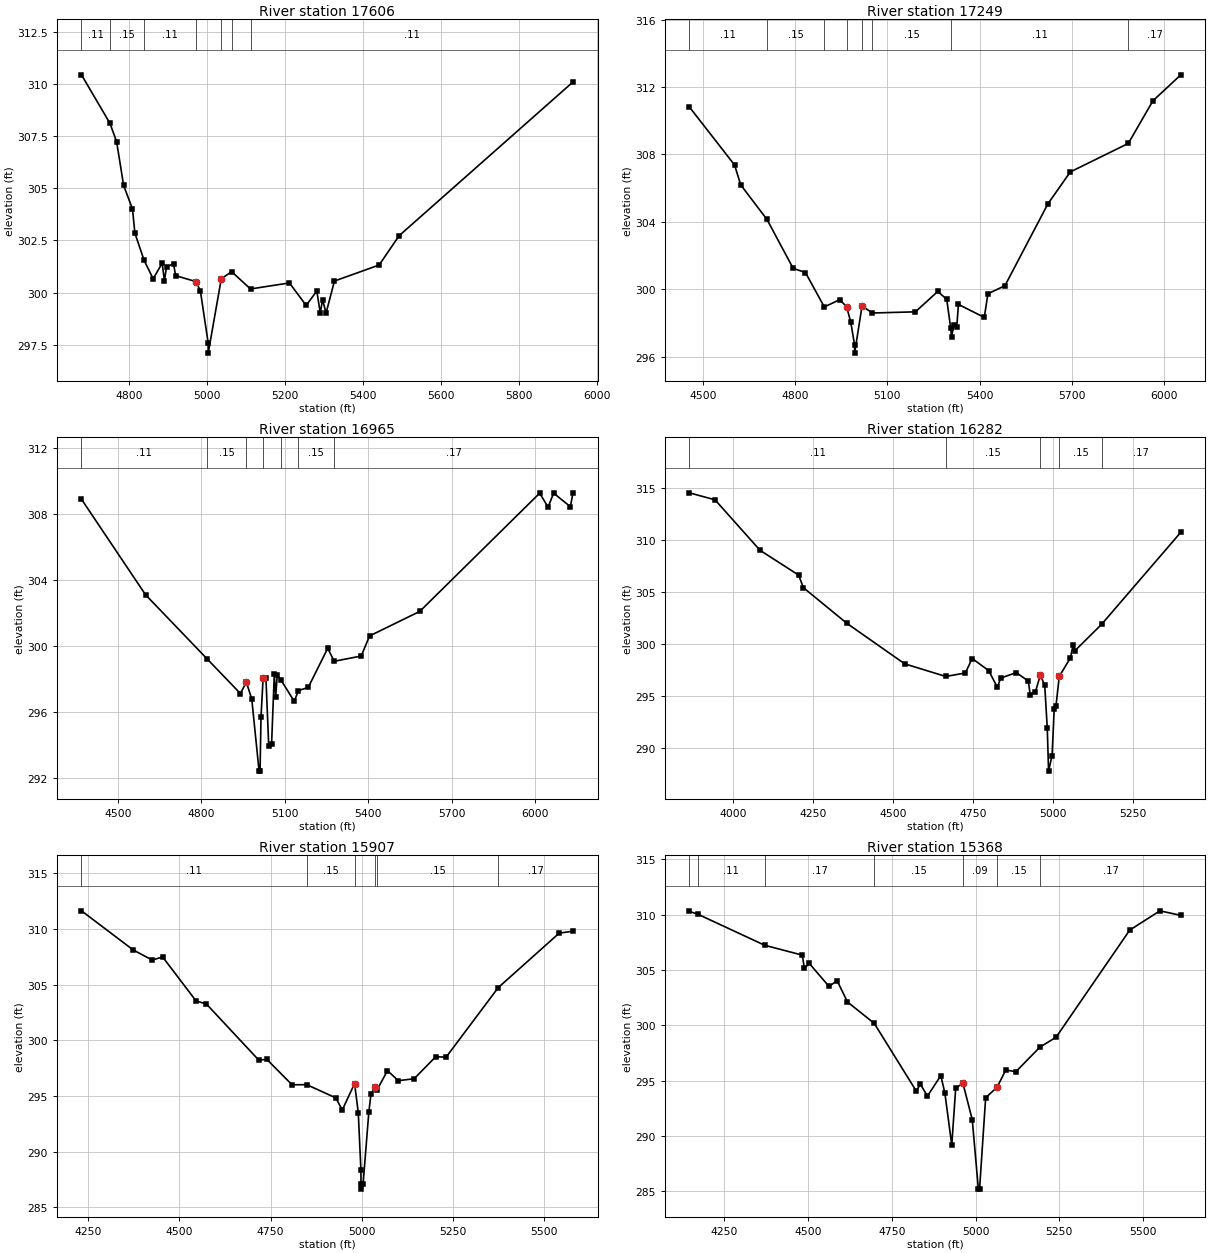
Type RM Length L Ch R = 1 ,17606   ,357,357,357
BEGIN DESCRIPTION:
MOCK BRANCH 30.0
END DESCRIPTION:
XS GIS Cut Line= 3
      3763767.87     10264361.07      3763261.78      10264581.2
      3762664.96     10264966.36
#Sta/Elev= 30
  4676.8  310.45  4749.9  308.12    4767  307.24    4785  305.14  4807.7  304.01
  4813.9  302.85  4837.7  301.54  4860.8  300.66    4884  301.41  4889.7  300.56
  4895.1  301.23  4913.1  301.38  4918.6  300.81  4971.3  300.52  4982.2  300.06
    5002  297.59  5002.2  297.09  5035.8  300.66  5062.4     301  5110.8  300.17
  5210.8  300.46  5253.7  299.38    5281  300.07    5290  299.02  5295.9  299.66
  5304.8  299.01  5326.3  300.55  5441.1  301.32  5492.6  302.73    5939  310.11
#Mann= 7 ,-1 , 0
  4676.8     .11       0  4749.9     .15       0  4837.7     .11       0
  4971.3     .06       0  5035.8     .11       0  5062.4     .15       0
  5110.8     .11       0
#XS Ineff= 1 ,-1
    4840  4913.1  301.38
Permanent Ineff=
       F
Bank Sta=4971.3,5035.8
XS Rating Curve= 0 ,0
Exp/Cntr=0.3,0.1

Type RM Length L Ch R = 1 ,17249   ,284,284,284
BEGIN DESCRIPTION:
Mapping XS fd1d87c7
END DESCRIPTION:
XS GIS Cut Line= 3
      3763834.67     10264133.28      3763376.37     10264171.47
       3762355.5     10264678.43
#Sta/Elev= 30
  4455.3  310.82  4602.6  307.37  4622.7  306.19  4708.1  304.14  4793.3  301.24
  4833.4  300.99  4894.7  298.95  4944.7  299.38  4967.1  298.97  4980.5  298.07
  4993.1  296.71  4993.4  296.21  5017.5  299.01  5051.1  298.59  5191.2  298.66
    5264  299.87  5293.1   299.4    5306   297.7  5308.8  297.14  5315.5  297.88
  5325.6  297.75  5331.2   299.1  5415.3  298.33  5427.1  299.73  5482.5  300.21
  5622.5  305.07  5695.3  306.96    5884  308.65  5964.2  311.18    6055  312.72
#Mann= 8 ,-1 , 0
  4455.3     .11       0  4708.1     .15       0  4894.7     .11       0
  4967.1     .06       0  5017.5     .11       0  5051.1     .15       0
    5306     .11       0    5884     .17       0
Bank Sta=4967.1,5017.5
XS Rating Curve= 0 ,0
Exp/Cntr=0.3,0.1

Type RM Length L Ch R = 1 ,16965   ,683,683,683
BEGIN DESCRIPTION:
MOCK BRANCH 29.0
END DESCRIPTION:
XS GIS Cut Line= 4
      3763767.82     10264011.07      3763244.42     10263994.39
      3763001.37     10264039.53      3762008.31     10263977.03
#Sta/Elev= 30
  4369.3   308.9  4599.4   303.1  4819.8  299.22  4940.3   297.1  4961.4   297.8
    4981  296.77  5007.3  292.39  5010.8  292.39  5014.2  295.68  5021.7  298.02
  5031.9  298.05    5042   293.9  5052.2  294.01  5061.9  298.27    5067  296.91
  5072.6  298.22  5085.7  297.93  5133.6  296.63  5148.5  297.28  5183.8  297.47
  5253.9  299.85  5277.1  299.06  5374.2  299.38  5404.2   300.6  5584.6  302.09
  6015.4  309.27  6045.5  308.42  6065.5  309.27  6125.6  308.45  6135.2  309.29
#Mann= 7 ,-1 , 0
  4369.3     .11       0  4819.8     .15       0  4961.4     .09       0
  5021.7     .15       0  5085.7     .11       0  5148.5     .15       0
  5277.1     .17       0
Bank Sta=4961.4,5021.7
XS Rating Curve= 0 ,0
Exp/Cntr=0.3,0.1

Type RM Length L Ch R = 1 ,16282   ,375,375,375
BEGIN DESCRIPTION:
MOCK BRANCH 28.0
END DESCRIPTION:
XS GIS Cut Line= 3
       3764017.9     10263861.08      3763115.95     10263772.17
      3762567.81     10263461.05
#Sta/Elev= 30
  3862.6  314.49    3943  313.82  4083.7  308.98  4204.3   306.6  4219.4  305.39
    4355  301.98  4535.9  298.09  4664.1  296.88  4725.5  297.21  4746.9   298.6
  4798.5  297.44  4825.9  295.83  4835.7  296.72    4885  297.25  4922.5  296.43
  4928.3  295.13  4944.1  295.35    4960  297.01  4973.7  296.02  4981.7  291.89
  4985.7   287.8  4996.7  289.29  5003.3  293.78    5009  294.08  5019.2  296.89
  5054.2  298.67  5062.4  299.93  5068.2  299.35  5151.5  301.88  5399.2  310.71
#Mann= 5 ,-1 , 0
  3862.6     .11       0  4664.1     .15       0    4960     .09       0
  5019.2     .15       0  5151.5     .17       0
Bank Sta=4960,5019.2
XS Rating Curve= 0 ,0
Exp/Cntr=0.3,0.1

Type RM Length L Ch R = 1 ,15907   ,539,539,539
BEGIN DESCRIPTION:
MOCK BRANCH 27.0
END DESCRIPTION:
XS GIS Cut Line= 3
      3763876.37      10263768.7      3763179.09     10263445.83
      3762674.97     10263161.05
#Sta/Elev= 30
  4231.6  311.62  4373.2  308.11  4425.5   307.2    4454  307.48  4545.6  303.53
  4574.1  303.25  4717.1  298.23    4740  298.27  4808.8     296  4849.2  296.01
  4928.9  294.82  4946.3  293.73  4980.2  296.11  4990.3  293.49  4997.6  288.33
  4997.7  287.13    4998  286.63  5003.6  287.13  5019.2  293.53    5025  295.13
  5035.2  295.78  5040.9  295.49  5070.3  297.27  5100.1  296.37  5143.4  296.54
  5202.6  298.52  5231.1  298.48  5374.1  304.73  5541.2  309.62    5579  309.79
#Mann= 6 ,-1 , 0
  4231.6     .11       0  4849.2     .15       0  4980.2     .09       0
  5035.2     .12       0  5040.9     .15       0  5374.1     .17       0
Bank Sta=4980.2,5035.2
XS Rating Curve= 0 ,0
Exp/Cntr=0.3,0.1

Type RM Length L Ch R = 1 ,15368   ,515,515,515
BEGIN DESCRIPTION:
MOCK BRANCH 26.0
END DESCRIPTION:
XS GIS Cut Line= 3
       3764122.9      10263268.7      3763338.17     10263049.95
      3762685.37     10263025.64
#Sta/Elev= 30
  4145.1  310.29  4170.2  310.04  4370.3  307.23  4482.5  306.34  4488.9  305.14
  4503.3  305.59  4562.5  303.51  4586.4  304.04  4617.5  302.11  4697.4  300.18
  4822.6  294.08  4835.5  294.67  4856.3  293.61  4896.2  295.46  4908.2  293.91
  4928.9  289.19  4940.7  294.35  4962.4  294.75  4990.1  291.48  5008.4  285.21
  5011.9  285.21  5030.1  293.46  5064.5  294.42  5090.2  295.97  5120.2  295.81
  5192.4  298.04  5240.3  298.92  5460.4   308.6  5550.5  310.34    5613  309.93
#Mann= 7 ,-1 , 0
  4145.1     .17       0  4170.2     .11       0  4370.3     .17       0
  4697.4     .15       0  4962.4     .09       0  5064.5     .15       0
  5192.4     .17       0
Bank Sta=4962.4,5064.5
XS Rating Curve= 0 ,0
Exp/Cntr=0.3,0.1

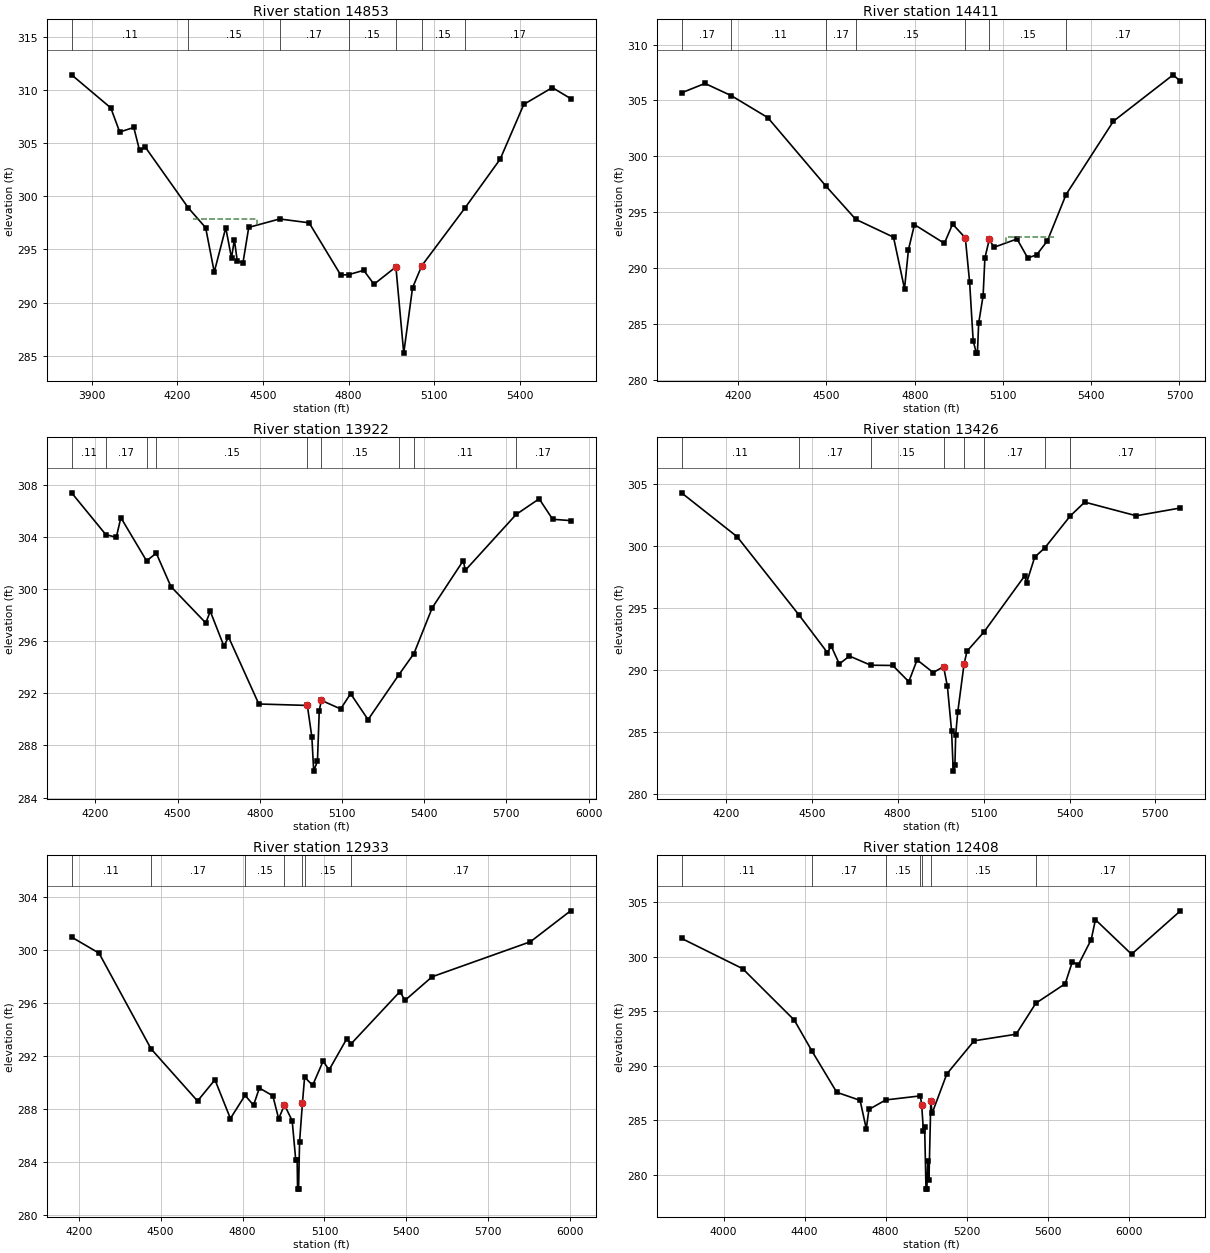
Type RM Length L Ch R = 1 ,14853   ,442,442,442
BEGIN DESCRIPTION:
MOCK BRANCH 25.0
END DESCRIPTION:
XS GIS Cut Line= 3
      3764404.15     10262536.06      3763355.53     10262664.53
      3762716.68     10262931.88
#Sta/Elev= 30
  3829.2  311.42  3966.5  308.31  3997.8  306.04  4047.1  306.47  4067.3  304.32
  4087.4  304.62  4238.1  298.91    4299  297.04  4329.2  292.87  4369.5  297.04
  4389.7  294.18  4399.7  295.91  4409.9   293.9    4430  293.76  4450.1  297.07
  4558.3  297.86  4661.7   297.5  4772.5  292.59  4800.2  292.62  4853.1  293.03
  4889.1  291.72  4965.9  293.35  4993.4  285.24  5024.3  291.39  5056.6  293.46
  5207.9  298.89  5331.5  303.49  5414.3  308.64  5514.3  310.22  5578.2  309.19
#Mann= 7 ,-1 , 0
  3829.2     .11       0  4238.1     .15       0  4558.3     .17       0
  4800.2     .15       0  4965.9     .09       0  5056.6     .15       0
  5207.9     .17       0
#XS Ineff= 1 ,-1
    4253  4480.3  297.82
Permanent Ineff=
       F
Bank Sta=4965.9,5056.6
XS Rating Curve= 0 ,0
Exp/Cntr=0.3,0.1

Type RM Length L Ch R = 1 ,14411   ,489,489,489
BEGIN DESCRIPTION:
MOCK BRANCH 24.0
END DESCRIPTION:
XS GIS Cut Line= 3
      3764206.27     10262147.16       3763230.3     10262328.63
      3762636.89     10262706.13
#Sta/Elev= 30
  4007.3  305.68  4087.1  306.52    4177  305.42  4300.7  303.46  4498.2  297.34
  4599.4  294.37  4727.9  292.77  4765.3  288.16  4778.7  291.65  4799.1  293.89
  4900.8  292.22  4928.8  293.94    4972  292.71  4986.6  288.74  4998.7   283.5
  5009.6   282.4  5013.1   282.4  5017.3  285.07  5032.5  287.54  5038.5   290.9
  5053.7   292.6  5068.9  291.86  5147.7  292.61  5184.1  290.91  5214.6  291.19
    5251  292.45  5314.4  296.58  5475.3  303.14  5678.5  307.29  5703.3   306.7
#Mann= 7 ,-1 , 0
  4007.3     .17       0    4177     .11       0  4498.2     .17       0
  4599.4     .15       0    4972     .09       0  5053.7     .15       0
  5314.4     .17       0
#XS Ineff= 2 ,-1
    4590  4928.8  293.94  5111.3    5275  292.81
Permanent Ineff=
       F       F
Bank Sta=4972,5053.7
XS Rating Curve= 0 ,0
Exp/Cntr=0.3,0.1

Type RM Length L Ch R = 1 ,13922   ,496,496,496
BEGIN DESCRIPTION:
MOCK BRANCH 23.0
END DESCRIPTION:
XS GIS Cut Line= 3
      3763917.83     10261611.08      3763130.14     10262018.89
      3762529.14     10262733.98
#Sta/Elev= 30
    4113  307.38    4238  304.17  4276.2  303.97  4292.7  305.48  4386.6  302.16
    4422  302.75  4475.4  300.19  4602.6   297.4  4619.1  298.29    4669  295.61
  4685.5  296.33  4796.2  291.18  4973.3  291.07  4989.8  288.66  4996.6  286.03
  5010.3   286.8  5016.9  290.68  5024.7  291.46  5094.9   290.8  5131.3  291.97
    5195  289.98  5306.3  293.39  5362.4  295.05  5429.2  298.56  5542.4  302.18
  5550.1  301.44  5735.4  305.72  5819.4  306.92  5868.8  305.35  5934.1  305.25
#Mann= 9 ,-1 , 0
    4113     .11       0    4238     .17       0  4386.6     .11       0
    4422     .15       0  4973.3     .09       0  5024.7     .15       0
  5306.3     .17       0  5362.4     .11       0  5735.4     .17       0
Bank Sta=4973.3,5024.7
XS Rating Curve= 0 ,0
Exp/Cntr=0.3,0.1

Type RM Length L Ch R = 1 ,13426   ,493,493,493
BEGIN DESCRIPTION:
MOCK BRANCH 22.0
END DESCRIPTION:
XS GIS Cut Line= 3
      3763428.44     10261088.16      3762843.44     10261842.38
      3762497.91     10262549.92
#Sta/Elev= 30
  4045.5  304.27  4239.7  300.73  4456.3   294.4  4554.7  291.39  4568.1  291.91
  4596.4  290.47  4631.7  291.11  4706.1  290.37  4782.9  290.35    4839  289.04
  4867.9   290.8  4924.1  289.78  4960.4  290.25  4973.8  288.66  4988.3  285.08
  4994.2  281.83    5000  282.33  5002.7  284.77  5009.7  286.56  5031.9  290.47
  5042.2   291.5  5101.7  293.06  5243.4  297.57  5250.5  297.03  5278.6  299.09
  5313.8  299.83  5402.8  302.41  5453.2  303.52  5632.9  302.42  5787.4  303.05
#Mann= 8 ,-1 , 0
  4045.5     .11       0  4456.3     .17       0  4706.1     .15       0
  4960.4     .09       0  5031.9     .15       0  5101.7     .17       0
  5313.8     .11       0  5402.8     .17       0
Bank Sta=4960.4,5031.9
XS Rating Curve= 0 ,0
Exp/Cntr=0.3,0.1

Type RM Length L Ch R = 1 ,12933   ,525,525,525
BEGIN DESCRIPTION:
MOCK BRANCH 21.0
END DESCRIPTION:
XS GIS Cut Line= 4
      3763223.56     10261004.84      3762634.23     10261583.17
      3762452.76     10262022.17      3762452.76     10262548.04
#Sta/Elev= 30
  4174.3  300.97  4274.7  299.76  4465.1  292.55  4635.3  288.62    4699  290.22
  4755.6   287.3  4809.3  289.05  4840.4   288.3  4861.6   289.6    4911  289.01
  4932.3  287.28  4953.5  288.33  4981.8  287.13  4994.9  284.15    5000  284.15
  5001.5  281.98  5005.2  281.98  5008.8  285.54  5019.4  288.49  5027.3  290.42
  5056.6   289.8  5095.1  291.63  5116.8  290.96  5181.6  293.31  5197.6  292.93
  5376.5  296.87  5394.5   296.2  5493.9  297.98  5853.9  300.62  6000.9  302.95
#Mann= 7 ,-1 , 0
  4174.3     .11       0  4465.1     .17       0  4809.3     .15       0
  4953.5     .09       0  5019.4     .12       0  5027.3     .15       0
  5197.6     .17       0
Bank Sta=4953.5,5019.4
XS Rating Curve= 0 ,0
Exp/Cntr=0.3,0.1

Type RM Length L Ch R = 1 ,12408   ,747,747,747
BEGIN DESCRIPTION:
MOCK BRANCH 20.0
END DESCRIPTION:
XS GIS Cut Line= 3
      3763299.94     10260706.22      3762195.81     10261404.11
      3761484.46     10262316.72
#Sta/Elev= 30
  3792.2  301.66  4093.9  298.89  4349.1  294.18  4435.9  291.36  4558.5  287.58
  4673.8  286.84  4704.4  284.23  4717.4  286.01  4800.5  286.88  4971.4  287.25
  4977.7  286.45  4986.7  284.02  4992.6  284.37  4999.2  278.72  5003.4  278.72
  5007.9  281.33  5013.8  279.57  5023.1  286.81  5029.1  285.65  5102.1  289.26
  5236.9  292.29    5444  292.89  5541.6  295.73  5686.5  297.51  5721.7  299.53
  5750.7  299.22  5814.9  301.55  5835.7  303.37    6014  300.21  6255.5  304.18
#Mann= 7 ,-1 , 0
  3792.2     .11       0  4435.9     .17       0  4800.5     .15       0
  4971.4     .12       0  4977.7     .09       0  5023.1     .15       0
  5541.6     .17       0
Bank Sta=4977.7,5023.1
XS Rating Curve= 0 ,0
Exp/Cntr=0.3,0.1

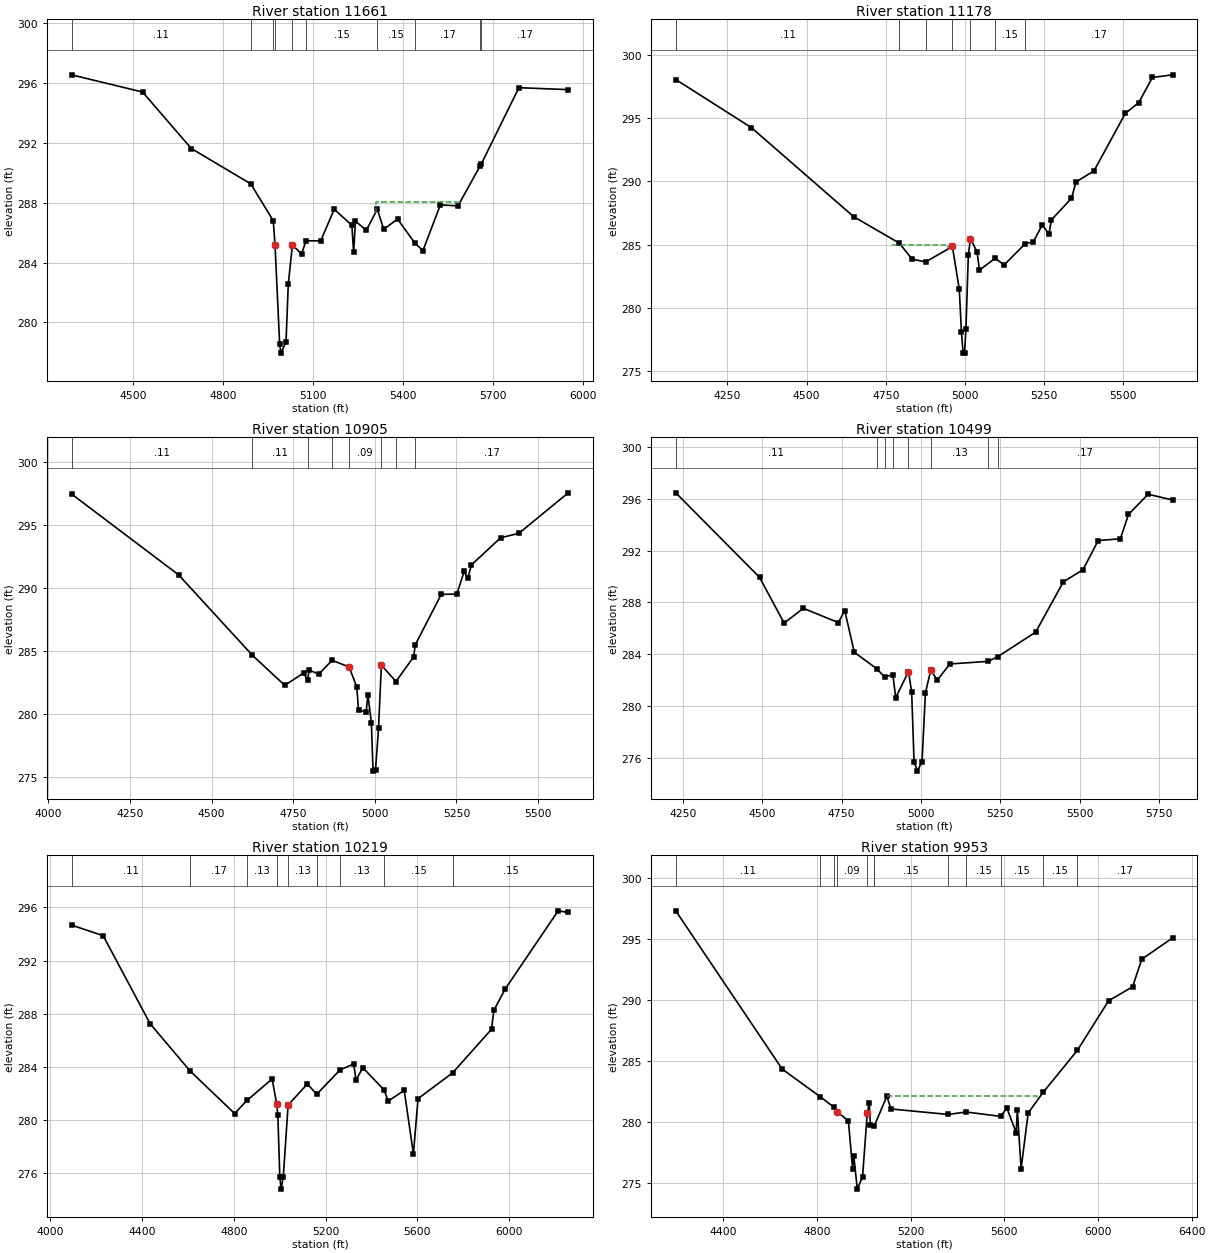
Type RM Length L Ch R = 1 ,11661   ,483,483,483
BEGIN DESCRIPTION:
Mapping XS 3e4c673d
END DESCRIPTION:
XS GIS Cut Line= 3
       3763001.4     10260674.94      3762404.14     10260883.28
      3761536.12     10261424.92
#Sta/Elev= 30
  4295.3  296.55  4532.1   295.4  4694.8  291.62  4892.8  289.26  4967.8  286.79
  4973.7  285.16    4989  278.57  4992.8  277.94  5010.3  278.69  5017.8  282.54
  5031.5  285.17  5062.2  284.57  5076.7  285.45  5125.9  285.45    5171  287.56
  5229.7  286.49  5235.6  284.68  5241.7  286.76  5278.1  286.16  5314.6  287.56
    5336  286.22  5381.9  286.91  5440.4  285.28  5466.8   284.8  5524.6  287.85
  5583.6  287.79  5656.4  290.43  5660.4  290.56  5786.5  295.69    5951  295.56
#Mann= 10 ,-1 , 0
  4295.3     .11       0  4892.8     .15       0  4967.8     .15       0
  4973.7     .09       0  5031.5     .15       0  5076.7     .15       0
  5314.6     .15       0  5440.4     .17       0  5656.4     .11       0
  5660.4     .17       0
#XS Ineff= 1 ,-1
  5308.7    5590  288.02
Permanent Ineff=
       F
Bank Sta=4973.7,5031.5
XS Rating Curve= 0 ,0
Exp/Cntr=0.3,0.1

Type RM Length L Ch R = 1 ,11178   ,273,273,273
BEGIN DESCRIPTION:
MOCK BRANCH 19.0
END DESCRIPTION:
XS GIS Cut Line= 3
      3762702.73      10260220.1      3762345.12      10260355.5
      3761453.22     10261136.35
#Sta/Elev= 30
  4087.3  298.05  4326.3  294.24  4649.1   287.2  4793.2  285.11  4833.2  283.85
  4875.9  283.63  4960.4  284.85  4982.2  281.45  4988.9  278.08  4994.3  276.42
  4998.7  276.42  5003.1  278.35  5010.7  284.16  5017.4  285.48  5038.2  284.42
  5045.8  282.98  5095.2  283.92  5123.6  283.39  5190.3  285.07  5215.7  285.21
  5244.2  286.57  5265.1  285.82  5272.7  286.95  5336.2  288.66  5350.5  289.95
  5407.4  290.83  5506.1  295.37  5548.8  296.23  5591.5  298.21  5655.1  298.42
#Mann= 7 ,-1 , 0
  4087.3     .11       0  4793.2     .15       0  4875.9     .15       0
  4960.4     .09       0  5017.4     .15       0  5095.2     .15       0
  5190.3     .17       0
#XS Ineff= 2 ,-1
    4770  4946.2     285
Permanent Ineff=
       F       F
Bank Sta=4960.4,5017.4
XS Rating Curve= 0 ,0
Exp/Cntr=0.3,0.1

Type RM Length L Ch R = 1 ,10905   ,406,406,406
BEGIN DESCRIPTION:
MOCK BRANCH 18.0
END DESCRIPTION:
XS GIS Cut Line= 3
      3762617.89     10260161.05      3761581.23     10260619.39
      3761407.74     10260966.37
#Sta/Elev= 30
  4071.1  297.46  4399.2  291.05  4625.4  284.67  4724.1   282.3  4781.8  283.27
  4793.9  282.73  4799.5  283.51  4828.2  283.18  4869.3  284.28  4921.4  283.75
  4944.7  282.18  4950.2  280.34  4973.5  280.18  4978.9  281.56  4989.6  279.29
  4994.6   275.5  5002.2   275.6  5011.4  278.88  5020.1   283.9  5064.8   282.6
  5118.7  284.54  5124.2  285.52  5203.7  289.51  5251.2  289.52  5273.6  291.32
  5284.7  290.77  5295.9  291.84  5385.4  293.99  5441.2  294.34  5592.5  297.55
#Mann= 8 ,-1 , 0
  4071.1     .11       0  4625.4     .11       0  4793.9     .15       0
  4869.3     .15       0  4921.4     .09       0  5020.1     .15       0
  5064.8     .17       0  5124.2     .17       0
Bank Sta=4921.4,5020.1
XS Rating Curve= 0 ,0
Exp/Cntr=0.3,0.1

Type RM Length L Ch R = 1 ,10499   ,280,280,280
BEGIN DESCRIPTION:
MOCK BRANCH 17.0
END DESCRIPTION:
XS GIS Cut Line= 3
      3762567.89     10260111.07      3761504.84     10260213.14
      3761338.18     10260681.86
#Sta/Elev= 30
  4227.4  296.45  4491.3  289.94    4569  286.41  4629.3  287.55  4739.8  286.45
  4759.9  287.38    4790  284.16  4860.3   282.9  4885.3  282.27  4911.5  282.42
  4920.6  280.66  4960.8  282.67  4970.8   281.1  4978.3  275.74  4988.7     275
  5003.5  275.74  5014.1  281.02  5031.1   282.8  5051.2  282.01  5091.4  283.26
  5211.9  283.46  5242.1  283.82  5361.5  285.71  5448.8  289.59  5510.5  290.52
  5558.5  292.77  5628.5  292.91    5654  294.78  5715.8  296.34  5792.8   295.9
#Mann= 8 ,-1 , 0
  4227.4     .11       0  4860.3     .12       0  4885.3     .12       0
  4911.5     .13       0  4960.8     .09       0  5031.1     .13       0
  5211.9     .15       0  5242.1     .17       0
Bank Sta=4960.8,5031.1
XS Rating Curve= 0 ,0
Exp/Cntr=0.3,0.1

Type RM Length L Ch R = 1 ,10219   ,266,266,266
BEGIN DESCRIPTION:
Mapping XS a686d1ef
END DESCRIPTION:
XS GIS Cut Line= 4
      3762532.63     10259799.94      3761730.53     10259970.09
      3761444.57     10260030.14      3760393.75     10260008.28
#Sta/Elev= 30
  4093.7  294.67  4231.5  293.87  4435.9  287.25    4610  283.69  4803.9  280.49
  4858.2  281.48  4967.5  283.09  4987.1  281.21  4992.2  280.37  5000.8  275.73
  5006.2   274.8    5016  275.73    5037  281.13  5120.8  282.71  5161.6  281.94
  5262.6  283.76  5322.6  284.22  5332.6  283.02  5362.6  283.93  5455.1  282.26
  5472.6  281.42  5542.6  282.23  5582.6  277.45  5602.7  281.61  5753.5  283.55
  5922.7  286.83  5932.7  288.25  5982.7  289.87  6212.8  295.74  6256.9  295.62
#Mann= 9 ,-1 , 0
  4093.7     .11       0    4610     .17       0  4858.2     .13       0
  4987.1     .09       0    5037     .13       0  5161.6     .13       0
  5262.6     .13       0  5455.1     .15       0  5753.5     .15       0
#XS Ineff= 3 ,-1
    4400  4967.5  283.09  5322.6    5810  284.22
Permanent Ineff=
       T       F       F
Bank Sta=4987.1,5037
XS Rating Curve= 0 ,0
Exp/Cntr=0.3,0.1

Type RM Length L Ch R = 1 ,9953    ,470,470,470
BEGIN DESCRIPTION:
MOCK BRANCH 16.0
END DESCRIPTION:
XS GIS Cut Line= 3
      3762517.83     10259661.07      3761722.58     10259772.31
      3760417.86     10259961.07
#Sta/Elev= 30
    4197  297.34  4651.4  284.33  4814.3  282.05  4873.5  281.18  4885.7  280.81
  4934.1  280.08  4952.1  276.15  4957.2  277.19  4972.2  274.46  4994.7  275.48
  5014.9  280.73  5023.1  281.52  5028.2  279.74  5045.2  279.67  5098.4   282.1
  5115.9  281.05  5360.2   280.6  5437.5   280.8    5584  280.44    5611  281.12
  5650.6  279.11  5655.7  280.95  5671.6  276.13    5702  280.72  5765.6  282.41
    5912  285.87  6045.5  289.95  6147.6  291.09    6187  293.36  6318.3  295.11
#Mann= 12 ,-1 , 0
    4197     .11       0  4814.3     .14       0  4873.5     .15       0
  4885.7     .09       0  5014.9     .13       0  5045.2     .15       0
  5045.2     .15       0  5360.2     .15       0  5437.5     .15       0
    5584     .15       0  5765.6     .15       0    5912     .17       0
#XS Ineff= 2 ,-1
  5098.4    5740   282.1
Permanent Ineff=
       T       F
Bank Sta=4885.7,5014.9
XS Rating Curve= 0 ,0
Exp/Cntr=0.3,0.1

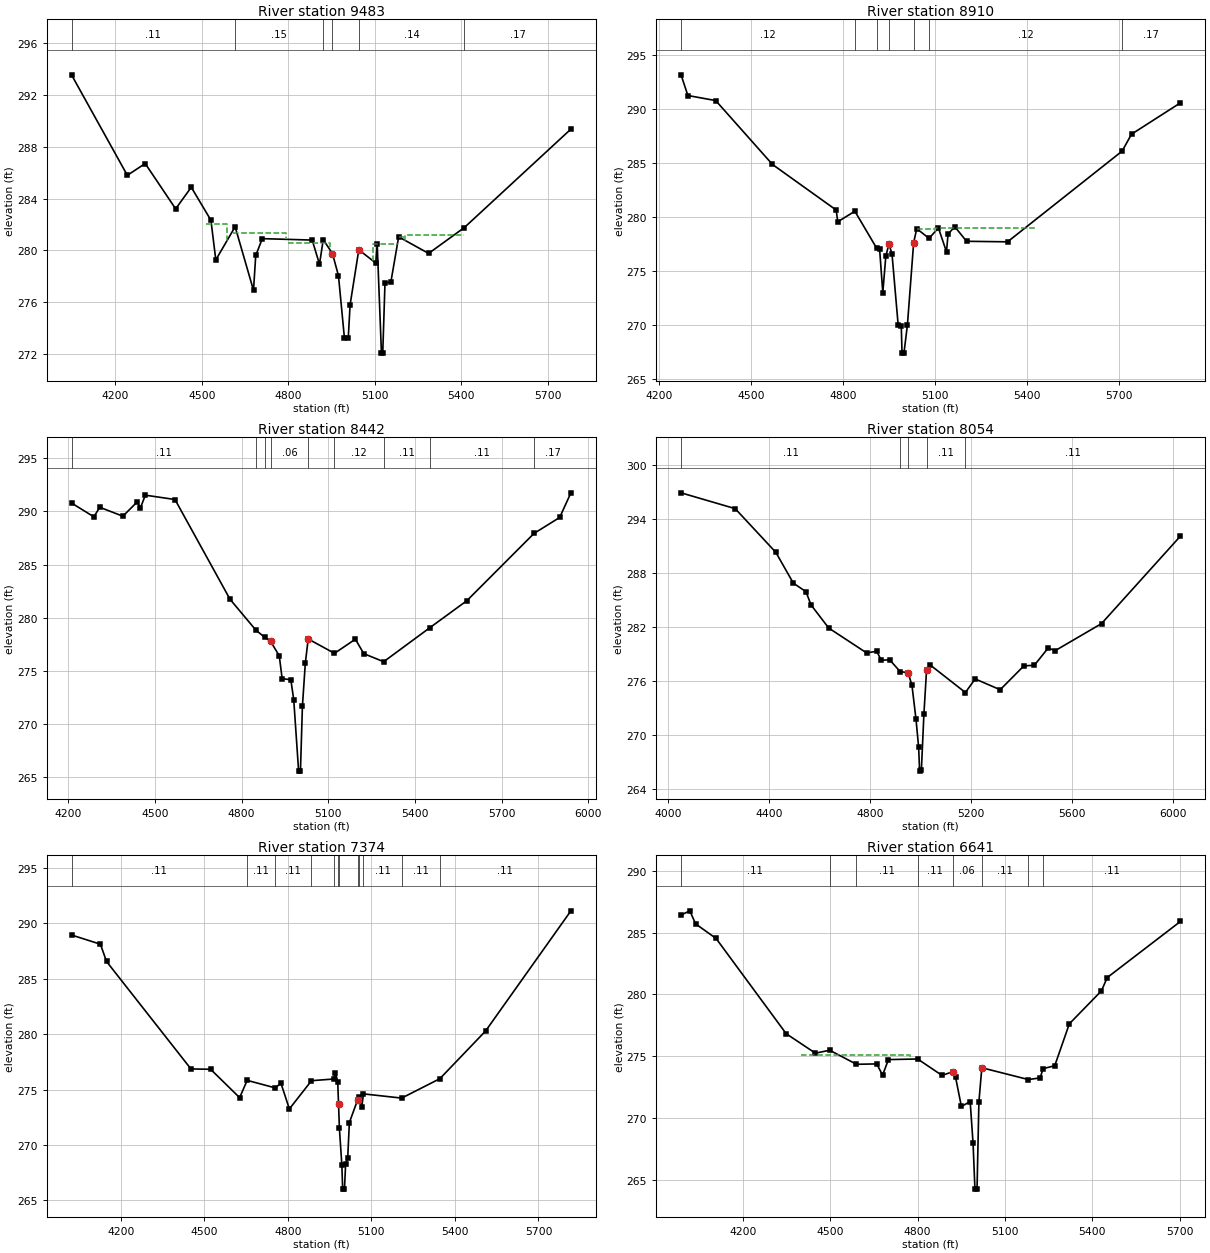
Type RM Length L Ch R = 1 ,9483    ,573,573,573
BEGIN DESCRIPTION:
MOCK BRANCH 15.0
END DESCRIPTION:
XS GIS Cut Line= 3
       3762267.9     10259261.05      3761407.62     10259574.25
      3760598.61     10259470.09
#Sta/Elev= 30
  4048.5  293.55    4242  285.79    4304   286.7  4409.5   283.2  4463.6  284.87
  4531.8  282.32  4548.7  279.26  4615.7  281.82  4679.4  276.91  4687.1   279.6
    4710   280.9  4882.8  280.79  4908.1  278.93  4921.2  280.82  4953.1  279.75
  4973.9  278.04  4994.5  273.24  5007.9  273.24  5014.2  275.79  5044.4  280.04
  5103.1  279.02  5108.2  280.46  5122.9  272.06  5127.4  272.06  5135.2   277.5
  5155.4  277.53  5182.6  281.04  5286.4  279.76  5410.5  281.76  5779.7  289.36
#Mann= 6 ,-1 , 0
  4048.5     .11       0  4615.7     .15       0  4921.2     .13       0
  4953.1     .09       0  5044.4     .14       0  5410.5     .17       0
#XS Ineff= 6 ,-1
    4515  4587.7  282.03    4610  4791.1  281.35    4800    4944  280.56
  5094.9    5181  280.49  5182.6    5200  281.04  5205.8    5410  281.22
Permanent Ineff=
       T       T       T       T       T       T
Bank Sta=4953.1,5044.4
XS Rating Curve= 0 ,0
Exp/Cntr=0.3,0.1

Type RM Length L Ch R = 1 ,8910    ,468,468,468
BEGIN DESCRIPTION:
MOCK BRANCH 14.0
END DESCRIPTION:
XS GIS Cut Line= 3
      3762089.89     10258994.39       3761207.1     10259119.39
      3760493.56      10259312.1
#Sta/Elev= 30
  4271.3  293.19  4293.6  291.27  4384.5   290.8  4569.9  284.87  4777.9  280.64
    4783  279.55  4838.9  280.53  4909.6  277.12  4919.7     277  4930.1  272.97
  4939.9  276.34    4950  277.48  4960.1  276.58  4980.3  269.96  4990.4   269.9
  4992.9  267.36  4999.2  267.36  5010.6  270.01  5030.8   277.6  5040.9  278.91
  5081.3  278.01  5111.6  278.99  5138.1  276.76  5143.1   278.4  5165.1   279.1
  5203.5  277.74  5337.5  277.69  5711.6  286.11  5742.2  287.68    5902  290.59
#Mann= 7 ,-1 , 0
  4271.3     .12       0  4838.9     .12       0  4909.6     .12       0
    4950     .07       0  5030.8     .12       0  5081.3     .12       0
  5711.6     .17       0
#XS Ineff= 2 ,-1
  5040.9    5100  278.91  5101.5    5430  278.97
Permanent Ineff=
       F       F
Bank Sta=4950,5030.8
XS Rating Curve= 0 ,0
Exp/Cntr=0.3,0.1

Type RM Length L Ch R = 1 ,8442    ,388,388,388
BEGIN DESCRIPTION:
MOCK BRANCH 13.0
END DESCRIPTION:
XS GIS Cut Line= 3
      3762035.23     10258726.16      3761092.51     10258799.08
      3760372.02      10259108.6
#Sta/Elev= 30
  4210.7  290.79  4288.3  289.49  4308.4  290.39  4388.6  289.55  4438.8  290.91
  4448.8  290.29  4466.4  291.53  4569.1  291.12  4759.7  281.73    4850   278.8
  4880.1  278.15  4900.1  277.77  4930.2  276.41  4940.3  274.25  4970.3  274.16
  4980.4  272.27  4997.3  265.55  5003.6  265.55  5010.5  271.69  5020.5  275.72
  5030.5  277.99  5121.5  276.64  5193.9  277.97  5222.9  276.61  5291.9  275.85
  5451.2  279.04  5579.8  281.59  5812.7  287.93  5901.4  289.43  5940.4  291.75
#Mann= 9 ,-1 , 0
  4210.7     .11       0    4850     .12       0  4880.1     .12       0
  4900.1     .06       0  5030.5     .12       0  5121.5     .12       0
  5291.9     .11       0  5451.2     .11       0  5812.7     .17       0
#XS Ineff= 1 ,-1
  5030.5    5450  277.99
Permanent Ineff=
       F
Bank Sta=4900.1,5030.5
XS Rating Curve= 0 ,0
Exp/Cntr=0.3,0.1

Type RM Length L Ch R = 1 ,8054    ,680,680,680
BEGIN DESCRIPTION:
MOCK BRANCH 12.0
END DESCRIPTION:
XS GIS Cut Line= 3
      3762082.05     10258421.48      3761287.82     10258452.72
      3760152.64     10258783.39
#Sta/Elev= 30
  4051.4  296.93  4265.8  295.17  4426.8  290.31  4495.9  286.89    4546  285.94
    4566  284.47    4636   281.9  4786.2  279.13  4826.2  279.32  4843.7  278.32
  4877.5  278.36  4919.1  277.05  4950.4  276.94  4965.7  275.51  4981.6  271.77
    4992  268.66    4996  265.99  5002.9  266.08  5012.9  272.31  5023.3  277.18
  5037.9  277.79  5177.2  274.73  5215.9  276.24  5314.9  275.04  5408.7  277.69
  5450.3  277.76  5504.7  279.67    5533  279.39  5716.1  282.39  6028.6  292.12
#Mann= 5 ,-1 , 0
  4051.4     .11       0  4919.1     .11       0  4950.4     .06       0
  5023.3     .11       0  5177.2     .11       0
#XS Ineff= 1 ,-1
  5037.9    5470  277.79
Permanent Ineff=
       F
Bank Sta=4950.4,5023.3
XS Rating Curve= 0 ,0
Exp/Cntr=0.3,0.1

Type RM Length L Ch R = 1 ,7374    ,733,733,733
BEGIN DESCRIPTION:
Mapping XS 6e29d782
END DESCRIPTION:
XS GIS Cut Line= 3
      3761652.43     10257970.95      3760795.64     10258093.35
      3760032.74     10258621.91
#Sta/Elev= 30
    4023  288.94  4126.8  288.11  4148.8  286.55  4451.9  276.86  4522.6  276.83
  4626.8  274.27  4653.9  275.83  4754.9  275.15  4775.1  275.58  4805.4  273.25
  4884.9   275.8  4964.2  275.95    4971   276.5  4979.1  275.72    4982 273.685
  4985.1  271.51  4993.9   268.2  4996.8  266.02  5003.3  266.02  5007.5  268.28
  5014.9  268.79  5020.9  272.02  5050.7  274.08  5056.8  274.31  5065.5  273.45
  5071.6  274.61  5208.8  274.23  5345.9  275.98  5510.1  280.28  5816.6  291.12
#Mann= 12 ,-1 , 0
    4023     .11       0  4653.9     .11       0  4754.9     .11       0
  4884.9     .11       0  4964.2     .11       0  4979.1     .11       0
    4982     .06       0  5050.7     .11       0  5056.8     .11       0
  5071.6     .11       0  5208.8     .11       0  5345.9     .11       0
#XS Ineff= 2 ,-1
    4440  4522.6  276.83    4523    4971   276.5
Permanent Ineff=
       F       F
Bank Sta=4982,5050.7
XS Rating Curve= 0 ,0
Exp/Cntr=0.3,0.1

Type RM Length L Ch R = 1 ,6641    ,461,461,461
BEGIN DESCRIPTION:
MOCK BRANCH 11.0
END DESCRIPTION:
XS GIS Cut Line= 3
      3761537.84     10257809.49       3760712.3     10257869.39
      3759826.91     10257825.12
#Sta/Elev= 30
  3987.9  286.44    4018  286.78    4038  285.72  4108.2  284.54  4348.8  276.82
  4449.1  275.24  4498.1  275.48  4590.1  274.34  4659.6  274.37  4679.7  273.46
  4699.8  274.72    4800  274.77  4883.6  273.44  4920.2  273.73  4930.2  273.29
  4950.2  270.92  4980.3  271.32  4990.3  267.93  4996.7  264.22  5003.9  264.22
  5010.3  271.28  5020.3  274.06  5180.5   273.1  5220.6  273.24  5230.6  273.99
  5270.6  274.22  5320.7  277.62  5430.8  280.29  5450.8  281.37  5702.1  285.92
#Mann= 8 ,-1 , 0
  3987.9     .11       0  4498.1     .15       0  4590.1     .11       0
    4800     .11       0  4920.2     .06       0  5020.3     .11       0
  5180.5     .11       0  5230.6     .11       0
#XS Ineff= 1 ,-1
    4400  4772.3  275.06
Permanent Ineff=
       F
Bank Sta=4920.2,5020.3
XS Rating Curve= 0 ,0
Exp/Cntr=0.3,0.1