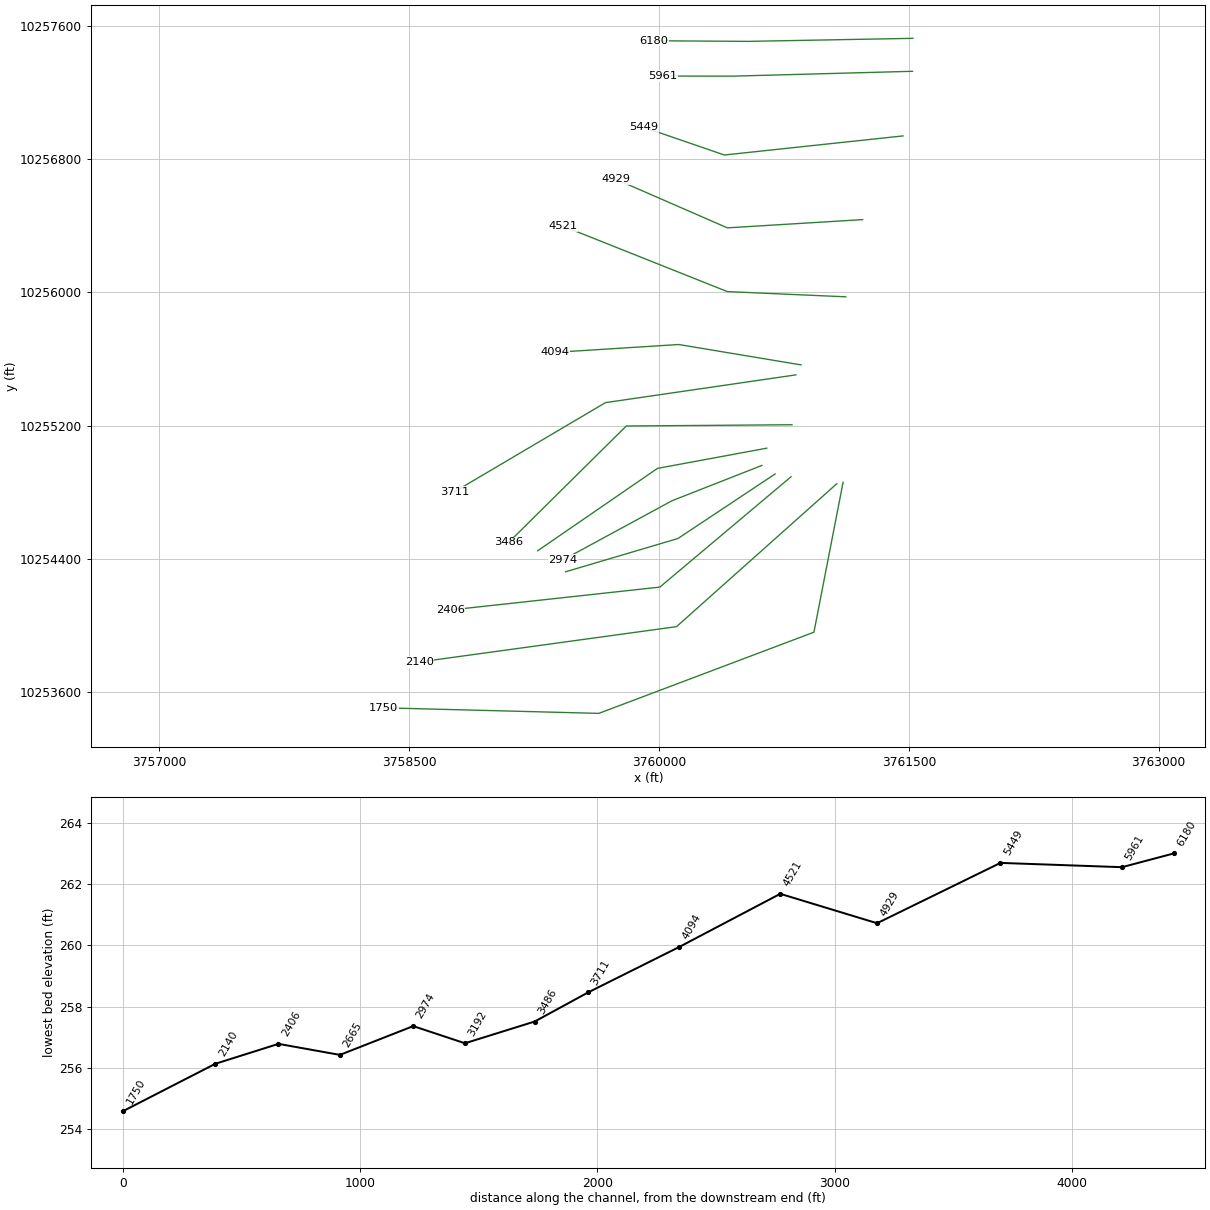
HEC-RAS study MOCK BRANCH.prj: MOCK BRANCH Base Level Engineering

--- MOCK BRANCH.g01 (geometry) --- (continued)

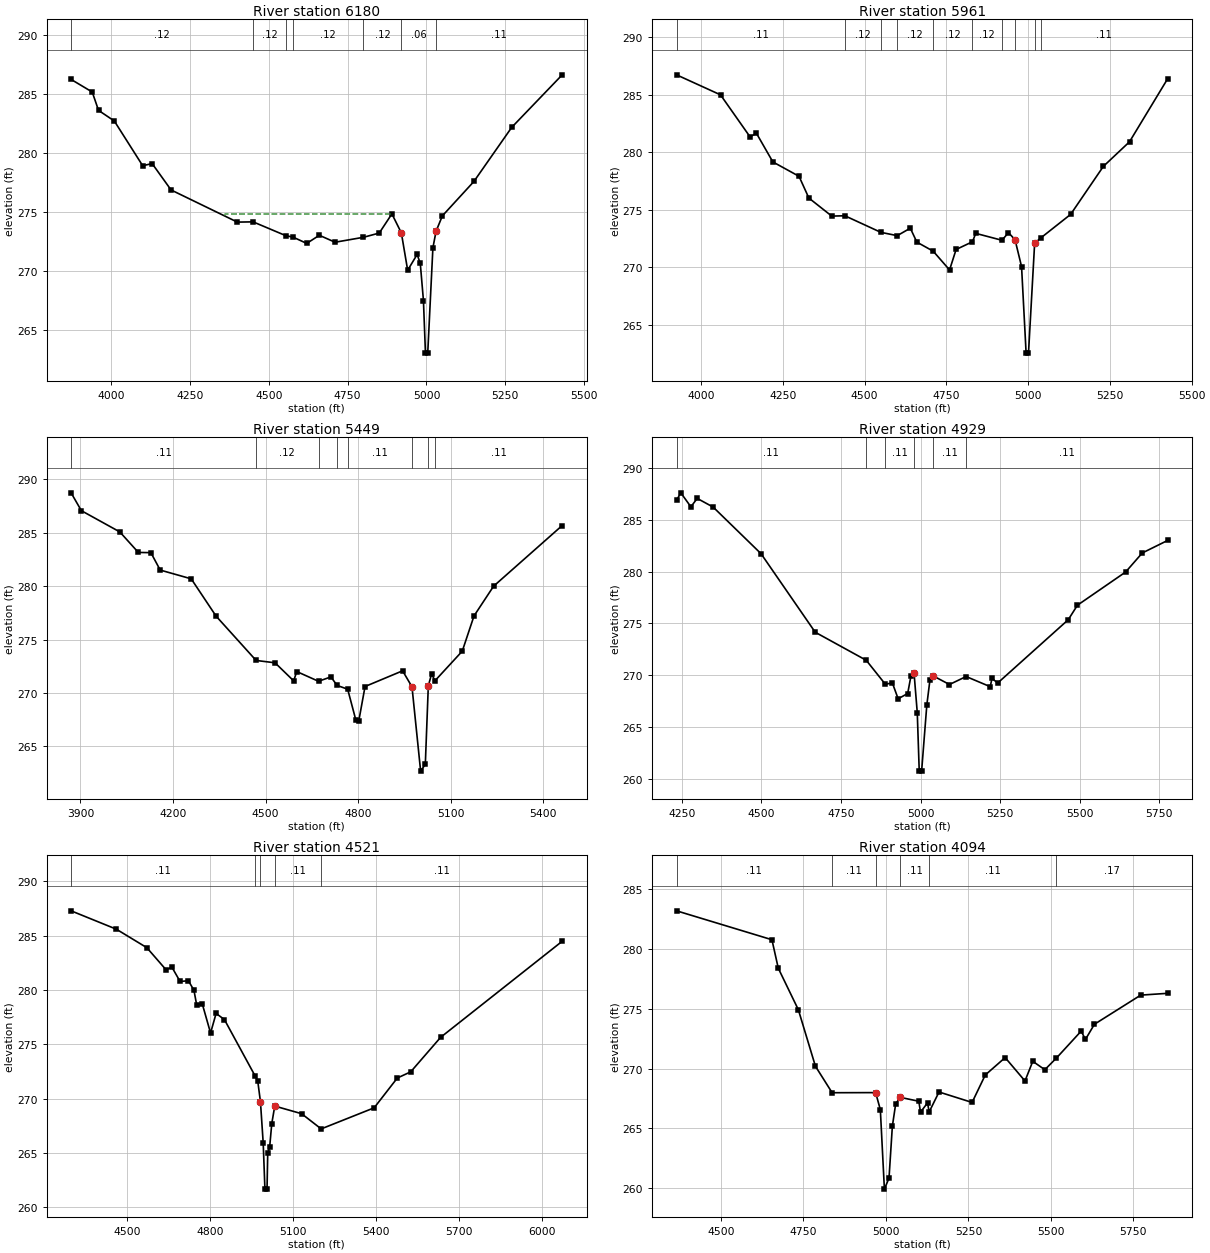
Type RM Length L Ch R = 1 ,6180    ,219,219,219
BEGIN DESCRIPTION:
MOCK BRANCH 10.0
END DESCRIPTION:
XS GIS Cut Line= 3
      3761524.84     10257525.64      3760535.22     10257507.41
      3759967.81     10257511.07
#Sta/Elev= 30
  3873.1  286.25  3940.1  285.18  3960.1  283.62  4010.1  282.72  4100.1  278.92
  4130.1   279.1  4190.1  276.86  4400.2  274.13  4450.2  274.15  4553.7  272.98
  4577.2  272.85  4620.2  272.32  4660.2  273.01  4710.2  272.42  4800.2  272.84
  4850.2   273.2  4890.3  274.83  4920.3  273.21  4940.3  270.04  4970.3  271.38
  4980.3  270.62  4990.3  267.47  4996.7     263  5003.9     263  5020.3  271.94
  5030.3  273.35  5050.3  274.66  5150.3  277.58  5270.3  282.18  5430.3  286.64
#Mann= 7 ,-1 , 0
  3873.1     .12       0  4450.2     .12       0  4553.7     .15       0
  4577.2     .12       0  4800.2     .12       0  4920.3     .06       0
  5030.3     .11       0
#XS Ineff= 1 ,-1
    4360  4890.3  274.83
Permanent Ineff=
       F
Bank Sta=4920.3,5030.3
XS Rating Curve= 0 ,0
Exp/Cntr=0.3,0.1

Type RM Length L Ch R = 1 ,5961    ,512,512,512
BEGIN DESCRIPTION:
MOCK BRANCH 9.0
END DESCRIPTION:
XS GIS Cut Line= 3
      3761522.16     10257327.72      3760447.85     10257298.76
      3760021.25     10257299.08
#Sta/Elev= 30
  3925.3  286.74  4059.7     285  4149.7  281.36  4169.7  281.65  4219.7  279.17
  4299.7  277.92  4329.8  276.03  4399.8  274.46  4439.8  274.49  4549.8  273.05
  4599.9  272.76  4639.9  273.41  4659.9   272.2  4709.9  271.41  4759.9  269.78
  4779.9  271.56  4829.9  272.23  4839.9  272.96    4920  272.36    4940  273.02
    4960  272.41    4980  270.07  4993.9  262.55  5001.2  262.55    5020  272.11
    5040  272.59    5130  274.61    5230  278.78    5310  280.92  5426.6   286.4
#Mann= 10 ,-1 , 0
  3925.3     .11       0  4439.8     .12       0  4549.8     .12       0
  4599.9     .12       0  4709.9     .12       0  4829.9     .12       0
    4920     .11       0    4960     .06       0    5020     .11       0
    5040     .11       0
#XS Ineff= 1 ,-1
    4640  4839.9  272.96
Permanent Ineff=
       F
Bank Sta=4960,5020
XS Rating Curve= 0 ,0
Exp/Cntr=0.3,0.1

Type RM Length L Ch R = 1 ,5449    ,520,520,520
BEGIN DESCRIPTION:
MOCK BRANCH 8.0
END DESCRIPTION:
XS GIS Cut Line= 3
      3761464.88      10256939.7      3760391.99     10256825.12
      3759907.65     10256991.78
#Sta/Elev= 30
  3869.8  288.74    3903  287.07  4027.7  285.08  4087.7  283.16  4128.3  283.14
  4158.5  281.51    4259  280.69  4339.5   277.2  4469.2  273.05  4530.6  272.83
  4590.9  271.14    4601  272.01  4671.4   271.1  4711.6  271.51  4731.7  270.71
  4765.9  270.36    4792  267.51  4802.1  267.42  4822.2  270.61  4943.9  272.08
  4974.3  270.58  5002.3  262.69  5017.5  263.33  5027.2  270.67  5037.8  271.79
  5048.8  271.15  5137.2  273.92  5175.3  277.22  5238.7     280    5461  285.68
#Mann= 8 ,-1 , 0
  3869.8     .11       0  4469.2     .12       0  4671.4     .12       0
  4731.7     .12       0  4765.9     .11       0  4974.3     .06       0
  5027.2     .11       0  5048.8     .11       0
#XS Ineff= 1 ,-1
    4520  4943.9  272.08
Permanent Ineff=
       F
Bank Sta=4974.3,5027.2
XS Rating Curve= 0 ,0
Exp/Cntr=0.3,0.1

Type RM Length L Ch R = 1 ,4929    ,408,408,408
BEGIN DESCRIPTION:
MOCK BRANCH 7.0
END DESCRIPTION:
XS GIS Cut Line= 3
      3761222.72      10256437.1      3760410.22     10256387.62
      3759741.93     10256678.86
#Sta/Elev= 30
  4233.4  286.89  4246.8  287.61  4278.4  286.26  4298.4  287.07  4348.5  286.23
  4498.8  281.73  4669.1  274.14  4829.4  271.43  4889.5  269.11  4911.4  269.25
  4929.6  267.71  4959.6  268.22  4969.6  269.87  4979.7  270.16  4989.7  266.37
  4995.9  260.72  5003.4  260.72  5019.7   267.1  5029.7  269.57  5039.8  269.92
  5090.9  269.09  5143.2  269.86  5218.9  268.88  5224.5  269.68  5242.3  269.23
  5464.1  275.35  5492.9  276.75  5644.4  279.96  5696.7   281.8  5776.4  283.01
#Mann= 6 ,-1 , 0
  4233.4     .11       0  4829.4     .11       0  4889.5     .11       0
  4979.7     .06       0  5039.8     .11       0  5143.2     .11       0
Bank Sta=4979.7,5039.8
XS Rating Curve= 0 ,0
Exp/Cntr=0.3,0.1

Type RM Length L Ch R = 1 ,4521    ,427,427,427
BEGIN DESCRIPTION:
MOCK BRANCH 6.0
END DESCRIPTION:
XS GIS Cut Line= 3
      3761121.16     10255973.56      3760410.22     10256004.81
       3759423.2     10256398.05
#Sta/Elev= 30
  4298.4  287.28  4461.9  285.59    4572  283.89    4642  281.84  4662.1  282.12
  4692.1  280.78  4722.1  280.85  4742.1  279.98  4752.1  278.62  4772.2  278.73
  4802.2  276.04  4822.2  277.84  4852.2  277.28  4962.3  272.13  4972.4  271.67
  4982.4  269.73  4992.4  265.91  4998.6  261.68  5006.2  261.68  5008.7  264.96
  5015.7  265.55  5023.3   267.7  5034.1  269.32    5131  268.62  5201.8  267.22
  5393.2  269.16  5476.8   271.9  5525.3  272.47  5633.2  275.64  6072.5  284.48
#Mann= 5 ,-1 , 0
  4298.4     .11       0  4962.3     .11       0  4982.4     .06       0
  5034.1     .11       0  5201.8     .11       0
Bank Sta=4982.4,5034.1
XS Rating Curve= 0 ,0
Exp/Cntr=0.3,0.1

Type RM Length L Ch R = 1 ,4094    ,383,383,383
BEGIN DESCRIPTION:
MOCK BRANCH 5.0
END DESCRIPTION:
XS GIS Cut Line= 3
      3760852.88     10255564.71      3760118.55      10255687.1
      3759376.39     10255640.23
#Sta/Elev= 30
  4365.6  283.15  4654.6  280.74  4673.9  278.36  4734.7   274.9  4786.4  270.19
    4837  267.98  4968.8  267.99  4983.1  266.57  4995.4  259.94  5009.4  260.86
  5019.5  265.18  5029.7  267.07  5043.9  267.59  5099.7  267.27  5104.8  266.36
  5126.1  267.13  5131.1  266.38  5160.9  268.04  5261.1  267.17  5301.1  269.46
  5361.3  270.91  5421.4  268.96    5445   270.6  5481.5   269.9  5516.6  270.87
  5591.7  273.12  5604.5  272.42  5631.8  273.69  5772.1  276.12  5853.7  276.27
#Mann= 6 ,-1 , 0
  4365.6     .11       0    4837     .11       0  4968.8     .06       0
  5043.9     .11       0  5131.1     .11       0  5516.6     .17       0
#XS Ineff= 1 ,-1
  5361.3    5570  270.91
Permanent Ineff=
       F
Bank Sta=4968.8,5043.9
XS Rating Curve= 0 ,0
Exp/Cntr=0.3,0.1

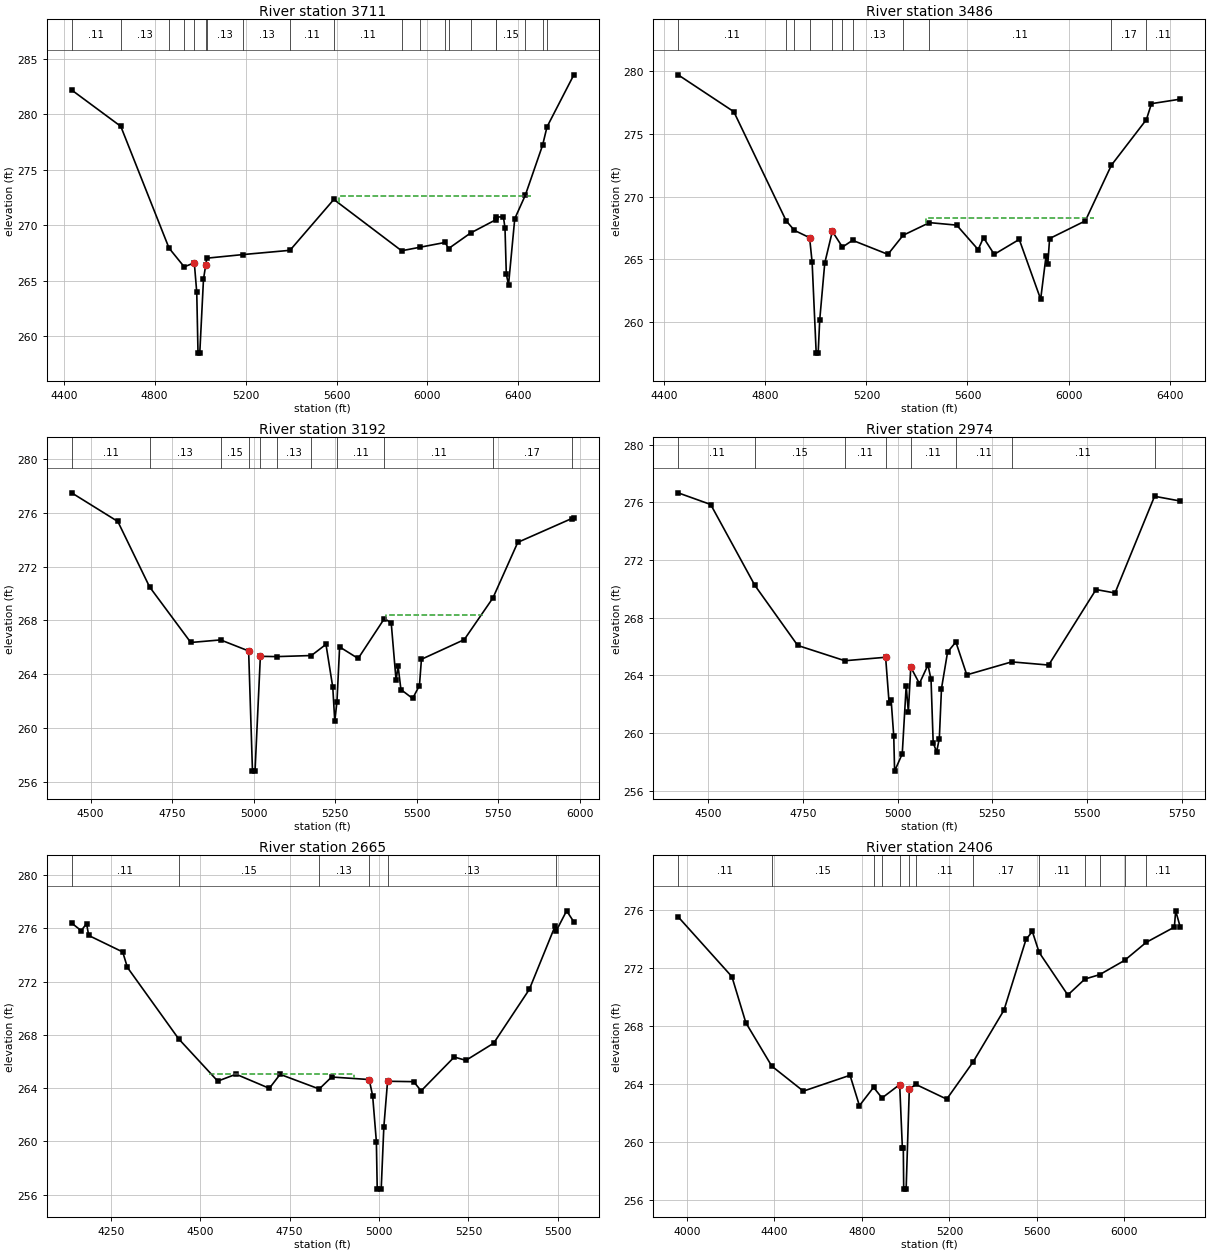
Type RM Length L Ch R = 1 ,3711    ,225,225,225
BEGIN DESCRIPTION:
MOCK BRANCH 4.0
END DESCRIPTION:
XS GIS Cut Line= 3
      3760821.69     10255504.81      3759678.45     10255338.14
      3758771.23     10254802.64
#Sta/Elev= 30
    4435  282.21  4651.1  278.93  4863.3  267.94    4930  266.25  4974.5  266.61
  4985.2  263.95  4990.8  258.46  4998.5  258.46  5014.9  265.14    5025  266.44
  5029.2  267.03  5190.3  267.36  5395.3  267.74  5588.1  272.33  5886.2   267.7
  5965.3  268.01  6077.4  268.45  6092.9   267.9  6189.5   269.3  6299.7  270.49
  6301.6  270.76  6334.2  270.74    6341  269.75  6346.8  265.57  6356.6  264.65
  6383.9  270.59  6430.3  272.71  6506.4  277.23  6525.8  278.88  6643.8  283.58
#Mann= 20 ,-1 , 0
    4435     .11       0  4651.1     .13       0  4863.3     .13       0
    4930     .13       0  4974.5     .07       0    5025     .13       0
  5029.2     .13       0  5190.3     .13       0  5395.3     .11       0
  5588.1     .11       0  5886.2     .17       0  5965.3     .11       0
  6077.4     .17       0  6092.9     .11       0  6189.5     .15       0
  6299.7     .11       0  6301.6     .15       0  6430.3     .17       0
  6506.4     .15       0  6525.8     .17       0
#XS Ineff= 1 ,-1
  5611.3    6455  272.63
Permanent Ineff=
       F
Bank Sta=4974.5,5025
XS Rating Curve= 0 ,0
Exp/Cntr=0.3,0.1

Type RM Length L Ch R = 1 ,3486    ,294,294,294
BEGIN DESCRIPTION:
Mapping XS f6998be0
END DESCRIPTION:
XS GIS Cut Line= 3
      3760798.26     10255205.33      3759803.41     10255197.83
      3759097.73     10254499.61
#Sta/Elev= 30
  4454.9  279.71  4675.3  276.77  4882.7  268.06  4915.3   267.3  4975.3  266.72
  4985.3  264.75  5001.4  257.51  5009.2  257.51  5015.3  260.15  5035.3   264.7
  5065.3  267.22  5105.3  265.97  5145.3  266.51  5285.3  265.39  5345.3  266.91
  5449.8  267.92  5557.5  267.72  5642.3  265.77  5663.6  266.72    5706  265.39
    5805  266.58  5889.8  261.81    5911  265.24  5918.1  264.61  5925.2  266.65
  6066.6  268.06  6169.7   272.5  6308.3  276.14  6328.3  277.41  6442.5  277.77
#Mann= 11 ,-1 , 0
  4454.9     .11       0  4882.7     .13       0  4915.3     .13       0
  4975.3     .08       0  5065.3     .13       0  5105.3     .13       0
  5145.3     .13       0  5345.3     .11       0  5449.8     .11       0
  6169.7     .17       0  6308.3     .11       0
#XS Ineff= 1 ,-1
  5435.3    6100  268.31
Permanent Ineff=
       T
Bank Sta=4975.3,5065.3
XS Rating Curve= 0 ,0
Exp/Cntr=0.3,0.1

Type RM Length L Ch R = 1 ,3192    ,218,218,218
BEGIN DESCRIPTION:
Mapping XS 89dd3a76
END DESCRIPTION:
XS GIS Cut Line= 3
      3760647.23     10255064.71      3759990.76     10254943.32
       3759271.2     10254448.62
#Sta/Elev= 30
  4441.6  277.48  4583.3  275.35  4680.7  270.49  4807.1  266.36  4898.6  266.55
  4984.6  265.73  4996.4   256.8  5004.2   256.8  5020.6  265.33  5071.5  265.31
  5177.2  265.39  5221.9  266.22  5242.8  263.03  5248.9   260.5  5255.6  261.96
  5263.8  266.03  5320.6  265.17  5401.2  268.14  5422.1  267.81    5437  263.54
  5443.1  264.61  5451.9  262.86  5487.8   262.2  5508.7  263.16  5514.8  265.11
  5646.1  266.57  5734.2  269.67  5810.4   273.8  5975.9  275.57  5982.4  275.63
#Mann= 11 ,-1 , 0
  4441.6     .11       0  4680.7     .13       0  4898.6     .15       0
  4984.6     .08       0  5020.6     .15       0  5071.5     .13       0
  5177.2     .13       0  5255.6     .11       0  5401.2     .11       0
  5734.2     .17       0  5975.9     .11       0
#XS Ineff= 1 ,-1
  5407.2    5705  268.37
Permanent Ineff=
       F
Bank Sta=4984.6,5020.6
XS Rating Curve= 0 ,0
Exp/Cntr=0.3,0.1

Type RM Length L Ch R = 1 ,2974    ,309,309,309
BEGIN DESCRIPTION:
MOCK BRANCH 3.0
END DESCRIPTION:
XS GIS Cut Line= 3
      3760617.88     10254961.08      3760078.47     10254749.28
       3759422.3     10254393.32
#Sta/Elev= 30
  4420.5  276.67  4506.5  275.86  4623.1  270.25  4736.3  266.08  4860.8  265.02
  4968.4  265.26  4977.6   262.1    4983  262.28  4989.9  259.77  4992.1  257.36
  5012.3  258.56  5022.7  263.27  5028.4  261.48  5034.8  264.57  5057.6  263.44
  5080.3  264.73  5088.3  263.72    5094  259.32  5103.1   258.7  5110.2  259.62
  5115.9  263.09    5132  265.62  5153.9  266.32  5182.7  264.04  5301.3  264.94
  5398.9  264.72    5524  269.96  5574.1  269.72  5678.5  276.43  5746.5   276.1
#Mann= 8 ,-1 , 0
  4420.5     .11       0  4623.1     .15       0  4860.8     .11       0
  4968.4     .06       0  5034.8     .11       0  5153.9     .11       0
  5301.3     .11       0  5678.5     .17       0
Bank Sta=4968.4,5034.8
XS Rating Curve= 0 ,0
Exp/Cntr=0.3,0.1

Type RM Length L Ch R = 1 ,2665    ,259,259,259
BEGIN DESCRIPTION:
Mapping XS 88b858fd
END DESCRIPTION:
XS GIS Cut Line= 3
      3760696.77     10254909.69      3760113.45      10254522.2
      3759438.45      10254322.2
#Sta/Elev= 30
  4140.4   276.4  4167.1  275.83  4182.1  276.36  4188.1  275.47  4283.2  274.23
  4296.3  273.07  4439.5  267.71  4548.9  264.53    4600  265.05  4693.2  263.99
  4723.3  265.04  4832.7  263.94  4867.4  264.84  4972.4  264.65  4982.1  263.43
  4992.5  259.99  4994.9  256.42    5006  256.42  5013.4  261.09  5023.8  264.52
  5096.8  264.49  5117.7   263.8  5210.3  266.34  5242.9  266.09  5320.5  267.38
  5420.2  271.42  5491.9  276.15  5495.6  275.82  5524.5  277.32  5544.7  276.49
#Mann= 6 ,-1 , 0
  4140.4     .11       0  4439.5     .15       0  4832.7     .13       0
  4972.4     .08       0  5023.8     .13       0  5495.6     .17       0
#XS Ineff= 1 ,-1
    4525  4928.7  265.05
Permanent Ineff=
       F
Bank Sta=4972.4,5023.8
XS Rating Curve= 0 ,0
Exp/Cntr=0.3,0.1

Type RM Length L Ch R = 1 ,2406    ,266,266,266
BEGIN DESCRIPTION:
Mapping XS 1c8d21b4
END DESCRIPTION:
XS GIS Cut Line= 3
       3760792.6     10254893.03      3760005.12     10254230.54
       3758746.8     10254093.04
#Sta/Elev= 30
  3960.2  275.51  4206.1  271.39  4269.8  268.22  4388.2  265.24  4532.5  263.52
  4745.8  264.61  4788.7  262.52  4853.3  263.78    4892  263.05  4972.7  263.97
    4985   259.6  4989.3   259.6  4991.1  256.78  5002.2  256.78  5016.7  263.67
  5046.9  263.98  5187.7  262.97  5307.9  265.52  5449.3  269.09  5549.9  273.95
  5578.9   274.5    5610  273.06    5741  270.13  5819.2  271.23  5886.5  271.53
  6000.3  272.51  6099.2  273.75    6228   274.8  6233.9  275.92  6255.1  274.79
#Mann= 13 ,-1 , 0
  3960.2     .11       0  4388.2     .15       0  4853.3     .11       0
    4892     .15       0  4972.7     .09       0  5016.7     .15       0
  5046.9     .11       0  5307.9     .17       0    5610     .11       0
  5819.2     .17       0  5886.5     .11       0  6000.3     .17       0
  6099.2     .11       0
Bank Sta=4972.7,5016.7
XS Rating Curve= 0 ,0
Exp/Cntr=0.3,0.1

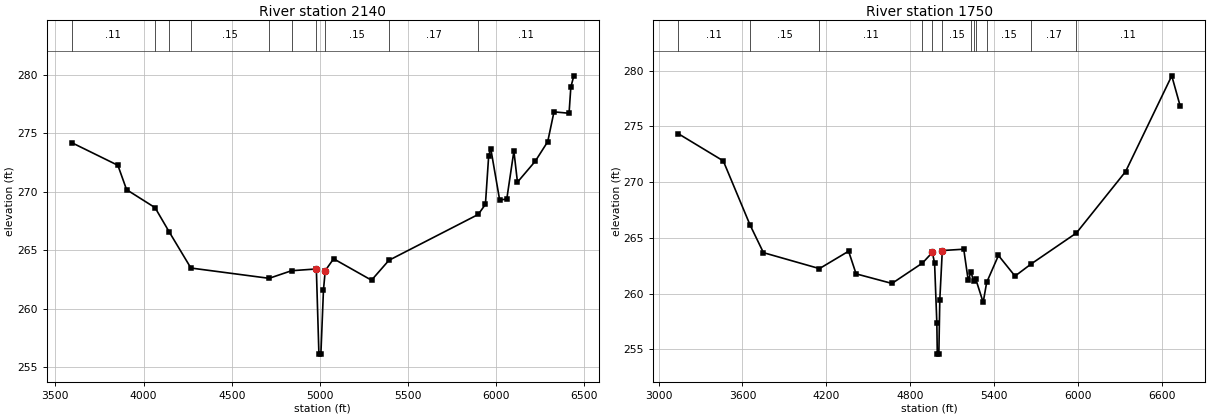
Type RM Length L Ch R = 1 ,2140    ,390,390,390
BEGIN DESCRIPTION:
MOCK BRANCH 2.0
END DESCRIPTION:
XS GIS Cut Line= 3
      3761067.61     10254851.36      3760105.12     10253993.04
      3758561.05     10253780.78
#Sta/Elev= 30
  3592.3  274.21  3854.5  272.27  3903.8  270.19  4065.4  268.65  4144.7   266.6
  4268.6  263.49  4712.2  262.61  4839.4  263.26  4980.1  263.41  4994.7  256.13
  5005.8  256.13  5020.5  261.62  5030.6  263.27    5078  264.28    5293  262.45
  5391.7  264.15  5898.1  268.07    5939  268.93  5957.6   273.1  5969.3   273.7
  6019.8   269.3  6060.2  269.39  6100.5  273.49  6120.7  270.83  6221.7  272.62
  6292.3  274.29  6327.9  276.84  6413.4  276.72  6423.5  278.96  6440.5  279.92
#Mann= 10 ,-1 , 0
  3592.3     .11       0  4065.4     .15       0  4144.7     .11       0
  4268.6     .15       0  4712.2     .11       0  4839.4     .15       0
  4980.1     .09       0  5030.6     .15       0  5391.7     .17       0
  5898.1     .11       0
Bank Sta=4980.1,5030.6
XS Rating Curve= 0 ,0
Exp/Cntr=0.3,0.1

Type RM Length L Ch R = 1 ,1750    ,0,0,0
BEGIN DESCRIPTION:
MOCK BRANCH 1.0
END DESCRIPTION:
XS GIS Cut Line= 4
      3761105.11     10254859.69      3760930.12      10253959.7
      3759638.45      10253472.2      3758346.82     10253505.54
#Sta/Elev= 30
  3140.1  274.36  3462.9  271.91  3653.7  266.18  3749.9  263.68  4150.3  262.25
  4358.6  263.81  4412.2  261.78  4668.6  260.92  4886.7  262.75  4957.2   263.7
  4973.3  262.74  4989.3   257.4  4992.6  254.58  5003.7  254.58  5010.6  259.46
  5028.4  263.87  5181.7  263.99  5213.7  261.19  5233.4  261.97  5251.6  261.13
  5268.1  261.29  5320.6  259.22  5345.5  261.01  5429.7  263.43  5548.2  261.58
  5664.9  262.68  5986.6  265.44  6338.4  270.95  6668.5  279.54  6729.6  276.79
#Mann= 12 ,-1 , 0
  3140.1     .11       0  3653.7     .15       0  4150.3     .11       0
  4886.7     .15       0  4957.2     .09       0  5028.4     .15       0
  5233.4     .17       0  5251.6     .15       0  5268.1     .17       0
  5345.5     .15       0  5664.9     .17       0  5986.6     .11       0
Bank Sta=4957.2,5028.4
XS Rating Curve= 0 ,0
Exp/Cntr=0.3,0.1

Chan Stop Cuts=-1
Use User Specified Reach Order=0
Composite Channel Slope=5