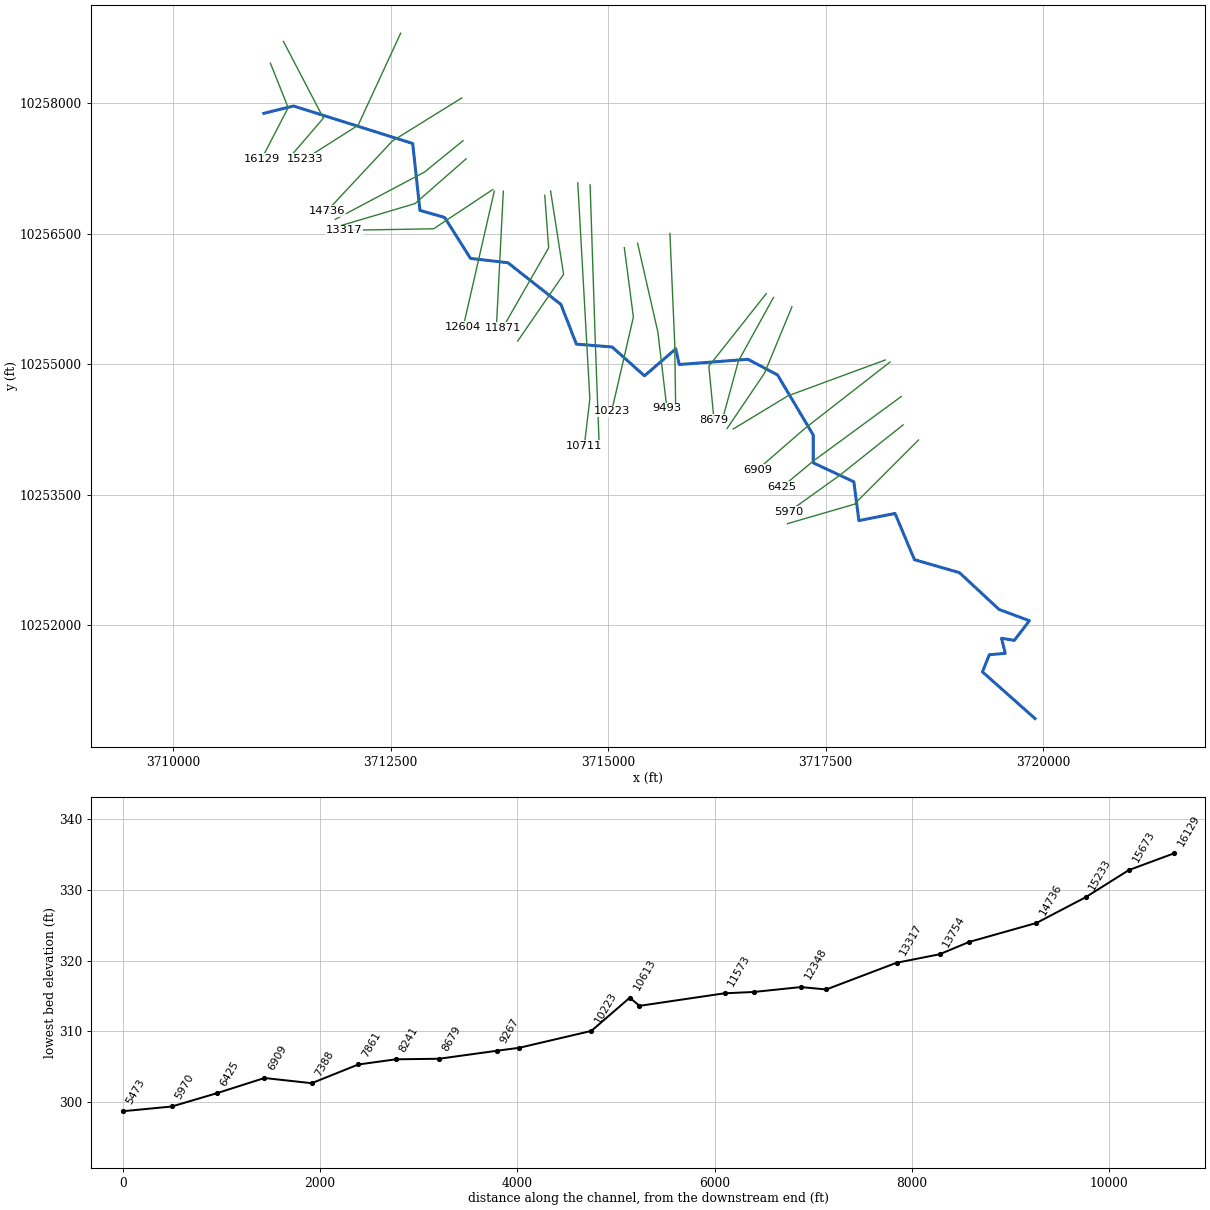
--- NEELY SPRING BRANCH.prj (project) ---

Proj Title=NEELY SPRING BRANCH Base Level Engineering
Current Plan=p01
Default Exp/Contr=0.3,0.1
English Units
Geom File=g01
Flow File=f01
Plan File=p01
Y Axis Title=Elevation
X Axis Title(PF)=Main Channel Distance
X Axis Title(XS)=Station
BEGIN DESCRIPTION:
NEELY SPRING BRANCH
END DESCRIPTION:
DSS Export Rating Curves= 0
DSS Export Rating Curve Sorted= 0
DSS Export Volume Flow Curves= 0
DXF OffsetX= 0
DXF OffsetY= 0
DXF ScaleX= 1
DXF ScaleY= 10

--- NEELY SPRING BRANCH.p01 (plan) ---

Plan Title=Multiple Run
Program Version=4.10
Short Identifier=Multiple
Geom File=g01
Flow File=f01
Subcritical Flow
K Sum by GR= 0
Std Step Tol= 0.01
Critical Tol= 0.01
Num of Std Step Trials= 20
Max Error Tol= 0.3
Flow Tol Ratio= 0.001
Split Flow NTrial= 30
Split Flow Tol= 0.02
Split Flow Ratio= 0.02
Log Output Level= 0
Friction Slope Method= 1
Unsteady Friction Slope Method= 2
Unsteady Bridges Friction Slope Method= 1
Parabolic Critical Depth
Global Vel Dist= 1 , 1 , 1
Global Log Level= 0
CheckData=True
Encroach Param=-1 ,0,0, 0
BEGIN DESCRIPTION:
Multiple Run
END DESCRIPTION:
Computation Interval=1HOUR
Output Interval=1HOUR
Run HTab= 0
Run UNet= 0
Run PostProcess= 0
Run WQNet= 0
UNET Theta= 1
UNET Theta Warmup= 1
UNET ZTol= 0.02
UNET ZSATol= 0.05
UNET MxIter= 20
UNET MaxInSteps= 0
UNET DtIC= 0
UNET DtMin= 0
UNET MaxCRTS= 20
UNET WFStab= 2
UNET SFStab= 1
UNET WFX= 1
UNET SFX= 1
UNET DSS MLevel= 4
UNET DZMax Abort= 100
UNET Convert EG Bridges= 0
UNET Use Existing IB Tables=-1
UNET Froude Reduction=False
UNET Froude Limit= 1
UNET Froude Power= 10
UNET Time Slicing=0,0, 5
UNET Junction Losses=0
Instantaneous Interval=1HOUR
Write IC File= 0
Write IC File at Sim End=0
Echo Input=False
Echo Parameters=False
Echo Output=False
Write Detailed= 0
WQ AD Non Conservative
WQ ULTIMATE=-1
WQ Max Comp Step=1HOUR
WQ Output Interval=15MIN
WQ Output Selected Increments= 0
WQ Output face flow=0
WQ Output face velocity=0
WQ Output face area=0
WQ Output face dispersion=0
WQ Output cell volume=0
WQ Output cell surface area=0
WQ Output cell continuity=0
WQ Output cumulative cell continuity=0
WQ Output face conc=0
WQ Output face dconc_dx=0
WQ Output face courant=0
WQ Output face peclet=0
WQ Output face adv mass=0
WQ Output face disp mass=0
WQ Output cell mass=0
WQ Output cell source sink temp=0
WQ Output cell source sink nsm=0
WQ Output MaxMinRange=-1
WQ Daily Max Min Mean=-1
WQ Daily Range=0
WQ Daily Time=0
WQ Create Restart=0
WQ Fixed Restart=0
WQ System Summary=0
WQ Use Fixed Temperature=0
Sorting and Armoring Iterations= 10
XS Update Threshold= 0.02
Hydraulics Update Threshold= 0.02
Energy Slope Method= 1
Volume Change Method= 0
XS Weighting Method= 0
Number of US Weighted Cross Sections= 1
Number of DS Weighted Cross Sections= 1
Upstream XS Weight=0.25
Main XS Weight=0.5
Downstream XS Weight=0.25
Number of DS XS's Weighted with US Boundary= 1
Upstream Boundary Weight= 1
Weight of XSs Associated with US Boundary= 0
Number of US XS's Weighted with DS Boundary= 1
Downstream Boundary Weight= 0.5
Weight of XSs Associated with DS Boundary= 0.5
Sediment Output Level= 4
Mass or Volume Output= 0
Output Increment Type= 1
Profile and TS Output Increment= 10
XS Output Flag= 0
XS Output Increment= 10
Disregard all LS=0
Disregard all Conn=0
Disregard all Breaches=0
Disregard all Pumps=0

--- NEELY SPRING BRANCH.f01 (steady flow) ---

Flow Title=Multiple
Program Version=4.10
Number of Profiles= 7
Profile Names=10-year,25-year,50-year,1pct_min,100-year,1pct_plu,500-year
River Rch & RM=NEELY SPRING BRA,Reach-1         ,16129
     246     311     401     171     515    1555     877
River Rch & RM=NEELY SPRING BRA,Reach-1         ,12604
     932    1279    1742     779    2352    7103    4436
River Rch & RM=NEELY SPRING BRA,Reach-1         ,7388
    1203    1668    2285    1027    3101    9365    5910
River Rch & RM=NEELY SPRING BRA,Reach-1         ,5970
    1203    1668    2285    1027    3101    9365    5910
Boundary for River Rch & Prof#=NEELY SPRING BRA,Reach-1         , 1
Up Type= 0
Dn Type= 3
Dn Slope=0.002
Boundary for River Rch & Prof#=NEELY SPRING BRA,Reach-1         , 2
Up Type= 0
Dn Type= 3
Dn Slope=0.002
Boundary for River Rch & Prof#=NEELY SPRING BRA,Reach-1         , 3
Up Type= 0
Dn Type= 3
Dn Slope=0.002
Boundary for River Rch & Prof#=NEELY SPRING BRA,Reach-1         , 4
Up Type= 0
Dn Type= 3
Dn Slope=0.002
Boundary for River Rch & Prof#=NEELY SPRING BRA,Reach-1         , 5
Up Type= 0
Dn Type= 3
Dn Slope=0.002
Boundary for River Rch & Prof#=NEELY SPRING BRA,Reach-1         , 6
Up Type= 0
Dn Type= 3
Dn Slope=0.002
Boundary for River Rch & Prof#=NEELY SPRING BRA,Reach-1         , 7
Up Type= 0
Dn Type= 3
Dn Slope=0.002
DSS Import GetInterval= 0
DSS Import GetPeak= 0
DSS Import FillOption= 0

--- NEELY SPRING BRANCH.g01 (geometry) ---

Geom Title=Existing Conditions
Program Version=4.10

River Reach=NEELY SPRING BRA,Reach-1
Reach XY= 30
      3711043.78     10257884.71      3711384.06     10257968.69
      3712753.84     10257537.71      3712837.18     10256768.96
      3713121.29     10256687.45      3713418.23     10256216.84
      3713848.23     10256166.84      3714458.23     10255686.84
      3714635.93     10255230.87      3715046.65     10255198.43
      3715418.23     10254866.84      3715778.23     10255176.84
      3715818.23     10254996.84      3716608.23     10255056.84
      3716948.23     10254876.84      3717358.23     10254186.84
      3717358.23     10253866.84      3717825.33     10253648.49
      3717883.23     10253202.56        3718299.     10253284.19
      3718522.04      10252753.4      3719039.03     10252604.16
      3719495.06     10252180.96      3719843.31     10252051.52
      3719670.38     10251825.57      3719522.93     10251850.29
      3719566.16      10251676.8      3719381.98     10251660.38
      3719303.85     10251463.53      3719908.23     10250926.84

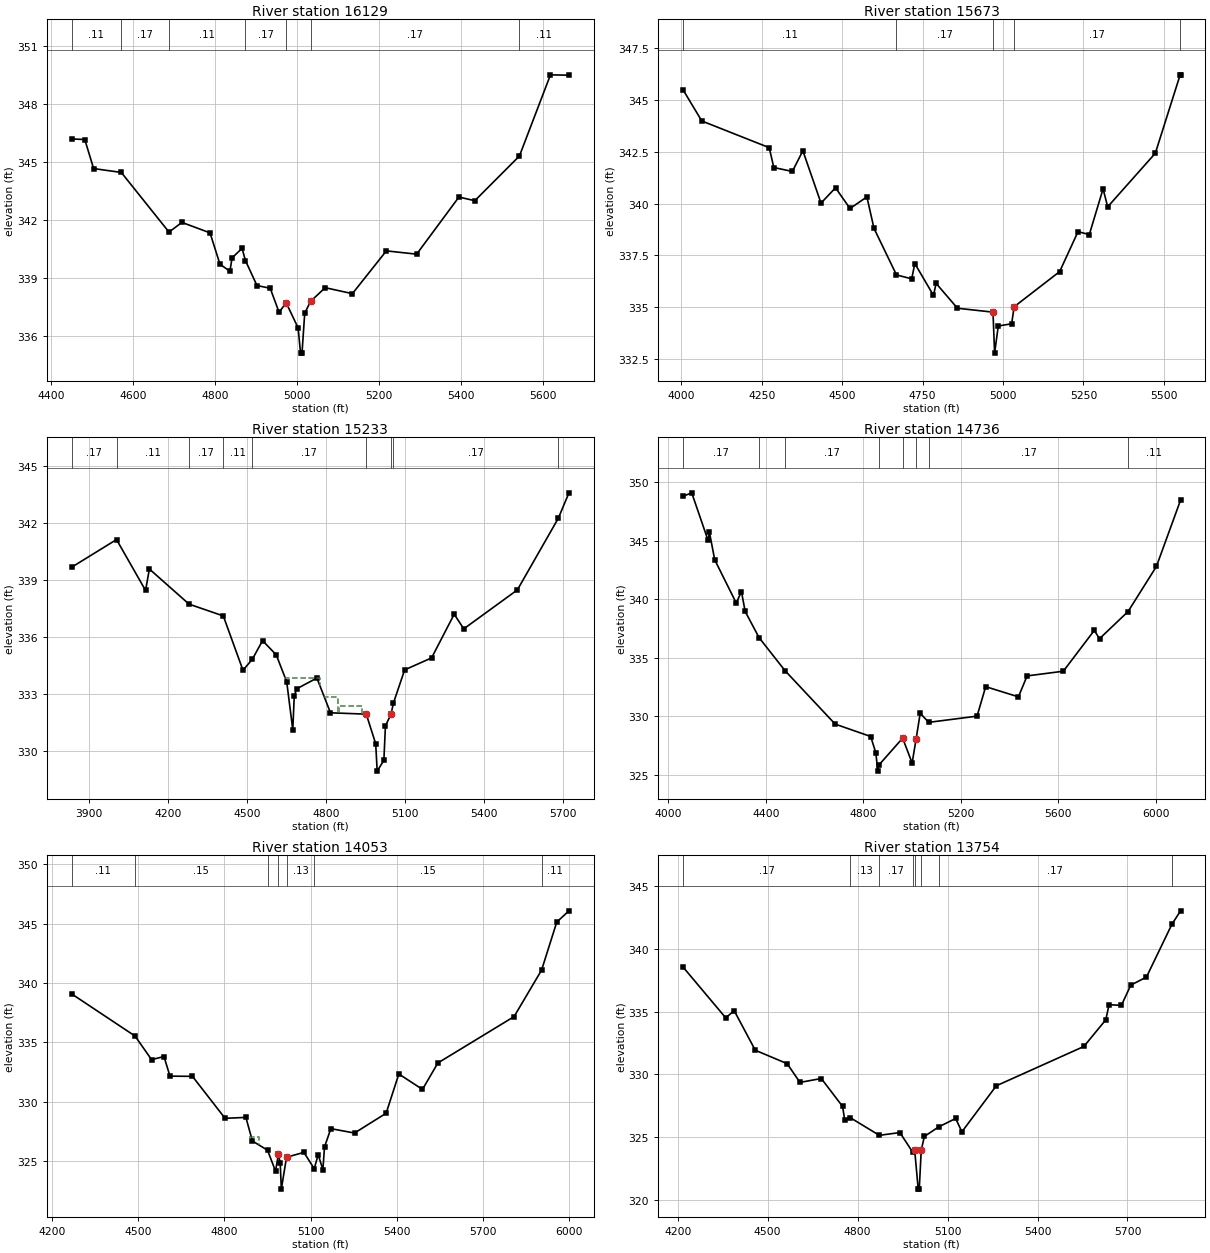
Type RM Length L Ch R = 1 ,16129   ,456,456,456
BEGIN DESCRIPTION:
NEELY SPRING BRANCH 30.0
END DESCRIPTION:
XS GIS Cut Line= 3
      3711117.84      10258461.1      3711322.43     10257949.81
      3711017.83     10257361.04
#Sta/Elev= 30
  4449.3  346.18  4481.6  346.15  4503.2  344.65  4570.7  344.45  4687.1  341.37
  4718.6  341.87  4787.2  341.33  4811.4  339.71  4835.7  339.35    4841  340.04
  4865.3  340.53  4873.6   339.9  4901.7  338.61    4934  338.47  4955.6  337.23
    4973  337.72  5002.1  336.42  5008.1  335.12  5011.6  335.12  5018.2  337.18
  5032.4  337.79  5068.1   338.5  5134.5  338.19  5217.4   340.4  5291.3  340.23
  5394.5  343.18  5433.2  342.99  5542.1   345.3  5617.8  349.49  5662.9  349.47
#Mann= 7 ,-1 , 0
  4449.3     .11       0  4570.7     .17       0  4687.1     .11       0
  4873.6     .17       0    4973     .09       0  5032.4     .17       0
  5542.1     .11       0
Bank Sta=4973,5032.4
XS Rating Curve= 0 ,0
Exp/Cntr=0.3,0.1

Type RM Length L Ch R = 1 ,15673   ,440,440,440
BEGIN DESCRIPTION:
NEELY SPRING BRANCH 29.0
END DESCRIPTION:
XS GIS Cut Line= 3
      3711267.87     10258711.03       3711727.8      10257829.5
      3711367.88     10257411.11
#Sta/Elev= 30
  4005.7  345.49  4063.7  343.99  4273.3   342.7  4287.6  341.74  4345.2  341.55
  4377.9  342.55  4434.3  340.02  4479.4  340.76  4524.5  339.76  4576.9  340.32
    4599   338.8  4668.9  336.55  4716.2  336.36  4725.9   337.1  4783.9  335.56
  4792.1  336.14  4858.4  334.94  4968.9  334.75  4973.9  332.77  4985.3  334.08
  5026.9  334.19  5034.6  335.01  5176.1  336.71  5233.2  338.64  5268.3   338.5
  5311.1  340.71  5325.4  339.84  5473.5  342.43  5550.7  346.22  5551.9  346.22
#Mann= 5 ,-1 , 0
  4005.7     .11       0  4668.9     .17       0  4968.9     .09       0
  5034.6     .17       0  5550.7     .11       0
#XS Ineff= 1 ,-1
    4650  4725.9   337.1
Permanent Ineff=
       F
Bank Sta=4968.9,5034.6
XS Rating Curve= 0 ,0
Exp/Cntr=0.3,0.1

Type RM Length L Ch R = 1 ,15233   ,497,497,497
BEGIN DESCRIPTION:
NEELY SPRING BRANCH 28.0
END DESCRIPTION:
XS GIS Cut Line= 3
      3712615.85     10258806.08      3712126.76     10257747.73
      3711517.85     10257361.07
#Sta/Elev= 30
  3834.1  339.65  4004.8  341.11    4115  338.43  4129.4  339.56    4280  337.71
  4409.9  337.09  4484.5  334.23  4520.1  334.81  4558.8  335.79  4610.8  335.04
  4650.5  333.62  4673.5   331.1    4679  332.85  4687.9  333.25    4765  333.82
  4816.6  331.99  4952.3  331.92  4988.1  330.36  4993.7  328.92  5019.1  329.49
    5025   331.3  5046.2  331.92  5055.5  332.51  5097.9  334.25  5200.1  334.88
  5285.9  337.18  5322.3  336.41  5525.6  338.46  5680.9  342.23  5721.3  343.57
#Mann= 9 ,-1 , 0
  3834.1     .17       0  4004.8     .11       0    4280     .17       0
  4409.9     .11       0  4520.1     .17       0  4952.3     .09       0
  5046.2     .12       0  5055.5     .17       0  5680.9     .11       0
#XS Ineff= 3 ,-1
    4639  4776.2  333.84    4788    4845  332.83    4850  4936.8  332.35
Permanent Ineff=
       F       F       F
Bank Sta=4952.3,5046.2
XS Rating Curve= 0 ,0
Exp/Cntr=0.3,0.1

Type RM Length L Ch R = 1 ,14736   ,683,683,683
BEGIN DESCRIPTION:
NEELY SPRING BRANCH 27.0
END DESCRIPTION:
XS GIS Cut Line= 3
      3713317.85     10258061.07      3712519.64     10257565.75
      3711767.87     10256761.09
#Sta/Elev= 30
  4060.6   348.8  4095.9  349.09  4162.8  345.03  4168.7   345.7  4190.1  343.37
  4278.5  339.67  4299.8  340.65  4315.1  338.95  4372.2  336.71  4478.9  333.88
  4684.3  329.32  4830.1  328.26  4851.3  326.85  4859.1   325.3  4862.8   325.8
  4961.2  328.12    5000  325.99 5016.54  328.06  5033.1  330.24  5068.3  329.47
  5266.4     330  5301.8  332.52  5436.1  331.65  5471.7  333.44  5620.3  333.84
  5747.3  337.33  5768.8  336.62  5885.8  338.94  6002.3   342.8  6101.2  348.46
#Mann= 8 ,-1 , 0
  4060.6     .17       0  4372.2     .11       0  4478.9     .17       0
  4862.8     .15       0  4961.2     .09       0 5016.54     .15       0
  5068.3     .17       0  5885.8     .11       0
Bank Sta=4961.2,5016.54
XS Rating Curve= 0 ,0
Exp/Cntr=0.3,0.1

Type RM Length L Ch R = 1 ,14053   ,299,299,299
BEGIN DESCRIPTION:
NEELY SPRING BRANCH 26.0
END DESCRIPTION:
XS GIS Cut Line= 3
      3713331.99     10257569.12      3712889.31      10257208.9
      3711865.03     10256666.38
#Sta/Elev= 30
  4268.4  339.09  4489.3  335.53  4546.7  333.54  4589.8   333.8  4610.7  332.15
  4688.9  332.13  4802.4  328.59  4874.7  328.67  4897.3  326.68  4950.1   325.9
  4977.8  324.13  4987.9  325.58  4994.1   324.8    4998  322.62  5016.1  325.31
  5076.5  325.72  5112.4  324.34  5126.1  325.53  5142.5  324.26  5148.1  326.17
  5170.1  327.72  5252.5  327.35  5362.4  329.02  5406.6  332.33  5488.8  331.03
  5542.4  333.26  5807.4  337.17    5903  341.09  5955.8  345.14  5998.2  346.09
#Mann= 7 ,-1 , 0
  4268.4     .11       0  4489.3     .15       0  4950.1     .13       0
  4987.9     .09       0  5016.1     .13       0  5112.4     .15       0
    5903     .11       0
#XS Ineff= 1 ,-1
    4885    4920  327.05
Permanent Ineff=
       F
Bank Sta=4987.9,5016.1
XS Rating Curve= 0 ,0
Exp/Cntr=0.3,0.1

Type RM Length L Ch R = 1 ,13754   ,437,437,437
BEGIN DESCRIPTION:
NEELY SPRING BRANCH 25.0
END DESCRIPTION:
XS GIS Cut Line= 3
      3713367.88      10257361.1      3712779.62      10256846.3
      3711938.82     10256596.94
#Sta/Elev= 30
  4218.3  338.54  4360.2  334.51  4388.7  335.07  4458.9  331.93  4565.2  330.86
  4607.9  329.37  4679.1  329.68  4749.9  327.46    4757  326.41  4775.9  326.56
  4872.6  325.16  4941.1  325.38  4983.8  323.82  4990.4  323.99  5002.2  320.88
  5005.7  320.88  5012.3  323.98  5022.7  325.07  5070.4  325.83    5127   326.5
  5147.9  325.44  5262.6   329.1  5554.7  332.23  5627.7  334.35  5638.6  335.55
  5679.8   335.5  5711.1  337.11  5763.3  337.75    5848  341.94    5877  343.02
#Mann= 8 ,-1 , 0
  4218.3     .17       0  4775.9     .13       0  4872.6     .17       0
  4983.8     .15       0  4990.4     .09       0  5012.3     .15       0
  5070.4     .17       0    5848     .11       0
#XS Ineff= 2 ,-1
    4800  4941.1  325.38  5022.7    5050  325.07
Permanent Ineff=
       F       F
Bank Sta=4990.4,5012.3
XS Rating Curve= 0 ,0
Exp/Cntr=0.3,0.1

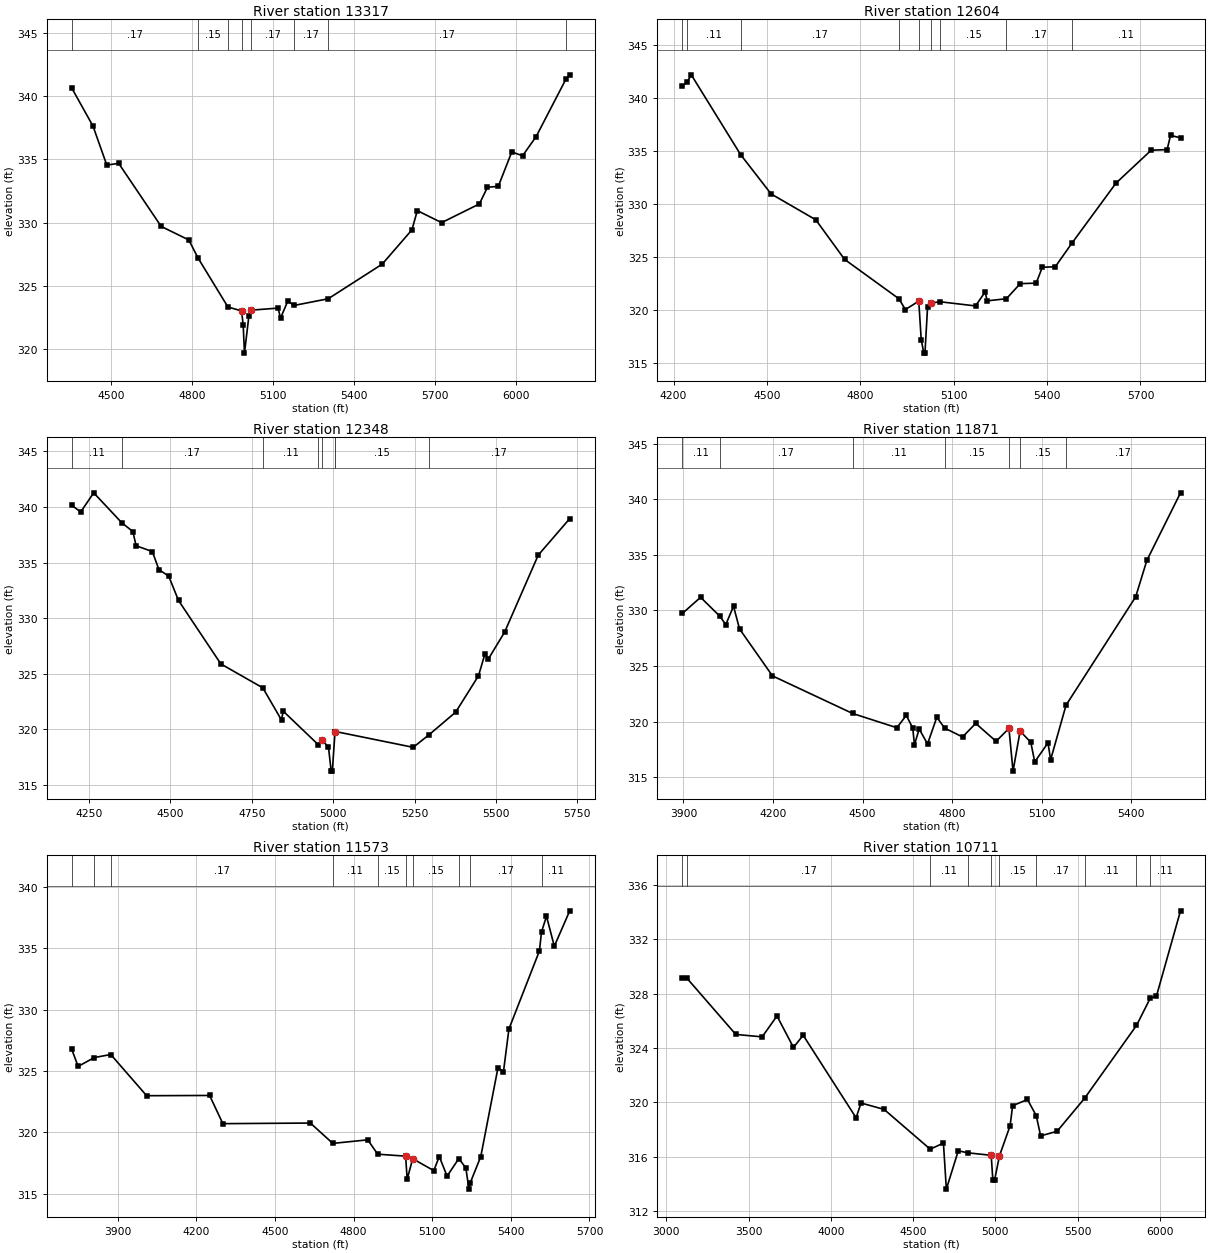
Type RM Length L Ch R = 1 ,13317   ,713,713,713
BEGIN DESCRIPTION:
NEELY SPRING BRANCH 24.0
END DESCRIPTION:
XS GIS Cut Line= 3
      3713673.29     10257007.19      3712994.35     10256556.99
      3711963.13     10256539.63
#Sta/Elev= 30
  4353.1  340.67  4432.6  337.63  4483.7  334.55  4527.6  334.69  4685.2   329.7
  4787.5  328.63  4821.8   327.2  4932.4  323.33    4983  323.02    4989  321.91
  4993.8  319.68    5010  322.59  5019.1  323.08  5118.3  323.24  5127.4  322.45
  5154.4   323.8  5177.3  323.45  5304.2  323.98  5504.3  326.72  5614.3  329.43
  5634.3  330.95  5724.3     330  5864.3  331.48  5894.3   332.8  5934.3  332.87
  5984.3  335.59  6024.4  335.29  6074.4   336.8  6184.8  341.34  6199.1  341.69
#Mann= 8 ,-1 , 0
  4353.1     .17       0  4821.8     .15       0  4932.4     .17       0
    4983     .09       0  5019.1     .17       0  5177.3     .17       0
  5304.2     .17       0  6184.8     .11       0
Bank Sta=4983,5019.1
XS Rating Curve= 0 ,0
Exp/Cntr=0.3,0.1

Type RM Length L Ch R = 1 ,12604   ,256,256,256
BEGIN DESCRIPTION:
NEELY SPRING BRANCH 23.0
END DESCRIPTION:
XS GIS Cut Line= 2
      3713691.56     10256989.02      3713334.79      10255429.1
#Sta/Elev= 30
  4228.4  341.06  4244.2  341.49  4257.1  342.15  4415.5  334.63  4513.5  330.92
  4657.1  328.48  4749.5  324.75  4923.9  321.04  4944.9  320.02  4987.8  320.81
  4995.7  317.19  5004.1  315.91  5007.7  315.91  5016.2  320.29  5025.6  320.64
  5057.2  320.75  5170.1  320.36  5200.8  321.67  5207.7  320.84  5269.4  321.04
  5313.7  322.46    5365  322.51  5384.6     324  5426.5  324.06  5479.6  326.27
  5621.4  331.94  5734.3  335.04  5785.5   335.1  5796.7  336.44  5828.6  336.21
#Mann= 9 ,-1 , 0
  4228.4     .17       0  4244.2     .11       0  4415.5     .17       0
  4923.9     .17       0  4987.8     .09       0  5025.6     .17       0
  5057.2     .15       0  5269.4     .17       0  5479.6     .11       0
Bank Sta=4987.8,5025.6
XS Rating Curve= 0 ,0
Exp/Cntr=0.3,0.1

Type RM Length L Ch R = 1 ,12348   ,477,477,477
BEGIN DESCRIPTION:
NEELY SPRING BRANCH 22.0
END DESCRIPTION:
XS GIS Cut Line= 2
      3713795.72       10256989.      3713717.85     10255461.09
#Sta/Elev= 30
  4196.8  340.17  4224.8  339.56  4264.8  341.28  4351.3  338.58    4385   337.8
    4395  336.52  4444.8     336  4465.1  334.37  4495.1  333.79  4525.2   331.6
  4655.3  325.89  4784.1  323.74  4841.6  320.84  4846.6  321.65  4954.7  318.62
  4965.7  319.06  4985.8   318.4    4994  316.25  4997.6  316.25  5005.8  319.77
  5007.3  319.81  5246.1  318.39  5294.5  319.52  5376.3  321.55  5446.4  324.82
  5466.4   326.8  5476.4  326.32  5526.5  328.74    5630  335.68  5726.7  338.96
#Mann= 8 ,-1 , 0
  4196.8     .11       0  4351.3     .17       0  4784.1     .11       0
  4954.7     .17       0  4965.7     .09       0  5005.8     .17       0
  5007.3     .15       0  5294.5     .17       0
Bank Sta=4965.7,5005.8
XS Rating Curve= 0 ,0
Exp/Cntr=0.3,0.1

Type RM Length L Ch R = 1 ,11871   ,298,298,298
BEGIN DESCRIPTION:
NEELY SPRING BRANCH 21.0
END DESCRIPTION:
XS GIS Cut Line= 3
      3714272.29     10256942.06      3714316.55     10256337.94
      3713787.92     10255416.09
#Sta/Elev= 30
  3896.5  329.73  3957.6  331.18  4021.4   329.5    4042  328.73  4067.9  330.38
    4088  328.34  4198.3  324.12  4466.9  320.74  4614.9  319.46  4646.6  320.57
  4668.1  319.43  4673.9  317.93  4689.7  319.35  4717.7     318  4748.7   320.4
  4774.9  319.43    4835  318.63    4879  319.85  4947.2  318.24  4990.3   319.4
    5004  315.56  5027.7  319.16  5063.5  318.15  5076.7  316.39  5121.1   318.1
  5129.9  316.58  5181.6  321.49  5414.7  331.22  5452.1  334.49  5564.9  340.57
#Mann= 7 ,-1 , 0
  3896.5     .11       0  4021.4     .17       0  4466.9     .11       0
  4774.9     .15       0  4990.3     .09       0  5027.7     .15       0
  5181.6     .17       0
Bank Sta=4990.3,5027.7
XS Rating Curve= 0 ,0
Exp/Cntr=0.3,0.1

Type RM Length L Ch R = 1 ,11573   ,862,862,862
BEGIN DESCRIPTION:
NEELY SPRING BRANCH 20.0
END DESCRIPTION:
XS GIS Cut Line= 3
      3714339.12     10256991.62      3714488.43     10256033.25
      3713960.63     10255265.86
#Sta/Elev= 30
  3723.3  326.81  3748.4  325.38  3809.8   326.1  3872.9  326.35  4009.8  322.99
  4250.1  323.01  4300.7  320.71  4634.7  320.76  4720.2   319.1  4853.7  319.39
  4891.6  318.22  4998.1  318.06  5004.2  316.18  5025.2  317.85  5105.7  316.88
  5126.7  318.03  5156.4  316.43  5201.2  317.86  5228.1   317.1  5239.8  315.37
  5244.6  315.87    5285  318.02  5350.6  325.26  5371.6  324.94  5392.5  328.43
  5508.9   334.8  5516.9  336.35  5535.9  337.63  5565.7  335.18  5624.6  338.07
#Mann= 10 ,-1 , 0
  3723.3     .17       0  3809.8     .11       0  3872.9     .17       0
  4720.2     .11       0  4891.6     .15       0  4998.1     .09       0
  5025.2     .15       0  5201.2     .17       0  5244.6     .17       0
  5516.9     .11       0
Bank Sta=4998.1,5025.2
XS Rating Curve= 0 ,0
Exp/Cntr=0.3,0.1

Type RM Length L Ch R = 1 ,10711   ,98,98,98
BEGIN DESCRIPTION:
NEELY SPRING BRANCH 19.0
END DESCRIPTION:
XS GIS Cut Line= 3
      3714651.62     10257085.37      3714790.51      10254602.7
      3714727.23     10254065.27
#Sta/Elev= 30
  3097.7  329.17  3124.1  329.15  3422.5  324.99  3582.8  324.81  3672.9  326.35
  3773.1  324.03    3832  324.93  4153.7  318.85  4183.7  319.94  4323.9  319.47
  4604.4  316.54  4684.5  316.99  4702.3   313.6  4774.6  316.42  4834.7  316.27
  4974.9  316.09  4984.9  314.25    4995  314.24    5025  316.05  5089.6  318.26
  5105.1  319.74  5195.3   320.2  5248.6  319.01  5275.4  317.52  5375.6  317.86
  5543.2   320.3  5857.9  325.65    5942  327.67  5978.6  327.79  6125.4  334.09
#Mann= 10 ,-1 , 0
  3097.7     .11       0  3124.1     .17       0  4604.4     .11       0
  4834.7     .15       0  4974.9     .09       0    5025     .15       0
  5248.6     .17       0  5543.2     .11       0  5857.9     .17       0
    5942     .11       0
#XS Ineff= 1 ,-1
  5195.3    5560   320.2
Permanent Ineff=
       F
Bank Sta=4974.9,5025
XS Rating Curve= 0 ,0
Exp/Cntr=0.3,0.1

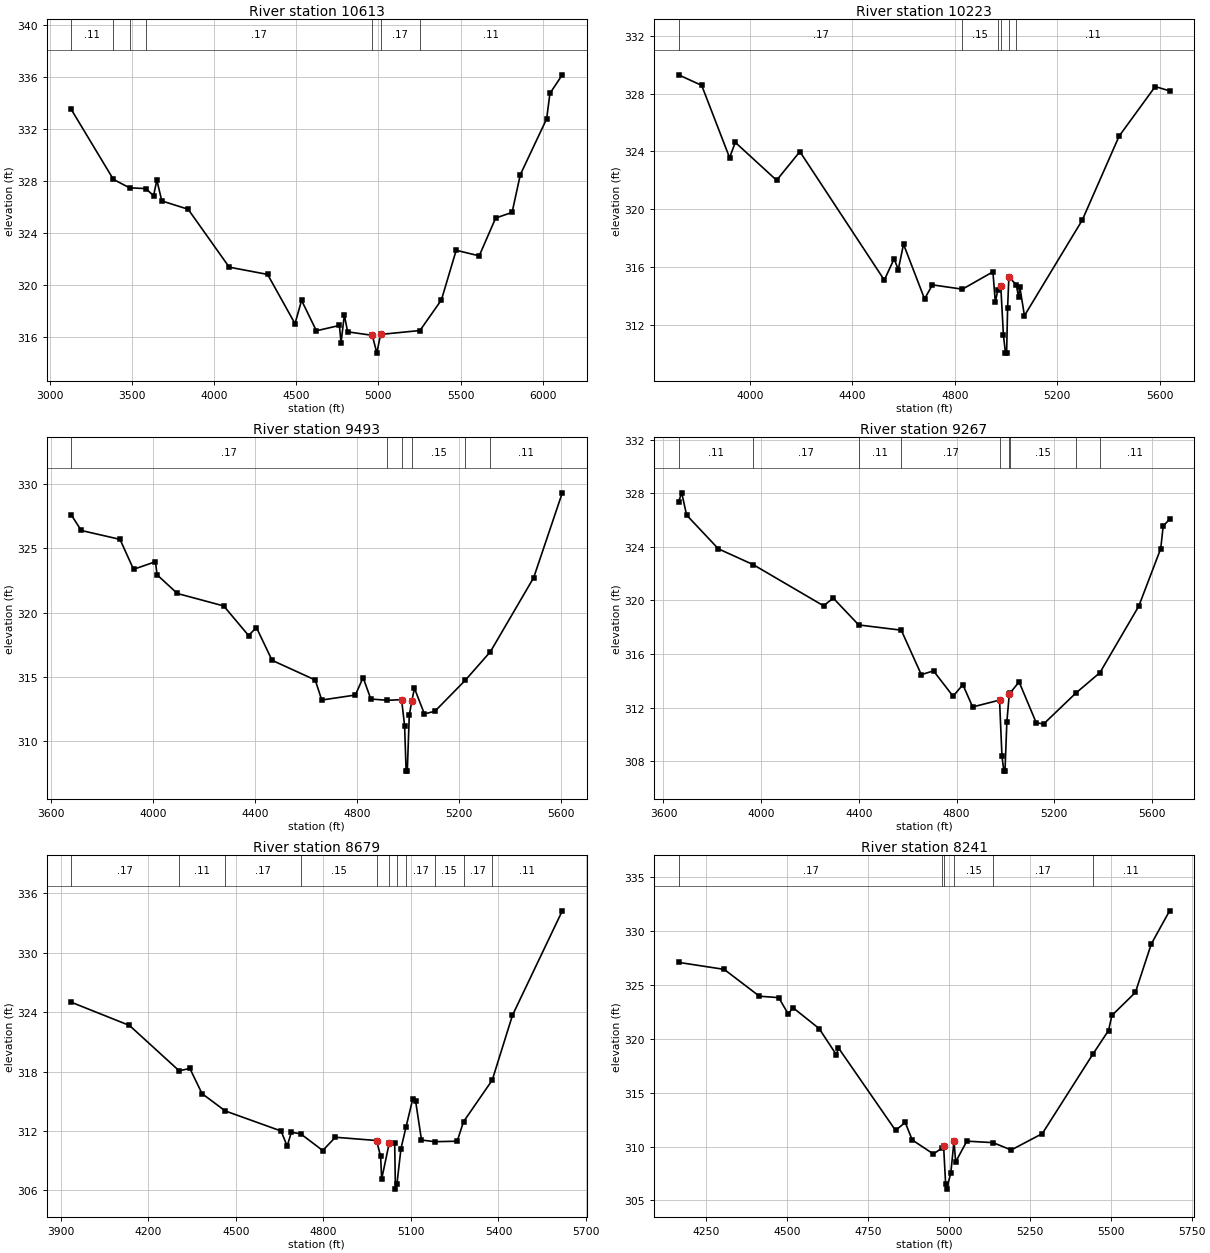
Type RM Length L Ch R = 1 ,10613   ,390,390,390
BEGIN DESCRIPTION:
NEELY SPRING BRANCH 18.0
END DESCRIPTION:
XS GIS Cut Line= 3
      3714793.55     10257061.87      3714855.11     10255193.98
      3714897.71     10254075.89
#Sta/Elev= 30
  3131.1  333.52  3387.6  328.13  3485.7  327.48  3583.9  327.42  3632.2  326.88
  3652.2  328.07  3682.2  326.47  3842.3  325.83  4092.4  321.37  4325.9  320.81
  4492.6  317.02  4532.7  318.81  4622.7  316.47  4762.8  316.88  4772.8  315.54
  4792.8   317.7  4812.8  316.39  4962.9  316.12  4990.7  314.75  5012.9  316.19
  5252.8  316.49  5383.2  318.84  5473.3  322.67  5613.4  322.24  5713.4  325.15
  5813.5  325.59  5863.5  328.49  6023.7  332.79  6043.7  334.75  6118.9  336.18
#Mann= 7 ,-1 , 0
  3131.1     .11       0  3387.6     .17       0  3485.7     .11       0
  3583.9     .17       0  4962.9     .09       0  5012.9     .17       0
  5252.8     .11       0
#XS Ineff= 1 ,-1
    4405  4532.7  318.81
Permanent Ineff=
       F
Bank Sta=4962.9,5012.9
XS Rating Curve= 0 ,0
Exp/Cntr=0.3,0.1

Type RM Length L Ch R = 1 ,10223   ,730,730,730
BEGIN DESCRIPTION:
NEELY SPRING BRANCH 17.0
END DESCRIPTION:
XS GIS Cut Line= 3
      3715186.67     10256340.86      3715290.83     10255542.28
      3715040.84     10254458.99
#Sta/Elev= 30
    3721   329.3  3811.5  328.57  3920.4  323.57  3942.6  324.63    4104  322.01
  4194.8  323.99  4524.4  315.11  4562.7  316.58  4578.9  315.83  4599.4  317.59
  4681.5  313.81  4712.3  314.78  4829.3  314.48  4948.4  315.68  4957.8  313.59
  4967.3  314.42  4979.1  314.69  4989.4   311.3  4997.5  310.06  5001.9  310.06
  5005.7  313.18  5010.8  315.34    5040  314.76  5048.4  313.93  5053.6  314.61
  5071.5  312.65  5297.3  319.26    5441  325.06  5582.1  328.49  5638.1  328.19
#Mann= 6 ,-1 , 0
    3721     .17       0  4829.3     .15       0  4967.3     .17       0
  4979.1     .09       0  5010.8     .17       0    5040     .11       0
#XS Ineff= 1 ,-1
    4415  4599.4  317.59
Permanent Ineff=
       F
Bank Sta=4979.1,5010.8
XS Rating Curve= 0 ,0
Exp/Cntr=0.3,0.1

Type RM Length L Ch R = 1 ,9493    ,226,226,226
BEGIN DESCRIPTION:
NEELY SPRING BRANCH 16.0
END DESCRIPTION:
XS GIS Cut Line= 3
      3715339.45     10256389.46      3715572.08     10255372.14
      3715676.11     10254494.86
#Sta/Elev= 30
  3679.2  327.62  3718.6   326.4  3870.6  325.71  3923.8  323.38  4009.7  323.97
  4016.1  322.95  4095.6   321.5  4277.6  320.53  4375.1  318.23  4405.9  318.85
  4467.4   316.3  4636.6  314.77  4662.3  313.21  4794.3   313.6  4824.6  314.96
  4854.8  313.29  4919.4  313.19  4975.6  313.24  4987.4  311.21  4993.4  307.68
    4998  307.68  5005.8  312.04  5015.9  313.15    5026  314.13  5065.1  312.13
  5106.5  312.34  5225.6  314.75  5324.1  316.97  5493.9  322.73  5606.2  329.33
#Mann= 6 ,-1 , 0
  3679.2     .17       0  4919.4     .15       0  4975.6     .09       0
  5015.9     .15       0  5225.6     .17       0  5324.1     .11       0
Bank Sta=4975.6,5015.9
XS Rating Curve= 0 ,0
Exp/Cntr=0.3,0.1

Type RM Length L Ch R = 1 ,9267    ,588,588,588
BEGIN DESCRIPTION:
NEELY SPRING BRANCH 15.0
END DESCRIPTION:
XS GIS Cut Line= 3
      3715710.97     10256504.13      3715766.52     10255227.51
      3715776.92     10254494.91
#Sta/Elev= 30
  3661.5  327.35  3674.6  328.03  3694.6  326.37  3824.7  323.85  3967.3  322.67
  4255.1   319.6  4295.2  320.17  4399.2  318.17  4573.4  317.78  4655.5  314.46
  4705.5  314.74  4785.6  312.85  4825.7  313.71  4865.7  312.05  4975.8  312.56
  4985.8  308.37  4993.5  307.26  4998.1  307.26  5005.8  310.94  5015.8  313.03
  5017.8  313.06  5055.8  313.92  5125.8  310.88  5155.8  310.77  5288.6  313.09
  5386.8  314.61  5545.8  319.57  5635.8  323.87  5645.8  325.55    5672  326.06
#Mann= 9 ,-1 , 0
  3661.5     .11       0  3967.3     .17       0  4399.2     .11       0
  4573.4     .17       0  4975.8     .09       0  5015.8     .17       0
  5017.8     .15       0  5288.6     .17       0  5386.8     .11       0
Bank Sta=4975.8,5015.8
XS Rating Curve= 0 ,0
Exp/Cntr=0.3,0.1

Type RM Length L Ch R = 1 ,8679    ,438,438,438
BEGIN DESCRIPTION:
NEELY SPRING BRANCH 14.0
END DESCRIPTION:
XS GIS Cut Line= 3
      3716817.85     10255811.07      3716158.23     10254976.84
      3716217.86     10254361.02
#Sta/Elev= 30
  3936.5  325.01  4136.1  322.66  4306.3  318.08  4342.9  318.32  4384.5  315.78
    4464  314.03  4655.4     312  4676.2  310.47  4690.6  311.87  4722.4  311.72
    4798  310.03  4841.4  311.37  4982.3  311.04  4996.3  309.46    5000  307.15
  5025.9  310.79  5044.5  310.79  5047.1  306.13  5052.2  306.63  5066.1  310.23
  5083.7  312.44  5106.3  315.22  5116.3  315.01  5136.4  311.09    5182  310.92
  5258.7  310.97  5280.4  312.94  5378.7  317.14  5447.9  323.68  5618.7  334.24
#Mann= 11 ,-1 , 0
  3936.5     .17       0  4306.3     .11       0    4464     .17       0
  4722.4     .15       0  4982.3     .09       0  5025.9     .15       0
  5052.2     .15       0  5083.7     .17       0    5182     .15       0
  5280.4     .17       0  5378.7     .11       0
#XS Ineff= 1 ,-1
  5106.3    5345  315.22
Permanent Ineff=
       F
Bank Sta=4982.3,5025.9
XS Rating Curve= 0 ,0
Exp/Cntr=0.3,0.1

Type RM Length L Ch R = 1 ,8241    ,380,380,380
BEGIN DESCRIPTION:
NEELY SPRING BRANCH 13.0
END DESCRIPTION:
XS GIS Cut Line= 3
      3716901.95     10255767.99      3716498.23     10255036.84
      3716318.62     10254379.13
#Sta/Elev= 30
  4164.8  327.08  4305.9  326.43  4414.7  323.94  4474.3  323.81    4504  322.28
  4517.9  322.89  4599.2  320.94  4652.5  318.51  4658.8  319.15  4835.2   311.5
  4865.1  312.23  4886.8  310.61  4952.1  309.31  4980.2  309.89  4983.7  310.03
  4989.9  306.56  4992.8  306.05    5006  307.55  5015.8  310.51    5021  308.58
  5055.5   310.5  5136.7  310.36  5192.6  309.68  5288.6   311.2  5445.5   318.6
  5493.2  320.76  5503.6  322.16  5576.1  324.29  5625.3  328.79  5681.8  331.86
#Mann= 6 ,-1 , 0
  4164.8     .17       0  4980.2     .12       0  4983.7     .09       0
  5015.8     .15       0  5136.7     .17       0  5445.5     .11       0
Bank Sta=4983.7,5015.8
XS Rating Curve= 0 ,0
Exp/Cntr=0.3,0.1

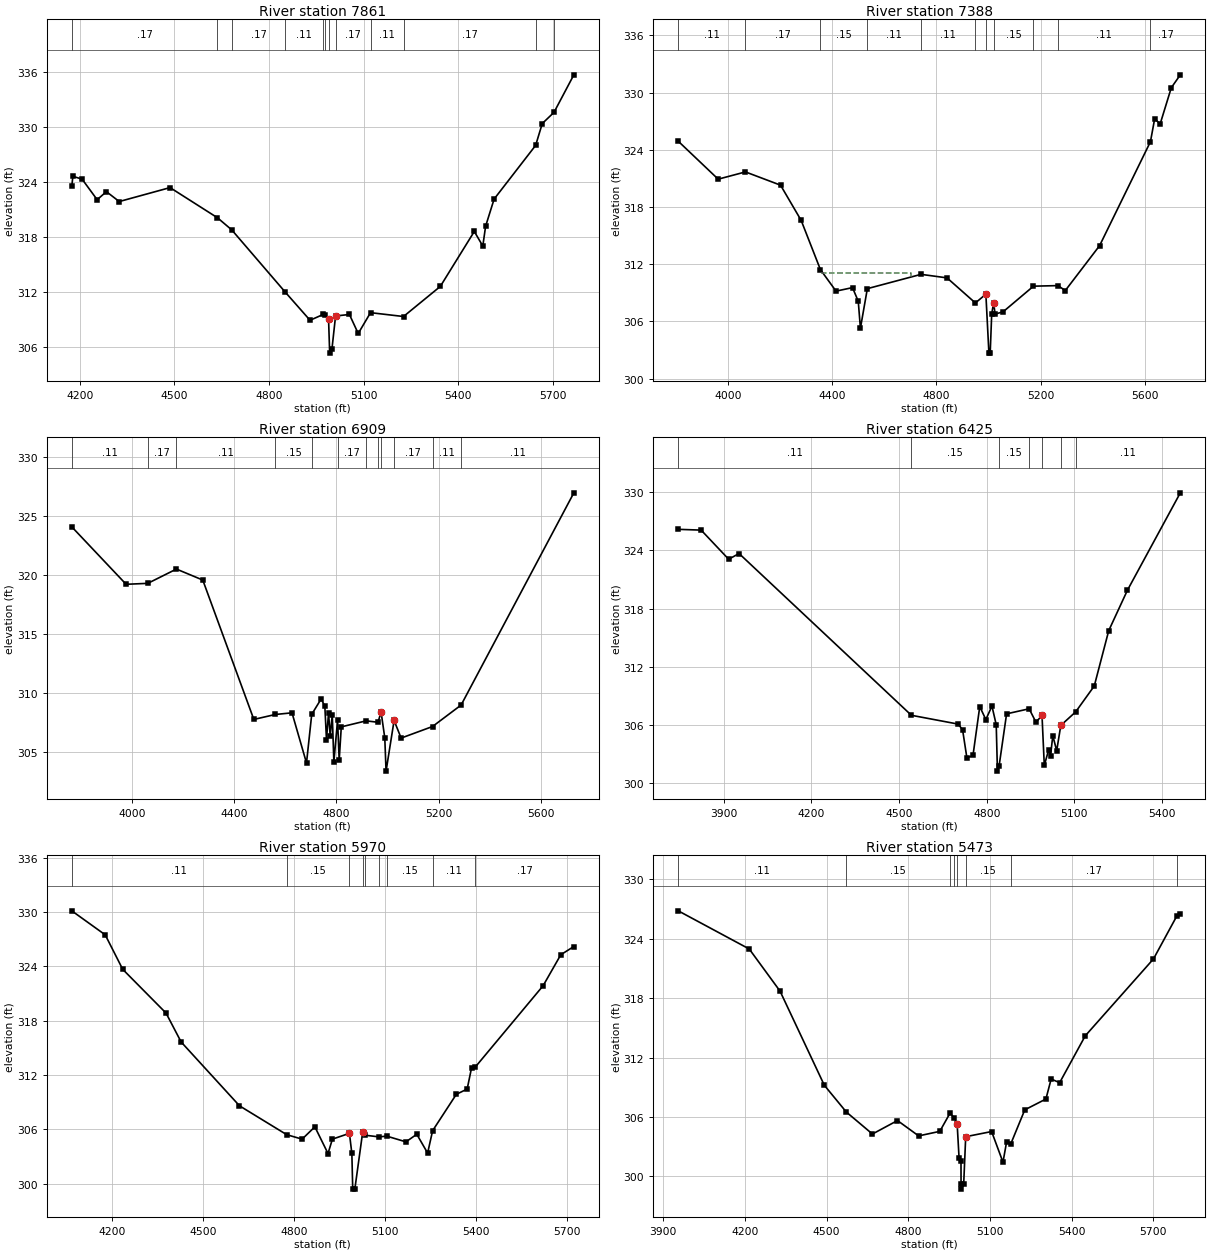
Type RM Length L Ch R = 1 ,7861    ,473,473,473
BEGIN DESCRIPTION:
NEELY SPRING BRANCH 12.0
END DESCRIPTION:
XS GIS Cut Line= 3
      3717113.74     10255660.32      3716798.23     10254896.84
      3716367.88     10254261.11
#Sta/Elev= 30
  4173.9  323.48  4177.4  324.59  4206.7  324.28  4254.5  322.04  4283.8  322.92
  4324.6  321.84  4485.9  323.36  4636.5  320.07  4681.8  318.75  4851.8  311.96
  4930.3   308.9  4971.6  309.53  4976.8  309.47    4989  309.08  4992.6  305.32
    5000  305.82  5011.3  309.37  5055.3  309.53  5083.2  307.46  5122.3  309.73
    5227  309.31  5343.8  312.59  5451.7  318.58  5478.7  316.99  5487.6  319.15
  5514.6  322.11  5646.4  327.96  5667.4  330.34  5704.7  331.56  5767.7  335.65
#Mann= 12 ,-1 , 0
  4173.9     .17       0  4636.5     .11       0  4681.8     .17       0
  4851.8     .11       0  4971.6     .15       0  4976.8     .17       0
    4989     .09       0  5011.3     .17       0  5122.3     .11       0
    5227     .17       0  5646.4     .11       0  5704.7     .17       0
Bank Sta=4989,5011.3
XS Rating Curve= 0 ,0
Exp/Cntr=0.3,0.1

Type RM Length L Ch R = 1 ,7388    ,479,479,479
BEGIN DESCRIPTION:
NEELY SPRING BRANCH 11.0
END DESCRIPTION:
XS GIS Cut Line= 3
      3718186.63     10255049.21      3717068.23     10254636.84
      3716438.29     10254255.07
#Sta/Elev= 30
    3808   324.9  3961.4  320.92  4066.2  321.68    4201  320.29  4280.3  316.59
  4354.1  311.44  4414.2  309.18  4477.4  309.55  4499.5  308.12  4507.8  305.29
  4534.4  309.44  4740.7  310.94  4840.5  310.57  4949.4  307.94  4989.7  308.86
  5001.4  302.68  5006.3  302.68  5012.1  306.77  5019.4  307.97  5025.2  306.77
  5056.2  307.02  5172.6   309.7  5266.5  309.76  5294.8  309.24  5426.6  313.95
  5621.9  324.85    5638  327.24  5659.3  326.72    5702  330.51  5736.6  331.86
#Mann= 11 ,-1 , 0
    3808     .11       0  4066.2     .17       0  4354.1     .15       0
  4534.4     .11       0  4740.7     .11       0  4949.4     .15       0
  4989.7     .09       0  5019.4     .15       0  5172.6     .15       0
  5266.5     .11       0  5621.9     .17       0
#XS Ineff= 1 ,-1
    4355    4702  311.05
Permanent Ineff=
       F
Bank Sta=4989.7,5019.4
XS Rating Curve= 0 ,0
Exp/Cntr=0.3,0.1

Type RM Length L Ch R = 1 ,6909    ,484,484,484
BEGIN DESCRIPTION:
NEELY SPRING BRANCH 10.0
END DESCRIPTION:
XS GIS Cut Line= 3
      3718241.93     10255025.56      3717268.23     10254266.84
      3716717.95     10253788.84
#Sta/Elev= 30
  3765.6  324.11  3978.1  319.24  4062.8  319.32  4174.8  320.53  4277.9   319.6
  4477.5  307.79  4561.7  308.21  4626.8  308.35  4683.5   304.1  4703.9  308.22
  4740.8  309.53  4755.2  308.91  4761.6  306.08  4769.7  308.36  4776.1  306.38
  4784.2  308.17  4790.5   304.2    4805  307.73  4811.3  304.33  4819.5  307.16
  4916.7  307.67  4963.1  307.55  4975.1  308.42  4989.6  306.23  4994.6  303.41
    5026   307.7  5053.5  306.21  5176.3  307.19  5288.1  309.01  5728.9  326.99
#Mann= 12 ,-1 , 0
  3765.6     .11       0  4062.8     .17       0  4174.8     .11       0
  4561.7     .15       0  4703.9     .17       0    4805     .17       0
  4916.7     .15       0  4963.1     .17       0  4975.1     .09       0
    5026     .17       0  5176.3     .11       0  5288.1     .11       0
#XS Ineff= 1 ,-1
    4430  4740.8  309.53
Permanent Ineff=
       F
Bank Sta=4975.1,5026
XS Rating Curve= 0 ,0
Exp/Cntr=0.3,0.1

Type RM Length L Ch R = 1 ,6425    ,455,455,455
BEGIN DESCRIPTION:
NEELY SPRING BRANCH 9.0
END DESCRIPTION:
XS GIS Cut Line= 3
       3718370.7     10254629.09      3717358.23     10253886.84
      3717002.74     10253590.98
#Sta/Elev= 30
  3744.6  326.16    3823  326.08  3917.2  323.08  3952.7  323.67  4542.4  307.01
    4703   306.1  4717.6   305.5  4732.3  302.62  4753.1  302.87  4776.3  307.91
  4797.1  306.57    4818  307.96  4832.6  306.04  4836.8  301.26  4842.3  301.76
  4868.1  307.16  4945.3  307.68  4968.5   306.3  4989.3  306.99  4997.1  301.84
  5011.9  303.44  5018.4  302.83  5026.2  304.91  5039.5  303.36  5053.6  305.97
  5104.4  307.36  5168.1  310.03  5217.6  315.73  5281.4  319.88  5462.5  329.92
#Mann= 7 ,-1 , 0
  3744.6     .11       0  4542.4     .15       0  4842.3     .15       0
  4945.3     .15       0  4989.3     .09       0  5053.6     .15       0
  5104.4     .11       0
Bank Sta=4989.3,5053.6
XS Rating Curve= 0 ,0
Exp/Cntr=0.3,0.1

Type RM Length L Ch R = 1 ,5970    ,497,497,497
BEGIN DESCRIPTION:
NEELY SPRING BRANCH 8.0
END DESCRIPTION:
XS GIS Cut Line= 3
      3718391.51     10254302.68      3717662.35     10253722.84
      3717075.56      10253302.7
#Sta/Elev= 30
  4068.4  330.12  4178.5  327.47  4236.2  323.66  4378.8  318.83  4428.5  315.64
  4620.7  308.59  4776.3   305.4  4826.9  304.91  4868.9  306.27  4912.2  303.32
  4926.6  304.91  4982.7  305.55  4990.7  303.33  4993.6  299.39  5000.5  299.39
  5026.4   305.7  5032.5  305.35  5080.3  305.16  5105.7  305.24  5168.9  304.61
  5204.5  305.45  5240.2  303.37  5256.6  305.84  5334.7  309.86  5370.4  310.44
  5385.1  312.82  5397.4  312.88  5620.5  321.85  5678.7  325.27  5721.7  326.18
#Mann= 9 ,-1 , 0
  4068.4     .11       0  4776.3     .15       0  4982.7     .09       0
  5026.4     .12       0  5032.5     .15       0  5080.3     .11       0
  5105.7     .15       0  5256.6     .11       0  5397.4     .17       0
Bank Sta=4982.7,5026.4
XS Rating Curve= 0 ,0
Exp/Cntr=0.3,0.1

Type RM Length L Ch R = 1 ,5473    ,830,830,830
BEGIN DESCRIPTION:
NEELY SPRING BRANCH 7.0
END DESCRIPTION:
XS GIS Cut Line= 3
      3718568.63     10254129.11      3717829.96     10253390.22
      3717062.23     10253167.44
#Sta/Elev= 30
  3955.2   326.8    4216  322.95  4329.1   318.7  4491.8   309.2  4572.6   306.5
  4668.5  304.28  4760.5  305.64  4838.3  304.09    4916  304.55  4953.4  306.38
  4968.8  305.92  4979.7   305.3  4986.7  301.88  4993.8  301.51    4994  299.22
  4994.5  298.72  5003.7  299.22  5011.1  304.01  5106.3  304.53    5148  301.44
    5161  303.43  5176.8  303.29  5228.1  306.72  5305.7  307.81    5325  309.83
  5356.2  309.46  5450.3  314.19  5700.9  321.95  5786.8  326.29  5799.4   326.5
#Mann= 8 ,-1 , 0
  3955.2     .11       0  4572.6     .15       0  4953.4     .17       0
  4968.8     .15       0  4979.7     .09       0  5011.1     .15       0
  5176.8     .17       0  5786.8     .11       0
Bank Sta=4979.7,5011.1
XS Rating Curve= 0 ,0
Exp/Cntr=0.3,0.1