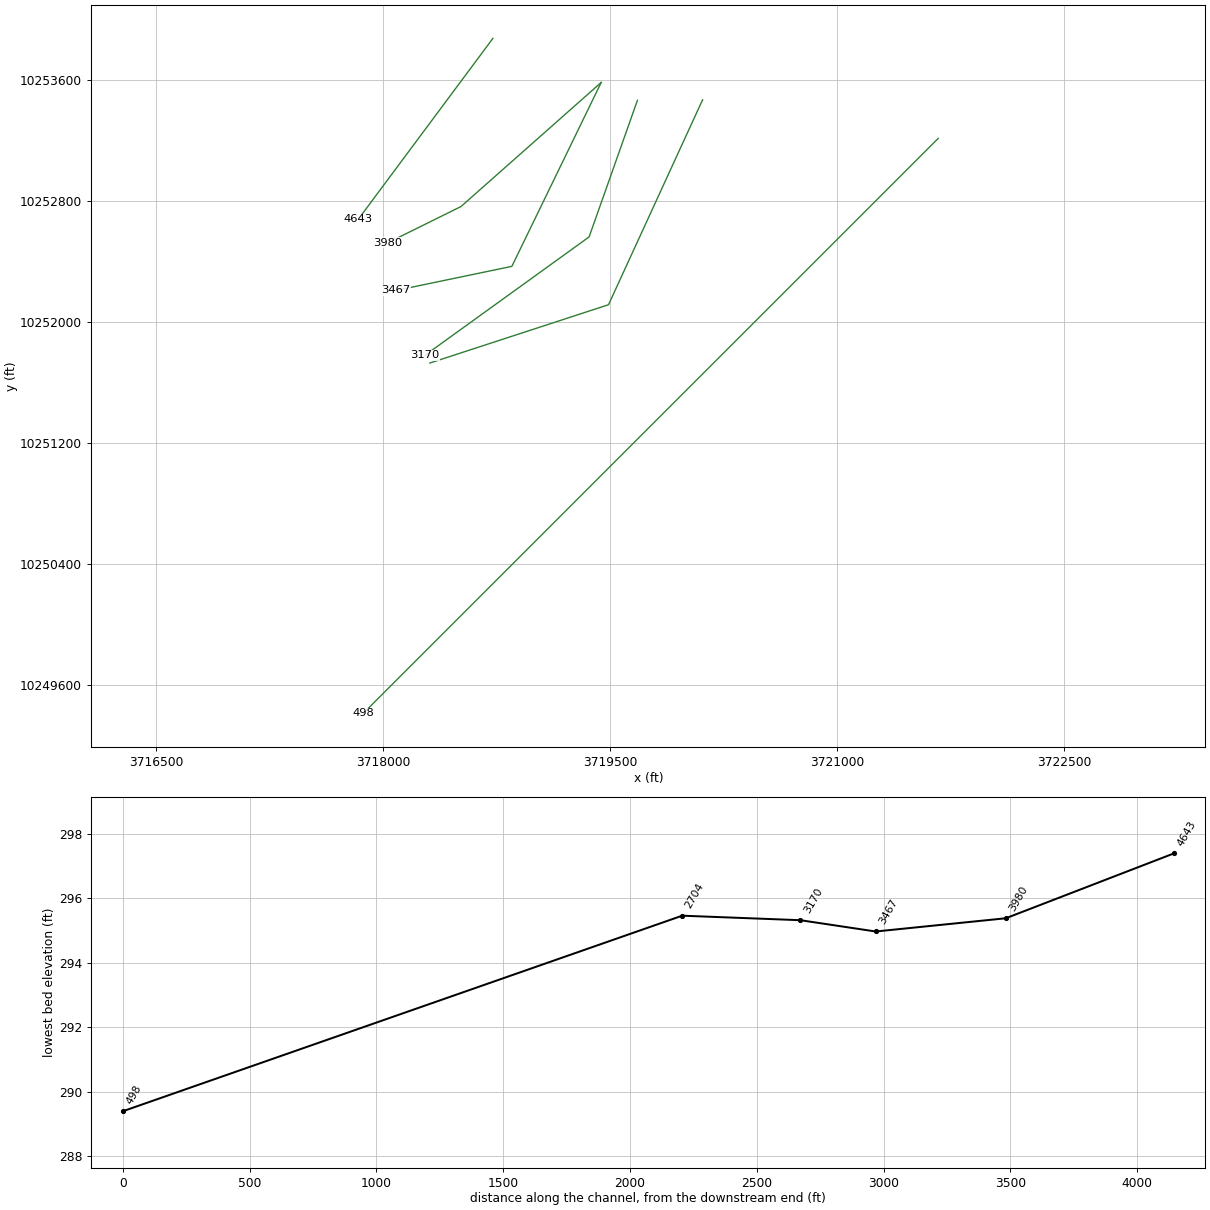
HEC-RAS study NEELY SPRING BRANCH.prj: NEELY SPRING BRANCH Base Level Engineering

--- NEELY SPRING BRANCH.g01 (geometry) --- (continued)

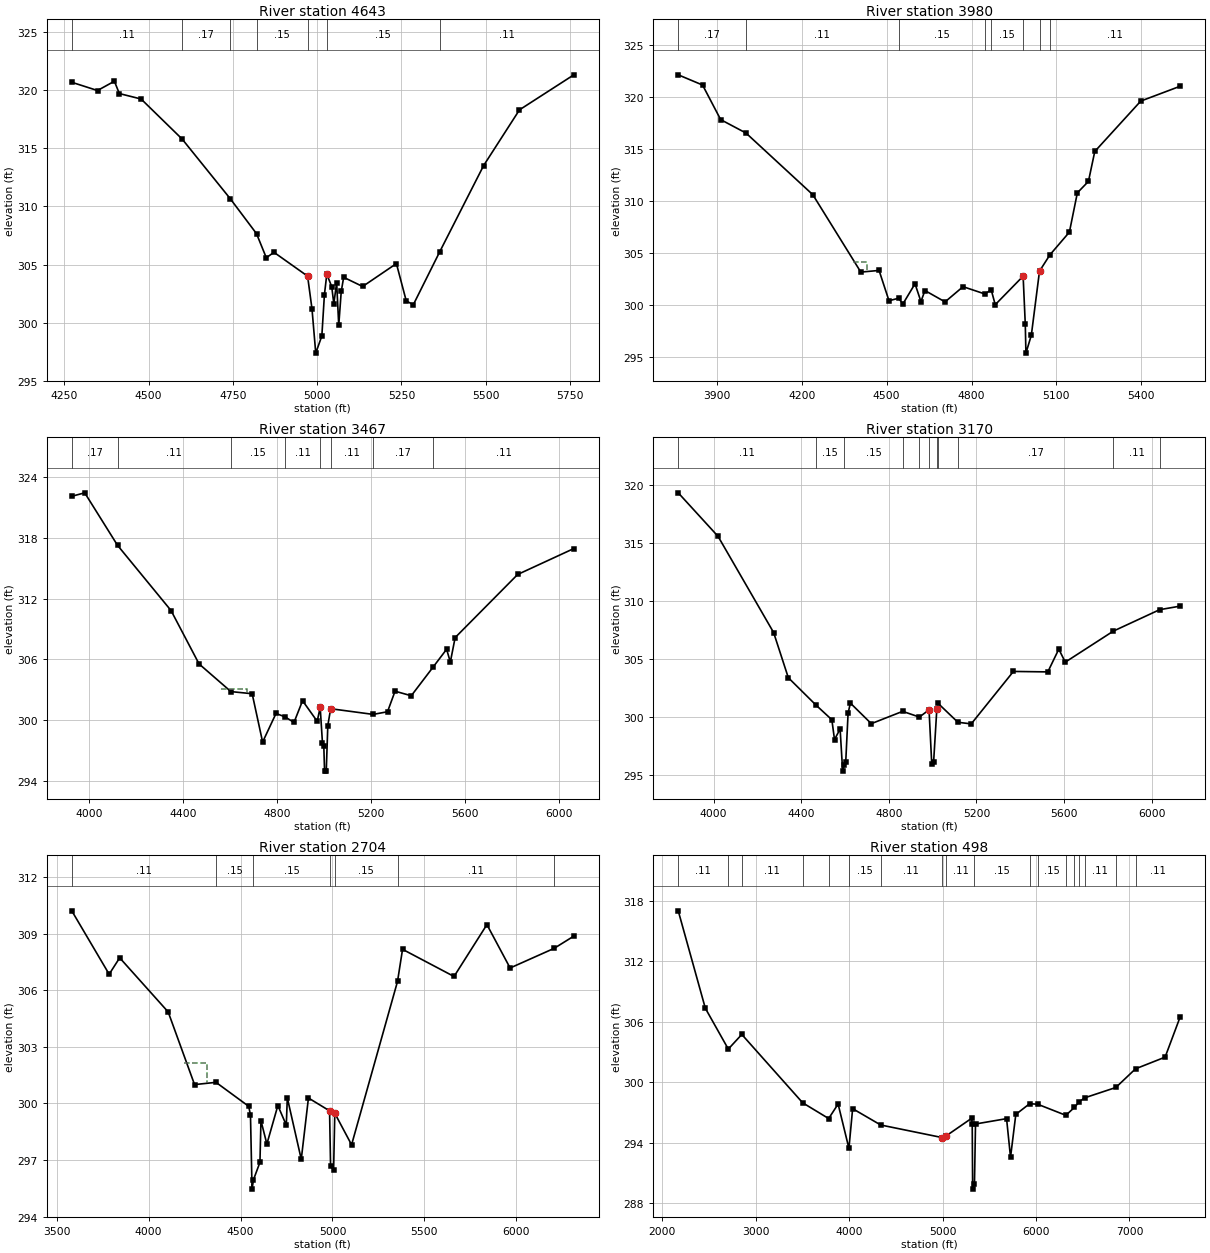
Type RM Length L Ch R = 1 ,4643    ,663,663,663
BEGIN DESCRIPTION:
NEELY SPRING BRANCH 6.0
END DESCRIPTION:
XS GIS Cut Line= 2
      3718724.83     10253872.11      3717835.94     10252677.66
#Sta/Elev= 30
  4272.2  320.68  4348.5  319.97  4398.6  320.77  4413.2  319.71  4477.8  319.24
  4599.4   315.8  4742.4  310.66  4820.1  307.66  4849.1  305.59  4871.8  306.06
  4971.5  304.01  4984.6  301.19  4995.7  297.39  5013.8  298.87  5021.4  302.41
  5028.5  304.17  5043.1  303.11  5049.3  301.63  5057.7  303.46  5063.9  299.77
  5071.3  302.69  5078.5  303.91  5134.8  303.12  5234.9  305.09  5264.1  301.88
    5285  301.55  5363.1  306.09  5493.6  313.52  5599.9  318.31  5761.1  321.32
#Mann= 7 ,-1 , 0
  4272.2     .11       0  4599.4     .17       0  4742.4     .11       0
  4820.1     .15       0  4971.5     .09       0  5028.5     .15       0
  5363.1     .11       0
Bank Sta=4971.5,5028.5
XS Rating Curve= 0 ,0
Exp/Cntr=0.3,0.1

Type RM Length L Ch R = 1 ,3980    ,513,513,513
BEGIN DESCRIPTION:
NEELY SPRING BRANCH 5.0
END DESCRIPTION:
XS GIS Cut Line= 3
      3719440.14     10253580.48      3718514.03     10252760.74
      3718031.65     10252522.06
#Sta/Elev= 30
  3763.2   322.1  3849.2  321.12  3913.2   317.8  4002.8  316.51    4239  310.59
  4408.7  303.16  4473.2  303.32  4508.3  300.41  4542.1  300.65  4557.6  300.11
  4600.3  302.04  4621.2  300.33  4635.4  301.39  4706.5   300.3  4770.1  301.76
  4847.3  301.06  4869.6  301.46  4883.9  300.03  4982.5  302.77  4990.1  298.16
  4992.4  295.38  5011.5   297.1  5040.4  303.25  5077.3  304.82  5146.1     307
  5174.2  310.77  5213.4  311.87  5235.8  314.74  5398.4  319.58  5538.2  321.01
#Mann= 8 ,-1 , 0
  3763.2     .17       0  4002.8     .11       0  4542.1     .15       0
  4847.3     .11       0  4869.6     .15       0  4982.5     .09       0
  5040.4     .15       0  5077.3     .11       0
#XS Ineff= 1 ,-1
    4382  4430.5  304.09
Permanent Ineff=
       F
Bank Sta=4982.5,5040.4
XS Rating Curve= 0 ,0
Exp/Cntr=0.3,0.1

Type RM Length L Ch R = 1 ,3467    ,297,297,297
BEGIN DESCRIPTION:
NEELY SPRING BRANCH 4.0
END DESCRIPTION:
XS GIS Cut Line= 3
      3719440.16     10253580.52      3718849.86      10252365.2
      3718084.06      10252205.8
#Sta/Elev= 30
  3927.9   322.1  3982.9  322.44  4122.3  317.26  4349.7  310.82  4468.8  305.55
  4604.2  302.82  4694.4  302.61  4738.8  297.84  4795.7  300.66  4832.7  300.34
  4872.2  299.78  4908.5  301.92  4970.7  299.89  4983.4  301.26  4993.2  297.71
  4998.8  297.44    5002  294.97  5009.2  294.97  5015.8  299.47  5027.9  301.13
  5208.3  300.57  5269.5  300.83  5301.5  302.86  5370.4  302.41  5464.5  305.28
  5520.6     307  5536.4  305.73  5556.8  308.15  5822.4  314.38  6061.2  316.94
#Mann= 8 ,-1 , 0
  3927.9     .17       0  4122.3     .11       0  4604.2     .15       0
  4832.7     .11       0  4983.4     .07       0  5027.9     .11       0
  5208.3     .17       0  5464.5     .11       0
#XS Ineff= 2 ,-1
    4560  4671.8  303.03  5301.5    5388  302.86
Permanent Ineff=
       F       F
Bank Sta=4983.4,5027.9
XS Rating Curve= 0 ,0
Exp/Cntr=0.3,0.1

Type RM Length L Ch R = 1 ,3170    ,466,466,466
BEGIN DESCRIPTION:
NEELY SPRING BRANCH 3.0
END DESCRIPTION:
XS GIS Cut Line= 3
      3719679.73     10253462.46      3719360.27     10252559.64
      3718276.96      10251778.4
#Sta/Elev= 30
  3838.2   319.3    4020  315.55  4273.9  307.26    4341  303.37  4468.5  300.99
  4539.8  299.75    4552  298.04  4577.6  298.95  4589.2  295.32  4596.9  295.82
  4603.2  296.07    4614  300.32  4624.6  301.18  4720.1  299.41  4863.1  300.47
  4939.7  299.98  4983.8   300.6  4996.2  295.91  5004.7  296.12  5019.4  300.68
  5025.6  301.15  5115.6  299.53  5176.5  299.39  5369.2  303.91  5526.3  303.87
  5576.5  305.83    5606  304.71  5825.2  307.38    6037  309.23  6131.5  309.54
#Mann= 11 ,-1 , 0
  3838.2     .11       0  4468.5     .15       0  4596.9     .15       0
  4863.1     .11       0  4939.7     .15       0  4983.8     .09       0
  5019.4     .12       0  5025.6     .15       0  5115.6     .17       0
  5825.2     .11       0    6037     .17       0
Bank Sta=4983.8,5019.4
XS Rating Curve= 0 ,0
Exp/Cntr=0.3,0.1

Type RM Length L Ch R = 1 ,2704    ,2206,2206,2206
BEGIN DESCRIPTION:
NEELY SPRING BRANCH 2.0
END DESCRIPTION:
XS GIS Cut Line= 3
      3720110.29     10253465.92      3719488.75     10252111.73
      3718308.19     10251726.31
#Sta/Elev= 30
  3581.5  310.21  3784.9  306.85  3842.2  307.72  4106.1  304.85  4249.6     301
  4366.2  301.12  4544.1  299.85  4553.9  299.39  4562.4  295.46  4570.2  295.96
  4605.4  296.88  4610.9  299.09  4643.1  297.85  4702.9  299.89  4748.8  298.85
  4754.3   300.3  4830.2  297.04  4869.3  300.29  4984.2  299.61  4989.7  296.67
  5006.2  296.49  5012.7  299.48    5104  297.81    5354  306.47  5381.3  308.17
  5661.5  306.73  5840.4  309.48  5966.6  307.18  6205.9  308.22  6313.4  308.87
#Mann= 7 ,-1 , 0
  3581.5     .11       0  4366.2     .15       0  4570.2     .15       0
  4984.2     .09       0  5012.7     .15       0    5354     .11       0
  6205.9     .17       0
#XS Ineff= 1 ,-1
    4191  4318.5  302.15
Permanent Ineff=
       F
Bank Sta=4984.2,5012.7
XS Rating Curve= 0 ,0
Exp/Cntr=0.3,0.1

Type RM Length L Ch R = 1 ,498     ,0,0,0
BEGIN DESCRIPTION:
NEELY SPRING BRANCH 1.0
END DESCRIPTION:
XS GIS Cut Line= 3
      3721667.82     10253211.04      3719666.75     10251210.32
      3717867.83     10249411.05
#Sta/Elev= 30
  2170.3     317  2460.2  307.34  2706.2  303.29  2850.7  304.74  3502.4  297.96
  3780.4   296.4  3881.5  297.84  3997.3  293.44    4037  297.38  4337.6  295.76
  4991.6  294.52  5041.1   294.7  5309.8  296.42  5316.9   295.9  5321.6   289.4
    5341   289.9  5352.2  295.86  5684.6  296.39    5727  292.56  5783.6  296.81
  5931.3  297.87  6017.2  297.82  6319.4  296.72  6410.2   297.5  6463.9  298.07
  6519.1  298.45  6854.2  299.48  7064.8  301.33  7381.6  302.49  7544.3  306.52
#Mann= 18 ,-1 , 0
  2170.3     .11       0  2706.2     .17       0  2850.7     .11       0
  3502.4     .15       0  3780.4     .17       0  3997.3     .15       0
  4337.6     .11       0  4991.6     .09       0  5041.1     .11       0
    5341     .15       0  5931.3     .11       0  6017.2     .15       0
  6319.4     .17       0  6410.2     .15       0  6463.9     .17       0
  6519.1     .11       0  6854.2     .15       0  7064.8     .11       0
Bank Sta=4991.6,5041.1
XS Rating Curve= 0 ,0
Exp/Cntr=0.3,0.1

Chan Stop Cuts=-1
Use User Specified Reach Order=0
Composite Channel Slope=5