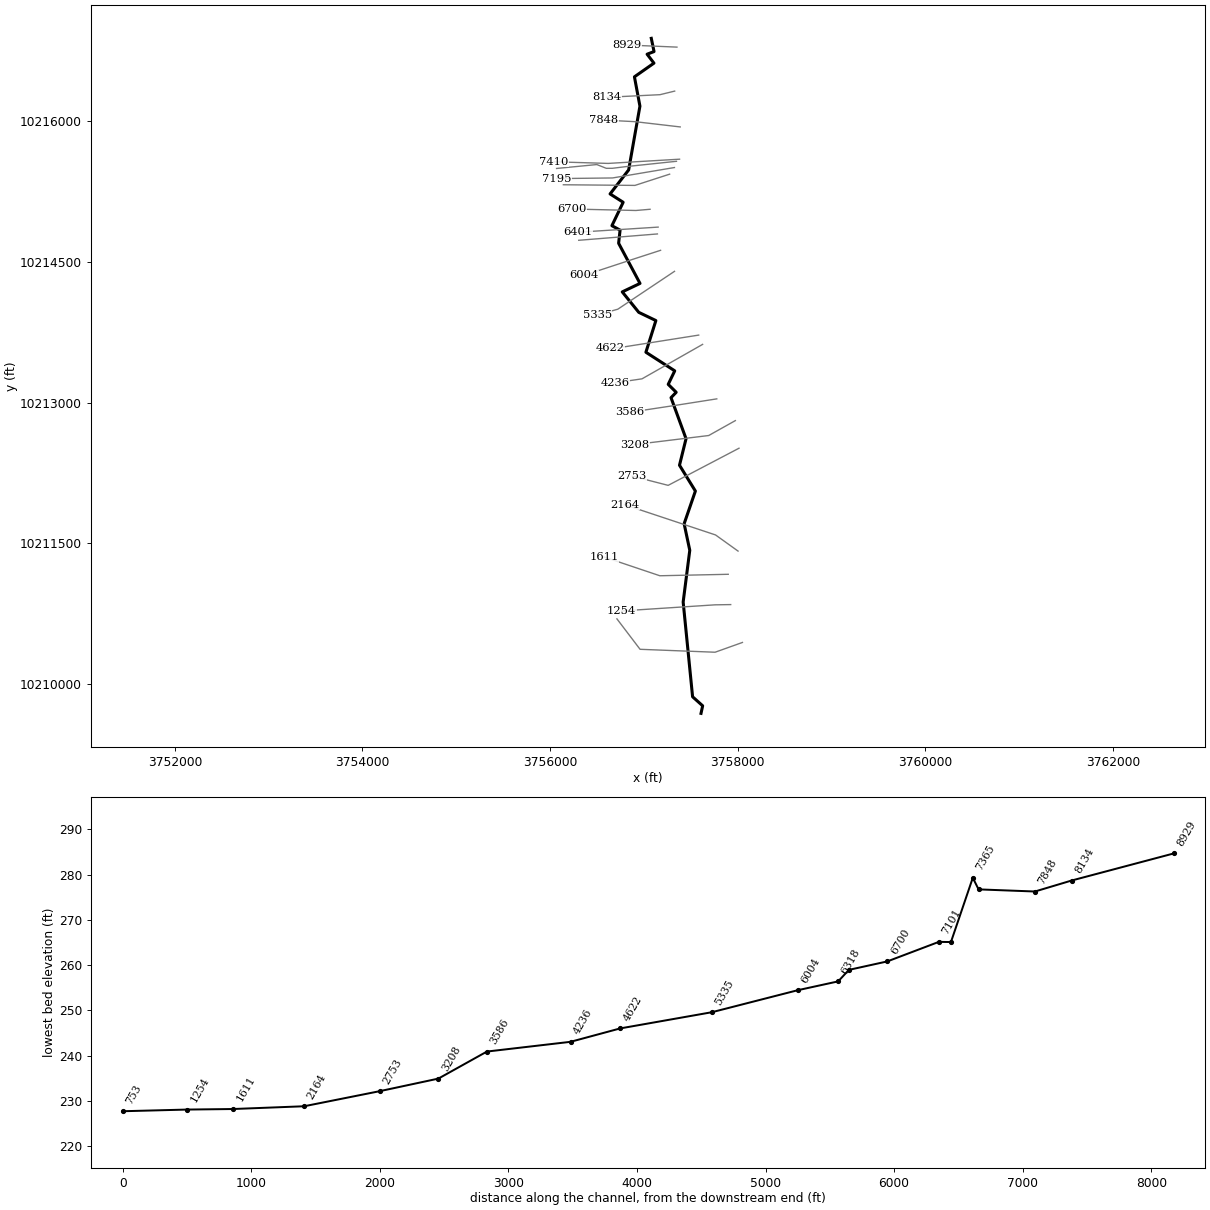
--- POLECAT BRANCH.prj (project) ---

Proj Title=POLECAT BRANCH Base Level Engineering
Current Plan=p01
Default Exp/Contr=0.3,0.1
English Units
Geom File=g01
Flow File=f01
Plan File=p01
Y Axis Title=Elevation
X Axis Title(PF)=Main Channel Distance
X Axis Title(XS)=Station
BEGIN DESCRIPTION:
POLECAT BRANCH
END DESCRIPTION:
DSS Export Rating Curves= 0
DSS Export Rating Curve Sorted= 0
DSS Export Volume Flow Curves= 0
DXF OffsetX= 0
DXF OffsetY= 0
DXF ScaleX= 1
DXF ScaleY= 10

--- POLECAT BRANCH.p01 (plan) ---

Plan Title=Multiple Run
Program Version=4.10
Short Identifier=Multiple
Geom File=g01
Flow File=f01
Subcritical Flow
K Sum by GR= 0
Std Step Tol= 0.01
Critical Tol= 0.01
Num of Std Step Trials= 20
Max Error Tol= 0.3
Flow Tol Ratio= 0.001
Split Flow NTrial= 30
Split Flow Tol= 0.02
Split Flow Ratio= 0.02
Log Output Level= 0
Friction Slope Method= 1
Unsteady Friction Slope Method= 2
Unsteady Bridges Friction Slope Method= 1
Parabolic Critical Depth
Global Vel Dist= 1 , 1 , 1
Global Log Level= 0
CheckData=True
Encroach Param=-1 ,0,0, 0
BEGIN DESCRIPTION:
Multiple Run
END DESCRIPTION:
Computation Interval=1HOUR
Output Interval=1HOUR
Run HTab= 0
Run UNet= 0
Run PostProcess= 0
Run WQNet= 0
UNET Theta= 1
UNET Theta Warmup= 1
UNET ZTol= 0.02
UNET ZSATol= 0.05
UNET MxIter= 20
UNET MaxInSteps= 0
UNET DtIC= 0
UNET DtMin= 0
UNET MaxCRTS= 20
UNET WFStab= 2
UNET SFStab= 1
UNET WFX= 1
UNET SFX= 1
UNET DSS MLevel= 4
UNET DZMax Abort= 100
UNET Convert EG Bridges= 0
UNET Use Existing IB Tables=-1
UNET Froude Reduction=False
UNET Froude Limit= 1
UNET Froude Power= 10
UNET Time Slicing=0,0, 5
UNET Junction Losses=0
Instantaneous Interval=1HOUR
Write IC File= 0
Write IC File at Sim End=0
Echo Input=False
Echo Parameters=False
Echo Output=False
Write Detailed= 0
WQ AD Non Conservative
WQ ULTIMATE=-1
WQ Max Comp Step=1HOUR
WQ Output Interval=15MIN
WQ Output Selected Increments= 0
WQ Output face flow=0
WQ Output face velocity=0
WQ Output face area=0
WQ Output face dispersion=0
WQ Output cell volume=0
WQ Output cell surface area=0
WQ Output cell continuity=0
WQ Output cumulative cell continuity=0
WQ Output face conc=0
WQ Output face dconc_dx=0
WQ Output face courant=0
WQ Output face peclet=0
WQ Output face adv mass=0
WQ Output face disp mass=0
WQ Output cell mass=0
WQ Output cell source sink temp=0
WQ Output cell source sink nsm=0
WQ Output MaxMinRange=-1
WQ Daily Max Min Mean=-1
WQ Daily Range=0
WQ Daily Time=0
WQ Create Restart=0
WQ Fixed Restart=0
WQ System Summary=0
WQ Use Fixed Temperature=0
Sorting and Armoring Iterations= 10
XS Update Threshold= 0.02
Hydraulics Update Threshold= 0.02
Energy Slope Method= 1
Volume Change Method= 0
XS Weighting Method= 0
Number of US Weighted Cross Sections= 1
Number of DS Weighted Cross Sections= 1
Upstream XS Weight=0.25
Main XS Weight=0.5
Downstream XS Weight=0.25
Number of DS XS's Weighted with US Boundary= 1
Upstream Boundary Weight= 1
Weight of XSs Associated with US Boundary= 0
Number of US XS's Weighted with DS Boundary= 1
Downstream Boundary Weight= 0.5
Weight of XSs Associated with DS Boundary= 0.5
Sediment Output Level= 4
Mass or Volume Output= 0
Output Increment Type= 1
Profile and TS Output Increment= 10
XS Output Flag= 0
XS Output Increment= 10
Disregard all LS=0
Disregard all Conn=0
Disregard all Breaches=0
Disregard all Pumps=0

--- POLECAT BRANCH.f01 (steady flow) ---

Flow Title=Multiple
Program Version=4.10
Number of Profiles= 7
Profile Names=10-year,25-year,50-year,1pct_min,100-year,1pct_plu,500-year
River Rch & RM=POLECAT BRANCH,Reach-1         ,8929
     482     645     865     383    1156    3491    2129
River Rch & RM=POLECAT BRANCH,Reach-1         ,4236
     587     792    1068     474    1431    4322    2659
Boundary for River Rch & Prof#=POLECAT BRANCH,Reach-1         , 1
Up Type= 0
Dn Type= 3
Dn Slope=0.001
Boundary for River Rch & Prof#=POLECAT BRANCH,Reach-1         , 2
Up Type= 0
Dn Type= 3
Dn Slope=0.001
Boundary for River Rch & Prof#=POLECAT BRANCH,Reach-1         , 3
Up Type= 0
Dn Type= 3
Dn Slope=0.001
Boundary for River Rch & Prof#=POLECAT BRANCH,Reach-1         , 4
Up Type= 0
Dn Type= 3
Dn Slope=0.001
Boundary for River Rch & Prof#=POLECAT BRANCH,Reach-1         , 5
Up Type= 0
Dn Type= 3
Dn Slope=0.001
Boundary for River Rch & Prof#=POLECAT BRANCH,Reach-1         , 6
Up Type= 0
Dn Type= 3
Dn Slope=0.001
Boundary for River Rch & Prof#=POLECAT BRANCH,Reach-1         , 7
Up Type= 0
Dn Type= 3
Dn Slope=0.001
DSS Import GetInterval= 0
DSS Import GetPeak= 0
DSS Import FillOption= 0

--- POLECAT BRANCH.g01 (geometry) ---

Geom Title=Existing Conditions
Program Version=4.10

River Reach=POLECAT BRANCH  ,Reach-1
Reach XY= 30
      3757078.23     10216881.84      3757107.53     10216740.76
      3757033.55     10216712.81      3757106.49     10216617.36
      3756898.55     10216471.63      3756957.09     10216158.98
      3756836.97     10215479.34      3756639.01     10215223.36
       3756778.4     10215134.54       3756658.4     10214884.73
      3756745.49     10214837.61      3756730.01     10214697.65
      3756957.95     10214269.66      3756768.78      10214179.3
       3756944.7     10213961.39      3757127.11     10213873.72
      3757020.73     10213536.01      3757328.14     10213337.82
      3757258.57     10213193.79      3757343.73     10213109.28
      3757288.61     10213051.86      3757448.55     10212614.21
      3757378.83     10212331.85      3757548.22     10212056.46
      3757428.24     10211707.86      3757488.37     10211425.15
      3757417.95     10210873.82      3757518.39      10209863.8
      3757625.69     10209767.62      3757608.23     10209686.84

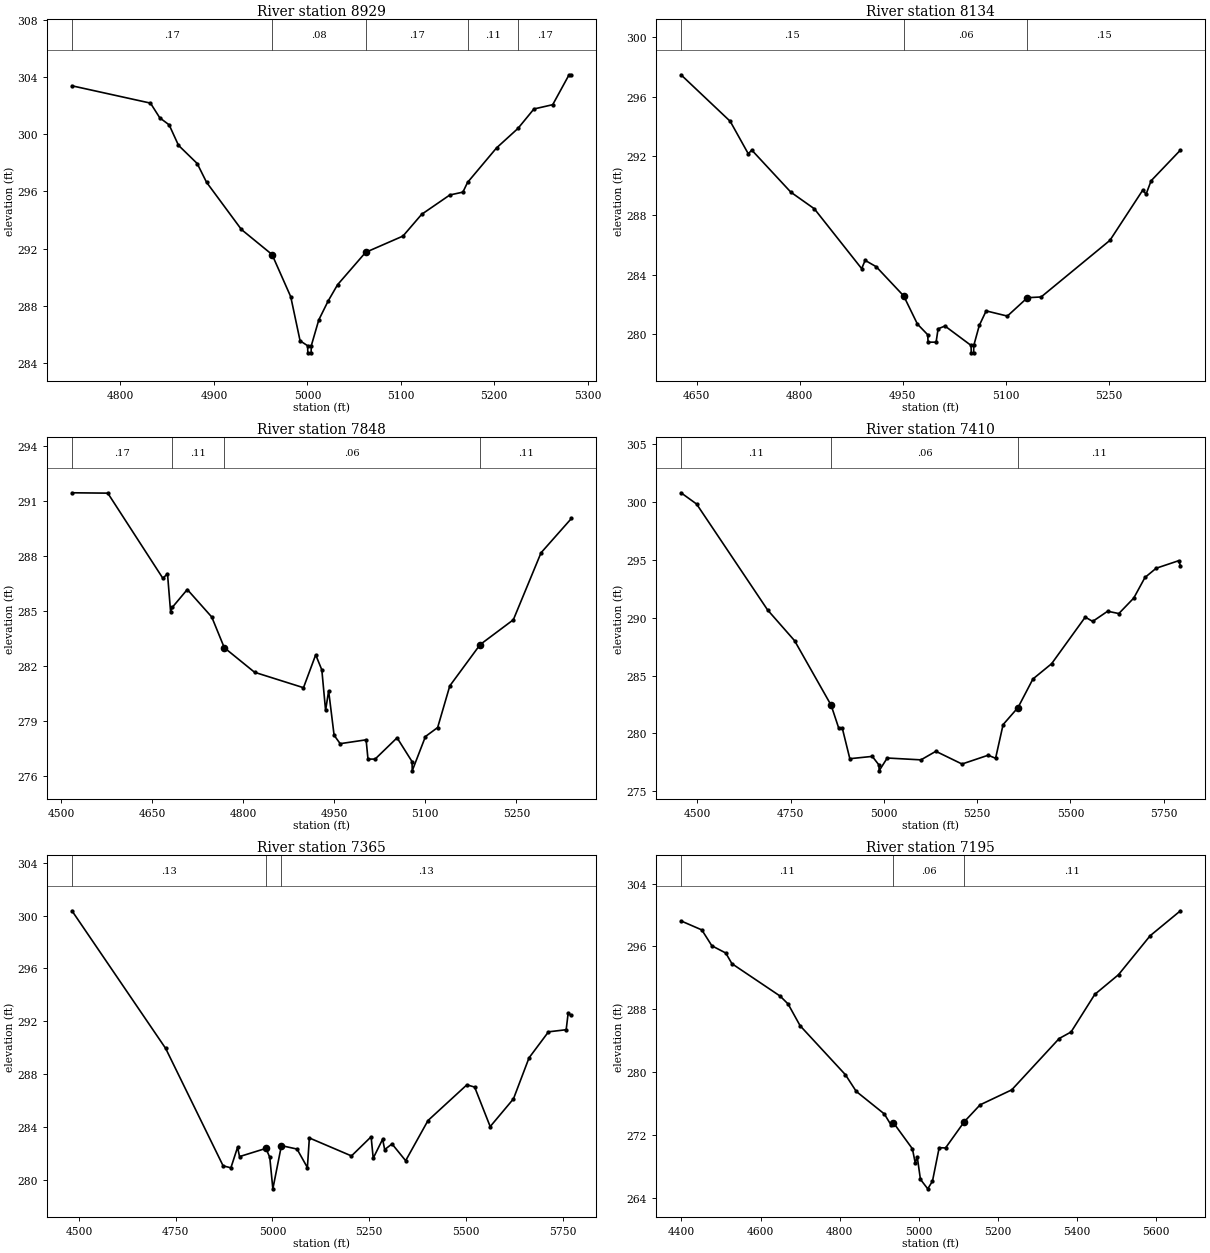
Type RM Length L Ch R = 1 ,8929    ,795,795,795
BEGIN DESCRIPTION:
POLECAT BRANCH 17.0
END DESCRIPTION:
XS GIS Cut Line= 2
      3757351.75     10216788.23      3756817.83     10216811.07
#Sta/Elev= 30
  4748.1  303.37  4832.1  302.16  4842.1  301.13  4852.1  300.64  4862.1  299.21
  4882.1  297.94  4892.1  296.63  4929.4  293.33  4962.2  291.58  4982.2  288.63
  4992.2  285.55  5000.2  285.21  5000.5  284.71    5004  284.71  5004.2  285.21
  5012.2  287.01  5022.2  288.33  5032.3  289.47  5062.3  291.73  5102.3  292.87
  5122.3  294.39  5152.4  295.74  5166.4  295.94  5171.4  296.62  5202.4  299.03
  5225.3  300.39  5242.4  301.75  5262.5  302.05    5280  304.14  5282.5  304.14
#Mann= 5 ,-1 , 0
  4748.1     .17       0  4962.2     .08       0  5062.3     .17       0
  5171.4     .11       0  5225.3     .17       0
Bank Sta=4962.2,5062.3
XS Rating Curve= 0 ,0
Exp/Cntr=0.3,0.1

Type RM Length L Ch R = 1 ,8134    ,286,286,286
BEGIN DESCRIPTION:
POLECAT BRANCH 16.0
END DESCRIPTION:
XS GIS Cut Line= 3
      3757327.46     10216319.48       3757171.2     10216281.28
      3756605.24      10216253.5
#Sta/Elev= 30
  4627.2  297.48  4698.9  294.34  4725.2  292.15  4730.3   292.4  4787.2  289.56
  4821.4  288.44  4890.4   284.4  4895.4  284.96  4911.6  284.53  4951.6  282.56
  4971.6  280.66  4986.6  279.94  4987.1  279.44  4998.8  279.44  5001.7  280.34
  5011.7  280.53  5049.7  279.22    5050  278.72  5053.5  278.72  5053.7  279.22
  5061.7  280.57  5071.7  281.55  5102.6   281.2  5131.8  282.44  5151.8  282.49
    5252  286.31  5299.7  289.69  5304.7  289.43    5312  290.33  5354.7   292.4
#Mann= 3 , 0 , 0
  4627.2     .15       0  4951.6     .06       0  5131.8     .15       0
Bank Sta=4951.6,5131.8
XS Rating Curve= 0 ,0
Exp/Cntr=0.3,0.1

Type RM Length L Ch R = 1 ,7848    ,438,438,438
BEGIN DESCRIPTION:
POLECAT BRANCH 15.0
END DESCRIPTION:
XS GIS Cut Line= 3
      3757386.49     10215937.53      3756907.94     10215993.38
       3756567.9     10216011.07
#Sta/Elev= 30
  4518.2  291.44  4577.2  291.42  4667.9  286.78  4675.5  287.03  4680.6  284.96
  4683.5   285.2  4708.1  286.17  4748.4  284.67    4769     283  4818.9  281.66
  4899.4  280.82  4919.5  282.61  4929.6  281.79  4935.8  279.58  4940.8  280.65
  4949.8  278.23  4959.8  277.77  5002.5  277.98  5005.6  276.93  5017.3  276.93
  5053.5  278.09  5078.2  276.79  5078.4  276.29  5100.2  278.16  5120.3  278.65
  5140.3  280.92  5190.3  283.17  5244.9  284.52  5290.5  288.17  5340.5  290.04
#Mann= 4 ,-1 , 0
  4518.2     .17       0  4683.5     .11       0    4769     .06       0
  5190.3     .11       0
Bank Sta=4769,5190.3
XS Rating Curve= 0 ,0
Exp/Cntr=0.3,0.1

Type RM Length L Ch R = 1 ,7410    ,45,45,45
BEGIN DESCRIPTION:
POLECAT BRANCH 14.0
END DESCRIPTION:
XS GIS Cut Line= 4
      3757379.52     10215593.78      3756907.31       10215566.
      3756619.11     10215548.64      3756042.82       10215566.
#Sta/Elev= 30
  4456.3  300.82    4498  299.85  4688.4  290.68  4760.7  288.02  4858.7  282.43
  4878.7  280.48  4888.7  280.43  4908.7  277.81  4968.9  278.01  4986.9  277.26
  4987.1  276.76  5008.9  277.87  5099.3  277.71  5139.2  278.45  5209.3  277.35
  5279.3  278.11  5299.3  277.85  5319.4  280.76  5359.4  282.24  5399.4  284.71
  5449.4  286.03  5539.5  290.06  5559.5  289.69  5599.5  290.57  5629.5  290.37
  5669.5  291.71  5699.5  293.49  5729.5  294.29  5789.6  294.94  5794.6  294.51
#Mann= 3 ,-1 , 0
  4456.3     .11       0  4858.7     .06       0  5359.4     .11       0
Bank Sta=4858.7,5359.4
XS Rating Curve= 0 ,0
Exp/Cntr=0.3,0.1

Type RM Length L Ch R = 1 ,7365    ,170,170,170
BEGIN DESCRIPTION:
Mapping XS bb06be0d
END DESCRIPTION:
XS GIS Cut Line= 6
      3757346.57     10215571.21      3756803.14     10215513.92
      3756662.52     10215496.56      3756598.28     10215496.56
      3756497.59     10215536.49       3756068.8     10215494.83
#Sta/Elev= 30
  4481.5  300.36  4723.9  289.94  4872.4  281.06  4892.5  280.91  4909.8  282.47
  4914.8  281.76    4983  282.38    4993  281.71    5001  279.32  5023.1  282.59
  5063.5  282.33  5090.3  280.93  5095.4  283.17  5204.3  281.81  5255.1  283.26
  5260.5  281.64  5284.8  283.07  5290.2  282.29  5309.1  282.72  5344.4  281.45
  5402.2  284.49  5502.7  287.19  5522.8  287.02    5563  284.03  5623.2  286.13
  5663.4  289.23  5713.7   291.2  5759.5  291.36  5764.5  292.59    5773  292.44
#Mann= 3 , 0 , 0
  4481.5     .13       0    4983     .06       0  5023.1     .13       0
Bank Sta=4983,5023.1
XS Rating Curve= 0 ,0
Exp/Cntr=0.3,0.1

Type RM Length L Ch R = 1 ,7195    ,94,94,94
BEGIN DESCRIPTION:
Mapping XS bf7a0d4b
END DESCRIPTION:
XS GIS Cut Line= 3
      3757324.91      10215504.8      3756665.16     10215393.69
      3756071.24     10215386.76
#Sta/Elev= 30
  4398.9  299.25  4451.6   298.1    4477  296.08  4512.1  295.16  4527.7   293.8
  4649.4  289.68  4669.7  288.67  4700.1   285.9  4814.8  279.65  4842.1  277.53
  4913.1  274.66  4930.7   273.2  4935.8  273.56  4984.1  270.22  4991.3  268.41
  4996.3   269.2  5004.4  266.33  5022.9  265.12  5034.8  266.09  5051.8  270.36
  5067.9  270.33  5115.3  273.67  5155.3  275.82  5235.3  277.73  5355.3  284.27
  5385.3   285.1  5445.3  289.89  5505.3   292.4  5585.3  297.36  5661.9  300.54
#Mann= 3 , 0 , 0
  4398.9     .11       0  4935.8     .06       0  5115.3     .11       0
Bank Sta=4935.8,5115.3
XS Rating Curve= 0 ,0
Exp/Cntr=0.3,0.1

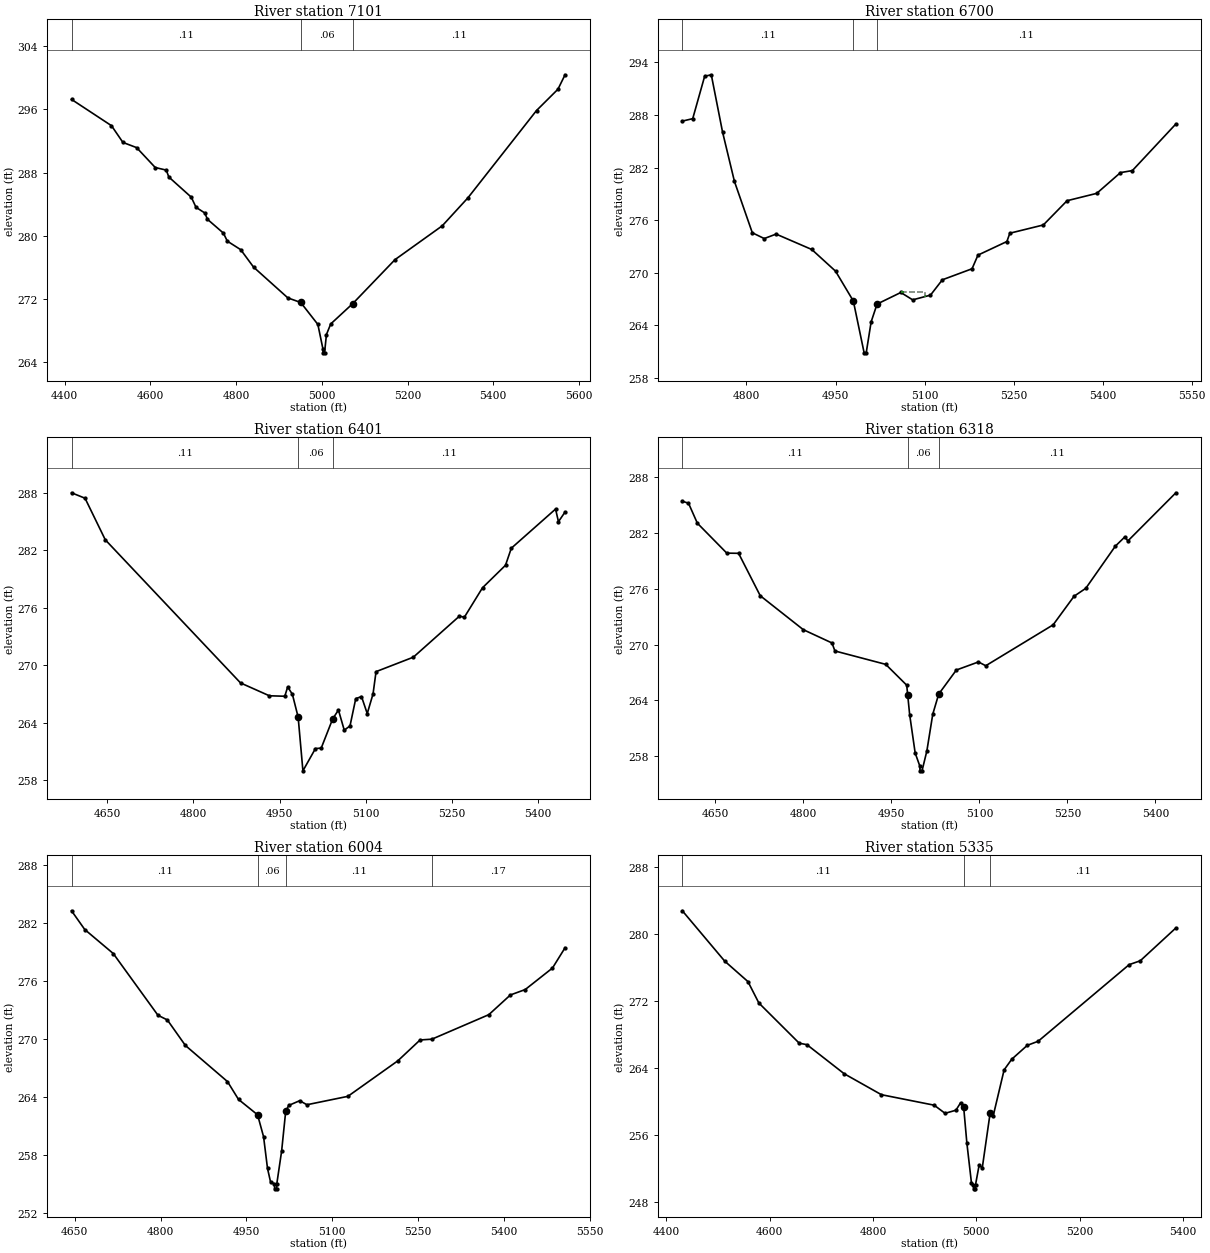
Type RM Length L Ch R = 1 ,7101    ,401,401,401
BEGIN DESCRIPTION:
POLECAT BRANCH 13.0
END DESCRIPTION:
XS GIS Cut Line= 3
      3757273.67     10215434.07      3756903.84     10215314.27
      3756141.22      10215321.2
#Sta/Elev= 30
  4416.1  297.27  4509.3  293.94    4536  291.82    4568  291.16  4611.4  288.64
  4637.2  288.31    4643  287.44  4695.5  284.88  4706.5   283.6    4727  282.88
  4733.2  282.08  4770.4  280.33  4779.6  279.31  4810.8  278.23  4840.8  276.02
  4920.8  272.12  4950.8  271.54  4990.8  268.76  5002.6  265.66  5002.9  265.16
  5006.4  265.16  5010.8  267.48  5020.8  268.82 5072.41  271.41  5170.8  276.97
  5280.9  281.25  5340.9   284.8  5500.9  295.86  5550.9  298.56  5567.5  300.39
#Mann= 3 , 0 , 0
  4416.1     .11       0  4950.8     .06       0 5072.41     .11       0
Bank Sta=4950.8,5072.41
XS Rating Curve= 0 ,0
Exp/Cntr=0.3,0.1

Type RM Length L Ch R = 1 ,6700    ,299,299,299
BEGIN DESCRIPTION:
POLECAT BRANCH 12.0
END DESCRIPTION:
XS GIS Cut Line= 3
      3757065.32     10215059.93      3756914.25     10215046.91
      3756234.56     10215062.53
#Sta/Elev= 30
  4691.9   287.3  4709.4  287.58  4729.5  292.42  4740.7  292.59  4759.6  286.07
  4779.7  280.41  4809.8  274.55  4829.9  273.89  4849.9   274.4    4910  272.64
    4950  270.17    4980  266.76  4998.2  260.84  5001.7  260.84    5010  264.38
    5020  266.41    5060  267.73    5080  266.89    5110  267.43    5130  269.18
    5180  270.44    5190     272  5238.7  273.55  5243.7   274.5  5300.1  275.44
  5340.1  278.21  5390.1  279.05  5430.1  281.42  5450.1  281.65  5523.4  286.97
#Mann= 3 , 0 , 0
  4691.9     .11       0    4980     .06       0    5020     .11       0
#XS Ineff= 1 ,-1
    5060    5100  267.73
Permanent Ineff=
       F
Bank Sta=4980,5020
XS Rating Curve= 0 ,0
Exp/Cntr=0.3,0.1

Type RM Length L Ch R = 1 ,6401    ,83,83,83
BEGIN DESCRIPTION:
Mapping XS d560baf9
END DESCRIPTION:
XS GIS Cut Line= 2
      3757151.26     10214869.82       3756294.5     10214815.14
#Sta/Elev= 30
  4588.2  288.01  4611.7  287.44  4646.9   283.1  4882.2  268.15  4932.3  266.81
  4959.2  266.76  4964.2  267.74  4972.4  266.96  4982.4  264.58  4990.7  258.97
  5012.5   261.3  5022.5  261.34  5042.5   264.4  5052.5  265.32  5062.6  263.22
  5072.6  263.66  5082.6  266.51  5092.6  266.73  5102.6  264.95  5112.7  267.01
  5117.9  269.33  5182.8  270.84    5263  275.13  5271.5  275.01  5303.1  278.09
  5343.1  280.44  5353.2  282.22  5430.2  286.31  5435.2  284.99  5446.7     286
#Mann= 3 , 0 , 0
  4588.2     .11       0  4982.4     .06       0  5042.5     .11       0
#XS Ineff= 1 ,-1
  5052.5    5079  265.32
Permanent Ineff=
       F
Bank Sta=4982.4,5042.5
XS Rating Curve= 0 ,0
Exp/Cntr=0.3,0.1

Type RM Length L Ch R = 1 ,6318    ,314,314,314
BEGIN DESCRIPTION:
Mapping XS 5ff691c9
END DESCRIPTION:
XS GIS Cut Line= 2
      3757143.42     10214796.91      3756304.85      10214729.2
#Sta/Elev= 30
  4593.6  285.42  4604.1  285.21  4619.2  283.06  4669.4  279.84  4689.5  279.82
  4726.4  275.26  4799.8  271.61  4848.7  270.18  4853.7  269.32  4940.3  267.88
  4976.1  265.64  4977.7 264.629  4981.1  262.48  4990.5  258.35  4998.5  256.93
  4998.7  256.43  5002.2  256.43  5010.5  258.59  5020.5  262.52  5030.6  264.68
  5060.7  267.27  5098.4  268.14  5110.8  267.73  5225.7  272.13  5261.3   275.2
  5281.4  276.06  5331.6  280.58    5348  281.59  5353.1  281.15  5434.9  286.33
#Mann= 3 , 0 , 0
  4593.6     .11       0  4977.7     .06       0  5030.6     .11       0
Bank Sta=4977.7,5030.6
XS Rating Curve= 0 ,0
Exp/Cntr=0.3,0.1

Type RM Length L Ch R = 1 ,6004    ,669,669,669
BEGIN DESCRIPTION:
POLECAT BRANCH 11.0
END DESCRIPTION:
XS GIS Cut Line= 3
      3757177.25     10214622.42      3756896.02     10214531.28
      3756356.99     10214354.21
#Sta/Elev= 30
  4644.2  283.28  4667.3  281.34  4717.2  278.85  4795.3  272.46  4811.8  271.97
  4843.3  269.33  4916.9  265.59  4936.2  263.74  4969.5  262.15    4980  259.88
  4986.9  256.59  4992.2   255.2  4999.1  254.98  4999.3  254.48  5002.8  254.48
  5003.1  254.98  5011.6   258.4  5018.7  262.51    5024  263.12  5043.2  263.61
  5055.8  263.19  5127.4  264.06  5214.8  267.74  5253.7   269.9  5274.3  269.98
  5373.9  272.52  5411.6  274.56  5437.5  275.12  5485.2  277.35  5507.2  279.45
#Mann= 4 ,-1 , 0
  4644.2     .11       0  4969.5     .06       0  5018.7     .11       0
  5274.3     .17       0
Bank Sta=4969.5,5018.7
XS Rating Curve= 0 ,0
Exp/Cntr=0.3,0.1

Type RM Length L Ch R = 1 ,5335    ,713,713,713
BEGIN DESCRIPTION:
POLECAT BRANCH 10.0
END DESCRIPTION:
XS GIS Cut Line= 3
      3757325.73     10214398.48      3756721.55     10213994.82
      3756501.57     10213932.71
#Sta/Elev= 30
  4431.2  282.75  4513.2  276.75  4558.2  274.31  4579.3  271.76  4657.4  266.97
  4672.4  266.79  4744.4  263.33  4816.5  260.83  4918.6  259.58  4939.7  258.61
  4960.7  258.98  4969.7  259.86  4975.7  259.35  4981.9  255.07  4990.7  250.36
  4994.7  250.11    4995  249.61  4998.5  249.61  4998.7  250.11  5005.7  252.46
  5011.7   252.1  5026.8  258.59  5032.8  258.29    5054  263.79  5068.8  265.06
  5098.8  266.71  5119.9   267.2    5296  276.33  5317.5  276.79  5386.4   280.7
#Mann= 3 , 0 , 0
  4431.2     .11       0  4975.7     .06       0  5026.8     .11       0
#XS Ineff= 1 ,-1
    4870  4969.7  259.86
Permanent Ineff=
       F
Bank Sta=4975.7,5026.8
XS Rating Curve= 0 ,0
Exp/Cntr=0.3,0.1

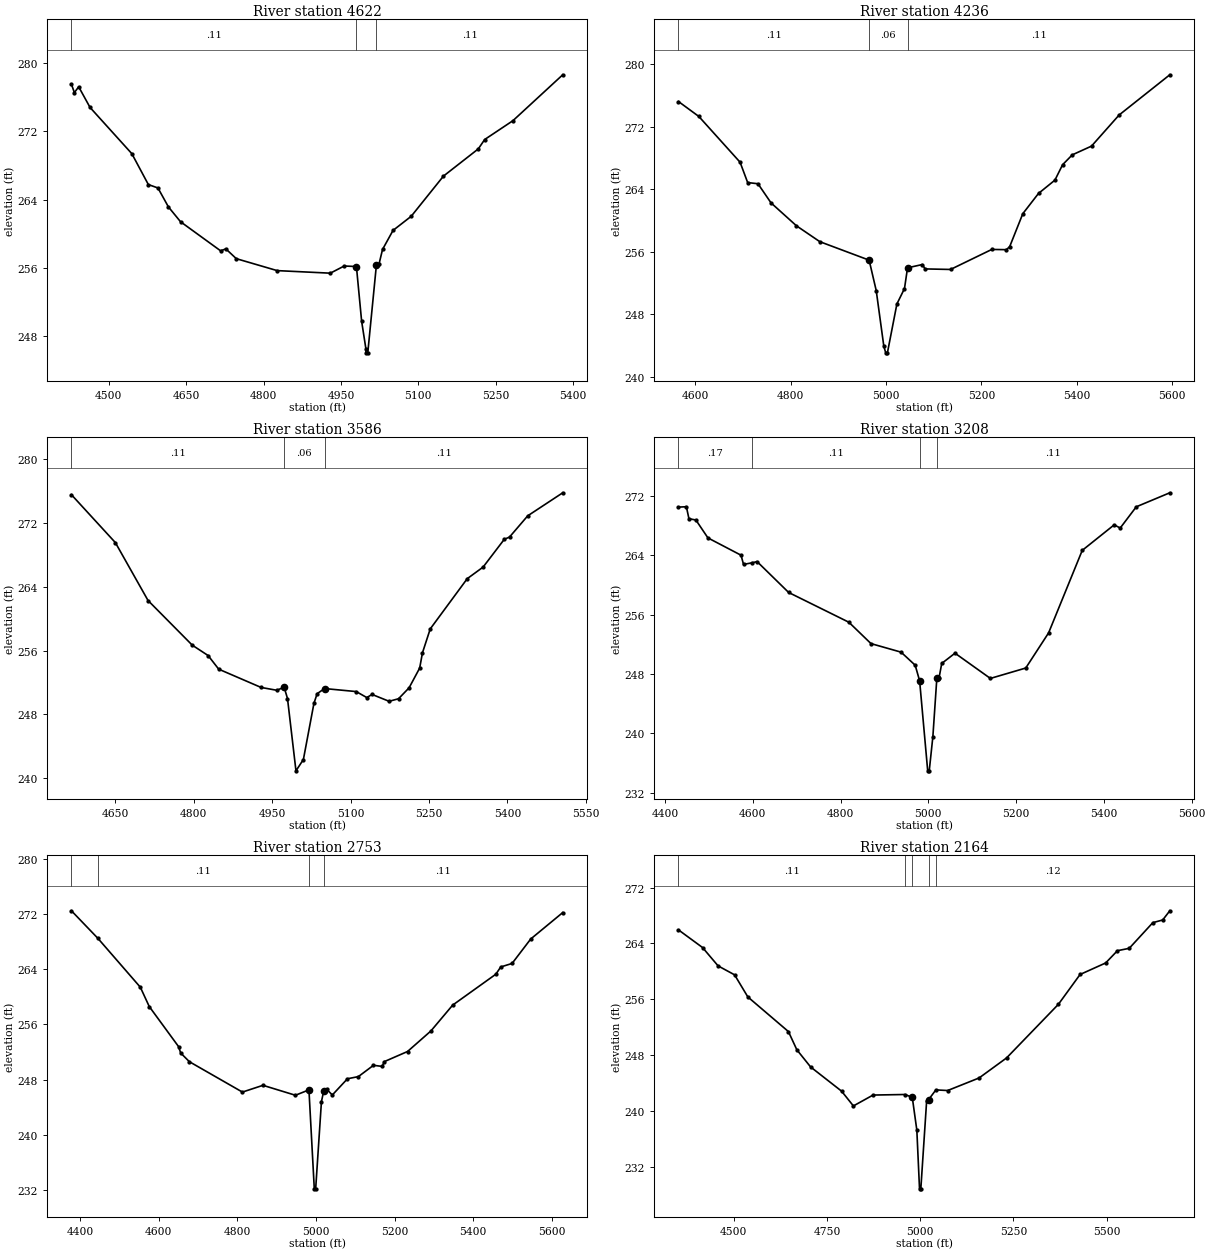
Type RM Length L Ch R = 1 ,4622    ,386,386,386
BEGIN DESCRIPTION:
POLECAT BRANCH 9.0
END DESCRIPTION:
XS GIS Cut Line= 3
      3757583.51     10213718.78      3756791.86     10213593.78
      3756641.82     10213578.26
#Sta/Elev= 30
  4427.7  277.53  4433.4  276.54  4441.8  277.22  4463.8   274.8  4544.8  269.38
  4576.8  265.76  4595.4  265.36  4615.7  263.14  4639.2   261.4  4716.9  257.99
    4727  258.22  4747.3  257.07  4826.5  255.67  4929.5  255.37  4956.4  256.21
  4980.1  256.15  4990.2  249.73  4998.4  246.53  4998.6  246.03  5002.1  246.03
  5018.8  256.31  5023.9  256.44  5030.7  258.15    5051  260.38  5086.3  262.04
  5148.8  266.75  5216.3  269.94  5228.7  271.04  5283.5  273.25    5380  278.63
#Mann= 3 , 0 , 0
  4427.7     .11       0  4980.1     .06       0  5018.8     .11       0
Bank Sta=4980.1,5018.8
XS Rating Curve= 0 ,0
Exp/Cntr=0.3,0.1

Type RM Length L Ch R = 1 ,4236    ,650,650,650
BEGIN DESCRIPTION:
POLECAT BRANCH 8.0
END DESCRIPTION:
XS GIS Cut Line= 3
      3757625.21     10213619.83      3756979.36     10213252.64
      3756695.54     10213210.97
#Sta/Elev= 30
    4565   275.2  4607.7  273.29  4694.1  267.44    4710  264.84  4731.6  264.69
    4759  262.24  4812.3  259.31  4861.3  257.28  4964.6  254.92  4979.5  251.02
  4995.4  243.91  4999.4  243.07  5002.9  243.07  5022.8  249.32  5038.7  251.29
  5045.1  253.94  5076.1  254.36  5081.9   253.8  5135.2  253.73  5221.7  256.29
  5252.2  256.26  5259.2  256.65  5286.7  260.86  5319.6  263.45    5354  265.15
  5370.1  267.12  5390.3  268.38  5430.7   269.5  5488.6  273.48  5594.8  278.62
#Mann= 3 , 0 , 0
    4565     .11       0  4964.6     .06       0  5045.1     .11       0
Bank Sta=4964.6,5045.1
XS Rating Curve= 0 ,0
Exp/Cntr=0.3,0.1

Type RM Length L Ch R = 1 ,3586    ,378,378,378
BEGIN DESCRIPTION:
POLECAT BRANCH 7.0
END DESCRIPTION:
XS GIS Cut Line= 3
      3757776.22     10213039.09       3757347.4     10212971.62
      3756847.19     10212895.96
#Sta/Elev= 30
  4565.9  275.55    4650  269.54  4712.5  262.28  4797.1  256.68  4827.4  255.38
  4847.7  253.67  4928.7  251.38    4959  251.02  4972.8  251.42  4979.3  249.99
  4995.5  240.92  5009.7  242.34  5029.9  249.39    5036  250.59  5050.1  251.24
  5110.8  250.86    5131  250.11  5141.1   250.5  5173.7  249.64  5191.7  249.96
  5211.9  251.33  5232.2  253.81  5237.5  255.72  5252.4  258.72  5323.2  265.02
  5353.5  266.47    5394  269.95  5404.1  270.24  5438.9   272.9  5505.9  275.79
#Mann= 3 , 0 , 0
  4565.9     .11       0  4972.8     .06       0  5050.1     .11       0
Bank Sta=4972.8,5050.1
XS Rating Curve= 0 ,0
Exp/Cntr=0.3,0.1

Type RM Length L Ch R = 1 ,3208    ,455,455,455
BEGIN DESCRIPTION:
POLECAT BRANCH 6.0
END DESCRIPTION:
XS GIS Cut Line= 3
      3757974.18     10212807.34       3757690.3     10212648.47
      3756902.06     10212552.22
#Sta/Elev= 30
  4430.8  270.47  4448.8  270.52  4454.6  268.91  4470.5  268.73  4497.9  266.32
  4573.3  263.99    4579  262.75  4597.9  262.96  4609.9  263.13  4681.8  258.97
    4819  254.96  4869.4  252.08  4937.9  250.93  4970.1  249.17  4980.2  247.07
  4998.6  234.94  5002.1  234.94  5010.4  239.56  5019.4   247.4  5024.5  247.48
  5030.6  249.41  5060.8  250.79  5141.4  247.39    5222  248.79  5274.1  253.53
  5350.7  264.64  5423.5  268.08  5437.2  267.65  5473.8  270.51  5550.2   272.4
#Mann= 4 ,-1 , 0
  4430.8     .17       0  4597.9     .11       0  4980.2     .06       0
  5019.4     .11       0
Bank Sta=4980.2,5019.4
XS Rating Curve= 0 ,0
Exp/Cntr=0.3,0.1

Type RM Length L Ch R = 1 ,2753    ,589,589,589
BEGIN DESCRIPTION:
POLECAT BRANCH 5.0
END DESCRIPTION:
XS GIS Cut Line= 3
      3758013.22     10212513.05        3757258.     10212117.22
      3756872.96     10212216.08
#Sta/Elev= 30
  4377.7  272.46    4445  268.47  4553.1  261.38  4575.7  258.59  4650.2  252.79
  4655.8  251.85  4677.9  250.59  4812.8  246.19  4865.1  247.17  4947.7  245.73
  4982.1  246.51  4995.7  232.17  4999.2  232.17  5013.9  244.82  5019.5  246.28
  5027.3  246.59  5041.6  245.77  5080.1  248.12  5107.8  248.43  5146.3  250.07
  5168.3  249.91  5174.1  250.61    5233  252.07  5292.5  255.05  5347.8  258.79
  5457.7  263.27  5470.1  264.32    5499  264.83  5546.4  268.37  5627.9   272.2
#Mann= 4 ,-1 , 0
  4377.7     .17       0    4445     .11       0  4982.1     .06       0
  5019.5     .11       0
Bank Sta=4982.1,5019.5
XS Rating Curve= 0 ,0
Exp/Cntr=0.3,0.1

Type RM Length L Ch R = 1 ,2164    ,553,553,553
BEGIN DESCRIPTION:
POLECAT BRANCH 4.0
END DESCRIPTION:
XS GIS Cut Line= 3
      3758002.83     10211416.67      3757763.21     10211588.57
      3756792.36     10211911.32
#Sta/Elev= 30
  4351.7  265.94  4416.3  263.41    4458  260.78  4502.2   259.5  4537.8  256.33
  4646.6  251.37  4669.2  248.76  4706.1   246.3  4789.2  242.83  4820.9  240.71
  4873.6  242.27  4959.4  242.35  4978.9  241.94  4991.1  237.24  4998.3  228.83
  5001.8  228.83  5017.4  241.43  5022.7  241.62  5042.2  243.01  5073.8  242.92
  5158.1  244.72  5231.8  247.59  5370.9  255.28    5429  259.55  5497.6   261.2
  5529.2  262.96  5560.9   263.3  5624.2  266.98  5650.6  267.36  5669.7  268.68
#Mann= 5 ,-1 , 0
  4351.7     .11       0  4959.4     .11       0  4978.9     .06       0
  5022.7     .11       0  5042.2     .12       0
#XS Ineff= 1 ,-1
    4785  4873.6  242.27
Permanent Ineff=
       F
Bank Sta=4978.9,5022.7
XS Rating Curve= 0 ,0
Exp/Cntr=0.3,0.1

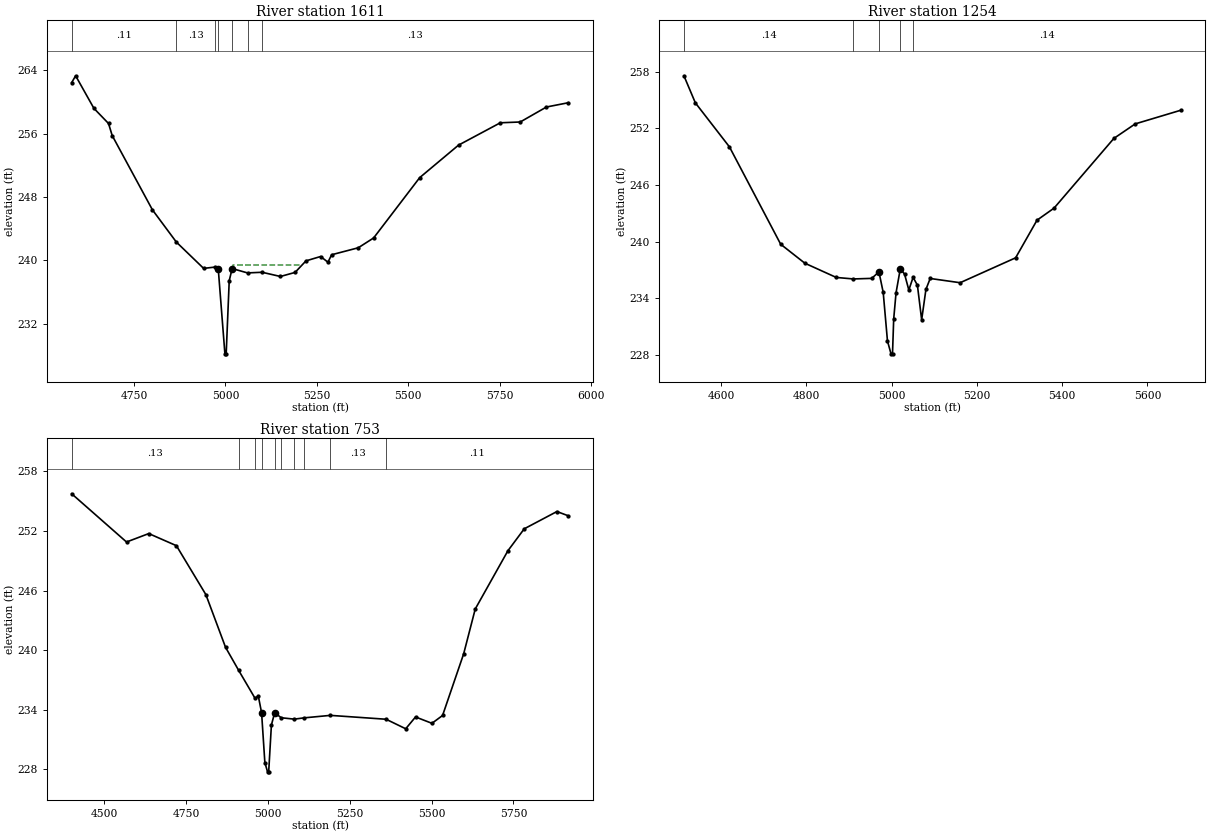
Type RM Length L Ch R = 1 ,1611    ,357,357,357
BEGIN DESCRIPTION:
POLECAT BRANCH 3.0
END DESCRIPTION:
XS GIS Cut Line= 3
      3757898.64      10211169.3      3757169.46     10211153.68
      3756573.12      10211354.2
#Sta/Elev= 30
  4579.6  262.44  4590.4   263.3  4640.4  259.19  4680.4  257.28  4690.4  255.76
  4800.4  246.39  4865.9  242.32  4940.5     239  4970.5  239.16  4980.5  238.95
  4998.7  228.22  5002.2  228.22  5010.5  237.44  5018.5  238.98  5060.5  238.43
  5100.5  238.51  5150.5  237.98  5190.5  238.49  5220.5  239.95  5260.5   240.5
  5280.5  239.78  5290.6  240.72  5363.4   241.6  5405.5  242.84  5531.5  250.45
  5637.7  254.55  5752.1  257.37  5806.5  257.47  5878.2  259.36  5938.1   259.9
#Mann= 7 ,-1 , 0
  4579.6     .11       0  4865.9     .13       0  4970.5     .11       0
  4980.5     .06       0  5018.5     .11       0  5060.5     .13       0
  5100.5     .13       0
#XS Ineff= 1 ,-1
  5020.5    5210  239.37
Permanent Ineff=
       F
Bank Sta=4980.5,5018.5
XS Rating Curve= 0 ,0
Exp/Cntr=0.3,0.1

Type RM Length L Ch R = 1 ,1254    ,501,501,501
BEGIN DESCRIPTION:
POLECAT BRANCH 2.0
END DESCRIPTION:
XS GIS Cut Line= 3
      3757924.68     10210846.39        3757758.     10210843.78
      3756761.72     10210778.75
#Sta/Elev= 30
  4512.6  257.58  4539.4  254.71  4619.4  250.04  4739.6  239.72  4796.2  237.71
  4869.9   236.2  4909.9  236.04  4953.1   236.1  4970.1  236.79  4980.1  234.61
  4990.1  229.46  4998.4   228.1  5001.9   228.1  5004.7   231.8  5010.2  234.57
  5020.2  237.12  5030.2  236.55  5040.2  234.87  5050.2  236.21  5060.3  235.38
  5070.3  231.71  5080.3  234.93  5090.3  236.09  5160.5  235.64  5290.7  238.28
  5340.9  242.27  5380.9  243.55  5521.2  250.94  5571.3  252.48  5677.7  253.92
#Mann= 5 ,-1 , 0
  4512.6     .14       0  4909.9     .13       0  4970.1     .08       0
  5020.2     .13       0  5050.2     .14       0
Bank Sta=4970.1,5020.2
XS Rating Curve= 0 ,0
Exp/Cntr=0.3,0.1

Type RM Length L Ch R = 1 ,753     ,0,0,0
BEGIN DESCRIPTION:
POLECAT BRANCH 1.0
END DESCRIPTION:
XS GIS Cut Line= 4
      3758049.67     10210442.74        3757758.     10210338.57
      3756958.52     10210369.82      3756712.01     10210694.18
#Sta/Elev= 30
  4400.4  255.75  4567.9  250.89  4635.9  251.74  4720.3  250.52  4810.3  245.59
  4870.4  240.28  4910.4  237.96  4960.5  235.14  4970.5  235.37  4980.5  233.69
  4990.5  228.67  4998.7  227.73  5002.2  227.73  5010.5  232.45  5020.5  233.69
  5040.5  233.18  5080.5  233.04  5110.6  233.17  5190.6  233.42  5360.8  233.03
  5420.8  232.07  5450.8  233.26  5500.9  232.62  5533.4  233.41  5597.8  239.62
  5633.2  244.14    5733  250.01  5782.9  252.22  5882.7  253.96  5917.6  253.53
#Mann= 10 ,-1 , 0
  4400.4     .13       0  4910.4     .11       0  4960.5     .11       0
  4980.5     .07       0  5020.5     .11       0  5040.5     .11       0
  5080.5     .11       0  5110.6     .11       0  5190.6     .13       0
  5360.8     .11       0
Bank Sta=4980.5,5020.5
XS Rating Curve= 0 ,0
Exp/Cntr=0.3,0.1

Chan Stop Cuts=-1
Use User Specified Reach Order=0
Composite Channel Slope=5