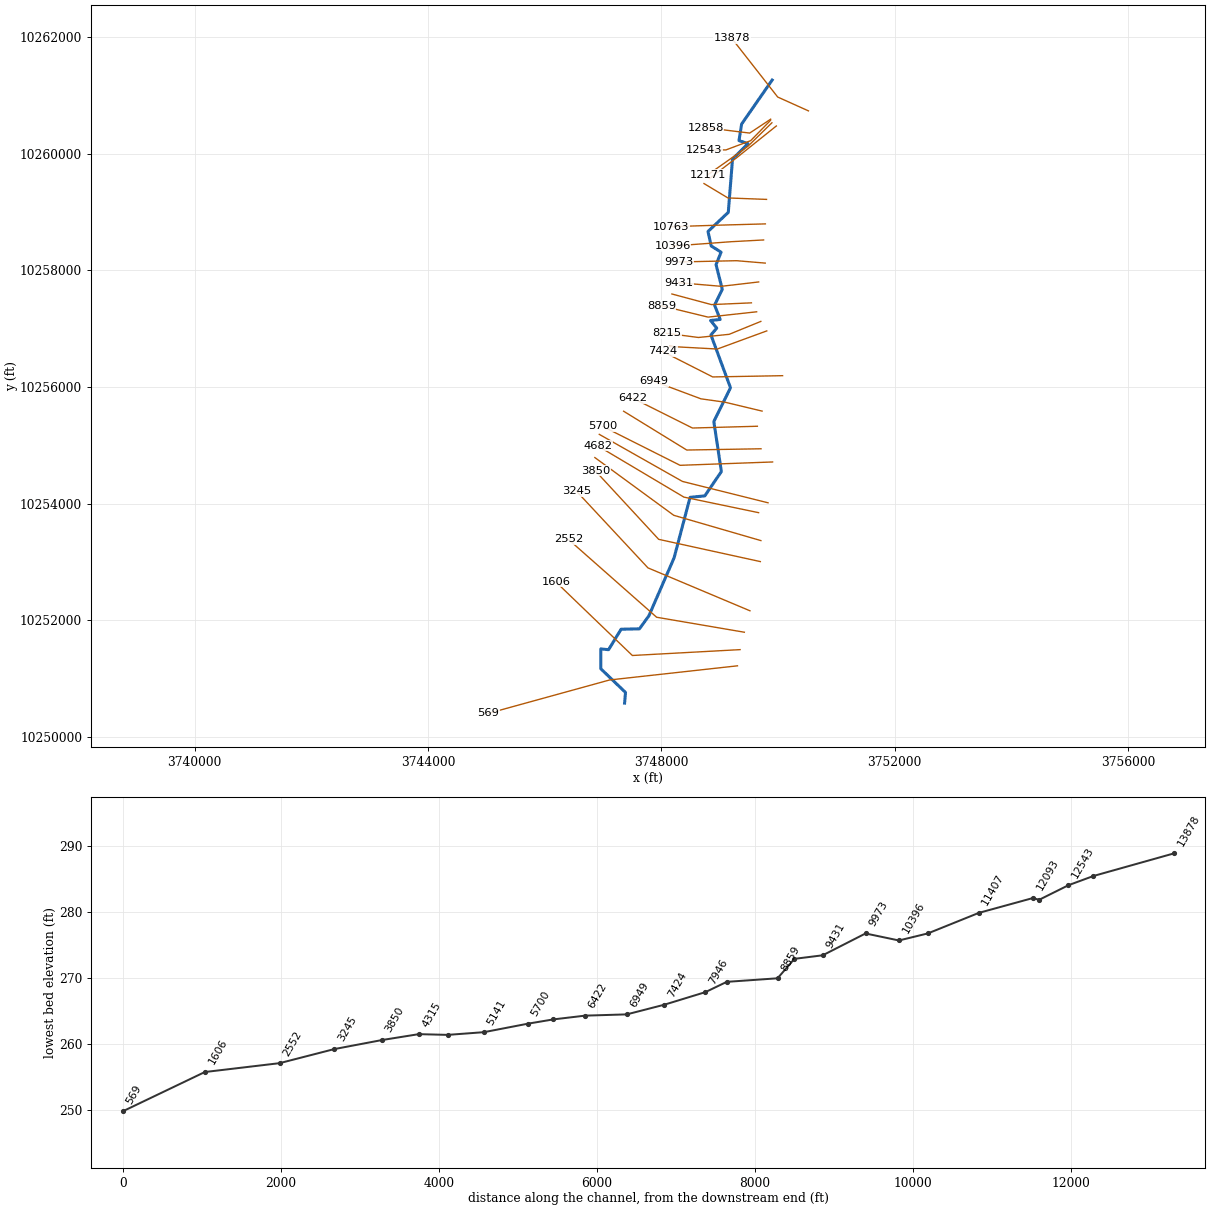
--- ROBINSON BRANCH.prj (project) ---

Proj Title=ROBINSON BRANCH Base Level Engineering
Current Plan=p01
Default Exp/Contr=0.3,0.1
English Units
Geom File=g01
Flow File=f01
Plan File=p01
Y Axis Title=Elevation
X Axis Title(PF)=Main Channel Distance
X Axis Title(XS)=Station
BEGIN DESCRIPTION:
ROBINSON BRANCH
END DESCRIPTION:
DSS Export Rating Curves= 0
DSS Export Rating Curve Sorted= 0
DSS Export Volume Flow Curves= 0
DXF OffsetX= 0
DXF OffsetY= 0
DXF ScaleX= 1
DXF ScaleY= 10

--- ROBINSON BRANCH.p01 (plan) ---

Plan Title=Multiple Run
Program Version=4.10
Short Identifier=Multiple
Geom File=g01
Flow File=f01
Subcritical Flow
K Sum by GR= 0
Std Step Tol= 0.01
Critical Tol= 0.01
Num of Std Step Trials= 20
Max Error Tol= 0.3
Flow Tol Ratio= 0.001
Split Flow NTrial= 30
Split Flow Tol= 0.02
Split Flow Ratio= 0.02
Log Output Level= 0
Friction Slope Method= 1
Unsteady Friction Slope Method= 2
Unsteady Bridges Friction Slope Method= 1
Parabolic Critical Depth
Global Vel Dist= 1 , 1 , 1
Global Log Level= 0
CheckData=True
Encroach Param=-1 ,0,0, 0
BEGIN DESCRIPTION:
Multiple Run
END DESCRIPTION:
Computation Interval=1HOUR
Output Interval=1HOUR
Run HTab= 0
Run UNet= 0
Run PostProcess= 0
Run WQNet= 0
UNET Theta= 1
UNET Theta Warmup= 1
UNET ZTol= 0.02
UNET ZSATol= 0.05
UNET MxIter= 20
UNET MaxInSteps= 0
UNET DtIC= 0
UNET DtMin= 0
UNET MaxCRTS= 20
UNET WFStab= 2
UNET SFStab= 1
UNET WFX= 1
UNET SFX= 1
UNET DSS MLevel= 4
UNET DZMax Abort= 100
UNET Convert EG Bridges= 0
UNET Use Existing IB Tables=-1
UNET Froude Reduction=False
UNET Froude Limit= 1
UNET Froude Power= 10
UNET Time Slicing=0,0, 5
UNET Junction Losses=0
Instantaneous Interval=1HOUR
Write IC File= 0
Write IC File at Sim End=0
Echo Input=False
Echo Parameters=False
Echo Output=False
Write Detailed= 0
WQ AD Non Conservative
WQ ULTIMATE=-1
WQ Max Comp Step=1HOUR
WQ Output Interval=15MIN
WQ Output Selected Increments= 0
WQ Output face flow=0
WQ Output face velocity=0
WQ Output face area=0
WQ Output face dispersion=0
WQ Output cell volume=0
WQ Output cell surface area=0
WQ Output cell continuity=0
WQ Output cumulative cell continuity=0
WQ Output face conc=0
WQ Output face dconc_dx=0
WQ Output face courant=0
WQ Output face peclet=0
WQ Output face adv mass=0
WQ Output face disp mass=0
WQ Output cell mass=0
WQ Output cell source sink temp=0
WQ Output cell source sink nsm=0
WQ Output MaxMinRange=-1
WQ Daily Max Min Mean=-1
WQ Daily Range=0
WQ Daily Time=0
WQ Create Restart=0
WQ Fixed Restart=0
WQ System Summary=0
WQ Use Fixed Temperature=0
Sorting and Armoring Iterations= 10
XS Update Threshold= 0.02
Hydraulics Update Threshold= 0.02
Energy Slope Method= 1
Volume Change Method= 0
XS Weighting Method= 0
Number of US Weighted Cross Sections= 1
Number of DS Weighted Cross Sections= 1
Upstream XS Weight=0.25
Main XS Weight=0.5
Downstream XS Weight=0.25
Number of DS XS's Weighted with US Boundary= 1
Upstream Boundary Weight= 1
Weight of XSs Associated with US Boundary= 0
Number of US XS's Weighted with DS Boundary= 1
Downstream Boundary Weight= 0.5
Weight of XSs Associated with DS Boundary= 0.5
Sediment Output Level= 4
Mass or Volume Output= 0
Output Increment Type= 1
Profile and TS Output Increment= 10
XS Output Flag= 0
XS Output Increment= 10
Disregard all LS=0
Disregard all Conn=0
Disregard all Breaches=0
Disregard all Pumps=0

--- ROBINSON BRANCH.f01 (steady flow) ---

Flow Title=Multiple
Program Version=4.10
Number of Profiles= 7
Profile Names=10-year,25-year,50-year,1pct_min,100-year,1pct_plu,500-year
River Rch & RM=ROBINSON BRANCH,Reach-1         ,13878
     978    1347    1841     826    2495    7535    4739
River Rch & RM=ROBINSON BRANCH,Reach-1         ,6949
    1043    1434    1956     875    2643    7982    4995
Boundary for River Rch & Prof#=ROBINSON BRANCH,Reach-1         , 1
Up Type= 0
Dn Type= 3
Dn Slope=0.005
Boundary for River Rch & Prof#=ROBINSON BRANCH,Reach-1         , 2
Up Type= 0
Dn Type= 3
Dn Slope=0.005
Boundary for River Rch & Prof#=ROBINSON BRANCH,Reach-1         , 3
Up Type= 0
Dn Type= 3
Dn Slope=0.005
Boundary for River Rch & Prof#=ROBINSON BRANCH,Reach-1         , 4
Up Type= 0
Dn Type= 3
Dn Slope=0.005
Boundary for River Rch & Prof#=ROBINSON BRANCH,Reach-1         , 5
Up Type= 0
Dn Type= 3
Dn Slope=0.005
Boundary for River Rch & Prof#=ROBINSON BRANCH,Reach-1         , 6
Up Type= 0
Dn Type= 3
Dn Slope=0.005
Boundary for River Rch & Prof#=ROBINSON BRANCH,Reach-1         , 7
Up Type= 0
Dn Type= 3
Dn Slope=0.005
DSS Import GetInterval= 0
DSS Import GetPeak= 0
DSS Import FillOption= 0

--- ROBINSON BRANCH.g01 (geometry) ---

Geom Title=Existing Conditions
Program Version=4.10

River Reach=ROBINSON BRANCH ,Reach-1
Reach XY= 30
      3749898.23     10261266.84      3749374.28      10260511.6
      3749329.46     10260228.33      3749483.99     10260175.71
      3749218.59     10259911.75      3749146.05     10258996.81
      3748798.37     10258669.53      3748852.73     10258420.23
      3749022.54     10258313.64      3748936.54     10258098.25
      3749043.13      10257676.3      3748911.16     10257405.38
      3749007.43     10257159.95      3748842.49     10257141.68
      3748948.75     10257010.24       3748848.4     10256894.03
      3749183.87      10255987.4      3748898.21     10255408.14
      3749027.49     10254549.99      3748743.68     10254132.72
      3748490.76     10254107.68      3748216.88     10253069.26
      3747784.13     10252073.56      3747622.72     10251851.63
      3747308.46     10251844.71      3747093.63     10251493.74
      3746960.45     10251506.79      3746960.25     10251166.87
      3747384.02     10250759.99      3747368.23     10250576.84

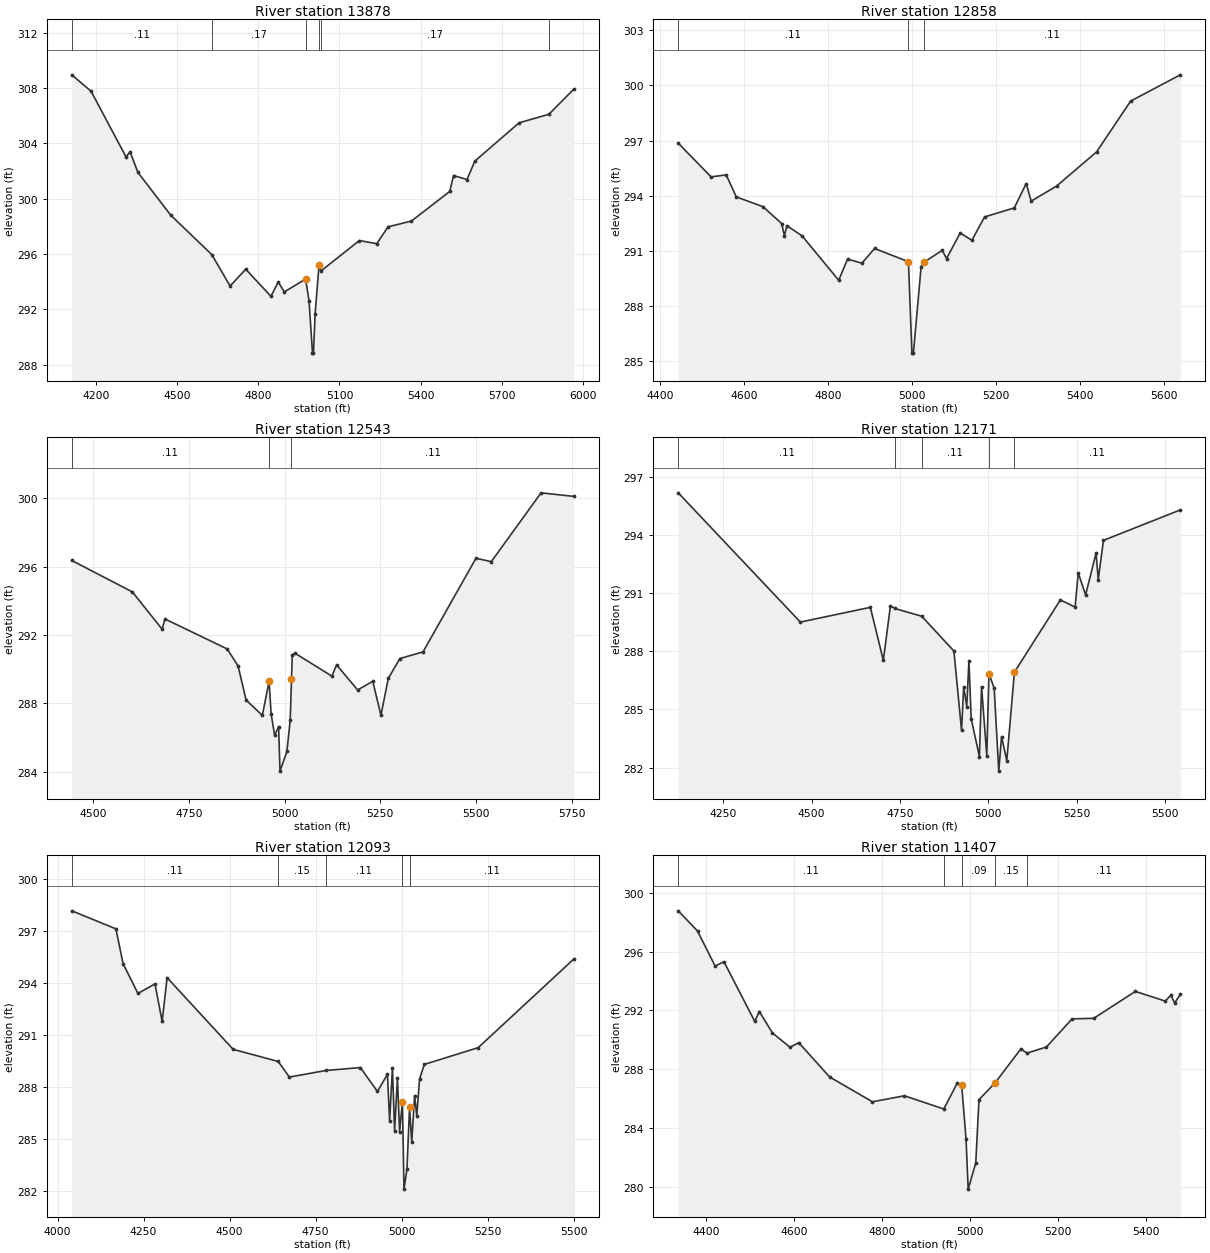
Type RM Length L Ch R = 1 ,13878   ,1020,1020,1020
BEGIN DESCRIPTION:
ROBINSON BRANCH 25.0
END DESCRIPTION:
XS GIS Cut Line= 3
      3750520.76      10260737.9      3749992.92     10260975.75
      3749205.68     10261982.68
#Sta/Elev= 30
  4109.8  308.96  4181.3  307.77  4310.4  303.03  4325.6  303.39  4354.3  301.91
  4475.5  298.82  4627.8  295.96  4695.5  293.69  4753.2  294.91  4846.4  292.95
  4873.5  293.98  4896.1  293.27  4974.8  294.19  4987.5   292.6  5000.2  288.84
  5003.7  288.84    5010   291.7  5024.5  295.23  5030.9  294.77  5173.7  296.98
  5237.9  296.75  5279.6  297.97  5366.3  298.39  5507.9  300.53  5521.9  301.68
  5571.7  301.39  5600.6  302.72  5764.3  305.49  5874.8  306.11  5966.9  307.93
#Mann= 6 ,-1 , 0
  4109.8     .11       0  4627.8     .17       0  4974.8     .09       0
  5024.5     .12       0  5030.9     .17       0  5874.8     .11       0
Bank Sta=4974.8,5024.5
XS Rating Curve= 0 ,0
Exp/Cntr=0.3,0.1

Type RM Length L Ch R = 1 ,12858   ,315,315,315
BEGIN DESCRIPTION:
ROBINSON BRANCH 24.0
END DESCRIPTION:
XS GIS Cut Line= 3
      3749873.06      10260595.9      3749512.84      10260357.2
       3748755.5     10260450.51
#Sta/Elev= 30
    4443  296.86  4521.2  295.02  4557.3  295.13  4581.2  293.93  4644.5   293.4
  4689.2  292.48  4695.7  291.82  4701.7  292.36  4737.7  291.81    4825  289.39
    4846  290.54  4880.2  290.32  4910.4  291.12    4991   290.4  4999.3  285.42
  5002.8  285.42  5021.2  290.13  5027.9  290.37  5071.6  291.02  5081.7  290.57
  5114.1  291.96  5142.1  291.57  5172.3  292.84  5242.9  293.33  5271.4  294.66
  5283.2   293.7  5343.6  294.52  5438.8  296.38    5520  299.15  5638.2  300.58
#Mann= 3 , 0 , 0
    4443     .11       0    4991     .07       0  5027.9     .11       0
Bank Sta=4991,5027.9
XS Rating Curve= 0 ,0
Exp/Cntr=0.3,0.1

Type RM Length L Ch R = 1 ,12543   ,372,372,372
BEGIN DESCRIPTION:
ROBINSON BRANCH 23.0
END DESCRIPTION:
XS GIS Cut Line= 4
      3749868.74     10260574.21       3749530.2     10260227.51
      3749107.03     10260068.57      3748732.24      10260066.4
#Sta/Elev= 30
    4444  296.36  4602.3  294.52  4680.2  292.33  4687.2  292.94    4850  291.18
  4878.3  290.19  4899.4  288.19  4941.8  287.29  4959.4  289.29  4964.8  287.36
  4973.8  286.13  4984.3  286.64  4987.9  284.03  5005.9  285.18  5014.6  287.03
  5017.9 289.396  5019.9  290.83  5027.2  290.93  5123.4  289.59  5135.6  290.25
  5190.7  288.78  5230.2  289.29  5251.5   287.3  5270.8  289.46    5301  290.62
  5361.5  291.01  5499.8  296.49  5539.8  296.29  5669.8  300.32  5755.4  300.11
#Mann= 3 , 0 , 0
    4444     .11       0  4959.4     .06       0  5017.9     .11       0
Bank Sta=4959.4,5017.9
XS Rating Curve= 0 ,0
Exp/Cntr=0.3,0.1

Type RM Length L Ch R = 1 ,12171   ,78,78,78
BEGIN DESCRIPTION:
ROBINSON BRANCH 22.0
END DESCRIPTION:
XS GIS Cut Line= 4
      3749893.77     10260533.84      3749481.74     10260129.77
      3749323.51     10260014.33      3748794.19     10259641.51
#Sta/Elev= 30
  4122.9  296.16  4468.4   289.5  4666.4  290.26  4703.1  287.53  4723.3  290.34
  4735.9   290.2  4811.8   289.8  4902.8  288.01  4924.4  283.92  4930.5  286.17
  4939.1  285.15  4945.3  287.51  4951.7  284.52  4974.9  282.57    4981  286.17
  4995.8  282.62  5001.9  286.85  5016.7  286.09  5029.7  281.82  5037.6   283.6
  5052.4  282.36    5074  286.92  5203.9  290.64  5245.8  290.27  5254.5  292.04
  5275.4   290.9    5305  293.06  5311.1  291.69  5325.9  293.71  5543.3  295.28
#Mann= 5 ,-1 , 0
  4122.9     .11       0  4735.9     .15       0  4811.8     .11       0
  5001.9     .06       0    5074     .11       0
Bank Sta=5001.9,5074
XS Rating Curve= 0 ,0
Exp/Cntr=0.3,0.1

Type RM Length L Ch R = 1 ,12093   ,686,686,686
BEGIN DESCRIPTION:
ROBINSON BRANCH 21.0
END DESCRIPTION:
XS GIS Cut Line= 3
      3749969.57     10260478.98      3749291.61      10259935.8
      3748822.84     10259576.41
#Sta/Elev= 30
  4041.2  298.16  4169.5  297.12  4190.3  295.11  4233.5  293.39  4283.1  293.94
  4303.9  291.77  4318.3   294.3  4510.4  290.16  4641.4  289.46  4673.6  288.56
  4779.7  288.94  4880.1  289.11  4929.7  287.73  4958.8  288.72  4965.1  286.02
  4973.3  289.11  4979.6  285.45  4987.8   288.5  4994.1   285.4  5002.3  287.12
  5006.9  282.09  5015.5  283.24  5023.1  286.83  5029.4  284.79  5037.7  287.49
    5044  286.34  5052.2  288.45  5065.9  289.29  5222.6  290.26  5500.6  295.38
#Mann= 5 ,-1 , 0
  4041.2     .11       0  4641.4     .15       0  4779.7     .11       0
  5002.3     .06       0  5023.1     .11       0
Bank Sta=5002.3,5023.1
XS Rating Curve= 0 ,0
Exp/Cntr=0.3,0.1

Type RM Length L Ch R = 1 ,11407   ,644,644,644
BEGIN DESCRIPTION:
ROBINSON BRANCH 20.0
END DESCRIPTION:
XS GIS Cut Line= 3
      3749801.66     10259219.26      3749139.64     10259244.35
      3748729.44      10259491.3
#Sta/Elev= 30
  4337.5  298.77  4381.3   297.4  4421.4  295.01  4441.4  295.31  4511.4  291.25
  4521.9  291.92  4551.5  290.47  4591.5  289.49  4611.5   289.8  4681.6  287.47
    4779  285.78  4851.7  286.19  4941.1  285.29  4971.8  287.05  4981.8  286.92
  4991.8  283.22  4996.6  279.84  5013.8  281.62  5021.2  285.93  5058.1  287.08
  5116.3  289.38  5130.2  289.09  5174.6  289.51  5232.8  291.42  5282.2  291.46
  5376.6  293.29  5444.5  292.63  5457.3  293.03  5465.9   292.5  5478.8  293.08
#Mann= 5 ,-1 , 0
  4337.5     .11       0  4941.1     .15       0  4981.8     .09       0
  5058.1     .15       0  5130.2     .11       0
Bank Sta=4981.8,5058.1
XS Rating Curve= 0 ,0
Exp/Cntr=0.3,0.1

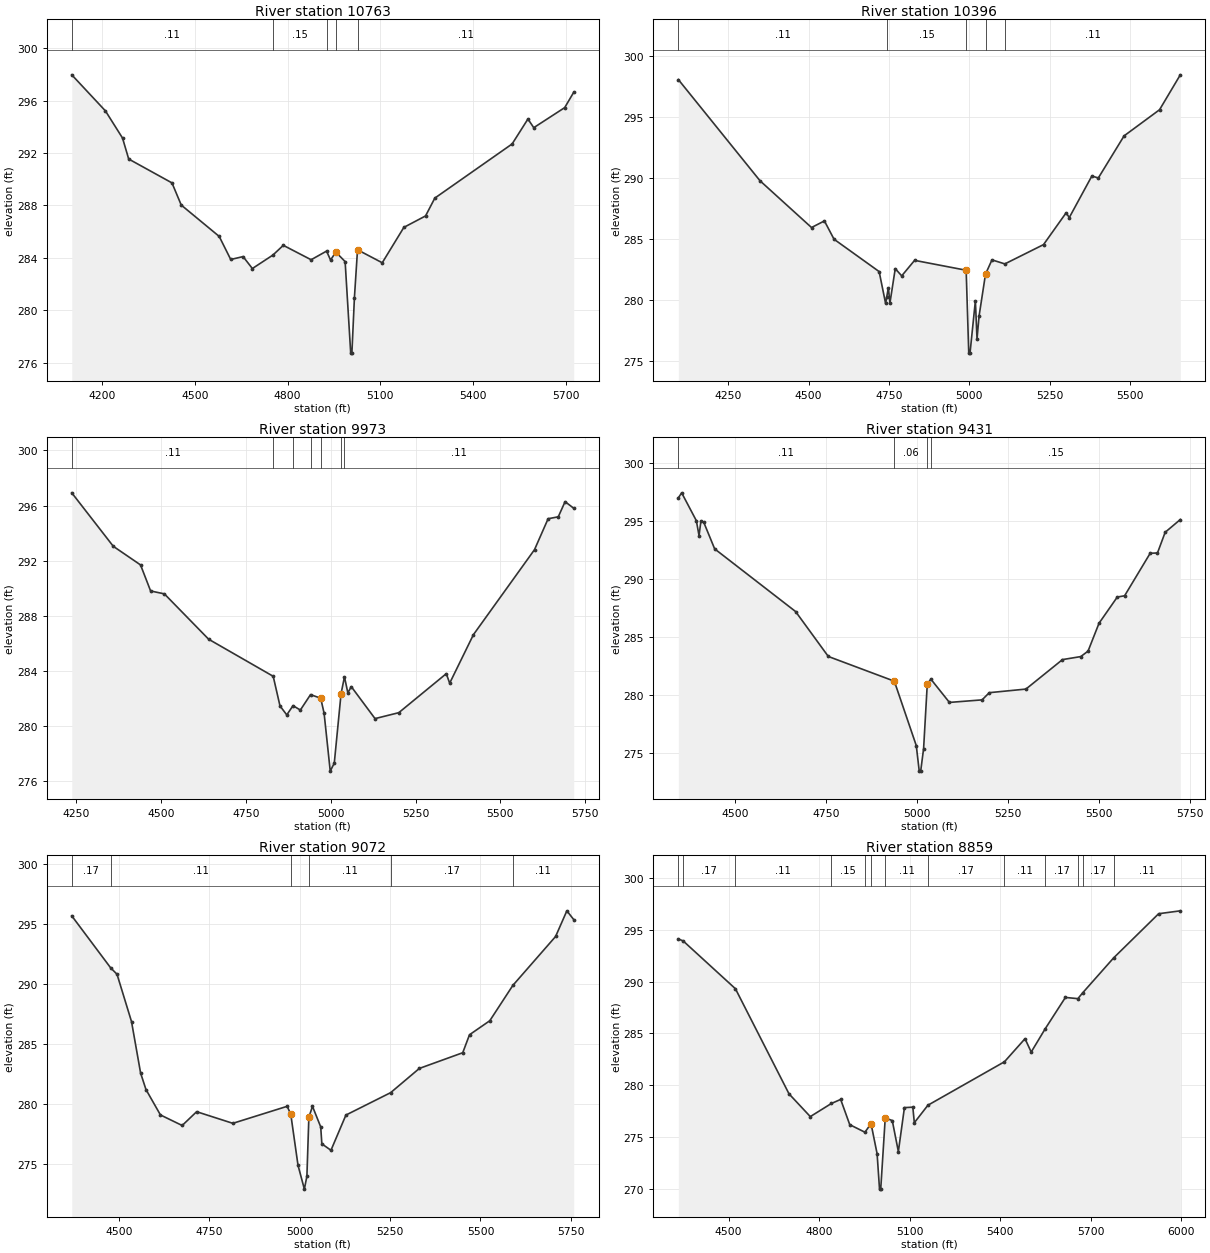
Type RM Length L Ch R = 1 ,10763   ,367,367,367
BEGIN DESCRIPTION:
ROBINSON BRANCH 19.0
END DESCRIPTION:
XS GIS Cut Line= 3
      3749781.95     10258799.04      3748987.67     10258777.34
      3748158.66      10258751.3
#Sta/Elev= 30
  4101.8  297.96  4210.7  295.21    4266  293.14    4286  291.54    4426  289.72
    4456  288.03  4578.8  285.64  4616.1  283.88  4656.1   284.1  4686.1  283.19
  4752.7  284.22  4786.2  284.96  4876.2  283.86  4926.2  284.52    4939  283.84
  4956.2  284.44  4986.2  283.72  5004.3  276.74  5008.1  276.74  5016.3  280.98
  5026.3  284.62  5106.3  283.63  5176.3  286.33  5246.4   287.2  5276.4  288.56
  5526.5  292.69  5577.6  294.59  5596.5  293.93  5696.6  295.46  5725.8  296.63
#Mann= 5 ,-1 , 0
  4101.8     .11       0  4752.7     .15       0  4926.2     .11       0
  4956.2     .06       0  5026.3     .11       0
Bank Sta=4956.2,5026.3
XS Rating Curve= 0 ,0
Exp/Cntr=0.3,0.1

Type RM Length L Ch R = 1 ,10396   ,423,423,423
BEGIN DESCRIPTION:
ROBINSON BRANCH 18.0
END DESCRIPTION:
XS GIS Cut Line= 3
      3749751.56     10258523.43      3749193.96     10258493.34
      3748193.41     10258419.27
#Sta/Elev= 30
  4094.7  298.08  4348.8  289.79    4509  285.96  4549.1   286.5  4579.1     285
  4719.4  282.35  4739.5  279.74  4743.2   280.3    4748  281.02    4753  279.78
  4769.5  282.59  4789.6     282  4829.7  283.27  4990.1  282.46  4998.2  275.67
  5002.1  275.67  5018.8  279.96  5023.9  276.83  5030.3  278.71  5050.3  282.14
  5070.4  283.31  5110.5  282.98  5230.8  284.56    5301  287.16    5311  286.78
  5381.2  290.18  5401.3  290.02  5481.5  293.47  5591.8  295.61  5656.4  298.47
#Mann= 5 ,-1 , 0
  4094.7     .11       0  4743.2     .15       0  4990.1     .09       0
  5050.3     .15       0  5110.5     .11       0
Bank Sta=4990.1,5050.3
XS Rating Curve= 0 ,0
Exp/Cntr=0.3,0.1

Type RM Length L Ch R = 1 ,9973    ,542,542,542
BEGIN DESCRIPTION:
ROBINSON BRANCH 17.0
END DESCRIPTION:
XS GIS Cut Line= 3
       3749779.8     10258126.29      3749287.15     10258167.53
      3748302.36     10258145.84
#Sta/Elev= 30
  4236.6  296.92    4359  293.04  4439.3  291.69    4469   289.8  4509.5  289.59
    4640   286.3  4830.3  283.61  4850.3  281.46  4870.3  280.81  4888.7  281.48
  4910.3  281.16  4940.3  282.28  4970.3  282.02  4980.3  280.93  4998.4  276.73
  5010.3  277.31  5030.3  282.35  5040.3  283.57  5050.3  282.41  5060.4  282.86
  5130.4  280.54  5200.4  280.97  5340.4   283.8  5350.4  283.11  5420.4  286.63
  5600.5   292.8  5640.5  295.04  5670.5  295.18  5690.5  296.28    5716   295.8
#Mann= 7 ,-1 , 0
  4236.6     .11       0  4830.3     .11       0  4888.7     .15       0
  4940.3     .11       0  4970.3     .06       0  5030.3     .11       0
  5040.3     .11       0
#XS Ineff= 1 ,-1
  5040.3    5390  283.57
Permanent Ineff=
       F
Bank Sta=4970.3,5030.3
XS Rating Curve= 0 ,0
Exp/Cntr=0.3,0.1

Type RM Length L Ch R = 1 ,9431    ,359,359,359
BEGIN DESCRIPTION:
ROBINSON BRANCH 16.0
END DESCRIPTION:
XS GIS Cut Line= 3
      3749666.91     10257802.94      3749026.04     10257728.07
      3748295.38     10257789.93
#Sta/Elev= 30
  4343.9  296.98    4353  297.41  4393.3  295.01  4400.7  293.72  4405.8  294.97
  4413.4  294.89  4443.6  292.58  4665.9  287.18  4755.7  283.31    4937  281.18
  4997.3  275.63  5005.4  273.43  5009.4  273.43  5017.4  275.37  5027.5  280.94
  5037.5  281.35  5088.3  279.35    5178  279.57  5197.8  280.19  5298.4   280.5
  5398.8  283.04    5449   283.3    5469  283.77  5499.1  286.17  5549.3  288.43
  5569.4  288.54  5639.6   292.2  5659.7  292.23  5680.8  294.01  5722.4  295.11
#Mann= 4 ,-1 , 0
  4343.9     .11       0    4937     .06       0  5027.5     .11       0
  5037.5     .15       0
#XS Ineff= 1 ,-1
  5037.5    5365  281.35
Permanent Ineff=
       F
Bank Sta=4937,5027.5
XS Rating Curve= 0 ,0
Exp/Cntr=0.3,0.1

Type RM Length L Ch R = 1 ,9072    ,213,213,213
BEGIN DESCRIPTION:
ROBINSON BRANCH 15.0
END DESCRIPTION:
XS GIS Cut Line= 3
      3749542.85     10257444.38      3748857.46     10257414.49
      3748179.49     10257596.44
#Sta/Elev= 30
  4369.9  295.69  4477.5  291.35    4495  290.82  4535.1  286.87  4560.3  282.57
  4575.1   281.2  4615.1  279.08  4675.2   278.2  4715.2  279.35  4815.3  278.38
  4965.5   279.8  4975.5  279.14  4995.5  274.88  5013.1  272.89  5020.1  273.97
  5025.5  278.88  5035.5   279.8  5058.3  278.08  5061.4  276.67  5086.6  276.13
    5128  279.07  5251.7  280.94    5331  282.96    5451  284.27  5469.7  285.77
  5525.8  286.94  5589.6  289.89  5707.8  293.97  5738.9  296.11  5757.9  295.38
#Mann= 6 ,-1 , 0
  4369.9     .17       0  4477.5     .11       0  4975.5     .06       0
  5025.5     .11       0  5251.7     .17       0  5589.6     .11       0
#XS Ineff= 1 ,-1
  5035.5    5180   279.8
Permanent Ineff=
       F
Bank Sta=4975.5,5025.5
XS Rating Curve= 0 ,0
Exp/Cntr=0.3,0.1

Type RM Length L Ch R = 1 ,8859    ,644,644,644
BEGIN DESCRIPTION:
ROBINSON BRANCH 14.0
END DESCRIPTION:
XS GIS Cut Line= 3
      3749632.22     10257290.79      3748798.87     10257199.65
      3747998.06     10257394.96
#Sta/Elev= 30
  4333.5  294.13  4349.4  293.94  4522.5  289.32    4700  279.16  4770.5  276.96
  4840.5  278.23  4871.1  278.62  4901.2  276.18  4951.5  275.45  4971.7  276.28
  4991.8  273.37  4999.8  269.95  5003.8  269.95  5018.8  276.85  5042.1  276.57
  5062.2  273.58  5082.3  277.83  5110.1  277.87  5115.1  276.37  5160.1  278.06
  5413.6  282.26  5481.7  284.49  5502.2   283.2  5548.6  285.45  5615.5  288.48
  5656.8  288.36  5672.6  288.92  5775.2   292.3  5924.3  296.57  5996.1  296.85
#Mann= 13 ,-1 , 0
  4333.5     .11       0  4349.4     .17       0  4522.5     .11       0
  4840.5     .15       0  4951.5     .11       0  4971.7     .06       0
  5018.8     .11       0  5160.1     .17       0  5413.6     .11       0
  5548.6     .17       0  5656.8     .11       0  5672.6     .17       0
  5775.2     .11       0
Bank Sta=4971.7,5018.8
XS Rating Curve= 0 ,0
Exp/Cntr=0.3,0.1

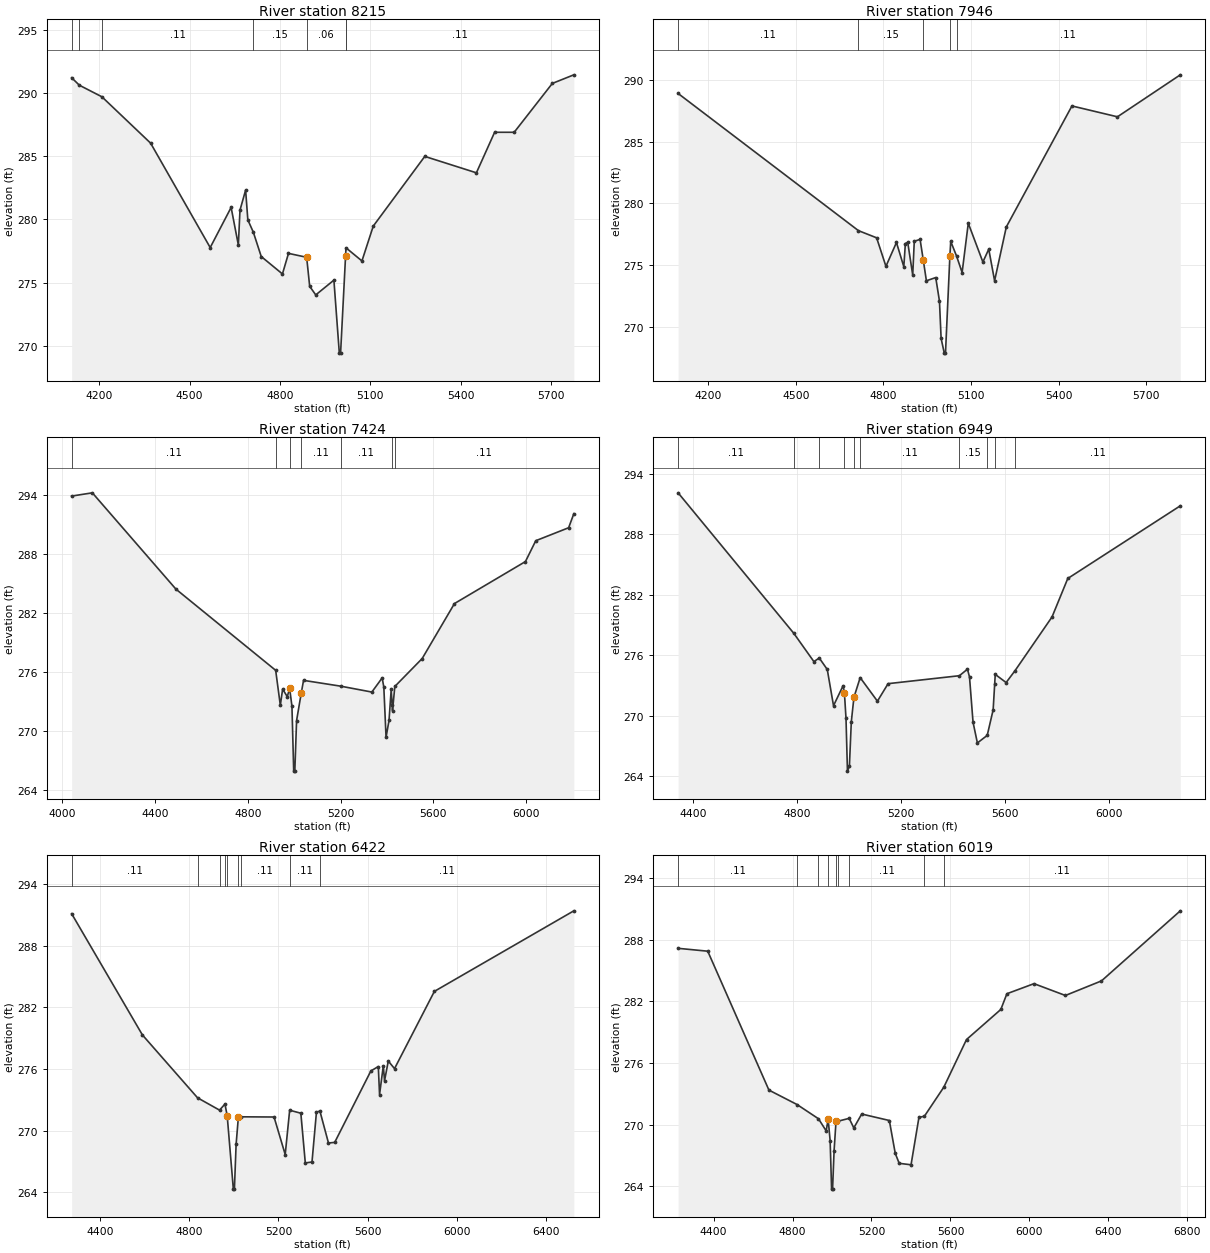
Type RM Length L Ch R = 1 ,8215    ,269,269,269
BEGIN DESCRIPTION:
Mapping XS e8fe91e9
END DESCRIPTION:
XS GIS Cut Line= 4
      3749703.84     10257125.87      3749161.28     10256904.51
      3748633.94     10256850.25      3748087.02     10256921.87
#Sta/Elev= 30
  4108.5  291.22  4133.9  290.63    4209  289.71  4370.7  286.04  4568.6  277.77
  4638.1  280.95  4662.1  277.97  4667.5  280.73  4686.2  282.32  4693.6  279.96
  4711.8  278.99  4738.1  277.06  4808.5  275.68  4828.6  277.31  4888.9     277
    4899   274.7  4919.1  274.02  4979.4  275.19  4997.4  269.41  5001.6  269.41
  5018.2 277.126  5019.6  277.75  5072.5  276.71  5110.1  279.47  5281.2  284.99
  5452.6  283.69  5513.1   286.9  5578.1   286.9  5704.8  290.77  5776.2  291.45
#Mann= 7 ,-1 , 0
  4108.5     .11       0  4133.9     .17       0    4209     .11       0
  4711.8     .15       0  4888.9     .06       0  5018.2     .11       0
  5019.6     .11       0
Bank Sta=4888.9,5018.2
XS Rating Curve= 0 ,0
Exp/Cntr=0.3,0.1

Type RM Length L Ch R = 1 ,7946    ,522,522,522
BEGIN DESCRIPTION:
ROBINSON BRANCH 13.0
END DESCRIPTION:
XS GIS Cut Line= 3
      3749805.85     10256963.11       3748958.2     10256652.12
      3748142.98     10256696.08
#Sta/Elev= 30
  4097.1  288.89  4714.5  277.78  4776.7   277.2  4808.6  274.89  4844.6  276.82
  4869.8  274.86  4875.1  276.73  4883.2  276.84  4900.3  274.18  4905.6  276.92
  4925.5  277.07  4936.5  275.39  4947.1  273.72  4979.1  273.98  4991.8  272.08
  4997.5  269.05  5008.3  267.86  5012.5  267.86  5027.5  275.71  5030.4  276.91
  5050.4  275.72  5069.4  274.39  5090.5  278.38  5140.5  275.24  5160.6  276.28
  5180.6  273.72  5220.7  278.08  5445.4  287.88  5601.2     287  5816.4   290.4
#Mann= 5 ,-1 , 0
  4097.1     .11       0  4714.5     .15       0  4936.5     .09       0
  5027.5     .15       0  5050.4     .11       0
#XS Ineff= 1 ,-1
  5090.5    5270  278.38
Permanent Ineff=
       F
Bank Sta=4936.5,5027.5
XS Rating Curve= 0 ,0
Exp/Cntr=0.3,0.1

Type RM Length L Ch R = 1 ,7424    ,475,475,475
BEGIN DESCRIPTION:
ROBINSON BRANCH 12.0
END DESCRIPTION:
XS GIS Cut Line= 3
      3750077.05     10256194.87      3748879.16     10256173.17
      3748017.87     10256611.06
#Sta/Elev= 30
  4040.9  293.92  4130.1  294.25  4490.2  284.46  4920.2   276.2  4940.2  272.65
  4950.2  274.29  4970.3  273.52  4980.3  274.38  4990.3  272.55  4997.9  265.95
  5002.7  265.95  5010.3  271.09  5030.3  273.87  5040.3  275.18  5200.3  274.59
  5334.7  273.99  5379.2  275.43  5386.3  274.49  5395.9   269.4  5408.7   271.1
  5418.1  274.27  5422.2  272.68  5423.7   272.1  5433.7  274.56  5551.6   277.4
  5690.7  282.99  5996.6  287.26  6041.1  289.38  6182.8   290.7  6205.2  292.13
#Mann= 7 ,-1 , 0
  4040.9     .11       0  4920.2     .11       0  4980.3     .06       0
  5030.3     .11       0  5200.3     .11       0  5422.2     .15       0
  5433.7     .11       0
#XS Ineff= 1 ,-1
  5379.2    5497  275.43
Permanent Ineff=
       F
Bank Sta=4980.3,5030.3
XS Rating Curve= 0 ,0
Exp/Cntr=0.3,0.1

Type RM Length L Ch R = 1 ,6949    ,527,527,527
BEGIN DESCRIPTION:
ROBINSON BRANCH 11.0
END DESCRIPTION:
XS GIS Cut Line= 4
       3749725.5     10255587.24      3749087.37     10255740.17
      3748677.34     10255797.74      3747871.42     10256098.87
#Sta/Elev= 30
  4343.8  292.14  4788.3  278.19  4865.8  275.37  4886.4  275.73  4917.2  274.59
  4941.2  270.99  4978.1  272.98  4983.2  272.24  4989.2  269.74  4994.8  264.49
  5002.3  264.99  5009.6  269.39  5019.7  271.82  5043.7  273.78    5110  271.44
    5151  273.18  5425.1  273.97  5456.2  274.62    5464  273.84  5477.6  269.35
  5494.3  267.29  5532.1  268.04  5554.9  270.58  5560.9  273.19    5563   274.1
  5604.8  273.29    5639  274.47  5781.3  279.81  5841.8  283.63  6274.4  290.85
#Mann= 10 ,-1 , 0
  4343.8     .11       0  4788.3     .17       0  4886.4     .11       0
  4983.2     .07       0  5019.7     .11       0  5043.7     .11       0
  5425.1     .15       0  5532.1     .11       0  5560.9     .15       0
    5639     .11       0
#XS Ineff= 2 ,-1
  5456.2    5670  274.62  5043.7    5445  273.78
Permanent Ineff=
       F       F
Bank Sta=4983.2,5019.7
XS Rating Curve= 0 ,0
Exp/Cntr=0.3,0.1

Type RM Length L Ch R = 1 ,6422    ,403,403,403
BEGIN DESCRIPTION:
ROBINSON BRANCH 10.0
END DESCRIPTION:
XS GIS Cut Line= 3
      3749644.92     10255327.12      3748531.63     10255296.74
      3747514.48      10255806.4
#Sta/Elev= 30
  4273.2  291.11  4590.4  279.31  4837.6  273.19  4936.2  271.99  4960.5  272.58
  4970.5  271.45  4998.1   264.3  5002.9   264.3  5010.5  268.66  5020.6   271.3
  5030.6  271.34  5180.6  271.32  5230.6  267.67  5250.6  271.98  5300.7  271.69
  5320.7  266.85  5350.7  266.94  5370.7   271.8  5386.3  271.89  5424.6  268.79
  5452.5  268.85  5614.8  275.81    5648  276.23  5653.6  273.51  5670.4   276.3
    5676  274.85  5692.7  276.77  5720.7  276.03  5899.4  283.55  6524.6  291.39
#Mann= 9 ,-1 , 0
  4273.2     .11       0  4837.6     .15       0  4936.2     .11       0
  4960.5     .09       0  4970.5     .06       0  5020.6     .09       0
  5030.6     .11       0  5250.6     .11       0  5386.3     .11       0
Bank Sta=4970.5,5020.6
XS Rating Curve= 0 ,0
Exp/Cntr=0.3,0.1

Type RM Length L Ch R = 1 ,6019    ,319,319,319
BEGIN DESCRIPTION:
ROBINSON BRANCH 9.0
END DESCRIPTION:
XS GIS Cut Line= 3
      3749707.89     10254940.84      3748433.97     10254919.14
      3747351.96     10255584.83
#Sta/Elev= 30
  4220.2  287.17  4370.3  286.89  4680.3  273.37  4823.2  271.96  4931.4  270.58
  4970.4   269.4  4980.4  270.53  4990.4  268.46  4997.9  263.73  5002.8  263.73
  5010.4  267.45  5020.4  270.37  5030.1  270.34  5086.9  270.62  5110.4  269.69
  5150.4  271.04  5290.4  270.41  5320.4  267.21  5340.4  266.24  5400.4   266.1
  5440.4  270.71  5468.2  270.83  5566.6  273.66  5681.4  278.29  5855.3  281.22
  5886.1  282.75  6023.4  283.73  6182.5  282.58  6365.4     284  6764.7  290.82
#Mann= 9 ,-1 , 0
  4220.2     .11       0  4823.2     .15       0  4931.4     .11       0
  4980.4     .06       0  5020.4     .11       0  5030.1     .15       0
  5086.9     .11       0  5468.2     .15       0  5566.6     .11       0
#XS Ineff= 1 ,-1
  5150.4    5500  271.04
Permanent Ineff=
       T
Bank Sta=4980.4,5020.4
XS Rating Curve= 0 ,0
Exp/Cntr=0.3,0.1

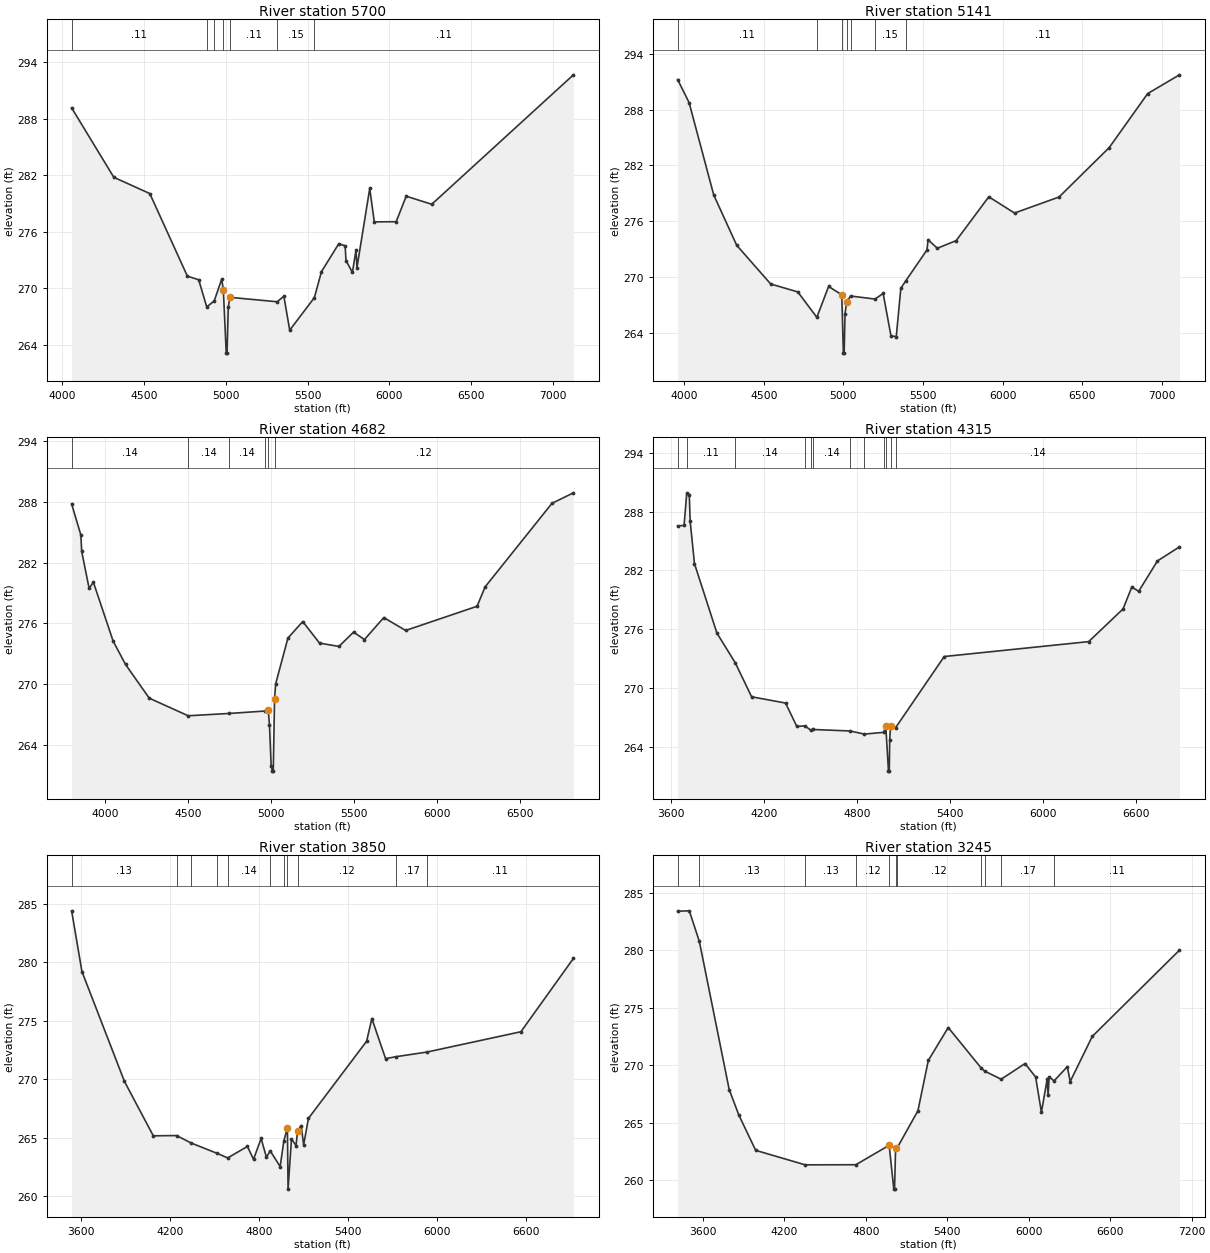
Type RM Length L Ch R = 1 ,5700    ,559,559,559
BEGIN DESCRIPTION:
ROBINSON BRANCH 8.0
END DESCRIPTION:
XS GIS Cut Line= 3
       3749905.8     10254714.28      3748319.82     10254656.98
      3746994.34     10255323.63
#Sta/Elev= 30
  4056.1  289.16  4314.2  281.78  4534.4  280.05  4764.5  271.27  4833.5  270.89
    4883     268  4928.7  268.64  4974.6  270.96  4984.7  269.77  5002.2  263.09
  5007.1  263.09  5014.7  267.98  5024.7  269.02  5314.3  268.55  5354.9  269.14
  5390.7  265.53  5541.6  268.99    5585  271.75  5690.6  274.71  5729.7   274.5
  5735.3  272.93  5774.3  271.66  5796.6  274.07  5802.2  272.17  5880.3  280.59
  5908.3  277.04  6042.2  277.06  6103.6  279.77  6259.8  278.91  7126.8  292.67
#Mann= 7 ,-1 , 0
  4056.1     .11       0    4883     .15       0  4928.7     .11       0
  4984.7     .06       0  5024.7     .11       0  5314.3     .15       0
  5541.6     .11       0
#XS Ineff= 1 ,-1
    4740  4974.6  270.96
Permanent Ineff=
       F
Bank Sta=4984.7,5024.7
XS Rating Curve= 0 ,0
Exp/Cntr=0.3,0.1

Type RM Length L Ch R = 1 ,5141    ,459,459,459
BEGIN DESCRIPTION:
ROBINSON BRANCH 7.0
END DESCRIPTION:
XS GIS Cut Line= 3
      3749827.63     10254013.76      3748358.89     10254380.94
      3746934.39     10255188.24
#Sta/Elev= 30
  3959.5  291.25  4031.4  288.77    4186  278.83  4330.4  273.41    4544  269.24
  4714.1  268.39  4833.6  265.65  4907.6  268.98  4990.1  268.08  5000.2   261.8
  5005.1   261.8  5010.7  266.04    5021  267.35  5045.6  267.95  5198.6  267.62
  5250.1  268.22  5299.3  263.65  5332.5  263.58  5361.1  268.78  5391.2  269.56
  5525.4  272.91  5532.1     274  5590.3  273.09  5708.6  273.91  5913.5  278.63
  6075.1  276.88    6355  278.61    6670  283.93  6911.4  289.74  7110.8  291.76
#Mann= 7 ,-1 , 0
  3959.5     .11       0  4833.6     .15       0  4990.1     .09       0
    5021     .15       0  5045.6     .11       0  5198.6     .15       0
  5391.2     .11       0
Bank Sta=4990.1,5021
XS Rating Curve= 0 ,0
Exp/Cntr=0.3,0.1

Type RM Length L Ch R = 1 ,4682    ,367,367,367
BEGIN DESCRIPTION:
ROBINSON BRANCH 6.0
END DESCRIPTION:
XS GIS Cut Line= 3
      3749666.16     10253844.49      3748384.76     10254111.66
       3746908.4      10254990.3
#Sta/Elev= 30
  3796.5  287.79  3852.1  284.73  3857.2   283.1  3902.1  279.44  3927.6  280.06
  4047.1  274.23  4121.7  271.93  4264.7   268.6  4499.6  266.86  4747.8  267.09
  4964.9  267.33  4982.5  267.41  4989.9  265.99  5000.2  261.91  5007.8  261.39
  5012.9  261.39  5020.6  268.54  5027.4  270.02  5101.3  274.54  5190.7  276.17
    5292  274.04  5408.8  273.71  5497.5  275.13  5562.7  274.39  5679.5  276.56
  5811.7  275.29  6242.3  277.68    6291   279.6  6694.1  287.85  6823.5  288.89
#Mann= 6 ,-1 , 0
  3796.5     .14       0  4499.6     .14       0  4747.8     .14       0
  4964.9     .12       0  4982.5     .08       0  5020.6     .12       0
Bank Sta=4982.5,5020.6
XS Rating Curve= 0 ,0
Exp/Cntr=0.3,0.1

Type RM Length L Ch R = 1 ,4315    ,465,465,465
BEGIN DESCRIPTION:
ROBINSON BRANCH 5.0
END DESCRIPTION:
XS GIS Cut Line= 3
      3749705.21     10253365.33      3748211.51     10253799.22
      3746858.89      10254789.8
#Sta/Elev= 30
    3646  286.54  3687.3  286.58  3704.8  289.91  3720.9  289.73  3726.6  287.01
  3754.4  282.68    3899  275.59  4018.1  272.53  4122.3  269.09  4340.9  268.45
  4413.8  266.06  4465.9  266.12  4505.7  265.65    4518  265.75  4756.1   265.6
  4848.5  265.28    4973  265.46  4986.6  266.07    5004   261.5  5009.1   261.5
  5011.8   264.7  5017.8  266.15  5050.5  265.95  5363.1   273.2  6293.4  274.72
    6515  278.06  6571.3   280.3  6615.3  279.85  6736.5  282.96    6878  284.39
#Mann= 12 ,-1 , 0
    3646     .15       0  3704.8     .11       0  4018.1     .14       0
  4465.9     .14       0  4505.7     .14       0    4518     .14       0
  4756.1     .14       0  4848.5     .14       0    4973     .13       0
  4986.6     .08       0  5017.8     .13       0  5050.5     .14       0
Bank Sta=4986.6,5017.8
XS Rating Curve= 0 ,0
Exp/Cntr=0.3,0.1

Type RM Length L Ch R = 1 ,3850    ,605,605,605
BEGIN DESCRIPTION:
ROBINSON BRANCH 4.0
END DESCRIPTION:
XS GIS Cut Line= 3
      3749695.71     10253005.07      3747952.64     10253387.02
      3746867.86     10254561.06
#Sta/Elev= 30
    3537  284.41  3606.5  279.22  3893.1  269.82  4087.6  265.17  4244.4  265.19
  4343.6  264.55  4517.6  263.67  4589.2  263.28  4722.3  264.26  4763.3  263.16
  4814.5  264.94  4850.1  263.34  4875.9  263.88  4942.8  262.54    4968  264.76
  4991.8  265.83  4996.1  260.61  5019.2   264.9  5049.9  264.34  5060.2  265.56
  5084.6  266.05  5101.1  264.39  5133.5  266.66  5525.9  273.26    5561   275.2
  5653.5  271.77  5726.3  271.94  5931.6  272.33  6565.9  274.07  6919.9  280.34
#Mann= 11 ,-1 , 0
    3537     .13       0  4244.4     .14       0  4343.6     .14       0
  4517.6     .14       0  4589.2     .14       0  4875.9     .13       0
    4968     .12       0  4991.8     .08       0  5060.2     .12       0
  5726.3     .17       0  5931.6     .11       0
#XS Ineff= 1 ,-1
    4000  4991.8  265.83
Permanent Ineff=
       T
Bank Sta=4991.8,5060.2
XS Rating Curve= 0 ,0
Exp/Cntr=0.3,0.1

Type RM Length L Ch R = 1 ,3245    ,693,693,693
BEGIN DESCRIPTION:
ROBINSON BRANCH 3.0
END DESCRIPTION:
XS GIS Cut Line= 3
      3749517.82     10252161.08      3747768.61     10252897.44
      3746542.95     10254213.37
#Sta/Elev= 30
  3413.5  283.39  3499.3  283.42  3573.4  280.76  3793.2  267.89  3864.1  265.68
  3988.2  262.61  4353.1  261.35  4726.3  261.36  4971.6  263.05  5005.7  259.24
  5011.1  259.24  5019.1  262.82  5030.1  262.82  5183.2  266.04  5259.9  270.42
  5406.5  273.28  5646.8   269.8    5674   269.5  5796.5  268.79  5972.3  270.15
  6050.5  268.98    6093  265.92  6135.5  268.79  6142.3  267.38  6149.6  269.01
  6185.8  268.64    6284  269.88    6305  268.59  6467.7  272.51  7109.7     280
#Mann= 11 ,-1 , 0
  3413.5     .17       0  3573.4     .13       0  4353.1     .13       0
  4726.3     .12       0  4971.6     .08       0  5019.1     .11       0
  5030.1     .12       0  5646.8     .17       0    5674     .11       0
  5796.5     .17       0  6185.8     .11       0
#XS Ineff= 1 ,-1
    3900  4971.6  263.05
Permanent Ineff=
       T
Bank Sta=4971.6,5019.1
XS Rating Curve= 0 ,0
Exp/Cntr=0.3,0.1

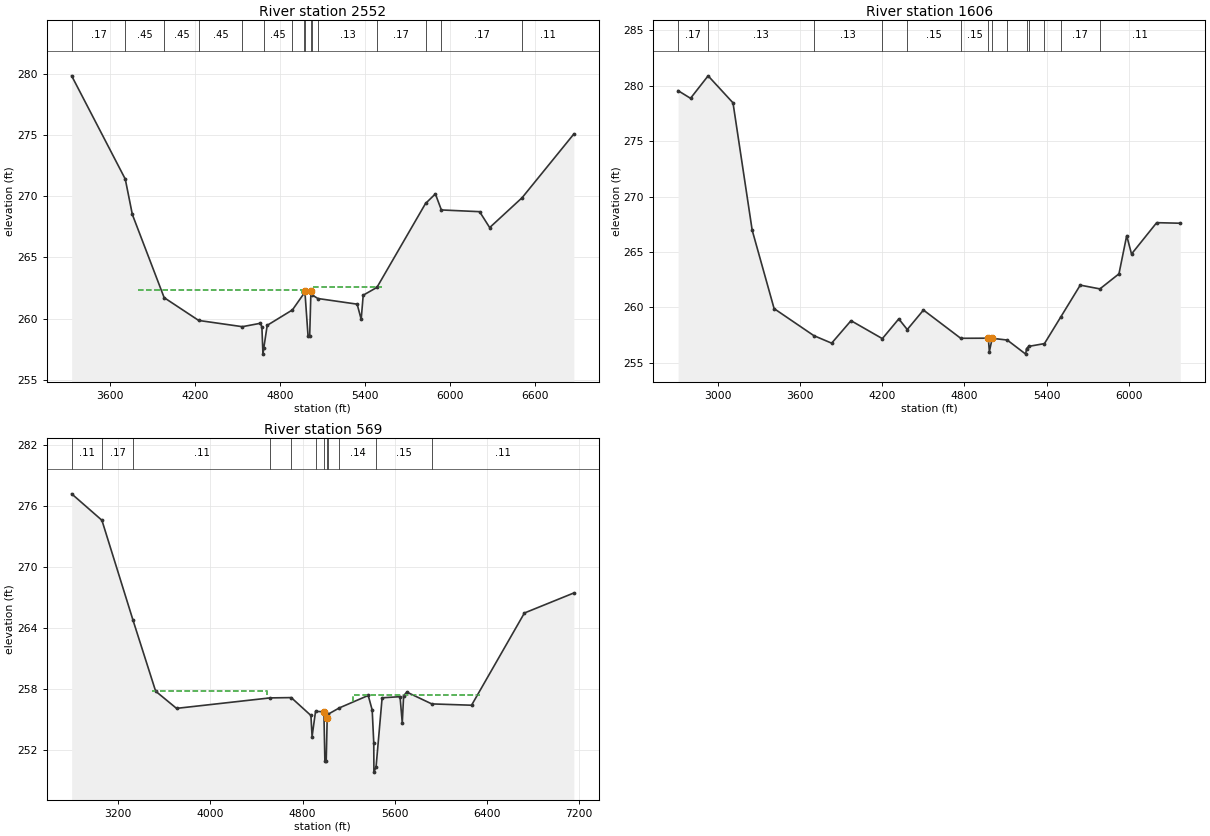
Type RM Length L Ch R = 1 ,2552    ,946,946,946
BEGIN DESCRIPTION:
Mapping XS ab20cbfe
END DESCRIPTION:
XS GIS Cut Line= 3
       3749421.4     10251793.27      3747917.91     10252050.21
      3746404.56     10253386.55
#Sta/Elev= 30
  3328.6  279.83    3707   271.4    3757  268.51  3981.5  261.72    4225  259.86
  4533.4  259.35  4661.2  259.63  4671.3  259.31  4678.7  257.11  4684.7  257.61
  4708.7  259.46  4886.7  260.72  4967.9  262.06  4974.6  262.25  4996.9   258.6
  5008.6   258.6  5017.3  262.24  5024.8  261.95  5066.1  261.65  5343.5  261.19
    5372  259.95  5386.2  261.92  5483.3  262.56  5826.2  269.41  5895.6  270.19
  5937.9  268.88  6207.7  268.74  6278.8  267.44  6507.7  269.88  6872.8  275.08
#Mann= 16 ,-1 , 0
  3328.6     .17       0    3707     .45       0  3981.5     .45       0
    4225     .45       0  4533.4     .45       0  4684.7     .45       0
  4886.7     .15       0  4967.9     .15       0  4974.6     .08       0
  5017.3     .15       0  5024.8     .15       0  5066.1     .13       0
  5483.3     .17       0  5826.2     .15       0  5937.9     .17       0
  6507.7     .11       0
#XS Ineff= 2 ,-1
    3800  4953.7  262.36  5031.5    5520  262.57
Permanent Ineff=
       T       T
Bank Sta=4974.6,5017.3
XS Rating Curve= 0 ,0
Exp/Cntr=0.3,0.1

Type RM Length L Ch R = 1 ,1606    ,1037,1037,1037
BEGIN DESCRIPTION:
ROBINSON BRANCH 2.0
END DESCRIPTION:
XS GIS Cut Line= 3
      3749348.47     10251494.66      3747501.25     10251393.96
      3746189.66     10252656.97
#Sta/Elev= 30
    2707  279.56  2797.7  278.87  2926.3   280.9  3108.2  278.46  3248.4  266.96
  3408.7  259.88  3699.1  257.44  3829.3  256.76  3970.8  258.79  4199.8  257.17
    4320  258.95  4381.9  257.99  4500.3  259.75  4772.7   257.2  4974.6  257.21
  4982.1     256  5002.9   257.2  5112.9  257.04  5247.7  255.77  5253.7  256.27
  5269.9  256.47  5384.7  256.72  5502.3  259.09  5646.4     262  5790.2  261.66
  5929.4  263.02    5986  266.47  6021.2  264.81  6205.1  267.64  6377.8  267.59
#Mann= 14 ,-1 , 0
    2707     .17       0  2926.3     .13       0  3699.1     .13       0
  4199.8     .13       0  4381.9     .15       0  4772.7     .15       0
  4974.6     .08       0  5002.9     .15       0  5112.9     .15       0
  5253.7     .17       0  5269.9     .15       0  5384.7     .15       0
  5502.3     .17       0  5790.2     .11       0
#XS Ineff= 1 ,-1
    3380  4500.3  259.75
Permanent Ineff=
       T
Bank Sta=4974.6,5002.9
XS Rating Curve= 0 ,0
Exp/Cntr=0.3,0.1

Type RM Length L Ch R = 1 ,569     ,0,0,0
BEGIN DESCRIPTION:
ROBINSON BRANCH 1.0
END DESCRIPTION:
XS GIS Cut Line= 3
      3749303.32     10251216.88      3747111.12     10250974.09
       3745032.7     10250400.96
#Sta/Elev= 30
  2794.4  277.21  3057.2  274.61  3327.4  264.78  3523.9   257.8  3705.3  256.11
  4517.4  257.14  4701.5  257.17  4872.5  255.41  4882.6  253.34  4912.7  255.82
  4985.1  255.77  4993.7  250.97  5005.4  250.97  5013.8  255.15  5024.1  255.55
    5120  256.16  5370.2  257.38  5404.6  255.95  5418.3  252.73  5419.6  249.84
  5438.2  250.34  5490.9  257.15  5646.5  257.26  5665.9  254.68  5677.7  257.36
  5705.4  257.71    5922  256.55  6267.7  256.42  6726.8  265.49    7156  267.46
#Mann= 12 ,-1 , 0
  2794.4     .11       0  3057.2     .17       0  3327.4     .11       0
  4517.4     .15       0  4701.5     .14       0  4912.7     .14       0
  4985.1     .08       0  5013.8     .11       0  5024.1     .14       0
    5120     .14       0  5438.2     .15       0    5922     .11       0
#XS Ineff= 2 ,-1
    3490  4490.2  257.82    5242    6340  257.38
Permanent Ineff=
       T       T
Bank Sta=4985.1,5013.8
XS Rating Curve= 0 ,0
Exp/Cntr=0.3,0.1

Chan Stop Cuts=-1
Use User Specified Reach Order=0
Composite Channel Slope=5