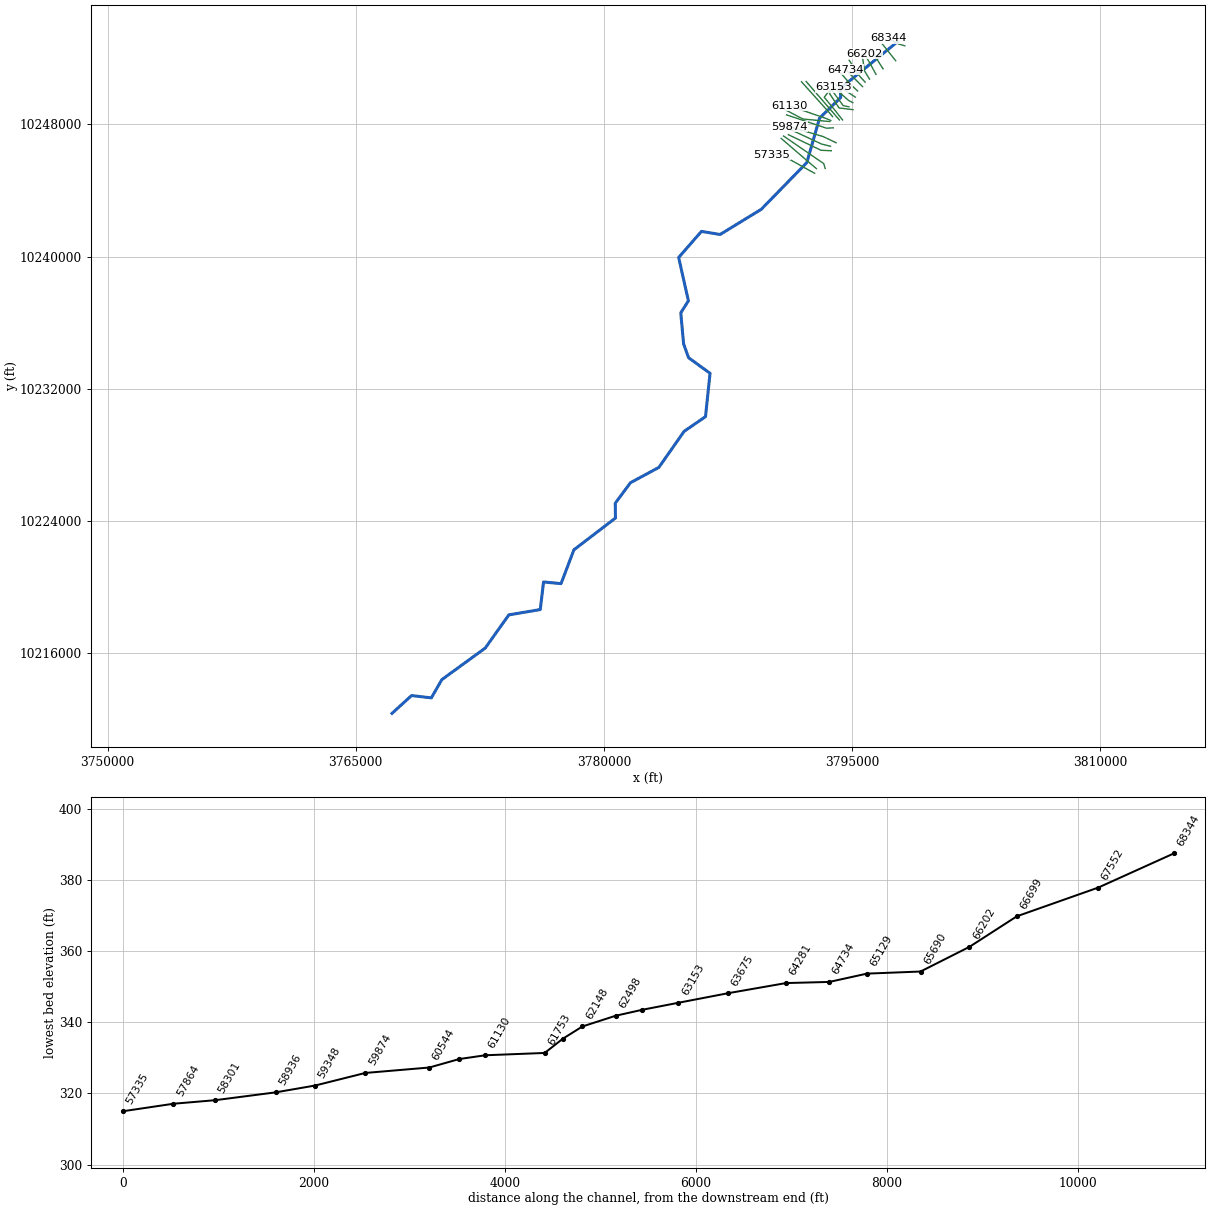
--- ROBINSON CREEK.prj (project) ---

Proj Title=ROBINSON CREEK Base Level Engineering
Current Plan=p01
Default Exp/Contr=0.3,0.1
English Units
Geom File=g01
Flow File=f01
Plan File=p01
Y Axis Title=Elevation
X Axis Title(PF)=Main Channel Distance
X Axis Title(XS)=Station
BEGIN DESCRIPTION:
ROBINSON CREEK
END DESCRIPTION:
DSS Export Rating Curves= 0
DSS Export Rating Curve Sorted= 0
DSS Export Volume Flow Curves= 0
DXF OffsetX= 0
DXF OffsetY= 0
DXF ScaleX= 1
DXF ScaleY= 10

--- ROBINSON CREEK.p01 (plan) ---

Plan Title=Multiple Run
Program Version=4.10
Short Identifier=Multiple
Geom File=g01
Flow File=f01
Subcritical Flow
K Sum by GR= 0
Std Step Tol= 0.01
Critical Tol= 0.01
Num of Std Step Trials= 20
Max Error Tol= 0.3
Flow Tol Ratio= 0.001
Split Flow NTrial= 30
Split Flow Tol= 0.02
Split Flow Ratio= 0.02
Log Output Level= 0
Friction Slope Method= 1
Unsteady Friction Slope Method= 2
Unsteady Bridges Friction Slope Method= 1
Parabolic Critical Depth
Global Vel Dist= 1 , 1 , 1
Global Log Level= 0
CheckData=True
Encroach Param=-1 ,0,0, 0
BEGIN DESCRIPTION:
Multiple Run
END DESCRIPTION:
Computation Interval=1HOUR
Output Interval=1HOUR
Run HTab= 0
Run UNet= 0
Run PostProcess= 0
Run WQNet= 0
UNET Theta= 1
UNET Theta Warmup= 1
UNET ZTol= 0.02
UNET ZSATol= 0.05
UNET MxIter= 20
UNET MaxInSteps= 0
UNET DtIC= 0
UNET DtMin= 0
UNET MaxCRTS= 20
UNET WFStab= 2
UNET SFStab= 1
UNET WFX= 1
UNET SFX= 1
UNET DSS MLevel= 4
UNET DZMax Abort= 100
UNET Convert EG Bridges= 0
UNET Use Existing IB Tables=-1
UNET Froude Reduction=False
UNET Froude Limit= 1
UNET Froude Power= 10
UNET Time Slicing=0,0, 5
UNET Junction Losses=0
Instantaneous Interval=1HOUR
Write IC File= 0
Write IC File at Sim End=0
Echo Input=False
Echo Parameters=False
Echo Output=False
Write Detailed= 0
WQ AD Non Conservative
WQ ULTIMATE=-1
WQ Max Comp Step=1HOUR
WQ Output Interval=15MIN
WQ Output Selected Increments= 0
WQ Output face flow=0
WQ Output face velocity=0
WQ Output face area=0
WQ Output face dispersion=0
WQ Output cell volume=0
WQ Output cell surface area=0
WQ Output cell continuity=0
WQ Output cumulative cell continuity=0
WQ Output face conc=0
WQ Output face dconc_dx=0
WQ Output face courant=0
WQ Output face peclet=0
WQ Output face adv mass=0
WQ Output face disp mass=0
WQ Output cell mass=0
WQ Output cell source sink temp=0
WQ Output cell source sink nsm=0
WQ Output MaxMinRange=-1
WQ Daily Max Min Mean=-1
WQ Daily Range=0
WQ Daily Time=0
WQ Create Restart=0
WQ Fixed Restart=0
WQ System Summary=0
WQ Use Fixed Temperature=0
Sorting and Armoring Iterations= 10
XS Update Threshold= 0.02
Hydraulics Update Threshold= 0.02
Energy Slope Method= 1
Volume Change Method= 0
XS Weighting Method= 0
Number of US Weighted Cross Sections= 1
Number of DS Weighted Cross Sections= 1
Upstream XS Weight=0.25
Main XS Weight=0.5
Downstream XS Weight=0.25
Number of DS XS's Weighted with US Boundary= 1
Upstream Boundary Weight= 1
Weight of XSs Associated with US Boundary= 0
Number of US XS's Weighted with DS Boundary= 1
Downstream Boundary Weight= 0.5
Weight of XSs Associated with DS Boundary= 0.5
Sediment Output Level= 4
Mass or Volume Output= 0
Output Increment Type= 1
Profile and TS Output Increment= 10
XS Output Flag= 0
XS Output Increment= 10
Disregard all LS=0
Disregard all Conn=0
Disregard all Breaches=0
Disregard all Pumps=0

--- ROBINSON CREEK.f01 (steady flow) ---

Flow Title=Multiple
Program Version=4.10
Number of Profiles= 7
Profile Names=10-year,25-year,50-year,1pct_min,100-year,1pct_plu,500-year
River Rch & RM=ROBINSON CREEK,Reach-1         ,68344
     307     400     527     230     696    2102    1244
River Rch & RM=ROBINSON CREEK,Reach-1         ,67552
    1223    1729    2405    1100    3323   10035    6558
River Rch & RM=ROBINSON CREEK,Reach-1         ,61942
    2047    2947    4150    1917    5789   17483   11653
River Rch & RM=ROBINSON CREEK,Reach-1         ,61130
    2047    2947    4150    1917    5789   17483   11653
River Rch & RM=ROBINSON CREEK,Reach-1         ,56828
    2303    3312    4660    2148    6487   19590   13012
River Rch & RM=ROBINSON CREEK,Reach-1         ,48931
    3560    5231    7467    3489   10537   31821   21710
River Rch & RM=ROBINSON CREEK,Reach-1         ,47829
    3232    4671    6592    3043    9190   27753   18485
River Rch & RM=ROBINSON CREEK,Reach-1         ,42357
    3644    5294    7499    3474   10490   31679   21239
River Rch & RM=ROBINSON CREEK,Reach-1         ,42043
    3644    5294    7499    3474   10490   31679   21239
River Rch & RM=ROBINSON CREEK,Reach-1         ,38959
    3664    5304    7493    3461   10451   31562   21036
River Rch & RM=ROBINSON CREEK,Reach-1         ,34743
    3628    5250    7415    3423   10336   31214   20791
River Rch & RM=ROBINSON CREEK,Reach-1         ,31135
    3900    5663    8018    3709   11201   33826   22630
River Rch & RM=ROBINSON CREEK,Reach-1         ,25196
    4242    6168    8738    4044   12214   36886   24701
River Rch & RM=ROBINSON CREEK,Reach-1         ,22205
    4215    6115    8651    3998   12073   36460   24336
River Rch & RM=ROBINSON CREEK,Reach-1         ,17064
    4368    6328    8942    4127   12463   37638   25055
River Rch & RM=ROBINSON CREEK,Reach-1         ,10458
    4335    6257    8818    4058   12254   37006   24491
River Rch & RM=ROBINSON CREEK,Reach-1         ,5940
    4307    6205    8733    4013   12120   36602   24163
Boundary for River Rch & Prof#=ROBINSON CREEK,Reach-1         , 1
Up Type= 0
Dn Type= 3
Dn Slope=0.0003
Boundary for River Rch & Prof#=ROBINSON CREEK,Reach-1         , 2
Up Type= 0
Dn Type= 3
Dn Slope=0.0003
Boundary for River Rch & Prof#=ROBINSON CREEK,Reach-1         , 3
Up Type= 0
Dn Type= 3
Dn Slope=0.0003
Boundary for River Rch & Prof#=ROBINSON CREEK,Reach-1         , 4
Up Type= 0
Dn Type= 3
Dn Slope=0.0003
Boundary for River Rch & Prof#=ROBINSON CREEK,Reach-1         , 5
Up Type= 0
Dn Type= 3
Dn Slope=0.0003
Boundary for River Rch & Prof#=ROBINSON CREEK,Reach-1         , 6
Up Type= 0
Dn Type= 3
Dn Slope=0.0003
Boundary for River Rch & Prof#=ROBINSON CREEK,Reach-1         , 7
Up Type= 0
Dn Type= 3
Dn Slope=0.0003
DSS Import GetInterval= 0
DSS Import GetPeak= 0
DSS Import FillOption= 0

--- ROBINSON CREEK.g01 (geometry) ---

Geom Title=Existing Conditions
Program Version=4.10

River Reach=ROBINSON CREEK  ,Reach-1
Reach XY= 30
      3797731.15     10252990.93      3794288.23     10250176.84
      3794298.23     10249616.84      3793020.87     10248367.58
      3792253.85     10245682.77      3789502.13     10242860.59
      3787018.19     10241339.16      3785885.86     10241523.27
      3784511.04      10239947.6      3785098.31     10237325.06
      3784638.38     10236597.73      3784809.28     10234720.26
      3785108.42     10233886.67      3786407.41     10232941.66
      3786132.68     10230321.36      3784839.39     10229430.43
      3783311.71      10227251.6      3781595.57     10226323.89
      3780679.66     10225085.41      3780691.47     10224189.73
      3778180.54     10222268.97      3777403.12     10220222.52
      3776346.06     10220324.88      3776147.47      10218655.6
      3774250.85     10218334.08      3772822.56     10216325.77
      3770200.26     10214418.89       3769564.9      10213313.6
      3768369.04     10213454.89      3767188.23     10212376.84

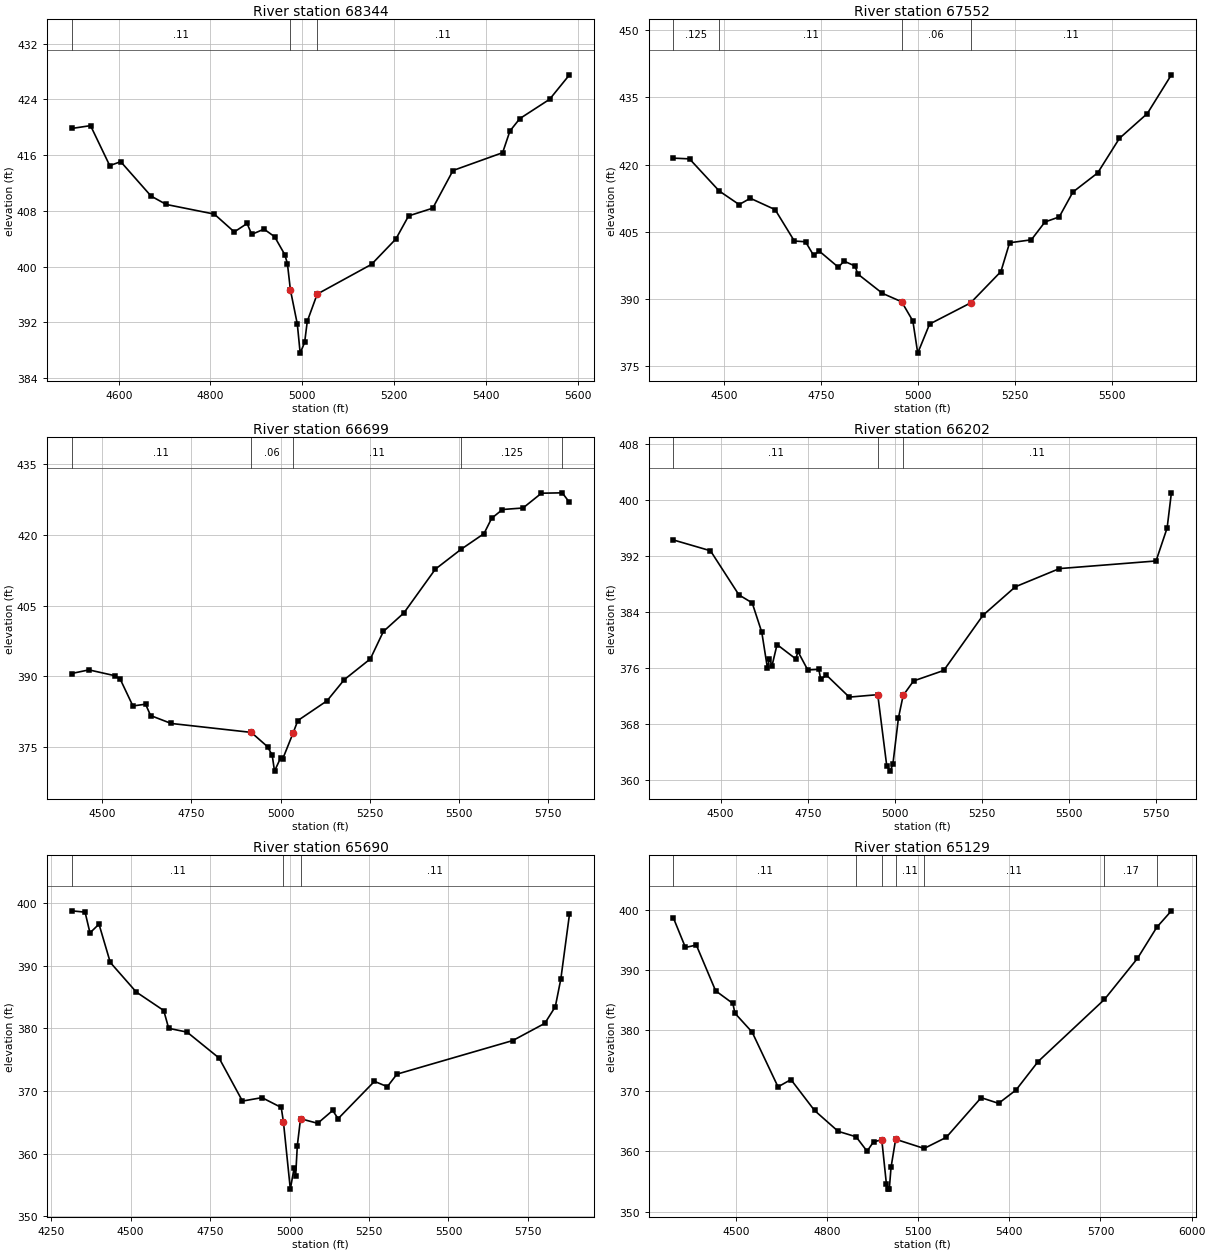
Type RM Length L Ch R = 1 ,68344   ,792,792,792
BEGIN DESCRIPTION:
ROBINSON CREEK 118.0
END DESCRIPTION:
XS GIS Cut Line= 3
      3798177.53     10252746.03      3797799.91     10252858.88
      3797198.65     10253199.36
#Sta/Elev= 30
  4497.3  419.83  4538.7  420.24  4580.5   414.5  4604.4  415.07  4670.6  410.13
  4703.7  408.93  4808.3  407.55  4851.9  404.99  4879.8   406.2  4889.9  404.64
  4916.8  405.39  4939.8   404.3    4962  401.73  4967.7  400.44  4974.2  396.68
  4989.3  391.76  4995.5   387.6  5005.2  389.13    5011  392.17  5032.6  396.07
    5151  400.34  5204.1  403.98  5231.8  407.29  5284.5   408.4  5328.5   413.8
  5436.7  416.36  5452.6  419.47  5474.2  421.25  5539.1  424.02  5582.4  427.53
#Mann= 3 , 0 , 0
  4497.3     .11       0  4974.2     .06       0  5032.6     .11       0
Bank Sta=4974.2,5032.6
XS Rating Curve= 0 ,0
Exp/Cntr=0.3,0.1

Type RM Length L Ch R = 1 ,67552   ,853,853,853
BEGIN DESCRIPTION:
Mapping XS 0cb81d05
END DESCRIPTION:
XS GIS Cut Line= 2
      3797627.56     10251842.25      3796825.74     10252846.65
#Sta/Elev= 30
  4368.3  421.46  4409.7   421.3  4486.5  414.13  4537.8  411.11  4566.7  412.51
  4630.7  409.98  4680.3  402.98  4709.2  402.81    4730  399.78  4744.4  400.75
    4794  397.13  4808.4   398.5  4837.3  397.39  4843.7  395.65  4907.7  391.31
  4957.3  389.43  4986.2  385.15  4998.8  377.98  5029.4  384.46  5135.1  389.17
  5213.5  396.17  5235.9  402.59    5292  403.25  5327.2  407.23    5364  408.35
  5399.3   413.9  5463.3  418.17  5519.3  425.87  5591.4  431.41  5653.5  440.04
#Mann= 4 ,-1 , 0
  4368.3    .125       0  4486.5     .11       0  4957.3     .06       0
  5135.1     .11       0
Bank Sta=4957.3,5135.1
XS Rating Curve= 0 ,0
Exp/Cntr=0.3,0.1

Type RM Length L Ch R = 1 ,66699   ,497,497,497
BEGIN DESCRIPTION:
Mapping XS ac07fe4b
END DESCRIPTION:
XS GIS Cut Line= 2
       3796859.4     10251355.72      3796112.72     10252535.48
#Sta/Elev= 30
  4414.1  390.61  4462.8  391.38  4535.7  390.14  4550.6   389.4  4586.1  383.72
  4621.6   384.1  4635.7  381.69  4693.3  380.01    4918  378.11  4963.8  375.06
  4976.7  373.27  4983.2  369.89  5000.2  372.69  5006.1  372.46  5035.8  378.08
  5048.5  380.62  5130.5  384.82    5179  389.32  5251.9  393.71  5288.4  399.53
    5346  403.47  5434.2  412.76  5506.6  416.99  5570.6   420.3  5592.1  423.56
  5622.4  425.42    5680  425.74  5731.7  428.88    5790  428.96  5810.3  426.93
#Mann= 5 ,-1 , 0
  4414.1     .11       0    4918     .06       0  5035.8     .11       0
  5506.6    .125       0    5790     .11       0
Bank Sta=4918,5035.8
XS Rating Curve= 0 ,0
Exp/Cntr=0.3,0.1

Type RM Length L Ch R = 1 ,66202   ,512,512,512
BEGIN DESCRIPTION:
ROBINSON CREEK 117.0
END DESCRIPTION:
XS GIS Cut Line= 3
      3796433.48     10251022.67      3796139.58     10251563.02
      3795739.04      10252270.5
#Sta/Elev= 30
    4365  394.32  4471.1  392.78  4552.8  386.47  4590.8  385.33  4618.4  381.12
  4634.5     376  4640.2  377.35  4647.8  376.37  4662.1  379.37  4716.1  377.31
  4721.9  378.38  4750.2  375.74  4781.8  375.83  4787.5  374.39  4803.6  375.01
  4869.2  371.86  4950.9  372.21  4976.7  362.05  4986.9  361.28  4994.4  362.31
  5010.3  368.89  5023.8   372.1  5053.6  374.17  5140.2  375.67  5252.8  383.56
  5345.6  387.63    5472  390.23  5749.1  391.32  5780.9  396.04  5793.1  401.06
#Mann= 3 , 0 , 0
    4365     .11       0  4950.9     .06       0  5023.8     .11       0
Bank Sta=4950.9,5023.8
XS Rating Curve= 0 ,0
Exp/Cntr=0.3,0.1

Type RM Length L Ch R = 1 ,65690   ,561,561,561
BEGIN DESCRIPTION:
ROBINSON CREEK 116.0
END DESCRIPTION:
XS GIS Cut Line= 3
      3796043.59      10250737.5      3795741.51     10251230.55
      3795595.94     10252207.94
#Sta/Elev= 30
  4314.3  398.78  4356.8  398.57  4372.2  395.26  4400.6  396.65  4436.1  390.54
  4517.9  385.81  4604.3  382.86  4619.8  380.02  4677.8  379.41  4778.4  375.27
  4851.9   368.4  4913.3  368.95  4973.9  367.38  4980.8  365.08  5002.5  354.34
  5014.2  357.64  5019.3  356.51  5024.5  361.28  5034.6  365.58  5088.6  364.85
  5135.7   366.9  5152.9  365.59  5267.1  371.55  5307.6   370.7  5337.9   372.7
  5702.5  378.07    5803  380.81  5836.1  383.47  5853.5   387.9  5880.7  398.24
#Mann= 3 , 0 , 0
  4314.3     .11       0  4980.8     .06       0  5034.6     .11       0
Bank Sta=4980.8,5034.6
XS Rating Curve= 0 ,0
Exp/Cntr=0.3,0.1

Type RM Length L Ch R = 1 ,65129   ,395,395,395
BEGIN DESCRIPTION:
ROBINSON CREEK 115.0
END DESCRIPTION:
XS GIS Cut Line= 3
      3795776.23     10250553.47      3795400.43     10250962.56
       3794814.4     10251872.95
#Sta/Elev= 30
  4295.1  398.59  4334.5  393.73  4370.3  394.13  4433.8  386.56  4490.5  384.47
  4497.3  382.85    4554  379.72  4639.1  370.67  4681.6  371.87  4759.3  366.76
    4837  363.31    4896  362.41  4932.1  360.02  4953.4  361.58  4980.5   361.9
  4995.7  354.59  5001.7  353.75  5005.2  353.75  5010.9  357.34  5026.1     362
  5119.8  360.48  5192.5  362.31  5307.4  368.88  5364.8  367.94  5422.2  370.15
  5494.9  374.86    5713  385.13  5821.7  391.92  5885.3  397.07  5933.3  399.79
#Mann= 7 ,-1 , 0
  4295.1     .11       0    4896     .11       0  4980.5     .06       0
  5026.1     .11       0  5119.8     .11       0    5713     .17       0
  5885.3     .11       0
Bank Sta=4980.5,5026.1
XS Rating Curve= 0 ,0
Exp/Cntr=0.3,0.1

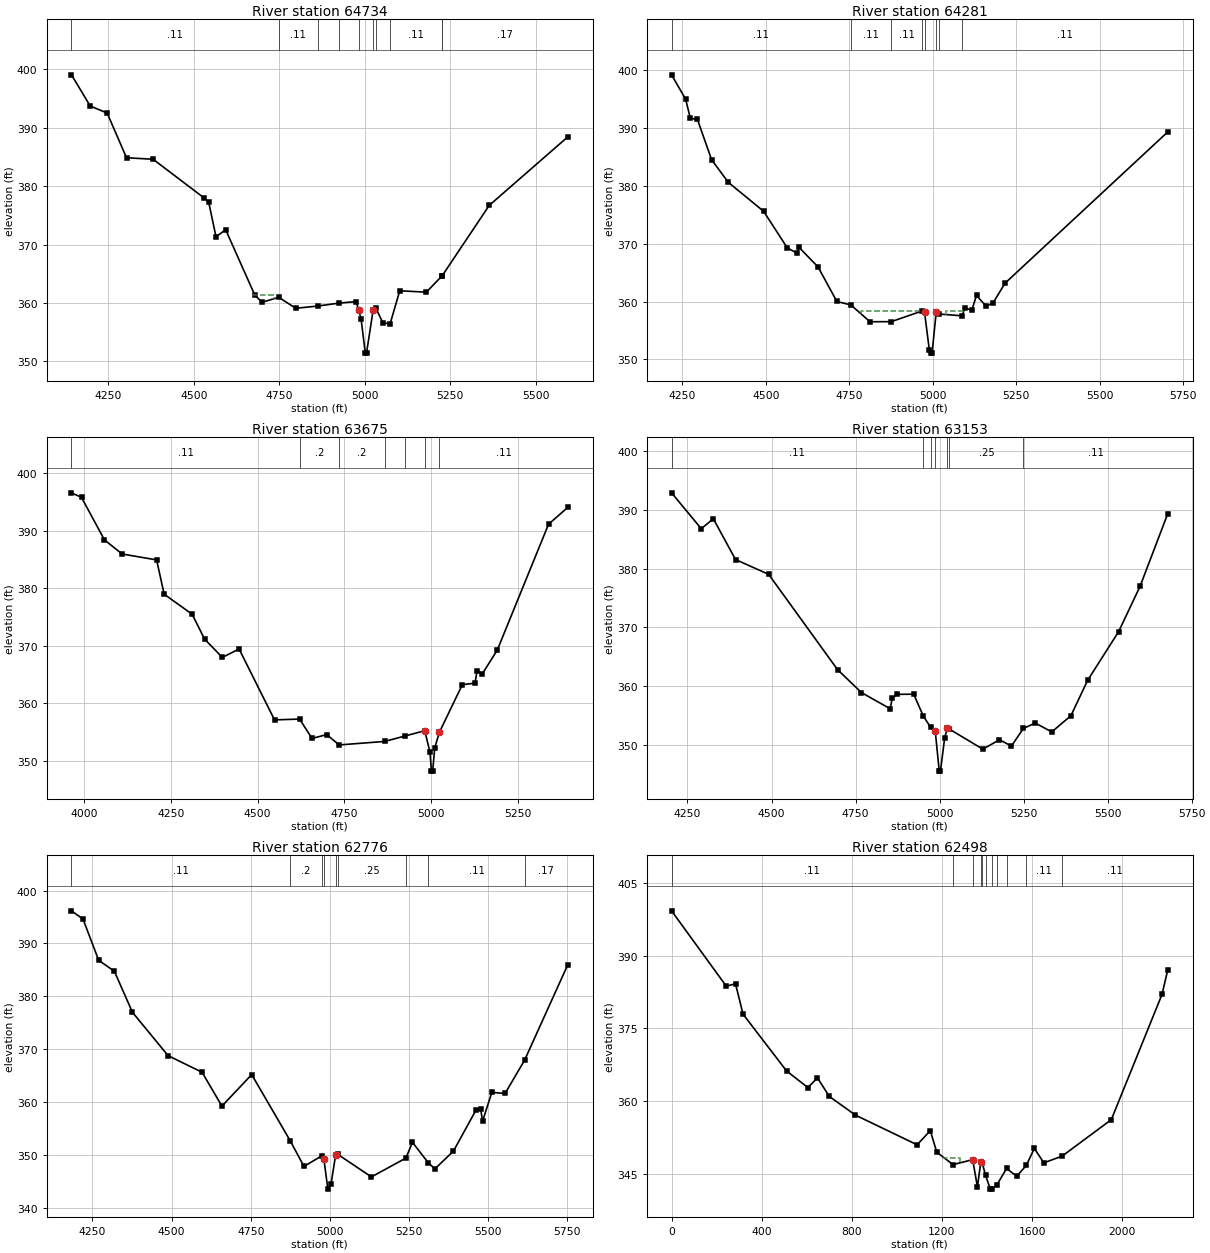
Type RM Length L Ch R = 1 ,64734   ,453,453,453
BEGIN DESCRIPTION:
ROBINSON CREEK 114.0
END DESCRIPTION:
XS GIS Cut Line= 3
      3795623.48     10250279.14      3795187.71     10250720.02
      3794599.36     10251307.31
#Sta/Elev= 30
  4142.3  399.07  4197.2  393.72  4246.6  392.53  4303.2  384.87    4381  384.61
  4529.5  378.01  4543.6  377.24  4564.9  371.34  4593.2  372.54    4678   361.4
  4699.2  360.12  4748.7  360.96  4798.2  359.09  4861.8  359.47  4925.5  359.98
    4975  360.24    4982  358.78  4989.1  357.28  5001.5  351.41    5005  351.41
  5024.5  358.79  5031.5   359.2  5052.8  356.62    5074  356.42  5102.2  362.09
    5180  361.85  5225.6  364.62  5226.1  364.64  5363.9  376.71  5593.5  388.44
#Mann= 10 ,-1 , 0
  4142.3     .11       0  4748.7     .11       0  4861.8     .11       0
  4925.5     .11       0    4982     .06       0  5024.5     .11       0
  5031.5     .11       0    5074     .11       0  5225.6     .15       0
  5226.1     .17       0
#XS Ineff= 1 ,-1
    4670  4734.6  361.32
Permanent Ineff=
       F
Bank Sta=4982,5024.5
XS Rating Curve= 0 ,0
Exp/Cntr=0.3,0.1

Type RM Length L Ch R = 1 ,64281   ,606,606,606
BEGIN DESCRIPTION:
ROBINSON CREEK 113.0
END DESCRIPTION:
XS GIS Cut Line= 3
      3795323.11     10250016.86      3794928.89     10250385.33
      3794305.88     10251097.33
#Sta/Elev= 30
  4217.9  399.22    4260  395.01  4274.2  391.68  4295.2  391.53  4337.7  384.55
  4387.5  380.64  4493.5  375.62  4564.3   369.3  4592.7   368.4  4599.5  369.38
  4656.2  366.01  4712.8  360.02  4754.8  359.42  4811.9  356.52  4875.5  356.53
  4967.6  358.37  4975.2  358.19  4989.4  351.71  4994.3  351.09  4997.8  351.09
  5010.3  358.25  5017.6  357.86  5088.1  357.54  5095.7  358.95  5116.6  358.48
  5130.8  361.06  5159.3  359.23  5180.2  359.76  5216.3  363.19  5703.6  389.36
#Mann= 8 ,-1 , 0
  4217.9     .11       0  4754.8     .11       0  4875.5     .11       0
  4967.6     .09       0  4975.2     .06       0  5010.3     .09       0
  5017.6     .11       0  5088.1     .11       0
#XS Ineff= 4 ,-1
    4785  4967.6  358.37  5038.8    5093  358.34  5095.7    5120  358.95
  5130.8    5195  361.06
Permanent Ineff=
       T       F       F       F
Bank Sta=4975.2,5010.3
XS Rating Curve= 0 ,0
Exp/Cntr=0.3,0.1

Type RM Length L Ch R = 1 ,63675   ,522,522,522
BEGIN DESCRIPTION:
ROBINSON CREEK 112.0
END DESCRIPTION:
XS GIS Cut Line= 3
      3795190.39      10249642.4      3794238.88     10250273.75
      3793991.32     10250422.07
#Sta/Elev= 30
  3963.6  396.58  3992.5  395.78  4058.7   388.4  4109.8  385.95    4209  384.93
  4230.7  378.97  4311.3   375.5  4347.4  371.16  4398.5  367.99  4446.7  369.46
  4548.9  357.14    4621  357.28  4657.1  353.92  4699.2  354.58  4735.3  352.79
  4866.7   353.4  4924.8  354.34  4981.9  355.26    4997  351.51  5001.2  348.24
  5004.7  348.24  5010.7  352.28    5024  354.98  5090.2  363.26  5126.8  363.52
  5132.7  365.66  5148.2  365.18    5191  369.27  5338.8  391.13  5394.1  394.05
#Mann= 7 ,-1 , 0
  3963.6     .11       0    4621      .2       0  4735.3      .2       0
  4866.7      .2       0  4924.8     .11       0  4981.9     .06       0
    5024     .11       0
Bank Sta=4981.9,5024
XS Rating Curve= 0 ,0
Exp/Cntr=0.3,0.1

Type RM Length L Ch R = 1 ,63153   ,377,377,377
BEGIN DESCRIPTION:
ROBINSON CREEK 111.0
END DESCRIPTION:
XS GIS Cut Line= 3
      3795035.88     10249309.55      3794774.36     10249448.24
      3793888.78     10250228.81
#Sta/Elev= 30
  4202.6  392.92  4290.9  386.82  4326.9   388.5  4392.9  381.56  4491.5  379.04
  4696.3  362.83  4767.4  358.92  4852.8  356.17  4859.4  357.95  4873.6  358.61
    4923  358.64  4951.4  354.95  4973.2     353  4987.2  352.31    4999  345.54
  5002.6  345.54    5015  351.14  5022.6  352.86  5029.2  352.69  5128.8  349.28
  5178.2  350.88  5213.8  349.81  5249.3   352.8  5284.4  353.73  5333.8  352.22
  5390.7  354.97  5440.4  360.99  5532.9  369.31  5596.5  377.01  5679.1   389.4
#Mann= 7 ,-1 , 0
  4202.6     .11       0  4951.4     .11       0  4973.2     .11       0
  4987.2     .06       0  5022.6     .11       0  5029.2     .25       0
  5249.3     .11       0
#XS Ineff= 2 ,-1
  5284.4    5380  353.73
Permanent Ineff=
       F       F
Bank Sta=4987.2,5022.6
XS Rating Curve= 0 ,0
Exp/Cntr=0.3,0.1

Type RM Length L Ch R = 1 ,62776   ,278,278,278
BEGIN DESCRIPTION:
ROBINSON CREEK 110.0
END DESCRIPTION:
XS GIS Cut Line= 3
      3794796.17     10249057.94      3794453.41     10249131.25
      3793732.56     10250111.53
#Sta/Elev= 30
    4184  396.17  4220.5   394.6  4269.9  386.82  4319.4  384.75  4376.6  376.99
  4489.1   368.8  4596.4  365.66  4659.1  359.26  4753.2  365.22  4874.3  352.76
  4918.3  347.86  4974.6  349.87  4981.1  349.28  4993.7  343.57  5003.9  344.62
  5018.4  350.08  5024.8  350.15  5131.3  345.88    5240  349.43  5260.9  352.41
    5311  348.54  5331.9   347.4  5390.4  350.77  5461.4   358.5  5476.1  358.76
  5482.3  356.42  5511.6  361.86  5553.3  361.65  5614.9  367.93  5751.3  385.97
#Mann= 9 ,-1 , 0
    4184     .11       0  4874.3      .2       0  4974.6     .11       0
  4981.1     .06       0  5018.4     .11       0  5024.8     .25       0
    5240     .11       0    5311     .11       0  5614.9     .17       0
#XS Ineff= 3 ,-1
    4880  4974.6  349.87  5260.9    5410  352.41
Permanent Ineff=
       F       F       F
Bank Sta=4981.1,5018.4
XS Rating Curve= 0 ,0
Exp/Cntr=0.3,0.1

Type RM Length L Ch R = 1 ,62498   ,350,350,350
XS GIS Cut Line= 5
       3795045.6      10248885.9      3794204.45     10248990.06
      3794204.45     10248990.06      3793636.74     10249846.83
      3793691.43     10250096.83
#Sta/Elev= 30
       0  399.21   242.7   383.7   283.8  384.18   317.3  377.93   510.4  366.24
   605.1  362.81   647.7  364.82   699.8     361   815.8  357.15  1089.8  351.03
  1148.4  353.95    1177  349.51  1249.2  346.95  1336.4  347.97  1357.5  342.36
  1372.5  347.48  1378.5  347.35  1393.6  344.75  1414.6   341.9  1423.7  342.02
  1444.7  342.83  1486.8  346.15    1532  344.55  1574.1  346.77  1610.2  350.27
  1652.3  347.31  1733.5   348.7  1951.8  356.21  2176.6  381.98  2202.6  387.11
#Mann= 11 ,-1 , 0
       0     .11       0  1249.2     .11       0  1336.4     .06       0
  1372.5     .11       0  1378.5     .25       0  1393.6     .25       0
  1423.7     .25       0  1444.7     .25       0  1486.8     .25       0
  1574.1     .11       0  1733.5     .11       0
#XS Ineff= 2 ,-1
    1200  1279.3  348.33  1610.2    1820  350.27
Permanent Ineff=
       F       F
Bank Sta=1336.4,1372.5
XS Rating Curve= 0 ,0
Exp/Cntr=0.3,0.1

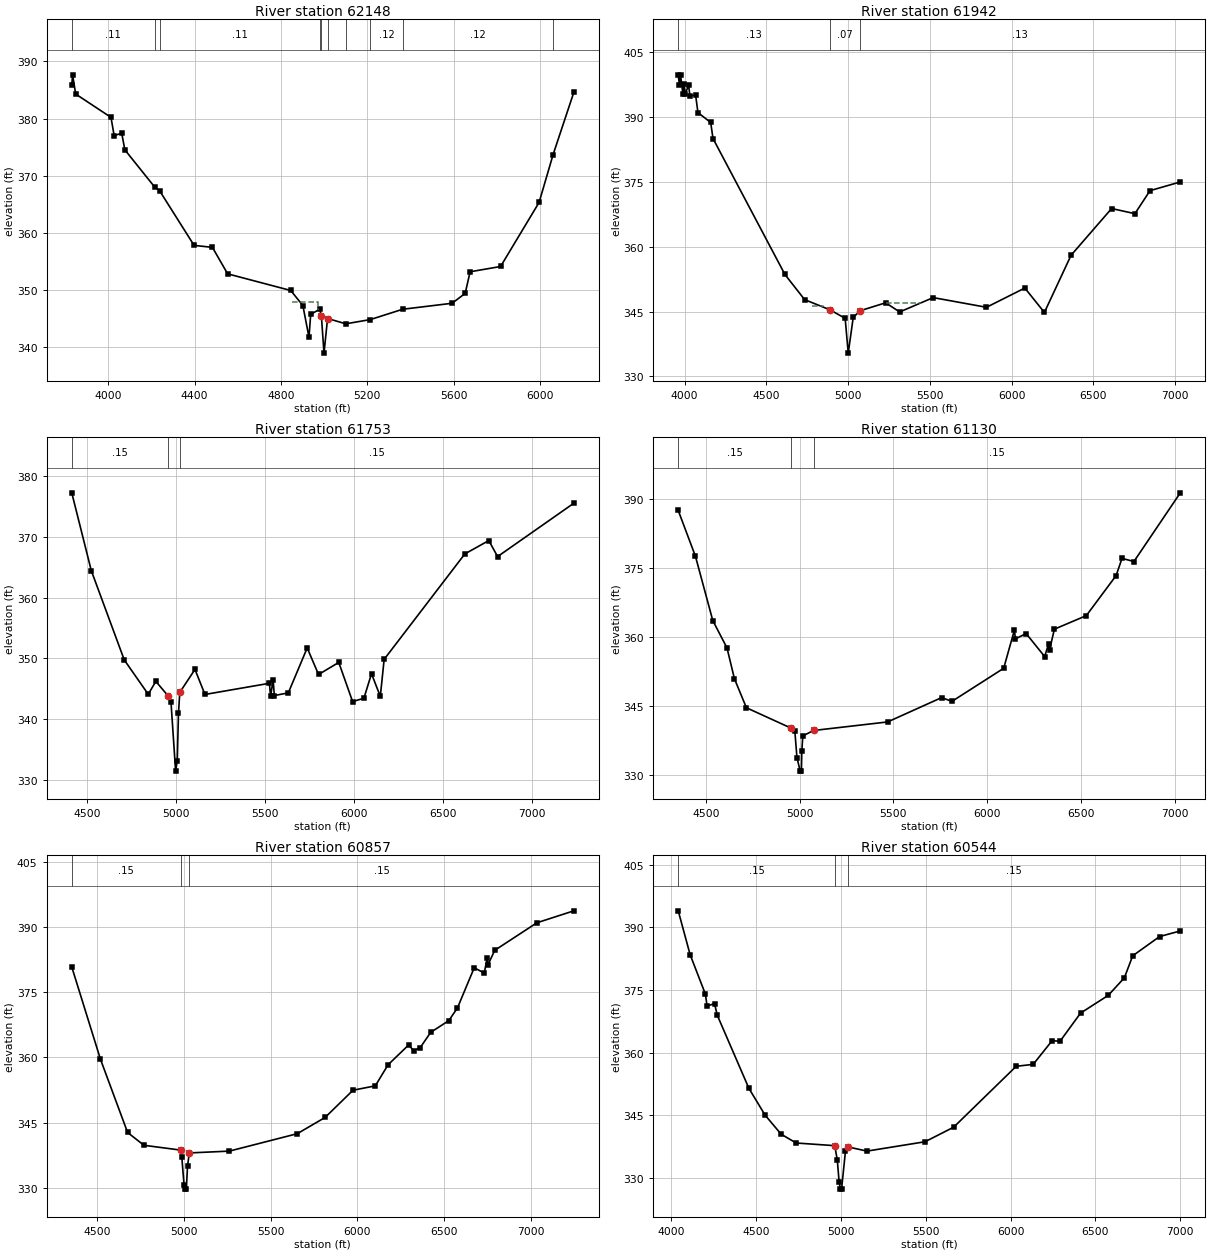
Type RM Length L Ch R = 1 ,62148   ,206,206,206
BEGIN DESCRIPTION:
ROBINSON CREEK 109.0
END DESCRIPTION:
XS GIS Cut Line= 4
      3794415.11     10248263.05      3793931.19     10248879.34
      3793308.36     10249634.55      3793653.11      10250081.2
#Sta/Elev= 30
  3830.8  385.86  3834.5  387.66    3849  384.29  4012.6   380.2  4027.1  377.01
  4062.3  377.42  4076.8  374.51  4214.9  367.99  4237.6  367.35  4397.6  357.76
  4482.6  357.41  4553.1  352.77  4845.5  349.85  4901.8  347.21  4930.1  341.65
    4938  345.67  4979.6  346.56  4987.5  345.41  4999.7  338.87  5016.2  344.94
  5100.8  344.01  5214.2  344.75  5364.1  346.56  5593.3  347.61    5654  349.35
  5676.7  353.13    5818  354.06  5996.4  365.29  6061.3  373.67  6157.5  384.61
#Mann= 10 ,-1 , 0
  3830.8     .11       0  4214.9     .17       0  4237.6     .11       0
  4979.6     .11       0  4987.5     .06       0  5016.2     .11       0
  5100.8     .12       0  5214.2     .12       0  5364.1     .12       0
  6061.3     .17       0
#XS Ineff= 1 ,-1
    4850  4973.2  347.79
Permanent Ineff=
       F
Bank Sta=4987.5,5016.2
XS Rating Curve= 0 ,0
Exp/Cntr=0.3,0.1

Type RM Length L Ch R = 1 ,61942   ,189,189,189
BEGIN DESCRIPTION:
Mapping XS 69b8d8c0
END DESCRIPTION:
XS GIS Cut Line= 2
      3794221.99     10248265.19      3792215.12     10250590.53
#Sta/Elev= 30
    3961  399.68  3968.6  397.35  3975.2  399.76  3989.4  395.33    3996  397.66
  4003.7   395.4  4024.6  397.32  4032.2  394.88  4067.3  395.08  4081.6  391.02
  4159.5  388.75  4173.7  385.03  4613.6  353.59  4734.3  347.77  4890.1   345.4
  4982.2  343.45    5001   335.4  5031.6  343.67  5074.4  345.21  5230.1  347.04
  5315.7  344.92  5520.8  348.24  5846.7     346  6081.4  350.45  6201.1  344.81
  6364.4  358.04  6612.4  368.84  6754.9  367.65  6847.1  372.97  7032.6  374.99
#Mann= 3 , 0 , 0
    3961     .13       0  4890.1     .07       0  5074.4     .13       0
#XS Ineff= 4 ,-1
    4780  4847.3  346.38  5230.1    5445  347.04  5520.8    5997  348.24
  6081.4    6280  350.45
Permanent Ineff=
       F       F       F       F
Bank Sta=4890.1,5074.4
XS Rating Curve= 0 ,0
Exp/Cntr=0.3,0.1

Type RM Length L Ch R = 1 ,61753   ,623,623,623
BEGIN DESCRIPTION:
ROBINSON CREEK 108.0
END DESCRIPTION:
XS GIS Cut Line= 3
      3793808.91     10248467.23      3793617.93     10248699.87
      3791933.93     10250571.37
#Sta/Elev= 30
  4415.4  377.29  4524.9  364.47  4710.1  349.74  4844.7  344.08  4887.3  346.21
  4958.3  343.74  4972.5  342.75  4998.4  331.41  5007.6  333.14  5014.4  340.92
  5021.8  344.39    5107  348.18  5163.1  344.05  5524.9  345.89  5531.6  343.74
  5545.8  346.47  5552.5  343.87    5631  344.31  5737.1  351.72  5800.7  347.34
  5914.3  349.33    5992  342.87  6055.5  343.43  6098.1  347.47  6147.5  343.73
  6169.1  349.84  6622.1  367.22  6756.6  369.42    6806  366.78    7234  375.58
#Mann= 3 , 0 , 0
  4415.4     .15       0  4958.3     .07       0  5021.8     .15       0
#XS Ineff= 3 ,-1
    4775  4887.3  346.21  5737.1    6300  351.72    5107    5700  348.18
Permanent Ineff=
       F       F       F
Bank Sta=4958.3,5021.8
XS Rating Curve= 0 ,0
Exp/Cntr=0.3,0.1

Type RM Length L Ch R = 1 ,61130   ,273,273,273
BEGIN DESCRIPTION:
ROBINSON CREEK 107.0
END DESCRIPTION:
XS GIS Cut Line= 3
      3793708.25     10248231.11       3793371.4     10248370.01
       3791183.9     10249123.49
#Sta/Elev= 30
  4352.6  387.46  4444.6  377.47  4536.9  363.51  4612.6  357.57  4652.3  350.86
  4716.2  344.55  4954.6  340.11  4974.6  339.44  4985.8  333.72    5003  330.76
  5009.5  330.76  5011.8  335.09    5017  338.42  5074.2   339.6  5469.4  341.46
  5757.2  346.75  5812.8  345.94  6088.5  353.13  6145.7  361.44    6151  359.52
  6208.1  360.69  6307.2  355.68  6327.7  358.41    6333   357.1  6358.9  361.64
  6529.3  364.59    6688  373.29  6719.7  377.04  6783.2  376.36  7030.6   391.3
#Mann= 3 , 0 , 0
  4352.6     .15       0  4954.6     .07       0  5074.2     .15       0
Bank Sta=4954.6,5074.2
XS Rating Curve= 0 ,0
Exp/Cntr=0.3,0.1

Type RM Length L Ch R = 1 ,60857   ,313,313,313
BEGIN DESCRIPTION:
ROBINSON CREEK 106.0
END DESCRIPTION:
XS GIS Cut Line= 3
       3793642.2     10248165.15      3792017.24      10248321.4
      3790899.23     10248908.18
#Sta/Elev= 30
  4353.1  380.83  4518.2  359.62    4675  342.73  4769.4  339.78  4980.3  338.68
  4987.5  337.08  5000.4  330.75  5007.2  329.69  5013.7  329.69  5020.5   334.9
  5030.6  338.02  5261.6  338.44  5653.4  342.45  5814.2   346.2  5974.9  352.46
  6103.3  353.46  6176.9  358.31  6296.2   362.9  6323.9  361.54  6362.3  362.26
  6422.8  365.78    6527  368.47  6577.2  371.41  6673.8  380.65  6731.6  379.42
    6748   382.8  6753.6  381.38  6792.1  384.66  7035.2     391  7248.2  393.75
#Mann= 3 , 0 , 0
  4353.1     .15       0  4980.3     .07       0  5030.6     .15       0
Bank Sta=4980.3,5030.6
XS Rating Curve= 0 ,0
Exp/Cntr=0.3,0.1

Type RM Length L Ch R = 1 ,60544   ,670,670,670
BEGIN DESCRIPTION:
ROBINSON CREEK 105.0
END DESCRIPTION:
XS GIS Cut Line= 3
      3793857.51     10247786.68      3793440.85     10247765.84
      3791031.97     10248571.12
#Sta/Elev= 30
  4042.7  393.92  4112.4  383.46  4202.6  373.99  4212.6  371.15  4256.4   371.7
  4272.6  368.93  4458.9  351.43  4553.9  345.04  4648.7  340.46  4737.2  338.35
  4964.6  337.71  4979.7  334.22  4990.2  329.05  4998.2  327.31  5004.7  327.31
  5027.7  336.46    5043  337.41  5154.1  336.41  5496.3  338.65  5665.1  342.14
  6033.2  356.71  6133.3  357.17    6245  362.85  6291.2  362.69  6412.3  369.44
  6575.5  373.69  6670.2  377.89  6719.5  383.16  6877.6  387.76  6999.8  389.11
#Mann= 3 , 0 , 0
  4042.7     .15       0  4964.6     .07       0    5043     .15       0
Bank Sta=4964.6,5043
XS Rating Curve= 0 ,0
Exp/Cntr=0.3,0.1

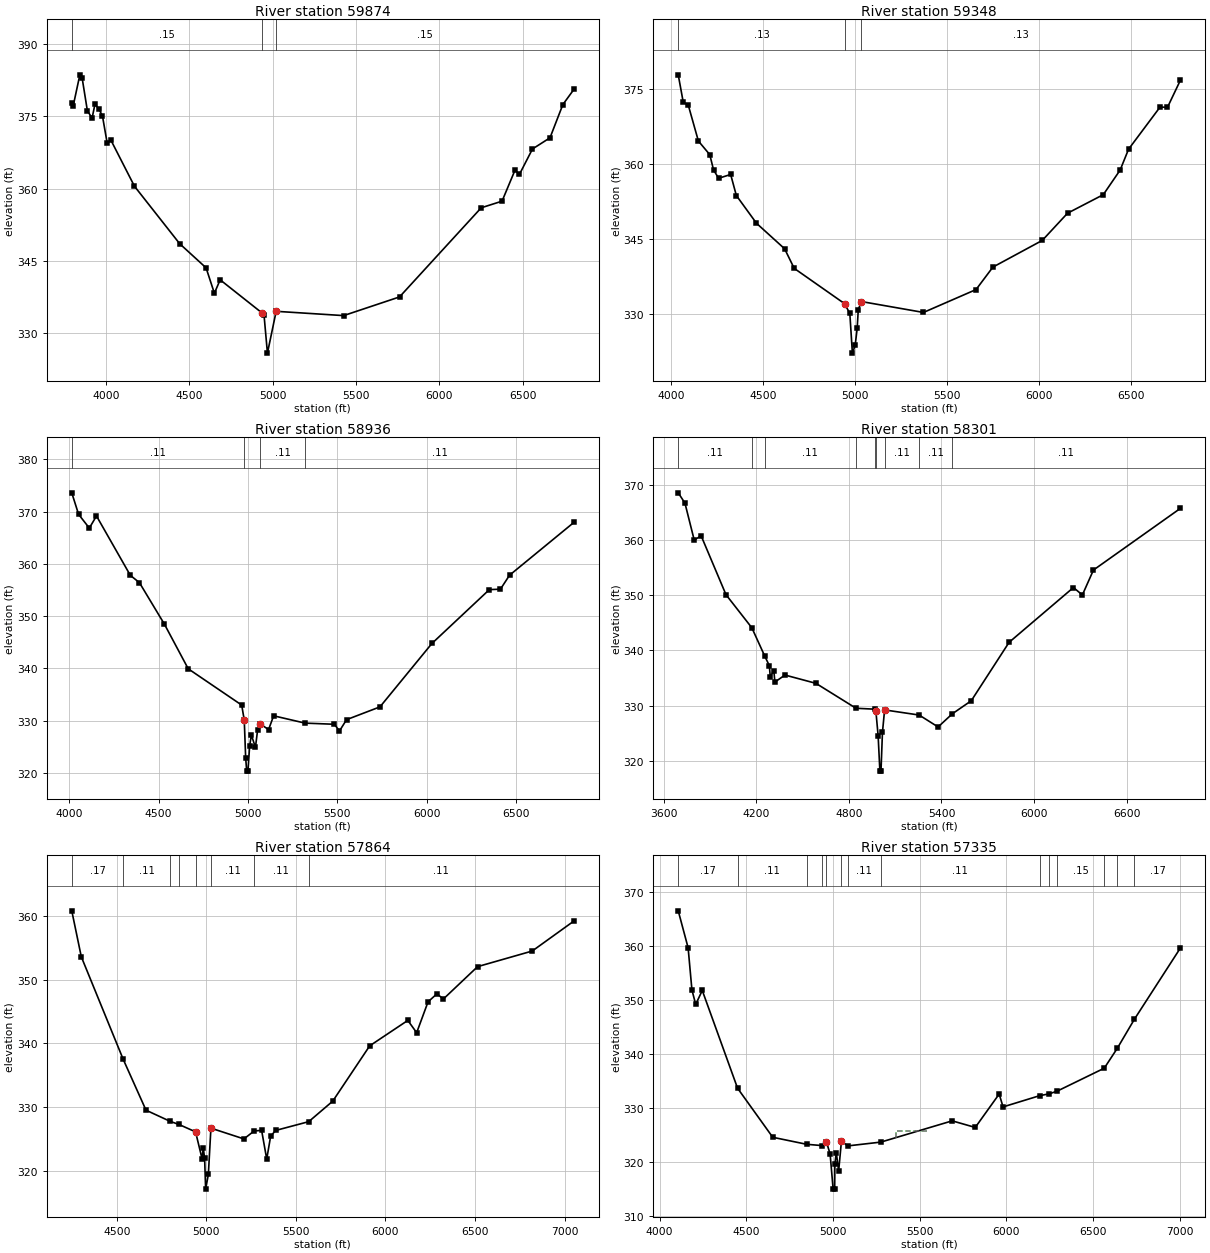
Type RM Length L Ch R = 1 ,59874   ,526,526,526
BEGIN DESCRIPTION:
ROBINSON CREEK 104.0
END DESCRIPTION:
XS GIS Cut Line= 3
      3794024.19     10246883.89      3793253.35     10247255.43
      3791184.67     10247866.31
#Sta/Elev= 30
  3794.9  377.81  3803.7  377.21  3843.4  383.63  3857.4  382.91  3888.6  376.15
  3916.8  374.64  3933.9  377.49  3956.5  376.61  3979.1  375.06  4007.3  369.45
  4029.9  370.04  4171.1  360.47  4442.5  348.52  4600.8  343.51  4650.6  338.23
  4685.3  341.02  4939.2  334.06  4948.3  333.79    4969  325.78  5021.3  334.47
  5426.2  333.58  5761.6  337.46  6251.7  355.99  6376.8  357.37  6454.3   363.8
    6481  362.93  6559.4  368.22  6664.5  370.54  6741.7  377.45  6807.6  380.59
#Mann= 3 , 0 , 0
  3794.9     .15       0  4939.2     .07       0  5021.3     .15       0
Bank Sta=4939.2,5021.3
XS Rating Curve= 0 ,0
Exp/Cntr=0.3,0.1

Type RM Length L Ch R = 1 ,59348   ,412,412,412
BEGIN DESCRIPTION:
ROBINSON CREEK 103.0
END DESCRIPTION:
XS GIS Cut Line= 3
      3793683.92     10246672.09      3793145.71     10246807.51
      3791176.94     10247724.19
#Sta/Elev= 30
  4040.1  377.79    4067  372.38  4095.1  371.68  4149.5  364.58  4211.3  361.86
    4232   358.8  4259.5  357.14  4324.8   357.9  4355.7   353.7  4465.1  348.16
  4617.8  343.07  4669.9  339.16  4943.6  332.11    4972  330.15  4985.9  322.24
  5000.9  323.77  5011.9  327.17  5017.8  330.89    5034  332.54  5371.9  330.36
  5657.5  334.93    5749  339.41  6017.2  344.74  6154.4  350.17  6348.5  353.87
    6440  358.78  6485.7  362.94  6656.9  371.36  6697.1   371.3  6766.8  376.68
#Mann= 3 , 0 , 0
  4040.1     .13       0  4943.6     .06       0    5034     .13       0
Bank Sta=4943.6,5034
XS Rating Curve= 0 ,0
Exp/Cntr=0.3,0.1

Type RM Length L Ch R = 1 ,58936   ,635,635,635
BEGIN DESCRIPTION:
ROBINSON CREEK 102.0
END DESCRIPTION:
XS GIS Cut Line= 3
      3793735.98     10246401.26      3793114.46     10246429.04
      3791141.24     10247372.69
#Sta/Elev= 30
  4013.7  373.59  4051.9  369.47  4111.9  366.84    4152  369.16  4341.3   357.8
  4392.2   356.4  4532.4  348.43  4665.3  339.91  4964.6  332.96  4978.9  330.07
  4986.8  322.82  4992.6  320.32  4999.6  320.32    5009  325.19  5018.8  327.21
  5041.4  324.85  5053.3  328.12  5069.6  329.32    5115  328.27  5143.2  330.91
  5319.1  329.51  5483.3  329.29  5511.5     328  5551.3  330.17  5738.3  332.62
  6028.8  344.75  6350.2  355.06  6412.4  355.15  6463.3  357.82  6823.1  367.92
#Mann= 4 ,-1 , 0
  4013.7     .11       0  4978.9     .06       0  5069.6     .11       0
  5319.1     .11       0
Bank Sta=4978.9,5069.6
XS Rating Curve= 0 ,0
Exp/Cntr=0.3,0.1

Type RM Length L Ch R = 1 ,58301   ,437,437,437
BEGIN DESCRIPTION:
ROBINSON CREEK 101.0
END DESCRIPTION:
XS GIS Cut Line= 3
      3793364.46     10245331.82      3793277.65     10245623.48
      3790847.07     10247293.64
#Sta/Elev= 30
  3694.2  368.57  3737.6  366.71  3797.8     360  3842.4  360.79  4003.7   350.1
  4171.2   344.1  4254.2     339  4284.5  337.23  4290.6  335.22  4313.7  336.35
  4320.4  334.26    4386  335.53  4586.3  334.03  4846.1  329.51  4968.6  329.34
  4974.6  329.09  4989.5  324.53  5000.9  318.11    5008  318.11  5017.5  325.14
  5031.4  329.21  5255.4  328.28  5377.9  326.12  5470.6  328.51    5593  330.87
    5838  341.46  6255.1   351.4  6312.9  350.05  6384.7  354.57  6947.6  365.74
#Mann= 9 ,-1 , 0
  3694.2     .11       0  4171.2     .15       0  4254.2     .11       0
  4846.1     .11       0  4968.6     .09       0  4974.6     .06       0
  5031.4     .11       0  5255.4     .11       0  5470.6     .11       0
Bank Sta=4974.6,5031.4
XS Rating Curve= 0 ,0
Exp/Cntr=0.3,0.1

Type RM Length L Ch R = 1 ,57864   ,529,529,529
BEGIN DESCRIPTION:
ROBINSON CREEK 100.0
END DESCRIPTION:
XS GIS Cut Line= 3
      3792833.21      10245321.4      3792261.23     10245808.37
      3790705.77      10247146.9
#Sta/Elev= 30
  4248.8  360.79    4302  353.58  4535.1  337.54  4663.3   329.5  4799.7  327.73
  4847.1  327.26    4940   326.1  4976.3  321.87  4982.9  323.58  4990.6  321.94
  4996.2  317.11  5011.4  319.41  5025.7  326.68    5210  324.99  5267.1  326.24
  5308.8  326.33  5337.3  321.82  5359.2  325.42  5387.1  326.32  5571.8   327.7
    5706  330.92  5912.3   339.6  6125.1  343.59  6174.5  341.66  6238.1  346.51
  6287.5  347.76  6323.7  346.95  6514.6  352.03  6819.7  354.48  7052.1  359.18
#Mann= 8 ,-1 , 0
  4248.8     .17       0  4535.1     .11       0  4799.7     .15       0
  4847.1     .11       0    4940     .06       0  5025.7     .11       0
  5267.1     .11       0  5571.8     .11       0
Bank Sta=4940,5025.7
XS Rating Curve= 0 ,0
Exp/Cntr=0.3,0.1

Type RM Length L Ch R = 1 ,57335   ,507,507,507
BEGIN DESCRIPTION:
ROBINSON CREEK 99.0
END DESCRIPTION:
XS GIS Cut Line= 4
      3792725.54     10245040.16      3792382.69     10245227.51
      3790585.81     10246229.39      3790143.09     10246164.28
#Sta/Elev= 30
  4107.4  366.48  4164.4  359.64  4186.3  351.86  4208.1  349.17    4246  351.75
  4449.5  333.67  4652.5  324.59  4848.5  323.29  4938.7  323.05  4961.6  323.81
  4983.4  321.47  5000.7     315  5009.6     315  5010.8  319.66  5018.9  321.77
  5032.5  318.35  5048.5  323.83  5086.2     323    5276   323.7  5687.4  327.63
  5820.3  326.41  5958.3  332.59  5980.6  330.21  6191.1  332.28  6248.3  332.64
  6292.9  333.13  6564.3  337.37  6639.3  341.04  6738.6  346.45  7002.9  359.58
#Mann= 14 ,-1 , 0
  4107.4     .17       0  4449.5     .11       0  4848.5     .11       0
  4938.7     .11       0  4961.6     .06       0  5048.5     .11       0
  5086.2     .11       0    5276     .11       0  6191.1     .15       0
  6248.3     .11       0  6292.9     .15       0  6564.3     .17       0
  6639.3     .11       0  6738.6     .17       0
#XS Ineff= 1 ,-1
  5362.8    5540  325.77
Permanent Ineff=
       F
Bank Sta=4961.6,5048.5
XS Rating Curve= 0 ,0
Exp/Cntr=0.3,0.1