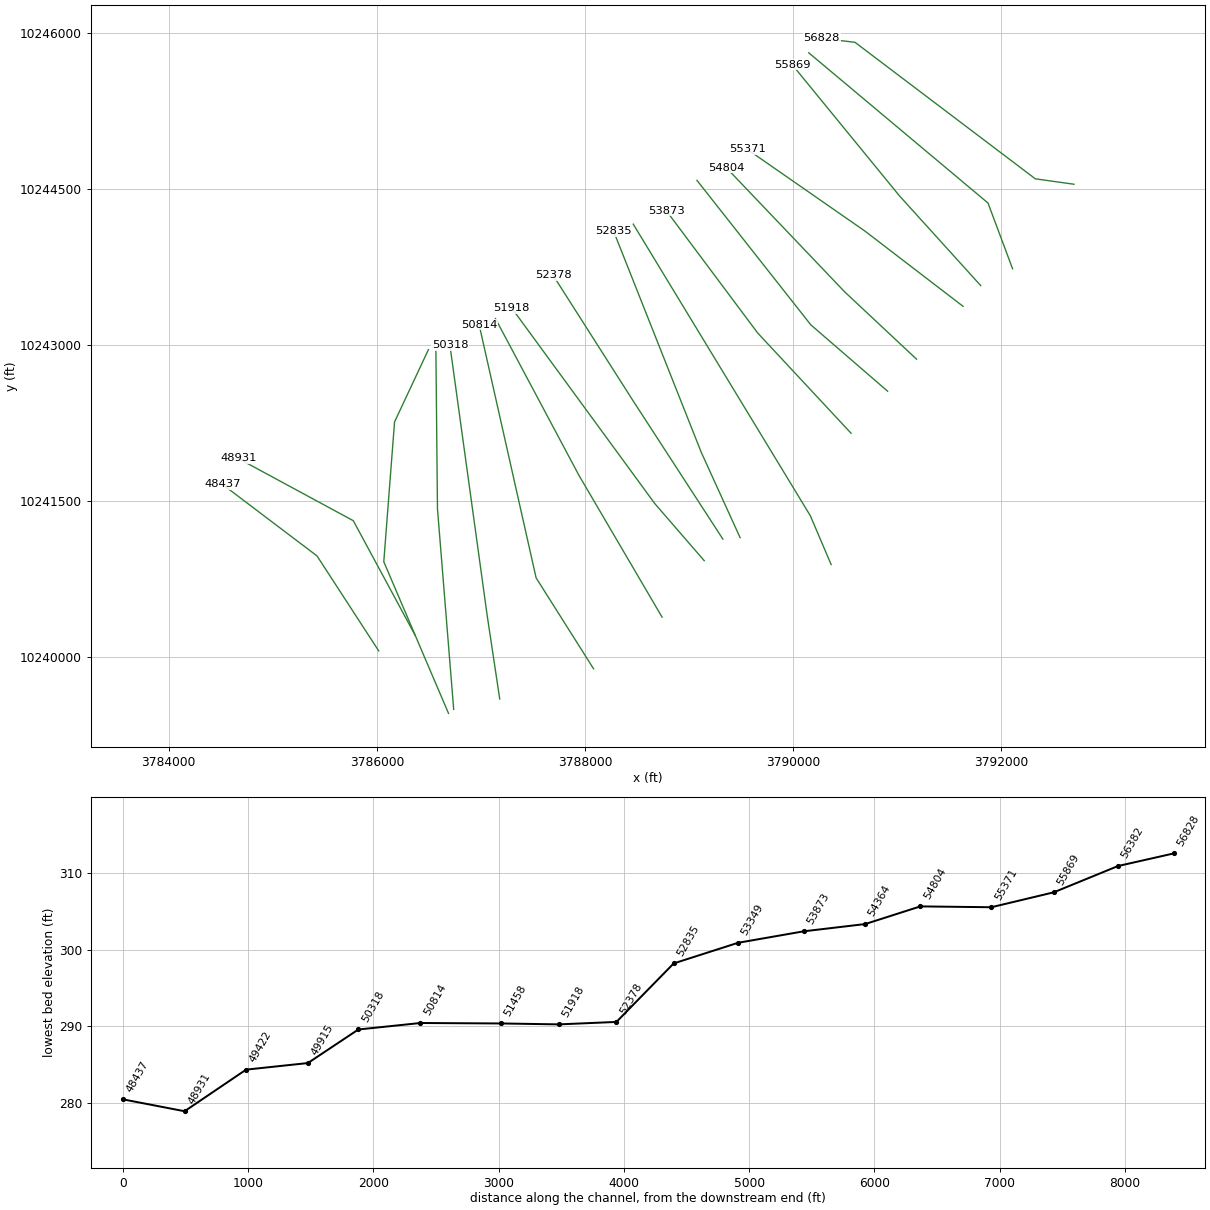
HEC-RAS study ROBINSON CREEK.prj: ROBINSON CREEK Base Level Engineering

--- ROBINSON CREEK.g01 (geometry) --- (continued)

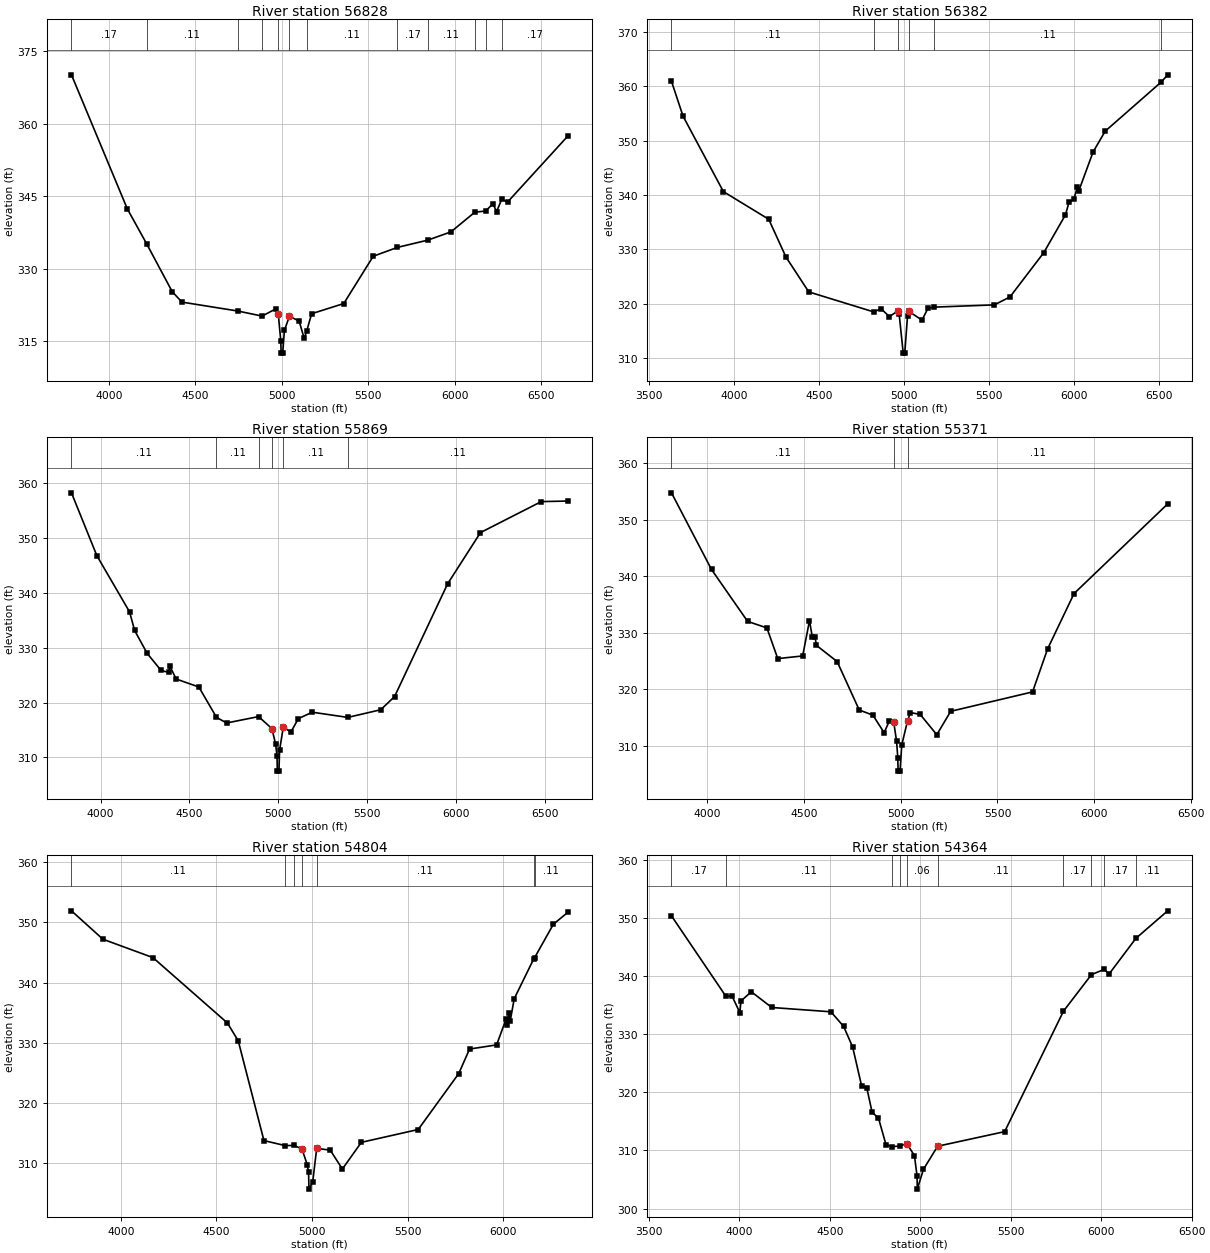
Type RM Length L Ch R = 1 ,56828   ,446,446,446
BEGIN DESCRIPTION:
ROBINSON CREEK 98.0
END DESCRIPTION:
XS GIS Cut Line= 4
      3792697.79      10244547.1      3792326.27     10244599.18
      3790593.63     10245911.68      3790274.19     10245949.87
#Sta/Elev= 30
  3782.8  370.06  4105.9  342.37    4218  335.14  4365.5  325.28  4421.7  323.12
  4744.2  321.28  4885.7  320.23  4964.7  321.72  4979.3   320.6  4993.8  315.02
  4995.6  312.58  5004.6  312.58  5014.6  317.29  5043.8   320.2    5100  319.19
  5129.1  315.61  5143.6  317.14  5172.1  320.72  5357.9  322.82  5528.5  332.59
  5668.5  334.42  5844.2  335.92  5977.9  337.62  6116.3  341.69  6178.7  341.93
  6221.3  343.44  6242.1   341.8  6271.2  344.32  6306.6  343.82  6653.3  357.38
#Mann= 12 ,-1 , 0
  3782.8     .17       0    4218     .11       0  4744.2     .11       0
  4885.7     .11       0  4979.3     .06       0  5043.8     .11       0
  5143.6     .11       0  5668.5     .17       0  5844.2     .11       0
  6116.3     .17       0  6178.7     .15       0  6271.2     .17       0
Bank Sta=4979.3,5043.8
XS Rating Curve= 0 ,0
Exp/Cntr=0.3,0.1

Type RM Length L Ch R = 1 ,56382   ,513,513,513
BEGIN DESCRIPTION:
ROBINSON CREEK 97.0
END DESCRIPTION:
XS GIS Cut Line= 3
       3792107.5     10243734.63       3791871.4     10244366.54
      3790149.22     10245810.96
#Sta/Elev= 30
    3631  360.92    3699  354.51  3936.8  340.63  4203.7  335.55  4305.3   328.6
  4439.5  322.19  4822.1  318.51    4865   319.1  4914.4  317.64  4963.9  318.68
  4971.7  318.14  4995.8  310.93  5004.8  310.93  5021.1  317.75    5028  318.63
  5106.4     317  5142.1  319.22  5177.2  319.39  5532.4   319.8  5624.7  321.27
  5823.8  329.42  5951.3  336.36  5972.1  338.67  6000.7  339.26  6021.6  341.49
  6029.3  340.73  6113.9  347.92  6185.4  351.75  6515.2  360.78  6553.3  362.11
#Mann= 6 ,-1 , 0
    3631     .11       0  4822.1     .11       0  4963.9     .06       0
    5028     .11       0  5177.2     .11       0  6515.2     .17       0
Bank Sta=4963.9,5028
XS Rating Curve= 0 ,0
Exp/Cntr=0.3,0.1

Type RM Length L Ch R = 1 ,55869   ,498,498,498
BEGIN DESCRIPTION:
ROBINSON CREEK 96.0
END DESCRIPTION:
XS GIS Cut Line= 3
       3791801.1     10243573.12      3791020.71     10244435.68
      3789992.01     10245694.53
#Sta/Elev= 30
  3836.8  358.26  3979.4   346.8  4163.3  336.54  4191.7  333.15  4262.6  328.95
  4340.4  325.86  4382.9   325.5  4389.7  326.63  4425.5  324.29  4552.6  322.84
  4651.9   317.3  4708.7  316.27  4888.4  317.44  4963.5  315.24  4984.5  312.36
  4991.9   310.3  4993.9  307.49  5002.9  307.49  5006.5  311.33  5027.3  315.51
  5070.3  314.63    5112  317.07  5190.2  318.24  5389.8  317.29    5575  318.69
  5652.7  321.09  5950.5  341.64  6135.7  351.01  6477.4  356.66  6625.7  356.76
#Mann= 6 ,-1 , 0
  3836.8     .11       0  4651.9     .11       0  4888.4     .11       0
  4963.5     .06       0  5027.3     .11       0  5389.8     .11       0
Bank Sta=4963.5,5027.3
XS Rating Curve= 0 ,0
Exp/Cntr=0.3,0.1

Type RM Length L Ch R = 1 ,55371   ,567,567,567
BEGIN DESCRIPTION:
ROBINSON CREEK 95.0
END DESCRIPTION:
XS GIS Cut Line= 3
       3791631.8      10243373.5      3790690.69     10244095.73
      3789557.18      10244883.9
#Sta/Elev= 30
  3813.7  354.76  4020.8   341.2  4207.6  332.02  4307.3  330.87  4363.5  325.44
  4492.2  325.91  4527.6  332.14  4542.1  329.28  4556.6  329.31  4562.9   327.8
  4670.8  324.91    4785  316.35  4855.7  315.44  4913.7  312.34  4940.9  314.41
  4963.6  314.15  4978.1  310.84  4984.4  307.92    4986  305.54    4996  305.54
  5005.1  310.18  5034.8  314.43  5049.6   315.9  5100.3  315.57  5186.2  311.98
  5258.2  316.12  5681.6  319.55  5759.3  327.15  5896.3  336.95  6380.6   352.8
#Mann= 3 , 0 , 0
  3813.7     .11       0  4963.6     .06       0  5034.8     .11       0
Bank Sta=4963.6,5034.8
XS Rating Curve= 0 ,0
Exp/Cntr=0.3,0.1

Type RM Length L Ch R = 1 ,54804   ,440,440,440
BEGIN DESCRIPTION:
ROBINSON CREEK 94.0
END DESCRIPTION:
XS GIS Cut Line= 3
      3791184.78     10242865.66      3790494.67     10243512.37
      3789357.54     10244705.93
#Sta/Elev= 30
  3742.3  351.92  3906.6   347.2  4168.4  344.14  4557.7  333.27  4614.3  330.29
  4748.6  313.72  4859.2  312.89  4904.3  312.91  4946.7  312.37    4975  309.73
  4981.9  308.42    4984  305.65  5003.3  306.79  5024.4  312.43  5095.2  312.13
  5158.7  308.99  5257.8  313.43    5555  315.56    5767  324.86  5823.6  328.94
  5965.2  329.63  6014.5  333.93  6021.8  332.93  6028.7  334.95  6035.9  333.56
    6057   337.3    6159  343.92    6164  344.15  6262.1   349.7  6336.6  351.65
#Mann= 7 ,-1 , 0
  3742.3     .11       0  4859.2     .15       0  4904.3     .11       0
  4946.7     .06       0  5024.4     .11       0    6159     .17       0
    6164     .11       0
Bank Sta=4946.7,5024.4
XS Rating Curve= 0 ,0
Exp/Cntr=0.3,0.1

Type RM Length L Ch R = 1 ,54364   ,491,491,491
BEGIN DESCRIPTION:
ROBINSON CREEK 93.0
END DESCRIPTION:
XS GIS Cut Line= 3
      3790906.99     10242557.51      3790169.15     10243195.53
      3789075.39     10244584.43
#Sta/Elev= 30
  3624.1  350.35  3924.6  336.53  3959.2  336.53  4001.9  333.72  4008.5  335.72
  4065.6  337.29  4178.6  334.59  4505.4  333.85  4575.6  331.35  4625.8  327.78
  4675.5  321.07  4704.4  320.69  4733.3  316.56  4768.5  315.56  4810.2  310.97
  4842.5  310.65  4888.7  310.76  4924.8  311.18  4967.3  309.11  4981.8   305.6
  4983.2  303.34    5017  306.74  5095.6  310.72  5466.1  313.23  5791.3  333.96
  5945.8  340.24  6016.6  341.15  6043.4  340.35  6191.6  346.48  6367.4  351.22
#Mann= 10 ,-1 , 0
  3624.1     .17       0  3924.6     .11       0  4842.5     .15       0
  4888.7     .11       0  4924.8     .06       0  5095.6     .11       0
  5791.3     .17       0  5945.8     .11       0  6016.6     .17       0
  6191.6     .11       0
Bank Sta=4924.8,5095.6
XS Rating Curve= 0 ,0
Exp/Cntr=0.3,0.1

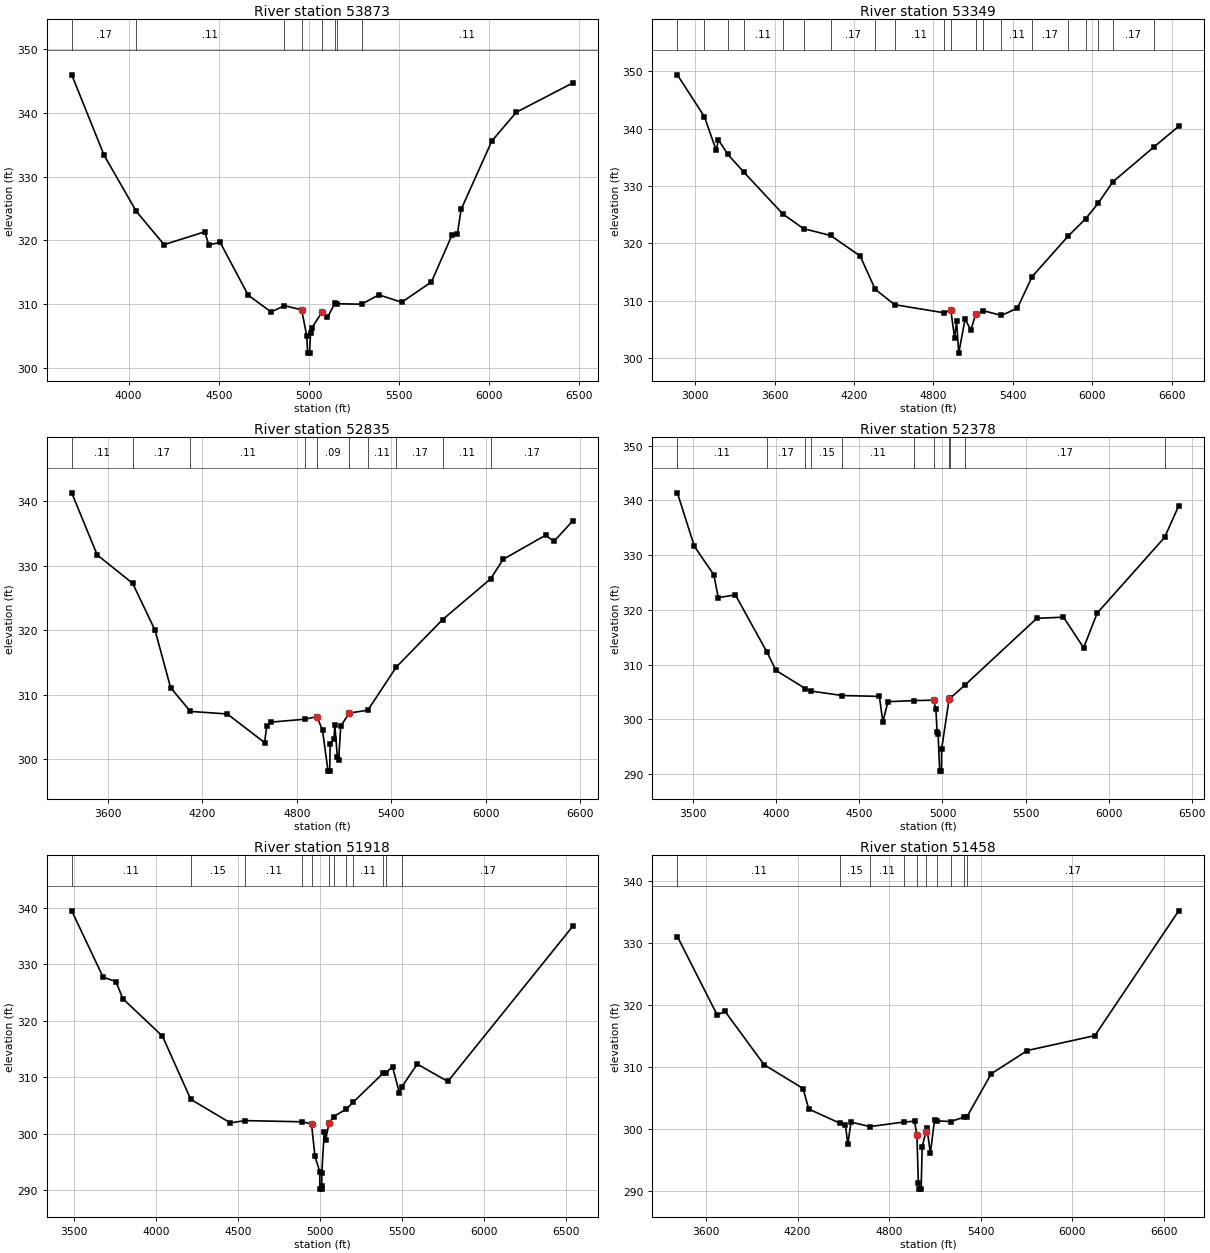
Type RM Length L Ch R = 1 ,53873   ,524,524,524
BEGIN DESCRIPTION:
ROBINSON CREEK 92.0
END DESCRIPTION:
XS GIS Cut Line= 3
      3790555.44     10242153.86      3789658.57     10243117.33
      3788780.27      10244293.6
#Sta/Elev= 30
  3683.7   345.9    3864  333.29  4042.7  324.54  4196.7  319.35  4422.9  321.36
  4444.4   319.3  4507.9  319.71  4663.6  311.46  4790.8  308.83  4865.3   309.8
  4960.8  309.16  4989.2  305.03  4993.9  302.39  5004.3  302.39  5010.2  305.53
  5017.1  306.33  5074.9  308.85  5104.1  307.97  5145.7  310.23    5159  310.11
  5293.3  310.04  5389.6   311.5  5516.8  310.35  5681.5  313.52  5796.1  320.87
  5825.3  320.99  5846.2  324.85  6017.1  335.56  6152.8  340.05    6468  344.65
#Mann= 8 ,-1 , 0
  3683.7     .17       0  4042.7     .11       0  4865.3     .15       0
  4960.8     .09       0  5074.9     .15       0  5145.7     .11       0
    5159     .15       0  5293.3     .11       0
Bank Sta=4960.8,5074.9
XS Rating Curve= 0 ,0
Exp/Cntr=0.3,0.1

Type RM Length L Ch R = 1 ,53349   ,514,514,514
BEGIN DESCRIPTION:
ROBINSON CREEK 91.0
END DESCRIPTION:
XS GIS Cut Line= 3
      3790364.44     10240890.89      3790164.81     10241359.59
      3788463.42     10244163.41
#Sta/Elev= 30
  2864.4  349.35  3068.9  342.05  3158.1   336.2  3174.5  338.04  3245.2  335.52
  3364.4  332.46  3662.6   325.1  3818.4  322.56  4022.5  321.38    4246   317.8
  4359.4  312.02  4505.9  309.33  4880.4  307.91  4931.3  308.37  4959.4  303.61
  4974.9  306.41    4991  300.89  5038.9  306.81  5083.4  304.89  5118.4  307.65
  5176.9  308.27  5314.1  307.46  5434.3  308.72  5545.8  314.21  5819.4   321.3
  5952.1  324.33    6044  326.96  6155.2   330.7  6466.8  336.79  6653.5  340.39
#Mann= 20 ,-1 , 0
  2864.4     .17       0  3068.9     .15       0  3245.2     .17       0
  3364.4     .11       0  3662.6     .11       0  3818.4     .17       0
  4022.5     .17       0  4359.4     .11       0  4505.9     .11       0
  4880.4     .15       0  4931.3     .09       0  5118.4     .15       0
  5176.9     .11       0  5314.1     .11       0  5545.8     .17       0
  5819.4     .11       0  5952.1     .17       0    6044     .11       0
  6155.2     .17       0  6466.8     .11       0
Bank Sta=4931.3,5118.4
XS Rating Curve= 0 ,0
Exp/Cntr=0.3,0.1

Type RM Length L Ch R = 1 ,52835   ,457,457,457
BEGIN DESCRIPTION:
ROBINSON CREEK 90.0
END DESCRIPTION:
XS GIS Cut Line= 3
      3789490.01     10241149.31      3789117.37     10241968.19
      3788275.43     10244093.73
#Sta/Elev= 30
  3370.3  341.27    3532  331.66  3757.8  327.25  3899.8  319.99  3998.5  311.12
  4124.2  307.43  4358.7  307.04  4595.8  302.61    4610  305.23  4634.3  305.77
  4853.7  306.23  4928.9  306.63    4964  304.51  4999.2  298.19  5009.8  298.19
  5012.6  302.35  5036.8  303.16  5042.3  305.37  5058.3  300.38  5066.7  299.98
  5079.8  305.14  5133.6  307.17  5251.9  307.62  5432.9   314.3  5726.7  321.64
  6032.2  327.95  6112.3  330.98  6381.2   334.7    6435  333.76  6556.2  336.97
#Mann= 10 ,-1 , 0
  3370.3     .11       0  3757.8     .17       0  4124.2     .11       0
  4853.7     .15       0  4928.9     .09       0  5133.6     .15       0
  5251.9     .11       0  5432.9     .17       0  5726.7     .11       0
  6032.2     .17       0
Bank Sta=4928.9,5133.6
XS Rating Curve= 0 ,0
Exp/Cntr=0.3,0.1

Type RM Length L Ch R = 1 ,52378   ,460,460,460
BEGIN DESCRIPTION:
ROBINSON CREEK 89.0
END DESCRIPTION:
XS GIS Cut Line= 3
      3789324.41     10241135.45      3788455.92     10242474.34
        3787692.     10243673.72
#Sta/Elev= 30
  3404.1   341.4  3506.2  331.63  3623.4  326.43  3650.5  322.25  3753.3  322.75
  3944.5  312.24  3997.9  308.95  4174.7  305.62  4208.6  305.17  4395.7  304.36
  4620.2   304.2  4641.3  299.53  4671.6  303.23  4831.3  303.43  4946.5  303.51
  4960.3  301.95  4967.6  297.72  4973.6  297.34  4983.4  290.54    4994  290.54
  4995.1   294.6  5040.3  303.76  5046.2  303.85  5134.2  306.24  5567.6  318.46
  5728.5  318.68  5849.8  313.08  5931.6  319.43  6337.4  333.26    6422  339.01
#Mann= 11 ,-1 , 0
  3404.1     .11       0  3944.5     .17       0  4174.7     .11       0
  4208.6     .15       0  4395.7     .11       0  4831.3     .15       0
  4946.5     .09       0  5040.3     .12       0  5046.2     .15       0
  5134.2     .17       0  6337.4     .11       0
Bank Sta=4946.5,5040.3
XS Rating Curve= 0 ,0
Exp/Cntr=0.3,0.1

Type RM Length L Ch R = 1 ,51918   ,460,460,460
BEGIN DESCRIPTION:
ROBINSON CREEK 88.0
END DESCRIPTION:
XS GIS Cut Line= 3
      3789144.95     10240928.46       3788671.1     10241475.91
      3787296.04     10243356.85
#Sta/Elev= 30
  3486.3  339.49  3677.2  327.76  3755.1  326.97  3797.8  323.93  4039.1   317.3
  4211.4  306.11  4452.1  301.96  4544.3  302.35  4891.7  302.14  4947.2  301.75
    4968  296.02  4997.1  293.33  4998.1  290.22    5009  290.22  5009.5  290.72
  5009.7  293.08  5024.4  300.41  5032.9  298.94  5053.7  301.87  5081.7  303.07
  5158.4  304.38  5200.3  305.59  5384.7  310.79  5399.4  310.84  5440.6  311.87
  5482.3  307.28  5498.5  308.38  5591.2  312.36  5777.3  309.28  6540.3  336.82
#Mann= 12 ,-1 , 0
  3486.3     .11       0  4211.4     .15       0  4544.3     .11       0
  4891.7     .15       0  4947.2     .09       0  5053.7     .15       0
  5081.7     .11       0  5158.4     .17       0  5200.3     .11       0
  5384.7     .17       0  5399.4     .11       0  5498.5     .17       0
Bank Sta=4947.2,5053.7
XS Rating Curve= 0 ,0
Exp/Cntr=0.3,0.1

Type RM Length L Ch R = 1 ,51458   ,644,644,644
BEGIN DESCRIPTION:
ROBINSON CREEK 87.0
END DESCRIPTION:
XS GIS Cut Line= 3
      3788740.12     10240385.53      3787939.59     10241751.96
      3787139.17      10243256.2
#Sta/Elev= 30
  3411.7  331.07  3673.1  318.41    3724  319.01  3980.1  310.41  4236.2  306.56
  4273.3  303.25  4480.9  300.93  4513.7  300.67  4529.4  297.62  4550.9  301.14
  4675.3  300.42    4896  301.16  4967.2  301.28  4982.7  299.06  4992.1  291.32
  4999.3  290.34  5010.5  290.34    5017   297.1  5039.7  299.48  5048.8  300.21
  5070.8   296.1  5098.4  301.54    5113  301.34    5204  301.24    5291  301.94
    5308  301.89  5470.1  308.94  5707.3  312.69  6149.8  315.09  6699.3  335.21
#Mann= 10 ,-1 , 0
  3411.7     .11       0  4480.9     .15       0  4675.3     .11       0
    4896     .15       0  4982.7     .09       0  5039.7     .15       0
    5113     .11       0    5204     .15       0    5291     .11       0
    5308     .17       0
Bank Sta=4982.7,5039.7
XS Rating Curve= 0 ,0
Exp/Cntr=0.3,0.1

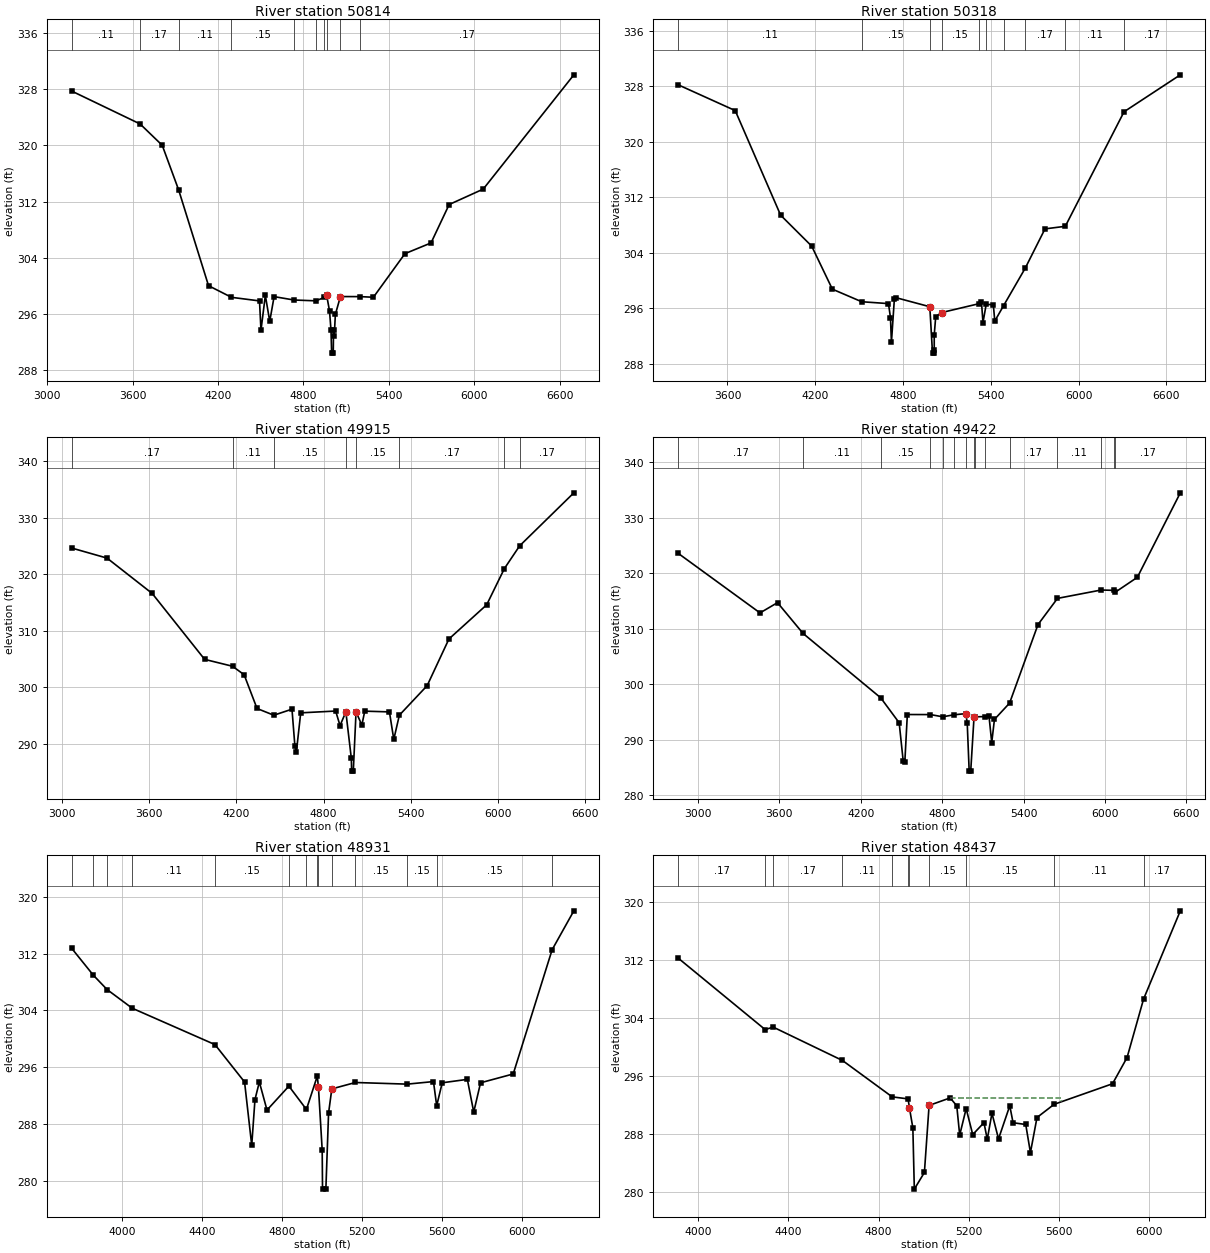
Type RM Length L Ch R = 1 ,50814   ,496,496,496
BEGIN DESCRIPTION:
ROBINSON CREEK 86.0
END DESCRIPTION:
XS GIS Cut Line= 3
      3788082.24     10239888.63      3787530.13     10240762.81
       3786982.8     10243195.88
#Sta/Elev= 30
  3172.7  327.73  3652.8  323.05  3808.3  320.01  3923.5  313.66  4133.6  300.01
    4295  298.35  4491.8  297.84  4502.1  293.66  4532.8  298.62  4563.7  294.93
  4594.3  298.45  4733.5  297.97  4887.7  297.85  4946.8  298.33  4963.3  298.67
  4983.8  296.42  4994.1  293.68  4998.7   290.4    5010   290.4  5011.9  293.69
    5017  292.86  5024.8  295.91  5060.3  298.46    5200  298.45  5292.1  298.36
  5513.7  304.57    5697   306.1  5824.3  311.57  6063.8  313.77  6700.5  330.05
#Mann= 10 ,-1 , 0
  3172.7     .11       0  3652.8     .17       0  3923.5     .11       0
    4295     .15       0  4733.5     .11       0  4887.7     .15       0
  4946.8     .11       0  4963.3     .07       0  5060.3     .11       0
    5200     .17       0
Bank Sta=4963.3,5060.3
XS Rating Curve= 0 ,0
Exp/Cntr=0.3,0.1

Type RM Length L Ch R = 1 ,50318   ,403,403,403
BEGIN DESCRIPTION:
ROBINSON CREEK 85.0
END DESCRIPTION:
XS GIS Cut Line= 3
      3787180.47     10239598.86      3787060.86     10240394.75
      3786702.19     10242997.42
#Sta/Elev= 30
  3263.4  328.18    3653  324.47  3963.4  309.41  4175.6  304.96  4316.9  298.76
  4517.4  296.95  4700.5  296.68  4714.2  294.67  4720.7  291.09  4740.8  297.34
  4750.9  297.54  4983.1  296.23  5001.5  289.55  5012.8  289.55  5013.3  290.05
  5013.4  292.18  5023.5   294.8  5063.9  295.39  5319.6  296.67  5336.4  296.88
  5346.5  293.95  5368.5  296.56  5417.2  296.53  5427.3  294.17  5487.3  296.38
  5635.6  301.79  5770.5  307.44  5909.3  307.81  6310.8   324.3  6695.5  329.62
#Mann= 10 ,-1 , 0
  3263.4     .11       0  4517.4     .15       0  4983.1     .09       0
  5063.9     .15       0  5319.6     .17       0  5368.5     .15       0
  5487.3     .11       0  5635.6     .17       0  5909.3     .11       0
  6310.8     .17       0
Bank Sta=4983.1,5063.9
XS Rating Curve= 0 ,0
Exp/Cntr=0.3,0.1

Type RM Length L Ch R = 1 ,49915   ,493,493,493
BEGIN DESCRIPTION:
ROBINSON CREEK 84.0
END DESCRIPTION:
XS GIS Cut Line= 3
      3786738.21     10239498.78      3786582.38     10241426.99
      3786567.23     10242951.62
#Sta/Elev= 30
  3065.5  324.66  3308.6  322.88  3619.6  316.62  3980.8  304.95    4173  303.73
    4253  302.23  4341.9  296.25  4457.7  295.06  4582.7  296.13  4602.8   289.6
  4612.8  288.52  4642.9  295.48  4883.7   295.8  4913.8  293.22  4953.9  295.66
  4991.6  287.42  4993.8  285.16  5005.2  285.16  5024.1  295.64  5064.1  293.32
  5084.1  295.78  5254.1  295.65  5284.1  290.78  5322.6  295.07  5514.1   300.3
  5664.1  308.56  5924.1  314.61    6046  321.02  6151.2  325.05  6524.7  334.44
#Mann= 8 ,-1 , 0
  3065.5     .17       0    4173     .11       0  4457.7     .15       0
  4953.9     .09       0  5024.1     .15       0  5322.6     .17       0
    6046     .11       0  6151.2     .17       0
Bank Sta=4953.9,5024.1
XS Rating Curve= 0 ,0
Exp/Cntr=0.3,0.1

Type RM Length L Ch R = 1 ,49422   ,491,491,491
BEGIN DESCRIPTION:
ROBINSON CREEK 83.0
END DESCRIPTION:
XS GIS Cut Line= 4
      3786688.57     10239460.16      3786066.63     10240918.26
       3786170.1     10242262.12       3786495.3     10242956.61
#Sta/Elev= 30
  2854.6  323.58  3457.2  312.84  3586.1  314.69  3774.3  309.14  4346.9  297.52
  4482.7  293.02  4512.8  286.04  4524.4  285.95  4542.9  294.51  4713.4   294.5
  4803.7   294.1  4883.9  294.45  4974.2  294.68  4984.2  292.97  4998.6   284.3
    5010   284.3  5034.4  294.05  5040.6  294.09  5114.6  294.14  5144.7  294.24
  5164.8  289.44  5184.8  293.63  5296.3  296.57  5505.8  310.74  5649.4  315.46
  5971.3  316.97  6062.9  316.91  6072.5  316.53  6237.9  319.26  6554.5   334.5
#Mann= 15 ,-1 , 0
  2854.6     .17       0  3774.3     .11       0  4346.9     .15       0
  4713.4     .15       0  4803.7     .15       0  4883.9     .15       0
  4974.2     .09       0  5034.4     .12       0  5040.6     .15       0
  5114.6     .15       0  5296.3     .17       0  5649.4     .11       0
  5971.3     .17       0  6062.9     .11       0  6072.5     .17       0
Bank Sta=4974.2,5034.4
XS Rating Curve= 0 ,0
Exp/Cntr=0.3,0.1

Type RM Length L Ch R = 1 ,48931   ,494,494,494
BEGIN DESCRIPTION:
ROBINSON CREEK 82.0
END DESCRIPTION:
XS GIS Cut Line= 3
      3786367.87     10240211.04      3785773.85     10241312.47
      3784667.86     10241911.07
#Sta/Elev= 30
  3748.6  312.72  3856.2  308.96  3924.9  306.94  4050.6  304.31  4464.3  299.19
  4612.1  293.93  4647.9  285.02  4664.1  291.46    4686  293.93  4724.2  289.98
  4833.6  293.35  4921.2  290.07  4975.5  294.76  4981.2  293.23    5000  284.37
  5001.7  278.86  5018.4  278.86  5031.9  289.56  5048.1  292.96    5166  293.86
  5424.8  293.63  5556.1  293.99  5572.2  290.59  5599.8  293.82  5725.4   294.3
  5757.3   289.7  5791.4  293.82  5954.6  295.06  6149.1  312.54  6257.6  318.01
#Mann= 14 ,-1 , 0
  3748.6     .17       0  3856.2     .11       0  3924.9     .17       0
  4050.6     .11       0  4464.3     .15       0  4833.6     .15       0
  4921.2     .13       0  4975.5     .12       0  4981.2     .09       0
  5048.1     .13       0    5166     .15       0  5424.8     .15       0
  5572.2     .15       0  6149.1     .17       0
#XS Ineff= 1 ,-1
    4560  4975.5  294.76
Permanent Ineff=
       F
Bank Sta=4981.2,5048.1
XS Rating Curve= 0 ,0
Exp/Cntr=0.3,0.1

Type RM Length L Ch R = 1 ,48437   ,608,608,608
BEGIN DESCRIPTION:
ROBINSON CREEK 81.0
END DESCRIPTION:
XS GIS Cut Line= 3
      3786017.88     10240061.03      3785425.36     10240973.78
      3784517.85     10241661.07
#Sta/Elev= 30
  3911.8  312.29  4297.4  302.43  4332.6  302.78  4640.2  298.17  4860.6  293.15
  4931.2  292.87  4937.2  291.62  4952.3  288.87  4958.8  280.42  5003.5  282.72
  5024.3  291.97  5117.9  293.01    5147  291.91    5160  287.88  5188.7  291.53
  5217.8  287.95  5267.7  289.59  5282.2  287.29  5303.1  290.89  5332.2  287.35
  5382.1  291.92  5396.7  289.58  5452.9  289.34  5473.7  285.46  5502.8   290.3
  5578.6  292.12  5837.8  294.96  5902.3  298.58  5975.4  306.64  6138.4  318.82
#Mann= 11 ,-1 , 0
  3911.8     .17       0  4297.4     .11       0  4332.6     .17       0
  4640.2     .11       0  4860.6     .15       0  4931.2     .12       0
  4937.2     .09       0  5024.3     .15       0  5188.7     .15       0
  5578.6     .11       0  5975.4     .17       0
#XS Ineff= 1 ,-1
  5117.9    5610  293.01
Permanent Ineff=
       T
Bank Sta=4937.2,5024.3
XS Rating Curve= 0 ,0
Exp/Cntr=0.3,0.1