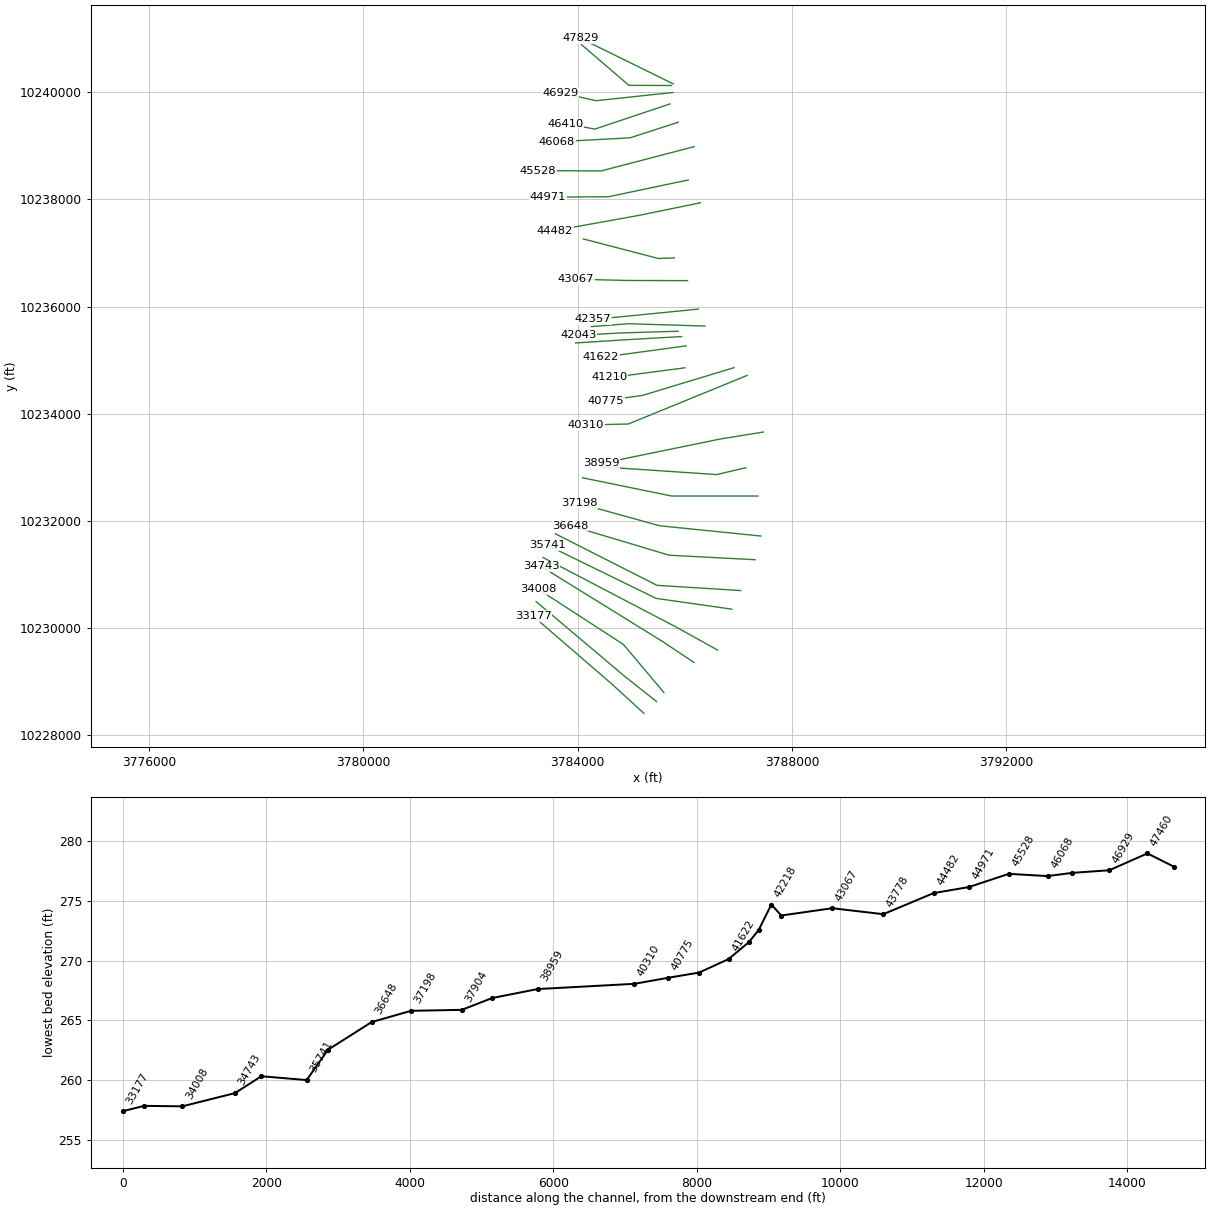
HEC-RAS study ROBINSON CREEK.prj: ROBINSON CREEK Base Level Engineering

--- ROBINSON CREEK.g01 (geometry) --- (continued)

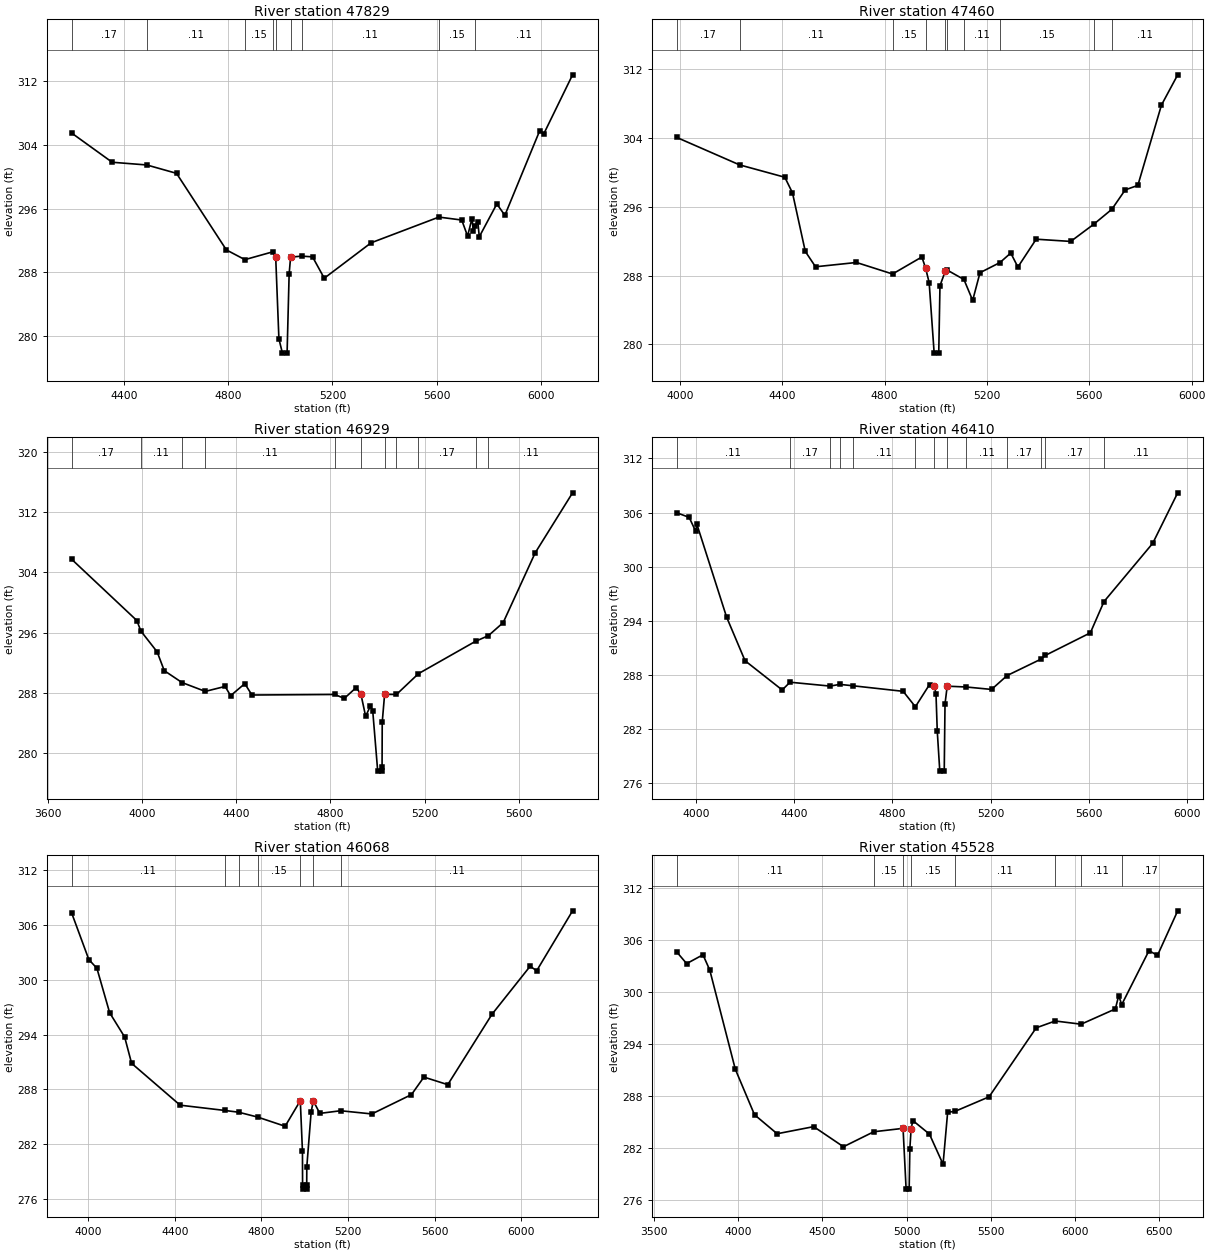
Type RM Length L Ch R = 1 ,47829   ,369,369,369
BEGIN DESCRIPTION:
ROBINSON CREEK 80.0
END DESCRIPTION:
XS GIS Cut Line= 2
      3785780.96     10240156.83      3784054.48     10241005.75
#Sta/Elev= 30
  4198.3  305.48  4353.7  301.82  4486.6  301.48  4600.9  300.43  4792.4  290.82
  4863.5   289.6  4971.7  290.59  4981.8  289.97  4994.2  279.66  5007.7  277.87
  5025.6  277.87  5033.5  287.81  5039.1  289.92  5081.8  290.04  5123.4  289.95
  5168.4  287.27  5348.2  291.71  5608.7  294.94  5696.5  294.57  5718.9  292.56
  5735.8  294.75  5741.4  293.19  5748.1   293.8  5758.3  294.35  5763.9  292.47
  5831.3  296.59  5862.1  295.16  5995.9  305.77  6011.1  305.35  6122.2  312.79
#Mann= 9 ,-1 , 0
  4198.3     .17       0  4486.6     .11       0  4863.5     .15       0
  4971.7     .12       0  4981.8     .09       0  5039.1     .15       0
  5081.8     .11       0  5608.7     .15       0  5748.1     .11       0
Bank Sta=4981.8,5039.1
XS Rating Curve= 0 ,0
Exp/Cntr=0.3,0.1

Type RM Length L Ch R = 1 ,47460   ,531,531,531
BEGIN DESCRIPTION:
ROBINSON CREEK 79.0
END DESCRIPTION:
XS GIS Cut Line= 3
      3785749.75     10240125.56      3784955.01     10240129.06
      3784072.79     10240885.86
#Sta/Elev= 30
  3988.4  304.08  4233.5  300.89  4410.3  299.45  4440.3  297.63  4490.3  290.82
  4530.3  289.03  4690.3  289.53  4831.3  288.19  4945.8  290.17  4960.1  288.91
  4974.3   287.2  4993.9  278.98  5011.8  278.98  5016.6  286.82    5038  288.58
  5044.6  288.65  5110.2  287.55  5144.4  285.12    5173  288.34  5250.9  289.52
  5293.2  290.63  5321.1     289  5392.5  292.24  5527.5  291.98  5616.6  293.96
  5688.2  295.72  5740.4  297.98  5789.8   298.5    5882  307.85  5945.5  311.37
#Mann= 10 ,-1 , 0
  3988.4     .17       0  4233.5     .11       0  4831.3     .15       0
  4960.1     .09       0    5038     .12       0  5044.6     .15       0
  5110.2     .11       0  5250.9     .15       0  5616.6     .17       0
  5688.2     .11       0
Bank Sta=4960.1,5038
XS Rating Curve= 0 ,0
Exp/Cntr=0.3,0.1

Type RM Length L Ch R = 1 ,46929   ,519,519,519
BEGIN DESCRIPTION:
ROBINSON CREEK 78.0
END DESCRIPTION:
XS GIS Cut Line= 3
      3785778.42     10239995.35      3784344.33     10239842.33
      3783676.83     10239990.14
#Sta/Elev= 30
  3702.3  305.73  3978.8  297.59  3995.9  296.19  4064.9  293.43  4095.1  290.93
  4170.3  289.35  4269.2  288.17  4353.4  288.83  4376.7   287.6    4437   289.2
  4467.2  287.69  4818.6  287.76  4859.4  287.24  4909.7  288.68  4929.8   287.8
  4949.9  284.86    4970  286.22  4980.1  285.54  5001.1  277.57  5019.1  277.57
  5019.6  278.07  5020.3  284.07  5030.4  287.78  5080.6  287.76  5174.2  290.53
  5416.3  294.83  5470.9  295.58  5533.6  297.31  5669.5  306.59  5828.2  314.57
#Mann= 11 ,-1 , 0
  3702.3     .17       0  3995.9     .11       0  4170.3     .15       0
  4269.2     .11       0  4818.6     .15       0  4929.8     .09       0
  5030.4     .15       0  5080.6     .11       0  5174.2     .17       0
  5416.3     .15       0  5470.9     .11       0
#XS Ineff= 1 ,-1
    4165    4437   289.2
Permanent Ineff=
       F
Bank Sta=4929.8,5030.4
XS Rating Curve= 0 ,0
Exp/Cntr=0.3,0.1

Type RM Length L Ch R = 1 ,46410   ,342,342,342
BEGIN DESCRIPTION:
ROBINSON CREEK 77.0
END DESCRIPTION:
XS GIS Cut Line= 3
      3785721.08      10239781.8      3784322.67     10239313.06
      3783767.84     10239411.07
#Sta/Elev= 30
  3922.4  305.97  3972.6  305.46  3998.9  303.93  4004.1  304.69  4125.1   294.4
    4200  289.58  4351.2  286.34    4383   287.2  4546.3  286.77  4585.7  286.96
    4641   286.8  4843.4  286.19  4893.2  284.48  4950.7  286.94  4969.9  286.77
    4977  285.93  4982.3  281.75  4992.5  277.35  5010.6  277.35  5013.8  284.81
  5022.7  286.76  5100.3  286.67  5203.1   286.4  5266.6  287.94  5404.6  289.76
  5422.7  290.18  5605.3  292.67  5660.7  296.13  5859.1  302.59  5960.7  308.18
#Mann= 13 ,-1 , 0
  3922.4     .11       0    4383     .17       0  4546.3     .15       0
  4585.7     .17       0    4641     .11       0  4893.2     .15       0
  4969.9     .09       0  5022.7     .15       0  5100.3     .11       0
  5266.6     .17       0  5404.6     .11       0  5422.7     .17       0
  5660.7     .11       0
Bank Sta=4969.9,5022.7
XS Rating Curve= 0 ,0
Exp/Cntr=0.3,0.1

Type RM Length L Ch R = 1 ,46068   ,540,540,540
BEGIN DESCRIPTION:
ROBINSON CREEK 76.0
END DESCRIPTION:
XS GIS Cut Line= 3
      3785877.35     10239440.66      3784975.58     10239149.23
      3783612.34     10239076.11
#Sta/Elev= 30
    3924  307.33  4003.1  302.24  4040.4  301.28  4099.2  296.41  4168.5  293.75
  4200.5  290.87  4424.7  286.28  4631.8   285.7  4694.6  285.51  4782.1  284.98
  4909.5  283.97  4979.6  286.77  4989.6  281.21  4990.1  277.58  4990.6  277.08
  5008.7  277.08  5009.2  277.58  5009.6  279.52  5029.7  285.54  5039.7  286.75
  5069.7  285.38  5165.8  285.67  5310.1  285.32    5493  287.44  5550.4  289.36
  5660.6  288.53    5865  296.25  6041.1  301.51  6071.1  301.01  6236.9  307.58
#Mann= 7 ,-1 , 0
    3924     .11       0  4631.8     .15       0  4694.6     .17       0
  4782.1     .15       0  4979.6     .09       0  5039.7     .15       0
  5165.8     .11       0
Bank Sta=4979.6,5039.7
XS Rating Curve= 0 ,0
Exp/Cntr=0.3,0.1

Type RM Length L Ch R = 1 ,45528   ,557,557,557
BEGIN DESCRIPTION:
ROBINSON CREEK 75.0
END DESCRIPTION:
XS GIS Cut Line= 3
      3786174.27     10238984.94      3784438.58     10238532.02
       3783257.6     10238537.01
#Sta/Elev= 30
  3635.2  304.62  3693.5  303.29  3790.4  304.31  3830.9  302.54  3982.4  291.11
  4096.6  285.85  4230.9  283.66    4448  284.48  4624.8  282.16  4804.9  283.89
  4978.8  284.28    4997  277.27  5015.1  277.27  5019.2  281.93  5026.7  284.25
    5037  285.18  5135.5  283.62  5216.4  280.14  5243.7  286.15  5285.8  286.23
  5489.7  287.92  5769.7  295.88  5882.6  296.67  6036.4   296.3  6239.7  298.06
  6259.7   299.6  6277.6  298.56  6439.7  304.79  6489.8  304.23    6610  309.38
#Mann= 8 ,-1 , 0
  3635.2     .11       0  4804.9     .15       0  4978.8     .09       0
  5026.7     .15       0  5285.8     .11       0  5882.6     .17       0
  6036.4     .11       0  6277.6     .17       0
Bank Sta=4978.8,5026.7
XS Rating Curve= 0 ,0
Exp/Cntr=0.3,0.1

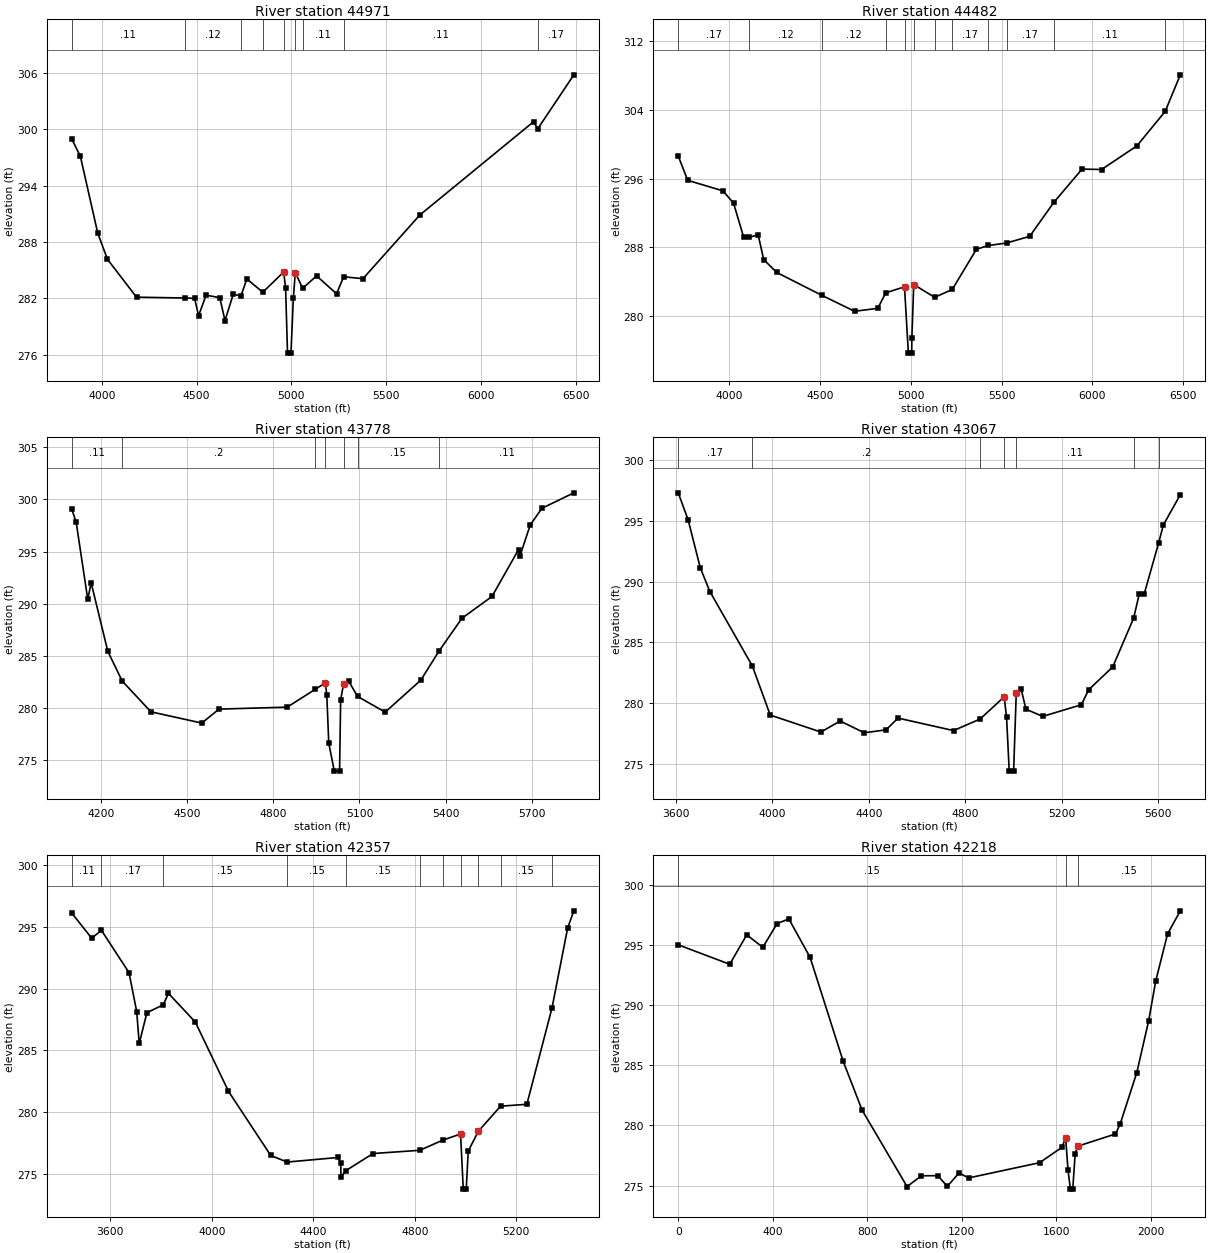
Type RM Length L Ch R = 1 ,44971   ,489,489,489
BEGIN DESCRIPTION:
ROBINSON CREEK 74.0
END DESCRIPTION:
XS GIS Cut Line= 3
      3786062.23     10238362.53      3784572.67     10238050.04
      3783445.08     10238042.22
#Sta/Elev= 30
  3841.2  298.96  3886.5  297.13  3978.5  288.92  4029.6  286.15  4182.9  282.12
    4439  282.03  4489.4  281.99  4510.4  280.15  4550.1  282.33  4622.2  282.07
  4649.8  279.63  4693.7  282.45  4733.3  282.23  4765.3  284.05  4849.4  282.65
  4959.4   284.8  4969.6   283.1  4979.8  276.16    4998  276.16  5010.5  282.01
  5020.7  284.74  5059.7  283.06  5133.1  284.39  5238.4  282.48  5276.1  284.29
    5378  284.09    5678  290.87    6278   300.8  6300.2  300.05  6490.8   305.8
#Mann= 9 ,-1 , 0
  3841.2     .11       0    4439     .12       0  4733.3     .15       0
  4849.4     .13       0  4959.4     .08       0  5020.7     .13       0
  5059.7     .11       0  5276.1     .11       0  6300.2     .17       0
Bank Sta=4959.4,5020.7
XS Rating Curve= 0 ,0
Exp/Cntr=0.3,0.1

Type RM Length L Ch R = 1 ,44482   ,704,704,704
BEGIN DESCRIPTION:
ROBINSON CREEK 73.0
END DESCRIPTION:
XS GIS Cut Line= 3
      3786288.84     10237938.06       3785166.3     10237706.59
      3783572.75     10237419.84
#Sta/Elev= 30
  3718.8  298.64  3770.9  295.81  3964.9  294.58  4023.4  293.15  4078.8   289.2
  4109.1  289.16  4158.9  289.46  4189.5  286.57    4261  285.07  4508.9  282.41
  4689.8  280.54  4817.7  280.88  4861.6  282.69    4965  283.39  4986.3  275.66
  5004.6  275.66  5005.6  277.44  5015.8  283.66  5130.8  282.17    5228  283.08
  5361.2  287.77  5427.2  288.21  5526.9   288.5  5654.6  289.28  5787.9  293.25
  5943.1  297.12  6050.4  297.07  6245.2  299.83  6400.6  303.84  6484.1  308.11
#Mann= 12 ,-1 , 0
  3718.8     .17       0  4109.1     .12       0  4508.9     .12       0
  4861.6     .13       0    4965     .07       0  5015.8     .13       0
  5130.8     .11       0    5228     .17       0  5427.2     .11       0
  5526.9     .17       0  5787.9     .11       0  6400.6     .17       0
Bank Sta=4965,5015.8
XS Rating Curve= 0 ,0
Exp/Cntr=0.3,0.1

Type RM Length L Ch R = 1 ,43778   ,711,711,711
BEGIN DESCRIPTION:
ROBINSON CREEK 72.0
END DESCRIPTION:
XS GIS Cut Line= 3
       3785803.3     10236908.43      3785506.11     10236897.62
      3784102.06     10237263.38
#Sta/Elev= 30
  4098.3  299.08  4113.8  297.79  4153.8  290.43    4166  291.97  4223.8   285.4
  4273.9  282.55  4373.9  279.59  4551.1  278.51  4610.9  279.85  4848.6  280.04
  4945.8  281.75  4981.2  282.37  4986.3  281.22  4993.2  276.58  5012.5  273.89
  5030.8  273.89  5034.6  280.75  5044.9  282.28  5062.2  282.55  5093.5  281.07
  5189.6  279.56  5313.6  282.63  5377.6  285.45  5456.8  288.58  5561.6  290.68
  5654.2  295.19  5659.3   294.6  5694.7  297.55  5735.2  299.15  5846.6  300.64
#Mann= 7 ,-1 , 0
  4098.3     .11       0  4273.9      .2       0  4945.8     .11       0
  4981.2     .06       0  5044.9     .11       0  5093.5     .15       0
  5377.6     .11       0
#XS Ineff= 1 ,-1
  5062.2    5320  282.55
Permanent Ineff=
       F
Bank Sta=4981.2,5044.9
XS Rating Curve= 0 ,0
Exp/Cntr=0.3,0.1

Type RM Length L Ch R = 1 ,43067   ,710,710,710
BEGIN DESCRIPTION:
ROBINSON CREEK 71.0
END DESCRIPTION:
XS GIS Cut Line= 3
      3786049.22     10236484.93      3784926.83     10236487.54
      3783967.82     10236511.07
#Sta/Elev= 30
  3609.4  297.32  3650.8  295.07  3700.8  291.14  3740.8  289.18  3916.8  283.05
  3990.8  279.01  4200.8  277.61  4280.8  278.52  4380.8  277.55  4470.8  277.79
  4520.8  278.76  4750.8  277.73  4860.8  278.68  4960.8  280.51  4970.8  278.81
  4981.7  274.39    5000  274.39  5010.9  280.83  5030.9  281.18  5050.9  279.49
  5120.9   278.9  5280.9  279.86  5310.9  281.09    5411  282.98  5497.5  286.99
    5521     289    5541  288.96  5601.3   293.2    5621  294.68  5691.1  297.17
#Mann= 7 ,-1 , 0
  3609.4     .17       0  3916.8      .2       0  4860.8     .11       0
  4960.8     .06       0  5010.9     .11       0  5497.5     .17       0
  5601.3     .11       0
#XS Ineff= 1 ,-1
  5030.9    5345  281.18
Permanent Ineff=
       F
Bank Sta=4960.8,5010.9
XS Rating Curve= 0 ,0
Exp/Cntr=0.3,0.1

Type RM Length L Ch R = 1 ,42357   ,139,139,139
BEGIN DESCRIPTION:
ROBINSON CREEK 70.0
END DESCRIPTION:
XS GIS Cut Line= 3
      3786252.36     10235953.68       3784968.5     10235826.08
      3784283.58     10235760.97
#Sta/Elev= 30
  3448.5  296.11  3526.9  294.08  3565.5  294.71  3674.1  291.29  3704.3  288.14
  3714.3  285.56  3744.5  288.05  3809.1  288.69  3829.3  289.62  3935.4  287.29
    4066  281.69  4232.5   276.5  4297.2  275.97  4498.2  276.34  4508.2  275.87
  4509.1  274.77    4528  275.27  4635.7  276.66  4819.7  276.92  4910.1  277.74
  4980.4  278.24    4991  273.78  5002.7  273.78  5010.6  276.86  5050.7  278.47
  5138.1  280.49  5241.6  280.64  5340.7  288.44  5402.3   294.9  5426.7  296.29
#Mann= 11 ,-1 , 0
  3448.5     .11       0  3565.5     .17       0  3809.1     .15       0
  4297.2     .15       0    4528     .15       0  4819.7     .14       0
  4910.1     .11       0  4980.4     .06       0  5050.7     .11       0
  5138.1     .15       0  5340.7     .17       0
Bank Sta=4980.4,5050.7
XS Rating Curve= 0 ,0
Exp/Cntr=0.3,0.1

Type RM Length L Ch R = 1 ,42218   ,175,175,175
XS GIS Cut Line= 3
      3786375.51     10235637.41      3784940.95     10235680.73
      3784254.31     10235626.42
#Sta/Elev= 30
       0  295.04   217.8  293.42   289.8  295.87   357.8  294.83   417.9   296.8
   467.9   297.2   557.9  293.99     698  285.33     778  281.27   968.1  274.91
  1028.1  275.81  1098.2  275.82  1138.2  274.93  1188.2  276.05  1228.2  275.63
  1528.6   276.9  1622.5  278.17  1638.9  278.95    1649  276.28    1659   274.7
    1669   274.7  1679.1  277.63  1689.1  278.27  1849.6  279.29  1869.7  280.13
  1939.9   284.4    1990  288.71  2020.1  292.04  2070.3  295.96    2124  297.87
#Mann= 3 , 0 , 0
       0     .15       0  1638.9     .08       0  1689.1     .15       0
Bank Sta=1638.9,1689.1
XS Rating Curve= 0 ,0
Exp/Cntr=0.3,0.1

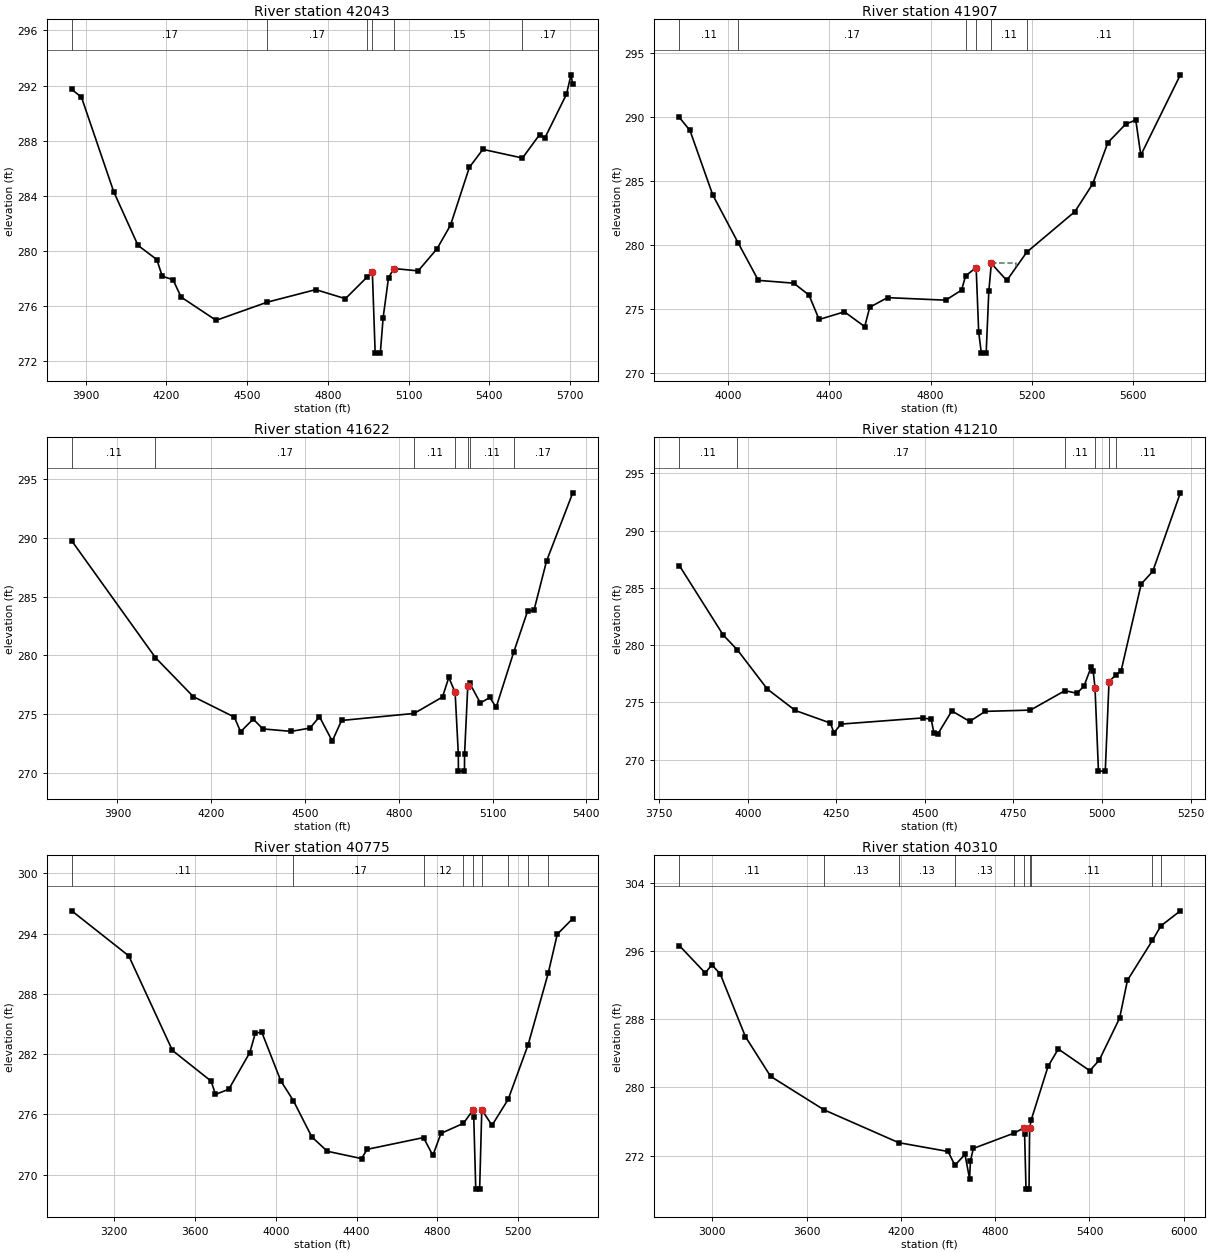
Type RM Length L Ch R = 1 ,42043   ,136,136,136
BEGIN DESCRIPTION:
ROBINSON CREEK 69.0
END DESCRIPTION:
XS GIS Cut Line= 3
       3785873.9     10235540.49      3784823.54     10235509.24
      3784014.53     10235465.84
#Sta/Elev= 30
  3848.8  291.72  3884.9  291.16  4004.9  284.29    4095   280.4    4165  279.37
    4185  278.16    4225  277.91    4255  276.65  4385.1  274.96  4575.2  276.28
  4755.3  277.19  4865.3  276.53  4945.4  278.09  4965.4  278.48  4975.9  272.58
    4995  272.58  5005.5  275.16  5025.5  278.05  5045.5  278.72  5135.7  278.55
  5205.8  280.16  5255.8  281.87  5325.9  286.07    5376  287.37  5523.1  286.74
  5586.3  288.43  5606.3   288.2  5686.4  291.37  5703.4  292.78  5709.8  292.08
#Mann= 6 ,-1 , 0
  3848.8     .17       0  4575.2     .17       0  4945.4     .15       0
  4965.4     .08       0  5045.5     .15       0  5523.1     .17       0
#XS Ineff= 2 ,-1
    4170  4965.4  278.48
Permanent Ineff=
       F       F
Bank Sta=4965.4,5045.5
XS Rating Curve= 0 ,0
Exp/Cntr=0.3,0.1

Type RM Length L Ch R = 1 ,41907   ,285,285,285
BEGIN DESCRIPTION:
ROBINSON CREEK 68.0
END DESCRIPTION:
XS GIS Cut Line= 3
      3785939.84     10235441.53      3784825.27     10235377.29
      3783961.77     10235321.81
#Sta/Elev= 30
  3806.5  289.99  3848.6  288.97  3938.7  283.93  4038.9  280.19    4119  277.25
  4259.2  277.03  4319.3   276.1  4359.4  274.19  4459.6  274.79  4539.7  273.63
  4559.7  275.15  4629.9   275.9  4860.2   275.7  4922.9  276.49  4938.7   277.6
  4980.5  278.25  4990.5  273.22    5001  271.56  5020.1  271.56  5030.6  276.41
  5040.6  278.57  5101.8  277.24  5180.9  279.46  5371.3  282.63  5441.4  284.79
  5501.5  288.02  5571.7  289.46  5611.8  289.79  5631.8  287.04  5788.2  293.32
#Mann= 6 ,-1 , 0
  3806.5     .11       0  4038.9     .17       0  4938.7     .11       0
  4980.5     .07       0  5040.6     .11       0  5180.9     .11       0
#XS Ineff= 2 ,-1
  5040.6    5140  278.57
Permanent Ineff=
       F       F
Bank Sta=4980.5,5040.6
XS Rating Curve= 0 ,0
Exp/Cntr=0.3,0.1

Type RM Length L Ch R = 1 ,41622   ,412,412,412
BEGIN DESCRIPTION:
ROBINSON CREEK 67.0
END DESCRIPTION:
XS GIS Cut Line= 3
      3786023.24     10235267.92      3784684.11     10235085.57
      3784434.64     10235054.38
#Sta/Elev= 30
  3753.8  289.77  4021.6  279.81  4142.9  276.48  4273.9  274.74  4294.1  273.49
  4334.5  274.57  4365.1  273.73  4455.6  273.52  4516.2   273.8  4546.4  274.77
  4587.3  272.69  4617.1  274.45  4849.2  275.05    4940  276.45  4960.2  278.12
  4980.4  276.84  4990.5  271.63    4991  270.13  5010.2  270.13  5010.7  271.63
  5020.8  277.35  5026.6  277.64  5061.1  275.94  5091.4  276.41  5111.6  275.57
  5167.8  280.27  5212.4  283.79  5232.5  283.83  5272.8  288.04  5356.7  293.86
#Mann= 7 ,-1 , 0
  3753.8     .11       0  4021.6     .17       0  4849.2     .11       0
  4980.4     .06       0  5020.8     .09       0  5026.6     .11       0
  5167.8     .17       0
#XS Ineff= 2 ,-1
  5026.6    5150  277.64
Permanent Ineff=
       F       F
Bank Sta=4980.4,5020.8
XS Rating Curve= 0 ,0
Exp/Cntr=0.3,0.1

Type RM Length L Ch R = 1 ,41210   ,435,435,435
BEGIN DESCRIPTION:
ROBINSON CREEK 66.0
END DESCRIPTION:
XS GIS Cut Line= 3
      3786000.65      10234858.2       3784677.7     10234684.58
       3784597.8     10234691.53
#Sta/Elev= 30
  3806.8  286.96  3930.7  280.89    3971  279.58  4055.2  276.17    4134   274.3
  4233.2   273.2  4243.3  272.36  4263.5  273.11  4495.5  273.65  4517.8  273.52
  4525.7  272.33  4535.8   272.2  4576.1  274.26  4626.6  273.34  4670.3  274.22
    4798  274.33  4895.5  276.03  4929.1   275.8  4949.3  276.43  4969.5   278.1
  4975.2  277.72  4980.3   276.3  4990.1     269  5009.3     269  5019.9  276.81
  5040.1  277.44    5054  277.76  5110.7  285.34  5143.5  286.46  5221.3  293.31
#Mann= 6 ,-1 , 0
  3806.8     .11       0    3971     .17       0  4895.5     .11       0
  4980.3     .07       0  5019.9     .11       0  5040.1     .11       0
Bank Sta=4980.3,5019.9
XS Rating Curve= 0 ,0
Exp/Cntr=0.3,0.1

Type RM Length L Ch R = 1 ,40775   ,465,465,465
BEGIN DESCRIPTION:
ROBINSON CREEK 65.0
END DESCRIPTION:
XS GIS Cut Line= 3
      3786917.81     10234861.06      3785212.42     10234344.31
      3784522.18     10234247.19
#Sta/Elev= 30
  2990.5  296.26  3272.6  291.78  3488.6  282.37  3680.1  279.31  3701.8  277.99
  3767.6   278.5  3871.6  282.15  3899.3   284.1  3930.9  284.18  4024.9  279.34
  4087.6  277.35  4178.3  273.76  4254.8  272.33  4424.4   271.6  4452.1  272.52
  4731.1  273.69  4777.3  271.91  4817.5  274.11  4928.6  275.11  4974.6  276.39
  4979.6  275.75  4989.6  268.56  5008.8  268.56  5019.4  276.46  5069.9  274.91
  5149.8  277.49    5249  282.95  5348.2  290.06  5393.1  293.94  5469.5  295.49
#Mann= 9 ,-1 , 0
  2990.5     .11       0  4087.6     .17       0  4731.1     .12       0
  4928.6     .12       0  4974.6     .09       0  5019.4     .12       0
  5149.8     .11       0    5249     .17       0  5348.2     .11       0
#XS Ineff= 3 ,-1
    3400  3930.9  284.18                          5019.4    5140  276.46
Permanent Ineff=
       F       F       F
Bank Sta=4974.6,5019.4
XS Rating Curve= 0 ,0
Exp/Cntr=0.3,0.1

Type RM Length L Ch R = 1 ,40310   ,1351,1351,1351
BEGIN DESCRIPTION:
ROBINSON CREEK 64.0
END DESCRIPTION:
XS GIS Cut Line= 3
      3787160.38     10234715.85      3784945.06     10233809.58
      3784151.38     10233792.26
#Sta/Elev= 30
  2790.7  296.67  2955.5  293.45  2997.4  294.41  3050.8  293.34  3211.1  285.97
  3371.3  281.31  3710.5  277.38  4185.8  273.52  4500.5  272.48  4543.8  270.86
  4607.8  272.13  4637.2  269.29  4642.6  271.36  4661.2  272.84  4921.9  274.65
  4981.8  275.24  4987.2  274.51  4996.2  268.06  5015.4  268.06  5019.1  275.22
  5029.8  276.22  5136.6  282.49  5201.4  284.52  5401.5  281.97  5461.5  283.19
  5591.5  288.14  5641.5  292.59  5800.7  297.29  5854.3  298.98  5978.1  300.75
#Mann= 10 ,-1 , 0
  2790.7     .11       0  3710.5     .13       0  4185.8     .13       0
  4543.8     .13       0  4921.9     .11       0  4981.8     .06       0
  5019.1     .09       0  5029.8     .11       0  5800.7     .17       0
  5854.3     .11       0
Bank Sta=4981.8,5019.1
XS Rating Curve= 0 ,0
Exp/Cntr=0.3,0.1

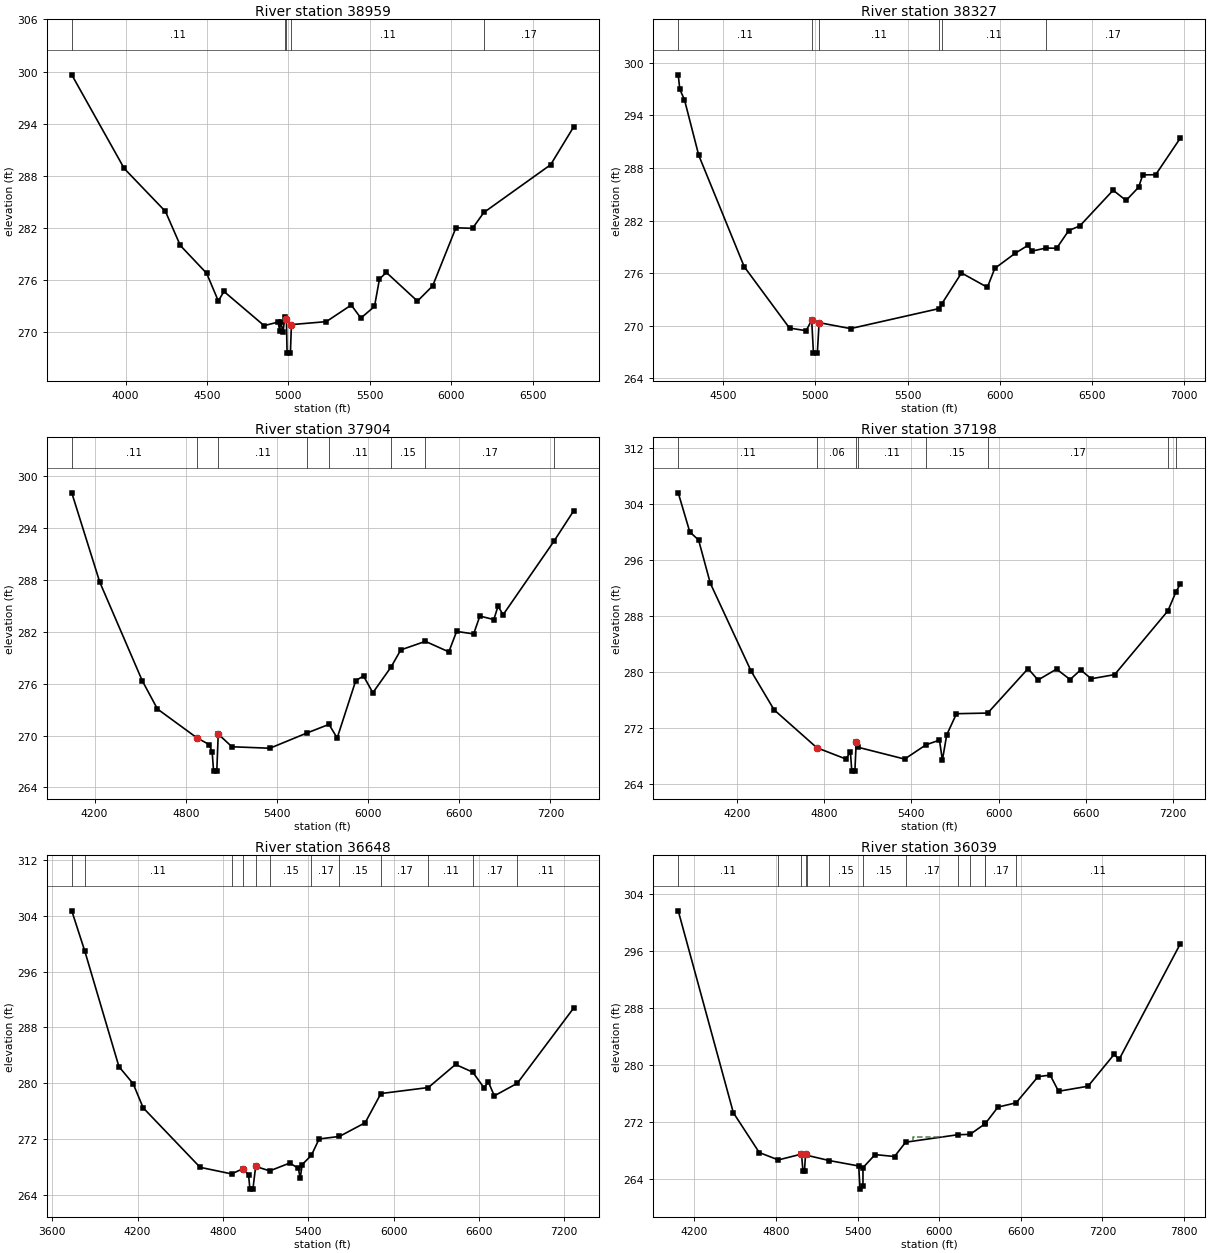
Type RM Length L Ch R = 1 ,38959   ,632,632,632
BEGIN DESCRIPTION:
ROBINSON CREEK 63.0
END DESCRIPTION:
XS GIS Cut Line= 3
      3787465.93     10233660.29      3786636.04     10233524.86
      3784438.08     10233073.47
#Sta/Elev= 30
  3669.2  299.62  3991.5  288.85  4244.8  283.91    4336     280  4497.8   276.8
  4569.5  273.62  4604.3  274.71  4851.1  270.78    4937  271.19  4946.8  270.19
  4951.9  271.25  4967.6  270.07  4977.8  271.77    4988   271.6    4992  267.62
  5012.5  267.62  5018.7   270.9    5233  271.24  5386.2  273.15  5445.4  271.65
  5529.1  272.99  5559.7  276.14  5601.7   276.9  5792.9   273.6  5886.4  275.35
  6029.3  282.03  6131.4  281.97  6200.8  283.79  6611.2  289.28  6753.9  293.67
#Mann= 5 ,-1 , 0
  3669.2     .11       0  4977.8     .09       0    4988     .06       0
  5018.7     .11       0  6200.8     .17       0
#XS Ineff= 2 ,-1
  5386.2    5535  273.15  5601.7    5940   276.9
Permanent Ineff=
       F       F
Bank Sta=4988,5018.7
XS Rating Curve= 0 ,0
Exp/Cntr=0.3,0.1

Type RM Length L Ch R = 1 ,38327   ,423,423,423
BEGIN DESCRIPTION:
ROBINSON CREEK 62.0
END DESCRIPTION:
XS GIS Cut Line= 3
      3787136.05     10232993.61      3786592.12     10232866.21
      3784434.62     10233010.98
#Sta/Elev= 30
    4257  298.63  4265.4  296.98  4290.6   295.8  4368.1  289.45  4614.6  276.73
    4860  269.73  4950.2  269.43  4980.3  270.64  4989.8  266.87  5010.8  266.87
  5020.4  270.35  5190.8  269.67    5672  271.96  5686.2  272.52  5792.1  276.02
  5932.4  274.38  5972.5  276.54  6082.8  278.26  6152.9  279.18    6173  278.51
  6249.6  278.86  6307.8  278.84  6373.4  280.86  6433.5  281.39    6614  285.46
  6684.1  284.29  6752.3  285.81  6774.3  287.21  6844.5  287.23    6978  291.41
#Mann= 6 ,-1 , 0
    4257     .11       0  4980.3     .06       0  5020.4     .11       0
    5672     .17       0  5686.2     .11       0  6249.6     .17       0
Bank Sta=4980.3,5020.4
XS Rating Curve= 0 ,0
Exp/Cntr=0.3,0.1

Type RM Length L Ch R = 1 ,37904   ,706,706,706
BEGIN DESCRIPTION:
ROBINSON CREEK 61.0
END DESCRIPTION:
XS GIS Cut Line= 3
      3787361.73     10232465.83      3785750.62     10232465.83
      3784091.93      10232805.9
#Sta/Elev= 30
  4049.6  298.09  4233.5  287.77  4513.5  276.34  4613.5  273.07  4873.5  269.73
  4953.5  268.96  4973.5  268.12  4982.9  265.88    5004  265.88  5013.5  270.17
  5103.5   268.7  5353.5  268.53  5596.8  270.29  5742.5  271.29  5796.2  269.71
  5918.7  276.36  5969.8  276.89    6031  274.95  6151.8  277.95  6214.8  279.91
    6377   280.9  6531.2  279.68  6582.3  282.05  6694.5  281.76  6735.4  283.83
  6827.2  283.42  6854.8  284.97  6888.5  283.98  7222.7  292.48  7353.9  296.04
#Mann= 8 ,-1 , 0
  4049.6     .11       0  4873.5     .06       0  5013.5     .11       0
  5596.8     .15       0  5742.5     .11       0  6151.8     .15       0
    6377     .17       0  7222.7     .11       0
Bank Sta=4873.5,5013.5
XS Rating Curve= 0 ,0
Exp/Cntr=0.3,0.1

Type RM Length L Ch R = 1 ,37198   ,550,550,550
BEGIN DESCRIPTION:
ROBINSON CREEK 60.0
END DESCRIPTION:
XS GIS Cut Line= 3
      3787417.28     10231719.31      3785531.87     10231910.28
      3784026.51     10232326.51
#Sta/Elev= 30
  3794.9  305.54  3874.7  299.94    3935  298.81  4015.5  292.64  4296.9  280.07
    4455  274.55  4749.2  269.14  4949.4  267.53  4980.4  268.56  4989.9   265.8
    5011   265.8  5020.6  269.96  5030.6  269.22  5353.9  267.52    5500  269.55
  5593.5  270.23  5613.6  267.35  5643.5  270.98  5710.7     274  5925.8  274.09
  6203.6  280.44  6272.2  278.81  6399.6  280.37    6493  278.88  6565.6  280.26
  6638.3  278.99  6799.5  279.58  7166.5  288.69  7221.3  291.37  7251.8  292.53
#Mann= 8 ,-1 , 0
  3794.9     .11       0  4749.2     .06       0  5020.6     .09       0
  5030.6     .11       0    5500     .15       0  5925.8     .17       0
  7166.5     .11       0  7221.3     .17       0
Bank Sta=4749.2,5020.6
XS Rating Curve= 0 ,0
Exp/Cntr=0.3,0.1

Type RM Length L Ch R = 1 ,36648   ,609,609,609
BEGIN DESCRIPTION:
ROBINSON CREEK 59.0
END DESCRIPTION:
XS GIS Cut Line= 3
      3787309.01     10231277.32      3785705.48     10231361.67
      3783862.28     10231913.59
#Sta/Elev= 30
  3737.4  304.69  3828.3  298.97    4069  282.39  4169.2  279.94  4239.3   276.5
  4639.8  267.98  4860.5  267.04  4940.2  267.77  4980.3  266.91  4989.7  264.86
  5010.9  264.86  5030.3  268.11    5129  267.47  5270.7   268.6  5330.8  267.82
  5343.1  266.39  5357.4  268.38  5421.7  269.69  5476.4  272.04    5619   272.4
    5800  274.36  5910.9  278.54  6244.1   279.4  6435.4   282.7  6556.8   281.6
  6635.1  279.37  6666.4  280.19  6708.1  278.21  6869.6  280.01  7267.2  290.81
#Mann= 12 ,-1 , 0
  3737.4     .17       0  3828.3     .11       0  4860.5     .14       0
  4940.2     .06       0  5030.3     .14       0    5129     .15       0
  5421.7     .17       0    5619     .15       0  5910.9     .17       0
  6244.1     .11       0  6556.8     .17       0  6869.6     .11       0
Bank Sta=4940.2,5030.3
XS Rating Curve= 0 ,0
Exp/Cntr=0.3,0.1

Type RM Length L Ch R = 1 ,36039   ,298,298,298
BEGIN DESCRIPTION:
ROBINSON CREEK 58.0
END DESCRIPTION:
XS GIS Cut Line= 3
      3787042.28     10230701.95      3785479.79     10230799.17
      3783583.92     10231760.99
#Sta/Elev= 30
  4081.8  301.62    4487  273.27  4677.4  267.68  4817.6  266.64    4988  267.46
  4998.5  265.15  5010.2  265.15    5018  267.53  5028.1  267.29  5192.4  266.55
  5408.8  265.79  5418.2  262.54    5440  263.04  5440.1  265.55    5529  267.39
  5671.9  267.12  5753.9  269.13    6138  270.18  6227.3  270.23  6339.9  271.74
  6340.2  271.76  6432.5  274.06    6566  274.66  6727.5  278.34  6816.6  278.55
  6877.8  276.28  7094.8  276.99  7286.6  281.46  7323.1  280.75  7773.2  296.99
#Mann= 13 ,-1 , 0
  4081.8     .11       0  4817.6     .15       0    4988     .06       0
    5018     .09       0  5028.1     .15       0  5192.4     .15       0
    5440     .15       0  5753.9     .17       0    6138     .11       0
  6227.3     .17       0  6339.9     .11       0  6340.2     .17       0
    6566     .11       0
#XS Ineff= 1 ,-1
  5806.5    6025  269.86
Permanent Ineff=
       F
Bank Sta=4988,5018
XS Rating Curve= 0 ,0
Exp/Cntr=0.3,0.1

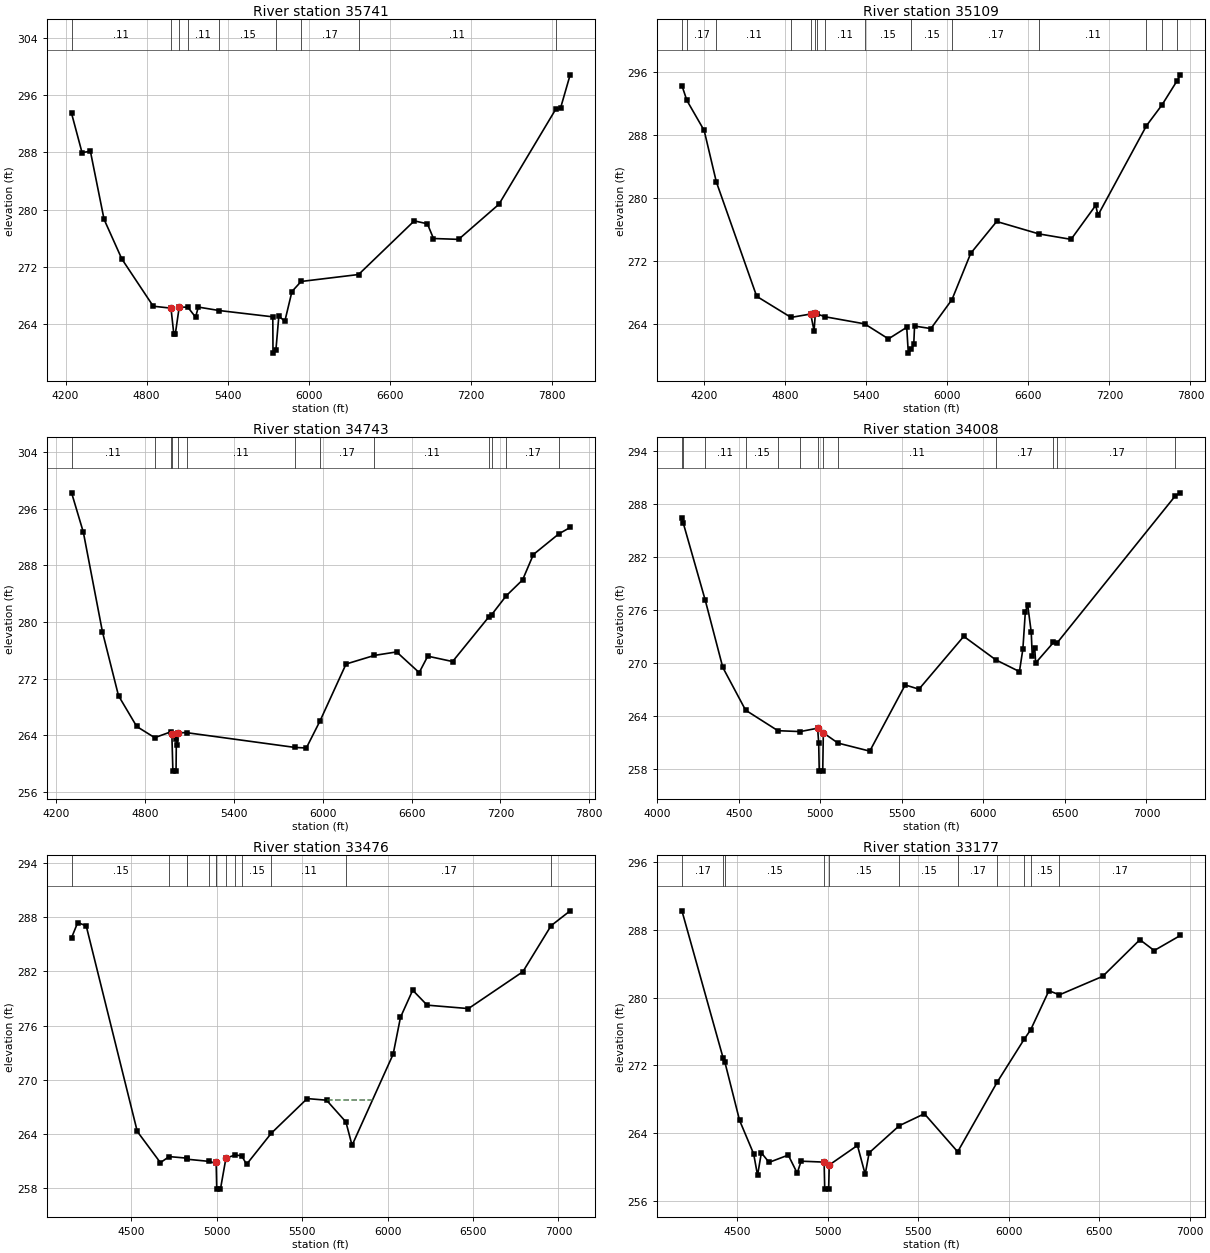
Type RM Length L Ch R = 1 ,35741   ,632,632,632
BEGIN DESCRIPTION:
ROBINSON CREEK 57.0
END DESCRIPTION:
XS GIS Cut Line= 3
      3786875.64     10230354.72      3785462.42     10230556.11
      3783431.98     10231548.77
#Sta/Elev= 30
    4245  293.41    4322  287.97  4384.2  288.13  4485.2  278.65  4616.5  273.13
  4848.8  266.54  4980.1  266.27  5000.8  262.71  5012.5  262.71  5040.8  266.39
  5103.9  266.42    5162  265.02  5182.2  266.42    5336  265.94  5733.2  265.06
  5734.7     260  5756.5   260.5  5777.8  265.15  5822.3  264.45  5874.8  268.59
  5942.7  269.99  6367.7  270.96  6779.6  278.44  6876.6  278.03  6921.7  275.98
  7107.4  275.86  7405.6  280.75  7826.2  294.01  7861.5  294.16  7932.6   298.8
#Mann= 9 ,-1 , 0
    4245     .11       0  4980.1     .06       0  5040.8     .15       0
  5103.9     .11       0    5336     .15       0  5756.5     .15       0
  5942.7     .17       0  6367.7     .11       0  7826.2     .17       0
Bank Sta=4980.1,5040.8
XS Rating Curve= 0 ,0
Exp/Cntr=0.3,0.1

Type RM Length L Ch R = 1 ,35109   ,366,366,366
BEGIN DESCRIPTION:
ROBINSON CREEK 56.0
END DESCRIPTION:
XS GIS Cut Line= 3
       3786611.7     10229590.85      3785816.59     10230031.81
      3783352.06     10231319.61
#Sta/Elev= 30
  4036.4  294.32  4073.2  292.43  4200.9  288.62  4290.9  282.09  4589.7  267.54
  4843.9  264.86  4989.3  265.29  5014.3  263.17  5024.2  265.41  5034.4  265.31
    5096  264.94  5388.6  264.04  5564.9  262.13  5700.1   263.6    5712  260.32
  5733.8  260.82  5752.3  261.48    5758  263.76  5879.1  263.44  6034.9  267.12
    6174  273.01  6365.8  277.05  6679.1  275.47  6916.4  274.78  7099.2  279.11
  7115.1  277.83  7474.7  289.23  7588.5  291.84  7702.1  294.96  7726.3  295.69
#Mann= 15 ,-1 , 0
  4036.4     .11       0  4073.2     .17       0  4290.9     .11       0
  4843.9     .15       0  4989.3     .06       0  5024.2     .09       0
  5034.4     .15       0    5096     .11       0  5388.6     .15       0
  5733.8     .15       0  6034.9     .17       0  6679.1     .11       0
  7474.7     .17       0  7588.5     .11       0  7702.1     .17       0
Bank Sta=4989.3,5024.2
XS Rating Curve= 0 ,0
Exp/Cntr=0.3,0.1

Type RM Length L Ch R = 1 ,34743   ,735,735,735
BEGIN DESCRIPTION:
ROBINSON CREEK 55.0
END DESCRIPTION:
XS GIS Cut Line= 3
      3786167.83     10229361.08      3785588.48     10229747.86
      3783316.57     10231153.34
#Sta/Elev= 30
  4303.4  298.25    4383  292.66  4512.1  278.57  4620.3  269.57  4743.4  265.22
  4864.8  263.64  4974.7  264.47  4980.7  264.18  4987.7  258.91  5009.1  258.91
  5011.1  263.46    5017  262.58  5024.3  264.35    5083  264.34  5812.1  262.26
  5889.2  262.18  5982.3  266.03  6157.5  274.05  6349.6  275.27  6499.1  275.76
  6651.6  272.84  6709.5  275.16  6877.3   274.4  7120.1  280.66  7140.6  281.01
    7239  283.68  7350.1  285.94  7423.1  289.53  7595.7  292.46  7671.5  293.35
#Mann= 13 ,-1 , 0
  4303.4     .11       0  4864.8     .15       0  4974.7     .11       0
  4980.7     .07       0  5024.3     .15       0    5083     .11       0
  5812.1     .15       0  5982.3     .17       0  6349.6     .11       0
  7120.1     .17       0  7140.6     .11       0    7239     .17       0
  7595.7     .11       0
Bank Sta=4980.7,5024.3
XS Rating Curve= 0 ,0
Exp/Cntr=0.3,0.1

Type RM Length L Ch R = 1 ,34008   ,532,532,532
BEGIN DESCRIPTION:
ROBINSON CREEK 54.0
END DESCRIPTION:
XS GIS Cut Line= 3
      3785608.23      10228799.2      3784854.79       10229695.
      3783272.12     10230722.34
#Sta/Elev= 30
  4151.1  286.37  4158.7  285.87  4294.3   277.1  4401.7  269.52  4541.5  264.69
  4739.5  262.37  4876.9  262.27  4983.1  262.65  4989.8  261.01  4993.2   257.8
  5014.6   257.8  5018.2  262.13  5107.9  260.97    5303  260.06  5520.2  267.54
  5604.6  267.06  5879.4  273.03  6075.5  270.38  6220.8  269.05  6241.9  271.58
  6257.1  275.83  6271.7  276.55  6293.3  273.49  6299.3  270.86  6314.4  271.74
  6320.4  270.03  6429.5  272.34  6453.5  272.33  7177.7  288.93  7208.5  289.25
#Mann= 13 ,-1 , 0
  4151.1     .17       0  4158.7     .15       0  4294.3     .11       0
  4541.5     .15       0  4739.5     .11       0  4876.9     .15       0
  4983.1     .06       0  5018.2     .15       0  5107.9     .11       0
  6075.5     .17       0  6429.5     .11       0  6453.5     .17       0
  7177.7     .11       0
Bank Sta=4983.1,5018.2
XS Rating Curve= 0 ,0
Exp/Cntr=0.3,0.1

Type RM Length L Ch R = 1 ,33476   ,299,299,299
BEGIN DESCRIPTION:
ROBINSON CREEK 53.0
END DESCRIPTION:
XS GIS Cut Line= 3
      3785469.39     10228632.49      3784868.67      10229108.2
      3783223.46     10230496.56
#Sta/Elev= 30
  4149.7  285.75  4185.6  287.43  4235.3  287.06  4534.3  264.24  4669.6  260.78
    4721  261.45  4823.8  261.28  4825.7  261.16  4954.5  260.92    4995  260.69
  4996.1   260.8  4999.6  257.84  5021.2  257.84  5053.3  261.27  5106.5  261.63
  5145.5  261.54  5174.2  260.59  5319.2  264.05  5529.2  267.89  5642.3  267.71
  5755.7   265.3  5791.8   262.7  6032.4  272.82  6075.3  276.91  6146.8  279.92
  6231.4  278.26  6473.2  277.88  6791.8  281.97  6957.1  287.08  7068.7  288.73
#Mann= 13 ,-1 , 0
  4149.7     .15       0    4721     .11       0  4823.8     .15       0
  4825.7     .11       0  4954.5     .15       0    4995     .09       0
  4996.1     .06       0  5053.3     .15       0  5106.5     .11       0
  5145.5     .15       0  5319.2     .11       0  5755.7     .17       0
  6957.1     .11       0
#XS Ineff= 1 ,-1
  5642.3    5910  267.71
Permanent Ineff=
       F
Bank Sta=4996.1,5053.3
XS Rating Curve= 0 ,0
Exp/Cntr=0.3,0.1

Type RM Length L Ch R = 1 ,33177   ,568,568,568
BEGIN DESCRIPTION:
ROBINSON CREEK 52.0
END DESCRIPTION:
XS GIS Cut Line= 3
      3785236.71      10228410.3      3784642.78     10228952.36
      3783168.08     10230226.82
#Sta/Elev= 30
  4195.9  290.25  4422.9  272.91  4433.3  272.37  4514.2  265.51  4591.9  261.56
  4613.6  259.02  4634.5  261.68  4677.1  260.55  4783.1  261.41  4832.5  259.28
  4854.1  260.69  4981.1  260.58  4984.5  257.39  5006.1  257.39  5009.4  260.24
  5165.2  262.55  5207.9  259.14  5229.8  261.68  5396.2  264.88  5534.8  266.29
  5718.7   261.8  5936.8  270.02  6085.3  275.07  6121.7   276.2  6222.5  280.82
  6280.5  280.33  6519.8  282.52  6724.9  286.84  6803.9  285.56  6949.1  287.35
#Mann= 11 ,-1 , 0
  4195.9     .17       0  4422.9     .11       0  4433.3     .15       0
  4981.1     .07       0  5009.4     .15       0  5396.2     .15       0
  5718.7     .17       0  5936.8     .15       0  6085.3     .17       0
  6121.7     .15       0  6280.5     .17       0
#XS Ineff= 1 ,-1
  5534.8    5860  266.29
Permanent Ineff=
       F
Bank Sta=4981.1,5009.4
XS Rating Curve= 0 ,0
Exp/Cntr=0.3,0.1