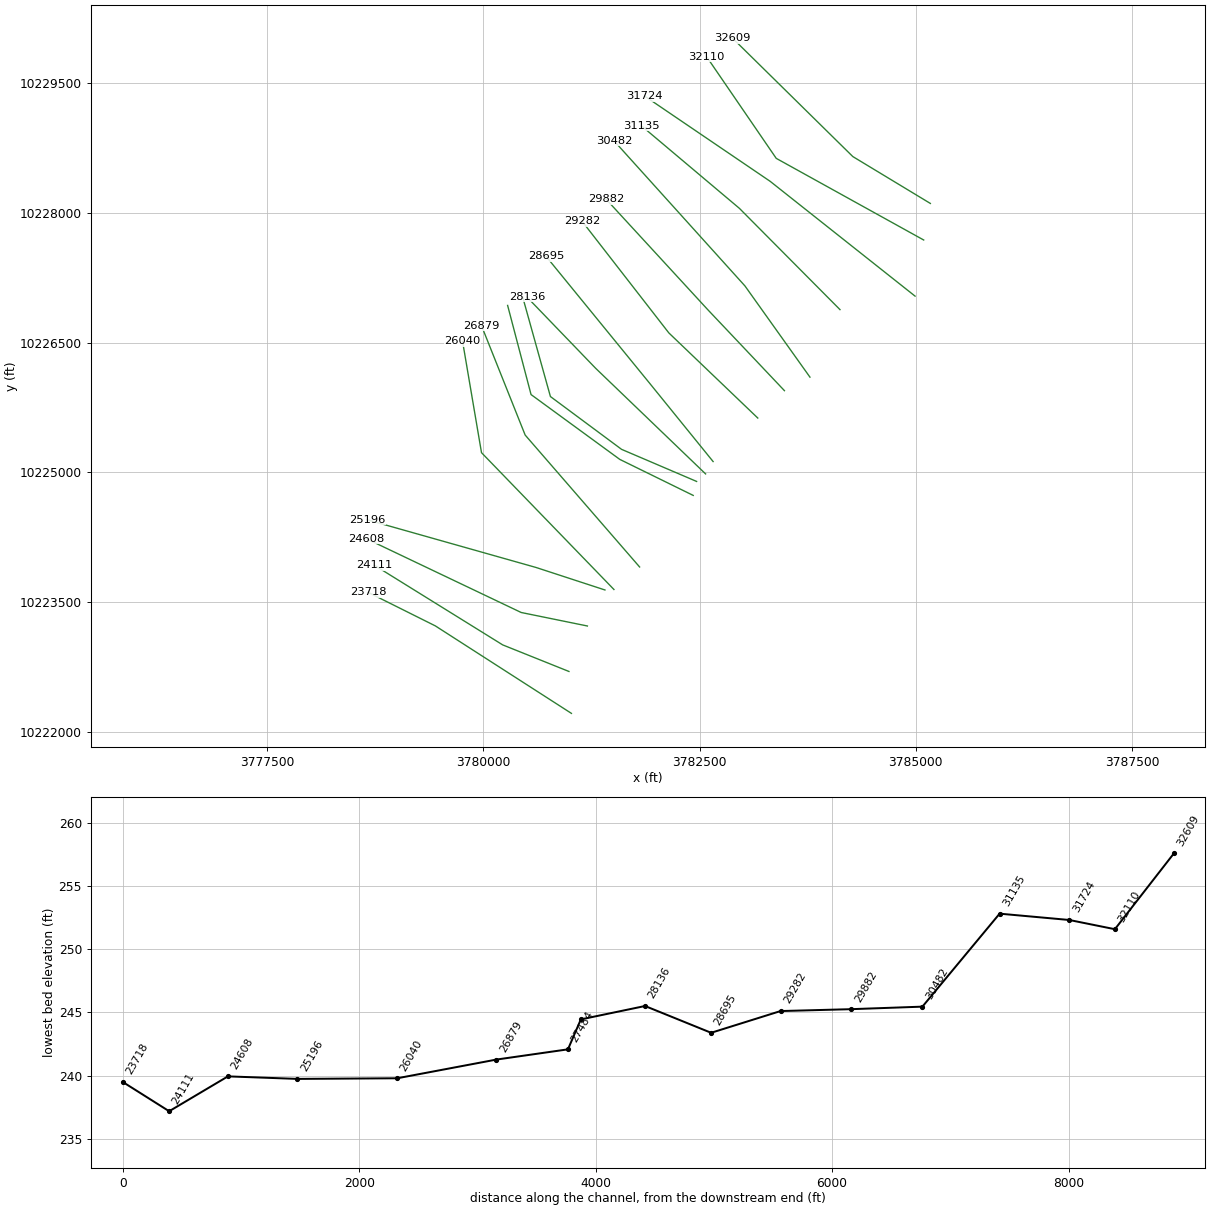
HEC-RAS study ROBINSON CREEK.prj: ROBINSON CREEK Base Level Engineering

--- ROBINSON CREEK.g01 (geometry) --- (continued)

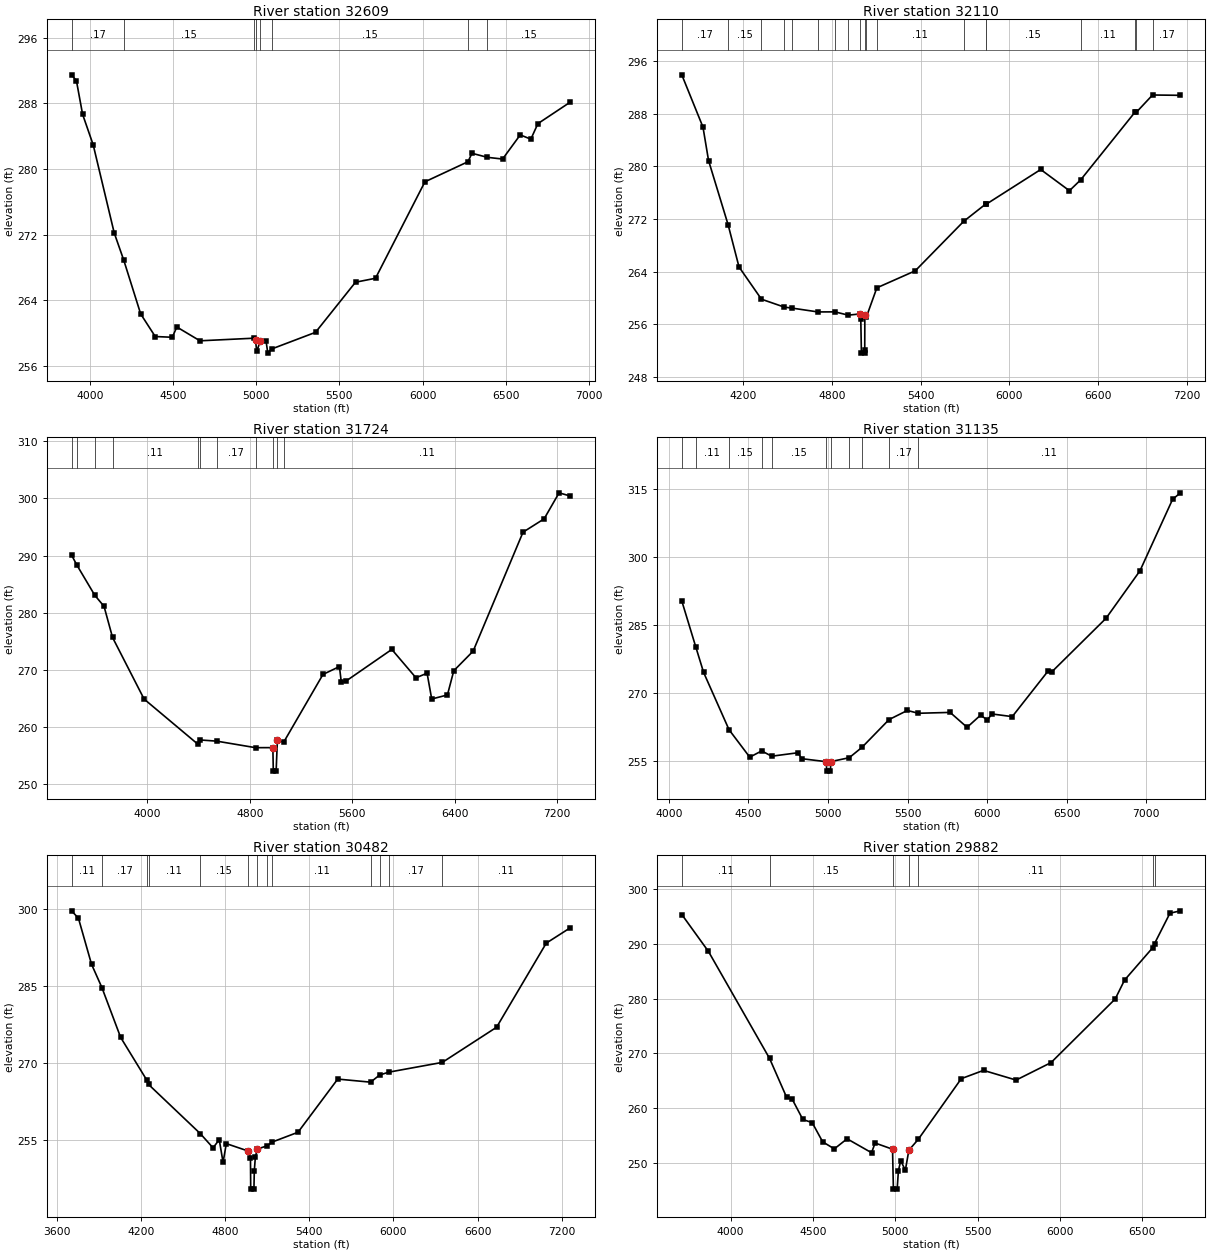
Type RM Length L Ch R = 1 ,32609   ,499,499,499
BEGIN DESCRIPTION:
ROBINSON CREEK 51.0
END DESCRIPTION:
XS GIS Cut Line= 3
      3785167.86     10228111.07      3784271.45     10228653.33
      3782882.68     10230021.27
#Sta/Elev= 30
    3891  291.46  3920.1  290.73    3957  286.66    4021  282.92  4147.1  272.22
  4204.5   268.9  4306.1  262.36  4393.6  259.61  4496.2  259.52  4523.4  260.77
  4662.4  259.09  4989.1  259.41  4996.2  259.16  5003.7  257.79  5024.5  259.05
  5059.8  259.04  5070.1  257.59  5092.6  258.09  5356.8  260.12  5597.2  266.22
  5717.4   266.7  6014.4  278.44  6272.7  280.88  6297.3  281.91  6389.5  281.42
  6481.1  281.21  6587.2  284.15  6650.9  283.63  6693.3  285.52    6888  288.14
#Mann= 8 ,-1 , 0
    3891     .17       0  4204.5     .15       0  4989.1     .12       0
  4996.2     .09       0  5024.5     .15       0  5092.6     .15       0
  6272.7     .17       0  6389.5     .15       0
Bank Sta=4996.2,5024.5
XS Rating Curve= 0 ,0
Exp/Cntr=0.3,0.1

Type RM Length L Ch R = 1 ,32110   ,386,386,386
BEGIN DESCRIPTION:
ROBINSON CREEK 50.0
END DESCRIPTION:
XS GIS Cut Line= 3
      3785090.88     10227688.06      3783386.04      10228632.5
      3782580.48     10229809.58
#Sta/Elev= 30
  3782.9  293.95  3926.3  285.99    3964   280.9  4096.5  271.12  4170.1  264.71
  4321.9   259.8  4477.4  258.59  4530.5  258.44  4704.2  257.86  4819.5  257.87
  4909.7  257.37  4986.7  257.55  4994.4  256.75  4998.6  251.59  5020.6  251.59
  5021.1  252.09  5021.8  257.38  5032.2  257.09  5103.1  261.53    5363  264.12
  5690.5  271.64  5839.1  274.27  5840.9  274.22  6212.2  279.54  6406.5  276.31
  6482.6  277.96  6853.1  288.35    6859  288.24  6969.1  290.88  7158.2  290.83
#Mann= 19 ,-1 , 0
  3782.9     .17       0  4096.5     .15       0  4321.9     .11       0
  4477.4     .15       0  4530.5     .11       0  4704.2     .17       0
  4819.5     .11       0  4909.7     .15       0  4986.7     .09       0
  5021.8     .12       0  5032.2     .15       0  5103.1     .11       0
  5690.5     .15       0  5839.1     .11       0  5840.9     .15       0
  6482.6     .11       0  6853.1     .17       0    6859     .15       0
  6969.1     .17       0
Bank Sta=4986.7,5021.8
XS Rating Curve= 0 ,0
Exp/Cntr=0.3,0.1

Type RM Length L Ch R = 1 ,31724   ,589,589,589
BEGIN DESCRIPTION:
ROBINSON CREEK 49.0
END DESCRIPTION:
XS GIS Cut Line= 3
      3784991.08     10227038.74      3783315.72     10228366.88
      3781866.07     10229352.12
#Sta/Elev= 30
  3410.3  290.08  3452.4  288.31  3591.1  283.07  3663.4  281.13  3729.8  275.69
  3975.9  264.92  4392.7  257.08  4414.2  257.77  4543.5  257.56  4845.3  256.42
  4980.6  256.43    4984  252.32  5006.1  252.32  5015.8  257.73  5065.5   257.4
  5371.6  269.23  5499.8   270.6  5514.2  267.92  5547.6  268.01  5908.5   273.6
    6097  268.64  6183.8  269.44  6219.8  264.93  6342.5  265.64    6392  269.87
  6543.1   273.3  6932.3   294.1  7096.9  296.43  7213.6  300.98    7301  300.42
#Mann= 11 ,-1 , 0
  3410.3     .17       0  3452.4     .11       0  3591.1     .17       0
  3729.8     .11       0  4392.7     .15       0  4414.2     .11       0
  4543.5     .17       0  4845.3     .15       0  4980.6     .09       0
  5015.8     .15       0  5065.5     .11       0
Bank Sta=4980.6,5015.8
XS Rating Curve= 0 ,0
Exp/Cntr=0.3,0.1

Type RM Length L Ch R = 1 ,31135   ,653,653,653
BEGIN DESCRIPTION:
ROBINSON CREEK 48.0
END DESCRIPTION:
XS GIS Cut Line= 3
      3784123.04     10226882.47      3782959.82     10228054.38
      3781826.97     10229009.27
#Sta/Elev= 30
  4081.3  290.35  4168.9  280.24  4218.3  274.59  4378.1  261.95  4508.2   255.9
  4583.2  257.28  4645.8  256.11  4812.3  256.88  4833.5  255.57  4989.1   254.9
  4991.8  252.82  5014.7  252.82  5017.4  254.92  5133.2  255.78  5213.1  258.06
  5383.3  264.19  5498.2   266.2  5567.2  265.58    5767  265.77  5873.6  262.48
  5958.1  265.16    6001   264.1  6029.6  265.43  6157.1  264.84  6384.6     275
  6405.5   274.7  6746.2  286.52  6959.4  296.99  7164.9  312.79  7214.1   314.2
#Mann= 11 ,-1 , 0
  4081.3     .17       0  4168.9     .11       0  4378.1     .15       0
  4583.2     .11       0  4645.8     .15       0  4989.1     .09       0
  5017.4     .15       0  5133.2     .11       0  5213.1     .15       0
  5383.3     .17       0  5567.2     .11       0
Bank Sta=4989.1,5017.4
XS Rating Curve= 0 ,0
Exp/Cntr=0.3,0.1

Type RM Length L Ch R = 1 ,30482   ,600,600,600
BEGIN DESCRIPTION:
ROBINSON CREEK 47.0
END DESCRIPTION:
XS GIS Cut Line= 3
       3783775.8     10226101.24      3783024.31     10227156.39
      3781510.15     10228835.64
#Sta/Elev= 30
  3704.6  299.63  3753.5  298.18  3846.6  289.24  3920.6   284.7  4054.4  274.99
  4242.2  266.62  4253.5  265.83  4621.8  256.28  4713.4   253.5  4757.6  255.08
  4784.8  250.66    4808  254.32  4965.4  252.86  4980.2  251.49    4982  245.46
  5004.9  245.46  5007.6  249.01  5015.1   251.7  5029.3  253.28  5098.1  253.87
  5136.7  254.64  5319.3  256.53  5602.5  266.88  5837.1  266.28  5900.7  267.66
    5965  268.22  6348.6  270.13  6735.5  276.97  7089.7  293.34  7261.1  296.33
#Mann= 13 ,-1 , 0
  3704.6     .11       0  3920.6     .17       0  4242.2     .15       0
  4253.5     .11       0  4621.8     .15       0  4965.4     .09       0
  5029.3     .15       0  5098.1     .15       0  5136.7     .11       0
  5837.1     .17       0  5900.7     .11       0    5965     .17       0
  6348.6     .11       0
Bank Sta=4965.4,5029.3
XS Rating Curve= 0 ,0
Exp/Cntr=0.3,0.1

Type RM Length L Ch R = 1 ,29882   ,600,600,600
BEGIN DESCRIPTION:
ROBINSON CREEK 46.0
END DESCRIPTION:
XS GIS Cut Line= 3
      3783480.67     10225944.98      3782589.46     10226887.02
      3781417.82      10228161.1
#Sta/Elev= 30
  3703.2  295.35    3865  288.61  4236.2  269.09  4339.1  262.04  4374.3  261.62
  4438.2  257.96  4494.8  257.39  4558.4  253.89  4629.2   252.6  4706.8  254.44
  4855.3   251.9  4876.7  253.67  4982.7  252.54  4987.9  245.26  5010.8  245.26
  5018.4  248.65  5032.6  250.44  5060.4   248.7  5081.9  252.36  5138.6  254.33
  5400.1  265.41  5535.1  266.92    5733  265.15  5945.1  268.34  6334.7  279.95
  6391.2  283.38  6562.4   289.3  6573.7  290.06    6667  295.59  6730.9  296.02
#Mann= 7 ,-1 , 0
  3703.2     .11       0  4236.2     .15       0  4982.7     .09       0
  5081.9     .15       0  5138.6     .11       0  6562.4     .17       0
  6573.7     .11       0
Bank Sta=4982.7,5081.9
XS Rating Curve= 0 ,0
Exp/Cntr=0.3,0.1

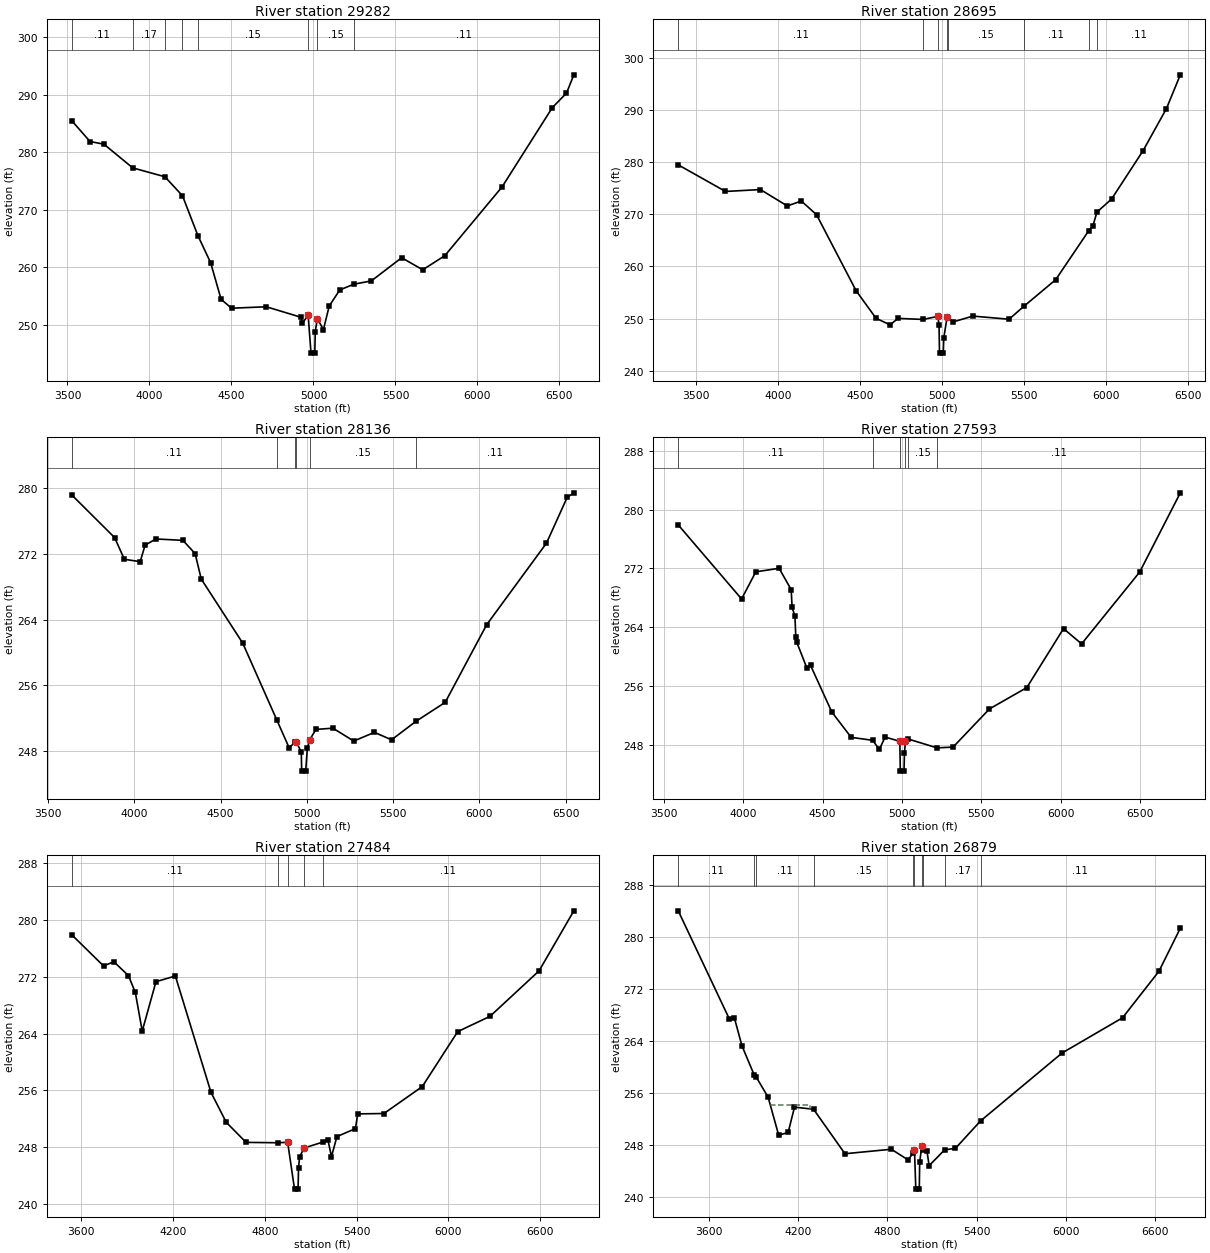
Type RM Length L Ch R = 1 ,29282   ,587,587,587
BEGIN DESCRIPTION:
ROBINSON CREEK 45.0
END DESCRIPTION:
XS GIS Cut Line= 3
      3783172.46     10225628.19      3782143.85      10226613.4
      3781139.85     10227906.47
#Sta/Elev= 30
  3526.1  285.47  3637.5  281.86  3722.4  281.39  3897.7  277.28  4093.9  275.74
  4201.1  272.44    4295  265.53  4373.1  260.79  4436.6  254.45  4500.5  252.91
  4712.5  253.16  4924.7  251.33  4931.7  250.29  4967.4  251.68  4984.9  245.11
  5007.9  245.11  5010.8  248.85  5023.5  251.09  5060.6  249.21  5095.9  253.29
  5160.2  256.08  5245.8  257.08  5352.6  257.65  5537.6  261.68  5666.1  259.58
    5801  262.04  6150.2  273.99  6456.3  287.75  6542.7  290.26  6587.5  293.44
#Mann= 8 ,-1 , 0
  3526.1     .11       0  3897.7     .17       0  4093.9     .15       0
  4201.1     .17       0    4295     .15       0  4967.4     .09       0
  5023.5     .15       0  5245.8     .11       0
Bank Sta=4967.4,5023.5
XS Rating Curve= 0 ,0
Exp/Cntr=0.3,0.1

Type RM Length L Ch R = 1 ,28695   ,559,559,559
BEGIN DESCRIPTION:
ROBINSON CREEK 44.0
END DESCRIPTION:
XS GIS Cut Line= 3
      3782656.01     10225124.68      3781920.75     10226032.34
      3780725.69     10227497.46
#Sta/Elev= 30
  3393.3  279.49  3681.2  274.39  3893.9  274.75  4057.9  271.61  4143.3  272.56
    4236  269.92  4477.4  255.33  4598.5  250.07  4683.5  248.82    4733  250.05
  4884.7  249.85  4974.3  250.43  4982.2  248.84    4985  243.39  5008.1  243.39
  5010.9  246.28  5031.7  250.36  5038.2  250.19  5066.9  249.37  5188.3  250.49
  5408.7  249.89  5499.7  252.38  5693.1  257.48  5894.8  266.89  5919.9  267.83
  5944.5  270.44  6033.4  272.94  6225.1   282.2  6367.3  290.26  6452.1  296.75
#Mann= 8 ,-1 , 0
  3393.3     .11       0  4884.7     .15       0  4974.3     .09       0
  5031.7     .12       0  5038.2     .15       0  5499.7     .11       0
  5894.8     .17       0  5944.5     .11       0
Bank Sta=4974.3,5031.7
XS Rating Curve= 0 ,0
Exp/Cntr=0.3,0.1

Type RM Length L Ch R = 1 ,28136   ,543,543,543
BEGIN DESCRIPTION:
ROBINSON CREEK 43.0
END DESCRIPTION:
XS GIS Cut Line= 4
      3782569.19     10224981.46      3781739.24     10225779.42
      3781297.02     10226204.61      3780502.05     10227029.62
#Sta/Elev= 30
  3637.6  279.21  3885.9  274.01  3942.5  271.36  4034.3  271.07  4062.6  273.09
  4126.2  273.84  4281.8  273.67  4352.6  272.06  4388.1  268.95  4628.4  261.14
  4826.5  251.74  4897.2  248.38  4932.5  249.01  4939.7  249.11    4968   247.8
  4970.5  245.51  4993.7  245.51  5003.2  248.32  5017.4  249.35  5052.9   250.6
  5151.6  250.75  5272.1  249.18  5392.2  250.24  5491.3  249.33  5633.7   251.6
  5802.3   253.9  6042.9  263.38  6389.4  273.33  6509.6  278.92  6548.1  279.47
#Mann= 6 ,-1 , 0
  3637.6     .11       0  4826.5     .15       0  4932.5     .12       0
  4939.7     .09       0  5017.4     .15       0  5633.7     .11       0
Bank Sta=4939.7,5017.4
XS Rating Curve= 0 ,0
Exp/Cntr=0.3,0.1

Type RM Length L Ch R = 1 ,27593   ,109,109,109
BEGIN DESCRIPTION:
ROBINSON CREEK 42.0
END DESCRIPTION:
XS GIS Cut Line= 4
      3782465.04     10224894.65      3781597.84     10225265.75
      3780774.92     10225876.86      3780453.45     10227030.53
#Sta/Elev= 30
  3589.3  277.92  3988.7  267.85  4078.5  271.54  4225.5  272.02  4301.7  269.11
  4307.1  266.73  4325.2  265.48  4330.7  262.66  4336.8  261.97  4401.4  258.41
  4423.8  258.82  4557.5  252.49  4679.9  249.04  4815.5  248.64  4857.2  247.39
  4893.8  249.08  4986.6   248.5  4989.6  244.45  5012.8  244.45  5015.8  246.87
    5022  248.54  5038.8  248.82  5221.3  247.61  5322.5  247.72    5552  252.91
    5787   255.8  6018.7  263.82  6132.9  261.75    6499  271.51  6755.2  282.28
#Mann= 6 ,-1 , 0
  3589.3     .11       0  4815.5     .15       0  4986.6     .09       0
    5022     .15       0  5038.8     .15       0  5221.3     .11       0
Bank Sta=4986.6,5022
XS Rating Curve= 0 ,0
Exp/Cntr=0.3,0.1

Type RM Length L Ch R = 1 ,27484   ,605,605,605
BEGIN DESCRIPTION:
ROBINSON CREEK 41.0
END DESCRIPTION:
XS GIS Cut Line= 4
      3782425.99     10224732.96      3781577.02     10225149.64
      3780550.98     10225899.64      3780280.13     10226930.92
#Sta/Elev= 30
  3537.2  277.94  3744.9  273.55  3812.3  274.14  3907.9  272.18  3952.8  269.81
  3997.8  264.36  4087.8  271.33  4214.6  272.13  4447.6  255.72  4547.3   251.5
  4677.1  248.67    4884  248.62  4948.9  248.68  4993.7  242.08  5016.9  242.08
  5019.9  245.04  5026.9   246.6  5055.4  247.87  5179.7  248.72  5212.7  248.96
  5235.4  246.66  5270.9  249.49  5392.1  250.61  5406.8  252.69  5578.2  252.74
    5829  256.54  6060.9  264.29  6272.3  266.45  6592.8  272.86  6820.1  281.32
#Mann= 5 ,-1 , 0
  3537.2     .11       0    4884     .15       0  4948.9     .09       0
  5055.4     .15       0  5179.7     .11       0
Bank Sta=4948.9,5055.4
XS Rating Curve= 0 ,0
Exp/Cntr=0.3,0.1

Type RM Length L Ch R = 1 ,26879   ,839,839,839
BEGIN DESCRIPTION:
ROBINSON CREEK 40.0
END DESCRIPTION:
XS GIS Cut Line= 3
      3781806.21     10223904.82      3780482.87     10225431.24
      3779978.15     10226696.28
#Sta/Elev= 30
  3390.7  284.05  3734.1  267.47  3769.6  267.54  3819.6  263.32  3902.7   258.8
  3914.6  258.55  3996.2   255.4  4067.4  249.56  4131.1  249.98  4173.8  253.87
  4302.3  253.55  4513.8  246.71  4826.3   247.4  4939.3  245.76  4974.4  246.88
    4982  247.31  4991.2  241.27  5014.5  241.27  5017.1  245.38  5031.4  247.87
    5039  247.35  5066.6  247.07  5080.7  244.88    5185   247.3  5258.4  247.55
    5427  251.75  5976.8   262.2  6383.8  267.61    6629  274.76  6772.9  281.38
#Mann= 10 ,-1 , 0
  3390.7     .11       0  3902.7     .15       0  3914.6     .11       0
  4302.3     .15       0  4974.4     .12       0    4982     .09       0
  5031.4     .12       0    5039     .15       0    5185     .17       0
    5427     .11       0
#XS Ineff= 1 ,-1
    4008  4280.2  254.18
Permanent Ineff=
       F
Bank Sta=4982,5031.4
XS Rating Curve= 0 ,0
Exp/Cntr=0.3,0.1

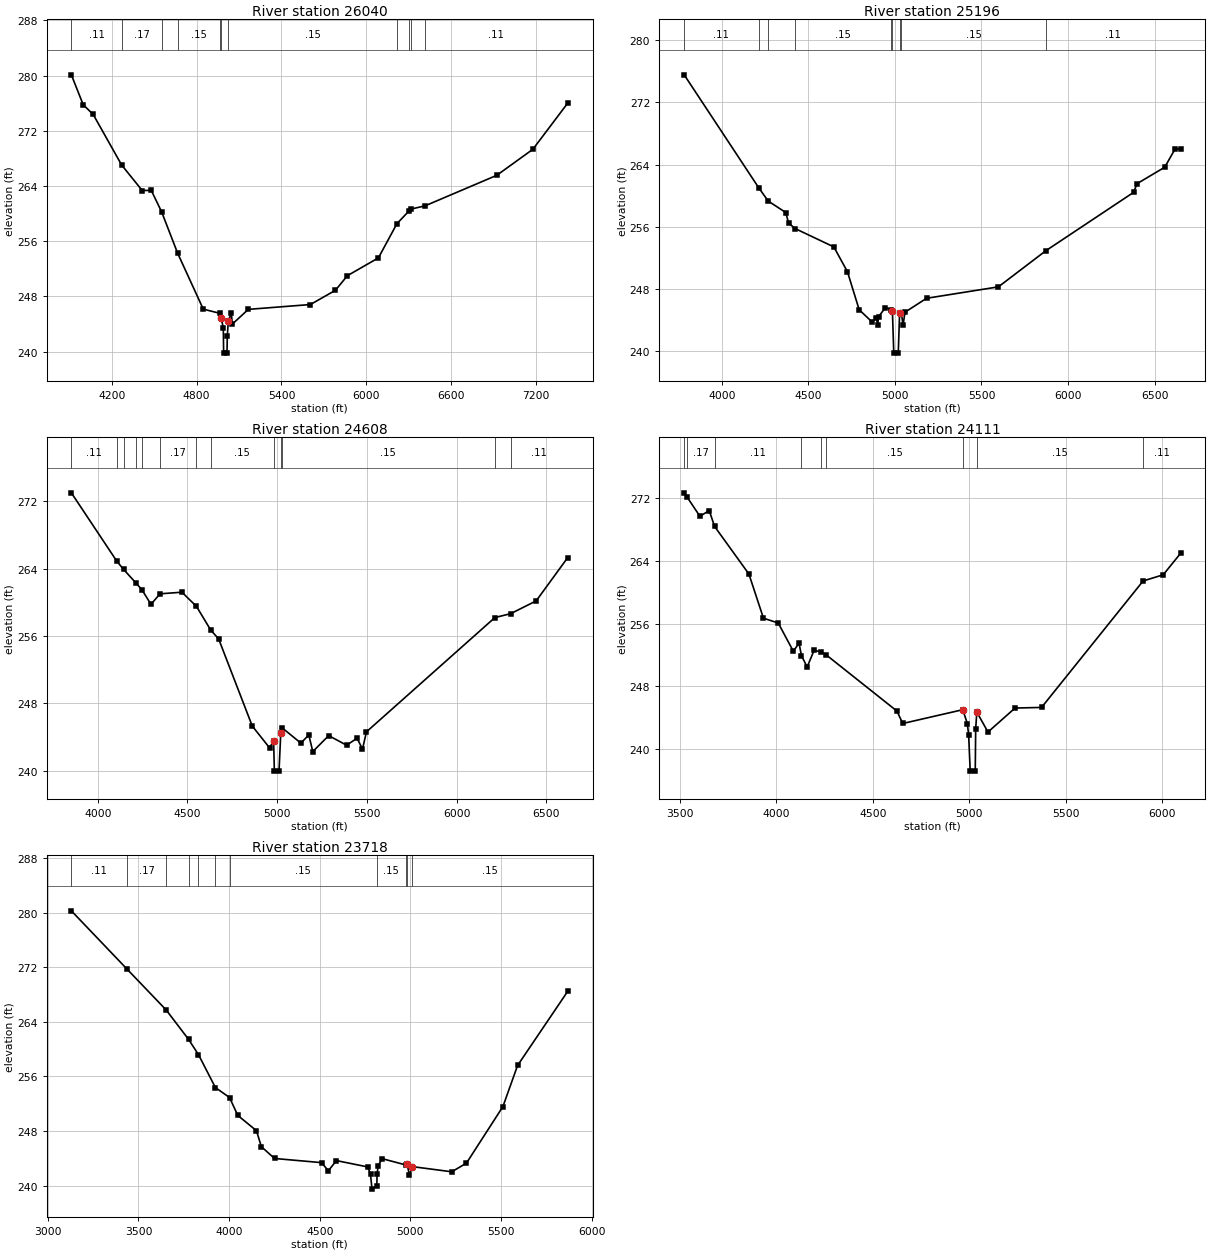
Type RM Length L Ch R = 1 ,26040   ,844,844,844
BEGIN DESCRIPTION:
ROBINSON CREEK 39.0
END DESCRIPTION:
XS GIS Cut Line= 3
      3781509.31     10223644.43      3779978.06     10225227.51
      3779759.32     10226514.18
#Sta/Elev= 30
  3915.4  280.11  3998.9  275.78  4069.6  274.37  4270.9  267.04  4416.1  263.35
  4479.9  263.37    4553  260.27  4666.3  254.27  4847.5  246.16  4967.9  245.54
  4974.9  244.84    4989  243.42  4991.4  239.79    5015  239.79  5017.3  242.27
  5024.3  244.38  5045.6  245.61  5052.6  243.99  5165.7  246.13  5604.3  246.83
  5781.1  248.89  5865.9  251.01  6085.1  253.59  6215.6  258.54  6302.4  260.41
  6314.6  260.66  6413.6  261.12  6921.2  265.55  7176.4  269.32    7423  276.02
#Mann= 11 ,-1 , 0
  3915.4     .11       0  4270.9     .17       0    4553     .11       0
  4666.3     .15       0  4967.9     .12       0  4974.9     .09       0
  5024.3     .15       0  6215.6     .11       0  6302.4     .15       0
  6314.6     .17       0  6413.6     .11       0
Bank Sta=4974.9,5024.3
XS Rating Curve= 0 ,0
Exp/Cntr=0.3,0.1

Type RM Length L Ch R = 1 ,25196   ,588,588,588
BEGIN DESCRIPTION:
ROBINSON CREEK 38.0
END DESCRIPTION:
XS GIS Cut Line= 3
      3781405.68      10223638.7       3780608.8     10223899.12
      3778655.68      10224451.2
#Sta/Elev= 30
  3782.4  275.56  4212.2  261.05  4267.8  259.31  4369.3  257.84  4385.3  256.49
  4422.6  255.78    4647  253.41  4725.7  250.21  4793.3  245.33  4866.4  243.78
  4891.9  244.25  4900.4  243.39  4905.6  244.43  4944.8   245.6  4978.7  245.32
  4985.5  245.12  4993.3  239.74  5019.2  239.74    5027   244.9  5037.4   244.9
  5046.7  243.32  5058.2  245.01  5182.9   246.8  5597.8  248.27  5871.9  252.92
  6378.7  260.43  6398.7  261.55  6558.9  263.67    6617  265.96  6650.4  266.04
#Mann= 9 ,-1 , 0
  3782.4     .11       0  4212.2     .17       0  4267.8     .11       0
  4422.6     .15       0  4978.7     .12       0  4985.5     .09       0
    5027     .12       0  5037.4     .15       0  5871.9     .11       0
Bank Sta=4985.5,5027
XS Rating Curve= 0 ,0
Exp/Cntr=0.3,0.1

Type RM Length L Ch R = 1 ,24608   ,497,497,497
BEGIN DESCRIPTION:
ROBINSON CREEK 37.0
END DESCRIPTION:
XS GIS Cut Line= 3
      3781202.52     10223222.04      3780436.93     10223378.28
      3778645.29     10224232.44
#Sta/Elev= 30
  3853.2  273.01  4107.3  264.86  4144.3  263.91  4215.4  262.24  4245.9  261.51
  4296.8  259.76  4347.4  261.01  4469.4   261.2  4550.5  259.51    4629  256.73
  4674.1  255.64  4861.2   245.3  4957.6  242.71  4980.3  243.52  4984.4  239.94
  5010.4  239.94  5020.1  244.48  5025.6  245.12  5132.1  243.27  5176.4  244.24
  5198.5  242.26  5287.2  244.16  5386.9  243.02  5445.3  243.85  5475.5  242.56
  5497.7  244.61  6213.4  258.19  6301.1  258.65  6443.4  260.17  6619.4  265.32
#Mann= 13 ,-1 , 0
  3853.2     .11       0  4107.3     .17       0  4144.3     .11       0
  4215.4     .17       0  4245.9     .11       0  4347.4     .17       0
  4550.5     .11       0    4629     .15       0  4980.3     .09       0
  5020.1     .12       0  5025.6     .15       0  6213.4     .17       0
  6301.1     .11       0
Bank Sta=4980.3,5020.1
XS Rating Curve= 0 ,0
Exp/Cntr=0.3,0.1

Type RM Length L Ch R = 1 ,24111   ,393,393,393
BEGIN DESCRIPTION:
ROBINSON CREEK 36.0
END DESCRIPTION:
XS GIS Cut Line= 3
      3780988.99       10222696.      3780223.39     10223003.28
      3778739.02     10223925.15
#Sta/Elev= 30
  3522.1   272.7    3536   272.2  3603.5  269.71  3651.9  270.43  3679.6  268.41
  3857.4  262.34  3932.8   256.7  4009.6  256.08  4087.6  252.48  4117.1  253.51
  4129.8  251.93  4159.1  250.46  4195.1  252.59  4230.5  252.41  4258.3  252.01
  4624.3  244.85  4654.7  243.26  4965.7  245.02  4989.3  243.25    4996  241.83
  5004.2  237.18  5030.3  237.18  5032.6  242.59  5038.5  244.71  5096.3  242.17
  5236.5  245.23  5373.9  245.31  5900.1  261.45  6004.4  262.24  6094.4  264.98
#Mann= 9 ,-1 , 0
  3522.1     .11       0    3536     .17       0  3679.6     .11       0
  4129.8     .15       0  4230.5     .17       0  4258.3     .15       0
  4965.7     .09       0  5038.5     .15       0  5900.1     .11       0
Bank Sta=4965.7,5038.5
XS Rating Curve= 0 ,0
Exp/Cntr=0.3,0.1

Type RM Length L Ch R = 1 ,23718   ,498,498,498
BEGIN DESCRIPTION:
ROBINSON CREEK 35.0
END DESCRIPTION:
XS GIS Cut Line= 3
      3781017.85     10222211.07      3779444.96     10223222.84
      3778667.84     10223611.08
#Sta/Elev= 30
  3129.8  280.27  3435.6  271.77  3653.1  265.74  3776.7  261.43  3831.2   259.2
  3924.5  254.38  4002.6  252.92    4048   250.3    4151  248.06  4178.1  245.72
  4250.8  243.99  4510.9  243.38  4547.3  242.18  4592.3  243.68  4765.2  242.75
  4780.4  241.66  4788.5   239.5  4815.1     240  4816.7  241.76  4822.6  242.89
  4843.8  243.97  4973.9  243.05  4983.1  243.11  4995.3   241.5  5010.4   242.8
  5228.5  242.04  5309.8  243.31    5511   251.6  5591.9  257.62  5868.7  268.49
#Mann= 11 ,-1 , 0
  3129.8     .11       0  3435.6     .17       0  3653.1     .11       0
  3776.7     .17       0  3831.2     .11       0  3924.5     .17       0
  4002.6     .15       0  4815.1     .15       0  4973.9     .12       0
  4983.1     .09       0  5010.4     .15       0
Bank Sta=4983.1,5010.4
XS Rating Curve= 0 ,0
Exp/Cntr=0.3,0.1