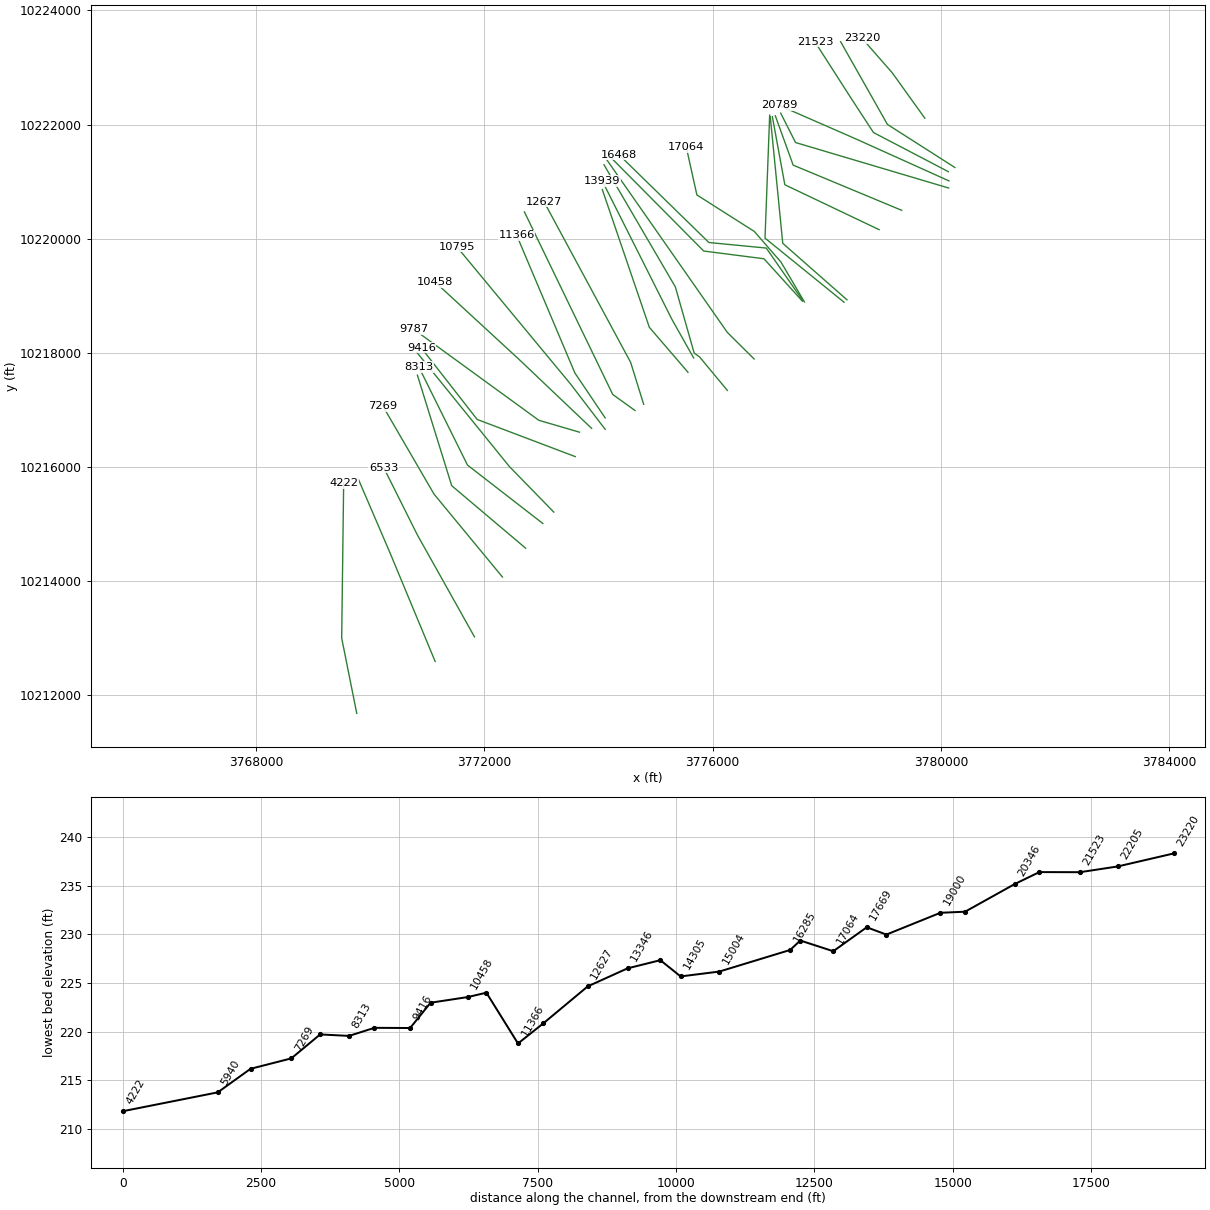
HEC-RAS study ROBINSON CREEK.prj: ROBINSON CREEK Base Level Engineering

--- ROBINSON CREEK.g01 (geometry) --- (continued)

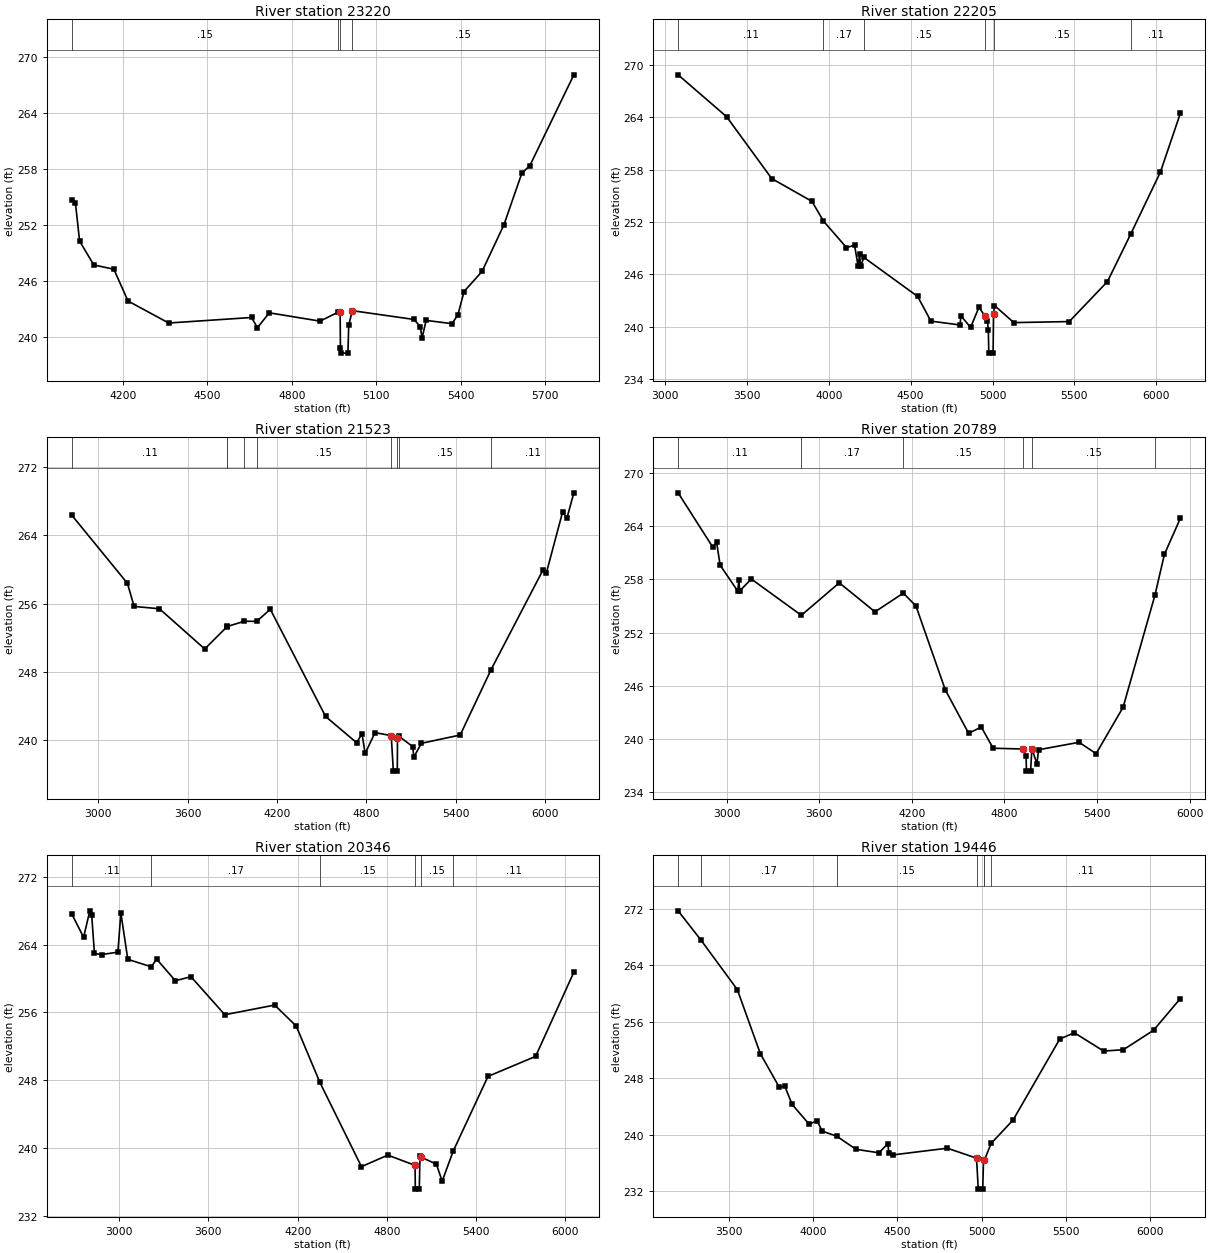
Type RM Length L Ch R = 1 ,23220   ,1015,1015,1015
BEGIN DESCRIPTION:
ROBINSON CREEK 34.0
END DESCRIPTION:
XS GIS Cut Line= 3
      3779717.83      10222111.1      3779145.75     10222908.27
      3778617.84     10223511.09
#Sta/Elev= 30
  4018.8   254.7  4032.3  254.33    4047  250.28  4097.4  247.73  4168.6  247.27
  4218.9  243.87  4363.4  241.52  4657.3  242.11  4678.2  241.02  4720.3  242.61
  4900.4  241.72  4965.5  242.69  4971.7  242.65  4972.9   238.8  4973.4   238.3
  4999.5   238.3  5002.2  241.28    5015  242.84  5234.2   241.9    5256  241.14
  5262.7  239.92  5276.9   241.8    5369  241.45  5389.9  242.41  5411.7  244.89
  5475.3  247.03  5553.1  252.02  5616.7  257.54  5645.2  258.35  5801.3  268.06
#Mann= 4 ,-1 , 0
  4018.8     .15       0  4965.5     .12       0  4971.7     .09       0
    5015     .15       0
Bank Sta=4971.7,5015
XS Rating Curve= 0 ,0
Exp/Cntr=0.3,0.1

Type RM Length L Ch R = 1 ,22205   ,682,682,682
BEGIN DESCRIPTION:
ROBINSON CREEK 33.0
END DESCRIPTION:
XS GIS Cut Line= 3
      3780244.24     10221248.06      3779061.93     10222003.28
      3778242.69     10223451.26
#Sta/Elev= 30
  3080.2  268.88  3376.1  264.08  3651.9  256.98  3897.2  254.37  3967.9   252.1
  4108.3  249.07  4157.8  249.33  4179.5   246.9  4188.2  248.32  4194.2  246.95
    4215  247.93    4543  243.46  4623.8  240.63  4801.4  240.19  4807.1  241.24
  4866.3  239.91  4917.2  242.22  4952.9  241.24  4968.8  240.63  4974.6  239.57
  4977.3  236.96  5003.6  236.96  5006.3  241.46  5012.1  242.42  5130.4  240.46
  5468.7  240.58    5702  245.17  5844.4  250.63  6025.3  257.73  6146.8  264.45
#Mann= 6 ,-1 , 0
  3080.2     .11       0  3967.9     .17       0    4215     .15       0
  4952.9     .09       0  5006.3     .15       0  5844.4     .11       0
Bank Sta=4952.9,5006.3
XS Rating Curve= 0 ,0
Exp/Cntr=0.3,0.1

Type RM Length L Ch R = 1 ,21523   ,734,734,734
BEGIN DESCRIPTION:
ROBINSON CREEK 32.0
END DESCRIPTION:
XS GIS Cut Line= 4
      3780129.63     10221175.16      3778817.85     10221861.07
      3778435.75     10222446.06      3777791.96     10223449.85
#Sta/Elev= 30
    2821  266.37  3195.4  258.37  3240.5  255.66  3410.5  255.39  3714.5  250.68
  3865.6  253.31  3867.2  253.32  3980.9  253.93  4063.2  253.91  4154.6  255.33
    4526  242.77  4734.1   239.7  4770.3  240.75  4791.4  238.44  4857.8  240.88
  4966.5  240.53  4980.8  236.37  5007.3  236.37  5008.6  240.29  5017.8  240.46
  5111.7  239.23  5117.7     238  5169.2  239.63  5429.5   240.6  5636.6  248.25
  5986.6  259.97  6007.7  259.57  6116.7   266.7  6146.4  266.03  6192.5  268.97
#Mann= 9 ,-1 , 0
    2821     .11       0  3865.6     .17       0  3867.2     .11       0
  3980.9     .17       0  4063.2     .15       0  4966.5     .09       0
  5008.6     .12       0  5017.8     .15       0  5636.6     .11       0
Bank Sta=4966.5,5008.6
XS Rating Curve= 0 ,0
Exp/Cntr=0.3,0.1

Type RM Length L Ch R = 1 ,20789   ,443,443,443
BEGIN DESCRIPTION:
ROBINSON CREEK 31.0
END DESCRIPTION:
XS GIS Cut Line= 3
      3780140.01     10221013.72      3778499.43     10221753.28
      3777166.76     10222336.33
#Sta/Elev= 30
  2685.7  267.74  2911.7  261.58  2934.8  262.21  2957.9  259.59    3072  256.67
  3079.1  257.94  3084.6  256.68  3159.7  258.03  3484.1  253.94  3730.1   257.6
  3961.4  254.33  4145.2  256.44  4226.8  254.99  4417.4  245.52    4568  240.65
  4650.7  241.34  4727.1  238.96  4923.6  238.87  4940.6  238.09    4943  236.38
  4969.6  236.38  4978.2   238.9  5010.8  237.22  5021.8  238.79  5283.8  239.63
  5394.4  238.35    5569  243.57  5775.2  256.18  5837.2  260.83  5939.9  264.85
#Mann= 6 ,-1 , 0
  2685.7     .11       0  3484.1     .17       0  4145.2     .15       0
  4923.6     .09       0  4978.2     .15       0  5775.2     .11       0
Bank Sta=4923.6,4978.2
XS Rating Curve= 0 ,0
Exp/Cntr=0.3,0.1

Type RM Length L Ch R = 1 ,20346   ,900,900,900
BEGIN DESCRIPTION:
ROBINSON CREEK 30.0
END DESCRIPTION:
XS GIS Cut Line= 3
       3780134.8     10220888.71      3777452.55     10221685.57
      3777192.48     10222200.51
#Sta/Elev= 30
  2681.1  267.63  2761.4  264.85  2803.1  267.97  2815.5  267.52  2834.4  262.94
  2881.9  262.81    2992   263.1  3011.7  267.73  3058.4  262.25    3217  261.37
  3251.7  262.29  3378.1  259.73  3482.9   260.2  3710.7  255.72  4045.5  256.86
  4190.6  254.38  4349.4  247.74  4628.7  237.81    4806  239.17    4989  237.96
  4990.9  235.16  5017.5  235.16  5022.2  239.11  5027.4  238.94  5132.2  238.11
  5171.2   236.1  5245.8  239.66  5479.1  248.45  5799.1  250.81  6056.1  260.73
#Mann= 6 ,-1 , 0
  2681.1     .11       0    3217     .17       0  4349.4     .15       0
    4989     .09       0  5027.4     .15       0  5245.8     .11       0
Bank Sta=4989,5027.4
XS Rating Curve= 0 ,0
Exp/Cntr=0.3,0.1

Type RM Length L Ch R = 1 ,19446   ,446,446,446
BEGIN DESCRIPTION:
ROBINSON CREEK 29.0
END DESCRIPTION:
XS GIS Cut Line= 3
      3779311.93     10220498.08      3777410.89     10221289.74
      3777098.39     10222154.31
#Sta/Elev= 30
  3199.7  271.68  3333.4   267.6  3550.8  260.54  3687.4  251.47  3799.9  246.72
  3832.4  246.87    3876  244.29  3976.7   241.5  4024.4  241.98  4053.7  240.52
  4140.4   239.8  4254.9  237.94  4390.7  237.45  4443.7  238.73  4449.8  237.36
    4473  237.15  4796.5   238.1  4969.8  236.69  4979.8  232.31  5006.5  232.31
  5011.1  236.47  5016.9  236.45  5056.5  238.78  5186.5  242.09  5463.4  253.55
  5550.1  254.43  5723.4  251.84  5840.7  252.03  6019.4  254.78  6178.3  259.26
#Mann= 7 ,-1 , 0
  3199.7     .11       0  3333.4     .17       0  4140.4     .15       0
  4969.8     .09       0  5011.1     .12       0  5016.9     .15       0
  5056.5     .11       0
Bank Sta=4969.8,5011.1
XS Rating Curve= 0 ,0
Exp/Cntr=0.3,0.1

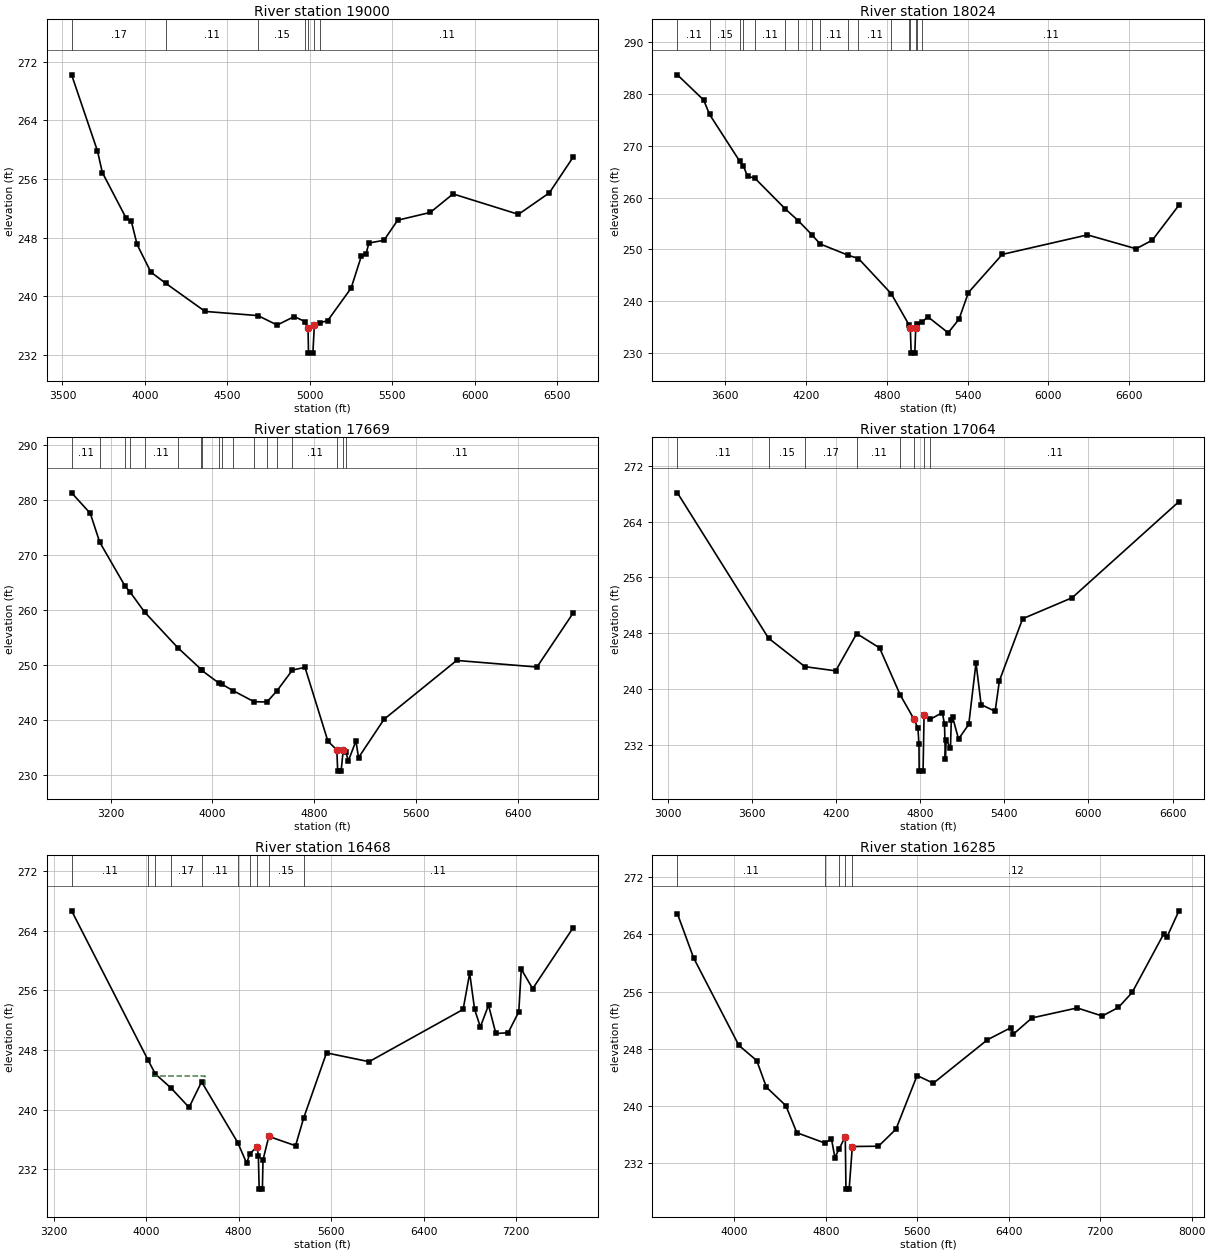
Type RM Length L Ch R = 1 ,19000   ,976,976,976
BEGIN DESCRIPTION:
ROBINSON CREEK 28.0
END DESCRIPTION:
XS GIS Cut Line= 3
      3778916.08     10220159.54      3777265.05     10220945.99
      3777046.55     10222137.36
#Sta/Elev= 30
  3555.6  270.24  3712.3  259.83  3741.9  256.88  3885.9  250.66  3916.6   250.3
  3952.4  247.05  4035.7  243.28  4126.3  241.74  4364.6   237.9  4684.9  237.33
  4801.5  236.04    4905   237.2  4971.5  236.49  4988.6  235.65  4991.3   232.2
    5018   232.2  5026.8  236.04    5062  236.36  5107.7  236.64  5249.5  241.08
    5312  245.48  5340.3  245.77  5357.4  247.25  5448.7  247.62  5531.9  250.37
  5729.6  251.43  5867.4  253.96  6263.9  251.17  6450.9   254.1  6595.6     259
#Mann= 7 ,-1 , 0
  3555.6     .17       0  4126.3     .11       0  4684.9     .15       0
  4971.5     .12       0  4988.6     .09       0  5026.8     .15       0
    5062     .11       0
Bank Sta=4988.6,5026.8
XS Rating Curve= 0 ,0
Exp/Cntr=0.3,0.1

Type RM Length L Ch R = 1 ,18024   ,355,355,355
BEGIN DESCRIPTION:
ROBINSON CREEK 27.0
END DESCRIPTION:
XS GIS Cut Line= 3
       3778353.6     10218930.37       3777228.6     10219919.95
      3777009.97      10222137.4
#Sta/Elev= 30
  3243.8  283.72  3439.3  278.84  3482.6  276.08  3707.9  266.99  3734.1  266.13
  3765.7  264.08  3817.2  263.81    4047  257.78  4142.6  255.52  4242.4  252.85
  4304.3  251.05  4514.6  248.85  4589.4  248.23  4833.4  241.42  4964.3  235.43
  4974.3  234.83    4981  229.96  5007.9  229.96  5014.5  234.76  5024.6   235.5
  5064.8  235.99  5103.2  237.01  5255.7  233.89  5336.1  236.51  5406.4  241.67
  5657.6  249.03  6290.7   252.8  6652.4  250.12    6773  251.79  6970.3  258.54
#Mann= 17 ,-1 , 0
  3243.8     .11       0  3482.6     .15       0  3707.9     .11       0
  3734.1     .15       0  3817.2     .11       0    4047     .17       0
  4142.6     .11       0  4242.4     .15       0  4304.3     .11       0
  4514.6     .15       0  4589.4     .11       0  4833.4     .15       0
  4964.3     .11       0  4974.3     .07       0  5014.5     .11       0
  5024.6     .15       0  5064.8     .11       0
Bank Sta=4974.3,5014.5
XS Rating Curve= 0 ,0
Exp/Cntr=0.3,0.1

Type RM Length L Ch R = 1 ,17669   ,605,605,605
BEGIN DESCRIPTION:
ROBINSON CREEK 26.0
END DESCRIPTION:
XS GIS Cut Line= 3
      3778301.48     10218888.73      3776917.85     10220011.07
      3776999.43     10222164.73
#Sta/Elev= 30
  2894.3  281.37  3040.6  277.64  3115.2  272.37  3313.6   264.4  3353.2  263.31
  3466.6  259.68  3727.5  253.18  3913.4  249.18    3917  249.03  4048.2  246.77
  4073.5  246.53  4161.1  245.37  4325.7  243.35  4426.9  243.29  4504.6  245.28
    4627   249.1  4725.9  249.61  4906.1  236.15  4976.1  234.58  4982.7  230.71
  5009.6  230.71  5026.1   234.5  5046.2  234.25  5066.2  232.57  5126.2  236.21
  5146.2  233.16  5346.4  240.14  5916.8  250.86  6547.2  249.66  6831.1  259.49
#Mann= 18 ,-1 , 0
  2894.3     .11       0  3115.2     .15       0  3313.6     .11       0
  3353.2     .15       0  3466.6     .11       0  3727.5     .17       0
  3913.4     .15       0    3917     .17       0  4048.2     .15       0
  4073.5     .17       0  4161.1     .15       0  4325.7     .17       0
  4426.9     .11       0  4504.6     .17       0    4627     .11       0
  4976.1     .06       0  5026.1     .09       0  5046.2     .11       0
Bank Sta=4976.1,5026.1
XS Rating Curve= 0 ,0
Exp/Cntr=0.3,0.1

Type RM Length L Ch R = 1 ,17064   ,596,596,596
BEGIN DESCRIPTION:
ROBINSON CREEK 25.0
END DESCRIPTION:
XS GIS Cut Line= 5
      3777607.92     10218892.49      3777198.21     10219590.38
      3776729.46     10220128.57      3775724.26     10220767.46
      3775538.01     10221607.74
#Sta/Elev= 30
  3069.9  268.13  3719.4   247.3  3978.7  243.22  4198.4  242.62  4348.1  247.96
  4510.8  245.91  4658.4  239.16  4755.4  235.73  4784.4   234.4  4791.8  232.09
  4793.1  228.25  4820.9  228.25  4828.2  236.36    4871  235.67  4958.6  236.63
  4973.9  234.95  4979.8  230.02  4985.8  232.78  5016.2   231.5  5022.1  235.54
  5031.4     236  5073.8  232.85  5146.6  234.95  5198.3  243.77  5234.6  237.79
  5334.6  236.82    5365   241.2  5530.8  250.09  5883.9   253.1  6644.6  266.87
#Mann= 8 ,-1 , 0
  3069.9     .11       0  3719.4     .15       0  3978.7     .17       0
  4348.1     .11       0  4658.4     .17       0  4755.4     .07       0
  4828.2     .15       0    4871     .11       0
#XS Ineff= 1 ,-1
  5198.3    5450  243.77
Permanent Ineff=
       F
Bank Sta=4755.4,4828.2
XS Rating Curve= 0 ,0
Exp/Cntr=0.3,0.1

Type RM Length L Ch R = 1 ,16468   ,183,183,183
BEGIN DESCRIPTION:
ROBINSON CREEK 23.0
END DESCRIPTION:
XS GIS Cut Line= 4
      3777578.83     10218917.67      3776940.07     10219836.78
      3775934.33     10219934.13      3774357.04     10221474.95
#Sta/Elev= 30
  3356.5  266.67    4016  246.69  4079.3  244.81  4215.4  242.91  4371.6  240.31
  4479.8  243.74  4792.7  235.58  4869.8  232.81  4896.7  234.12  4960.2  235.01
  4970.3  233.82  4977.5  229.35  5005.3  229.35  5010.5  233.25  5060.7  236.42
  5291.8  235.17  5362.1  238.89  5559.4  247.62  5927.1  246.44  6740.2  253.45
  6796.8  258.31  6839.2  253.47  6888.8   251.1  6959.6  254.01  7023.1  250.22
  7129.3  250.32  7221.2  253.13  7242.5  258.85  7341.3  256.23  7691.2  264.41
#Mann= 10 ,-1 , 0
  3356.5     .11       0    4016     .15       0  4079.3     .11       0
  4215.4     .17       0  4479.8     .11       0  4792.7     .17       0
  4896.7     .15       0  4960.2     .09       0  5060.7     .15       0
  5362.1     .11       0
#XS Ineff= 1 ,-1
    4050  4508.1  244.47
Permanent Ineff=
       F
Bank Sta=4960.2,5060.7
XS Rating Curve= 0 ,0
Exp/Cntr=0.3,0.1

Type RM Length L Ch R = 1 ,16285   ,1281,1281,1281
BEGIN DESCRIPTION:
ROBINSON CREEK 24.0
END DESCRIPTION:
XS GIS Cut Line= 4
       3777573.2     10218906.36       3776899.6     10219649.41
      3775844.05     10219784.82      3774209.52      10221431.5
#Sta/Elev= 30
  3501.6  266.91  3642.9  260.74  4039.6  248.48  4195.7  246.36  4280.2  242.64
  4450.5  240.05  4546.6  236.27  4793.6  234.81  4849.1  235.44  4879.3   232.8
  4914.8  233.95  4970.1  235.73  4976.3  228.38  5004.1  228.38    5032  234.34
  5260.8  234.38  5413.7  236.77  5598.7  244.27  5740.2  243.19  6213.9  249.27
    6419  250.96  6440.2  250.05  6602.9  252.32  6998.8  253.72    7218  252.59
  7359.4  253.79  7479.7  255.88  7755.4  264.06  7783.7  263.62  7888.9   267.3
#Mann= 5 ,-1 , 0
  3501.6     .11       0  4793.6     .15       0  4914.8     .12       0
  4970.1     .08       0    5032     .12       0
Bank Sta=4970.1,5032
XS Rating Curve= 0 ,0
Exp/Cntr=0.3,0.1

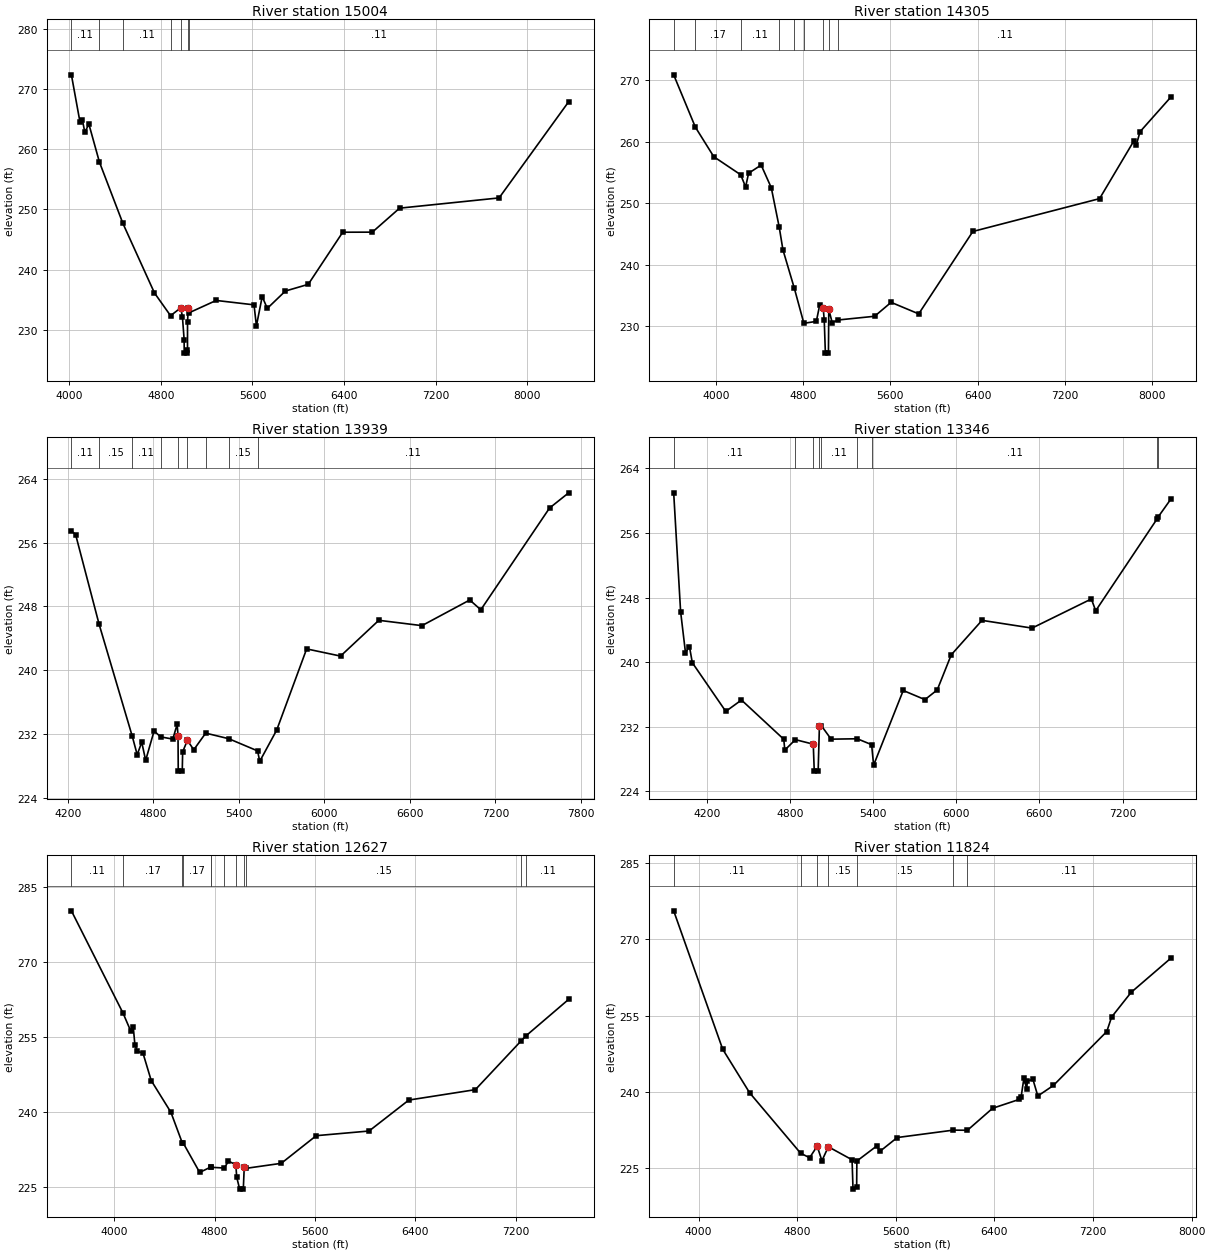
Type RM Length L Ch R = 1 ,15004   ,699,699,699
BEGIN DESCRIPTION:
ROBINSON CREEK 22.0
END DESCRIPTION:
XS GIS Cut Line= 3
      3776726.89     10217894.17      3776258.11     10218358.61
      3774148.74     10221379.43
#Sta/Elev= 30
  4018.1  272.33    4093   264.5  4114.3  264.81  4135.4   262.8  4170.8  264.15
  4262.8  257.86  4468.2  247.67  4743.8  236.14  4884.4  232.37  4973.7  233.68
  4988.1  232.16  5002.9  228.42  5003.7  226.16  5031.8  226.16  5032.3  226.66
  5032.6  231.25  5038.7  233.65  5047.8  232.87  5282.9   234.9  5613.5  234.17
  5634.4  230.68    5685  235.54  5729.5  233.58  5887.4  236.46  6087.1  237.57
  6388.5  246.22  6647.1  246.23  6885.3  250.21  7754.6  251.91  8362.4  267.87
#Mann= 7 ,-1 , 0
  4018.1     .11       0  4262.8     .15       0  4468.2     .11       0
  4884.4     .15       0  4973.7     .09       0  5038.7     .15       0
  5047.8     .11       0
Bank Sta=4973.7,5038.7
XS Rating Curve= 0 ,0
Exp/Cntr=0.3,0.1

Type RM Length L Ch R = 1 ,14305   ,366,366,366
BEGIN DESCRIPTION:
ROBINSON CREEK 21.0
END DESCRIPTION:
XS GIS Cut Line= 5
      3776258.09     10217343.01        3775772.     10217928.92
      3775676.51     10217998.36      3775346.65     10219157.22
      3774096.94     10221296.49
#Sta/Elev= 30
  3612.3  270.82  3811.4  262.32  3980.4  257.53  4227.2   254.6  4272.1  252.62
  4299.4  254.85  4414.7  256.18  4507.6   252.5  4580.4  246.11  4614.3  242.44
  4719.3  236.17  4806.5   230.5  4920.8  230.81    4952  233.47  4984.1  232.96
  4993.5  230.99  5003.9  225.66    5032  225.66  5035.1  232.75  5066.3  230.62
  5122.1  231.04  5455.5  231.64    5607   233.9    5860  232.03  6356.8   245.4
  7519.3  250.73    7832  260.04  7855.1  259.36  7890.2  261.58  8174.1  267.23
#Mann= 9 ,-1 , 0
  3612.3     .11       0  3811.4     .17       0  4227.2     .11       0
  4580.4     .15       0  4719.3     .11       0  4806.5     .15       0
  4984.1     .09       0  5035.1     .15       0  5122.1     .11       0
Bank Sta=4984.1,5035.1
XS Rating Curve= 0 ,0
Exp/Cntr=0.3,0.1

Type RM Length L Ch R = 1 ,13939   ,593,593,593
BEGIN DESCRIPTION:
ROBINSON CREEK 20.0
END DESCRIPTION:
XS GIS Cut Line= 3
      3775667.86     10217911.05      3775287.39     10218586.81
      3774067.87     10221011.04
#Sta/Elev= 30
  4224.5  257.48  4254.2  257.01  4419.1  245.75  4651.1  231.73  4686.2  229.39
    4718  230.96  4745.5  228.68  4804.7  232.37  4850.8  231.63    4936  231.35
  4966.6  233.21 4972.58  231.79  4974.2  227.33  5002.3  227.33  5005.1  229.75
  5038.4  231.19  5083.1  230.01  5166.8   232.1  5328.4   231.4  5530.9  229.87
  5545.9  228.56  5665.2  232.49  5875.1  242.67    6113  241.77  6381.6  246.26
  6684.2  245.59  7019.7  248.81  7097.1  247.58  7579.4  260.35  7713.7  262.26
#Mann= 9 ,-1 , 0
  4224.5     .11       0  4419.1     .15       0  4651.1     .11       0
  4850.8     .15       0 4972.58     .09       0  5038.4     .15       0
  5166.8     .11       0  5328.4     .15       0  5530.9     .11       0
Bank Sta=4972.58,5038.4
XS Rating Curve= 0 ,0
Exp/Cntr=0.3,0.1

Type RM Length L Ch R = 1 ,13346   ,719,719,719
BEGIN DESCRIPTION:
ROBINSON CREEK 19.0
END DESCRIPTION:
XS GIS Cut Line= 3
      3775567.88     10217661.04      3774891.47     10218448.66
      3774067.86     10220861.04
#Sta/Elev= 30
  3961.8  260.97  4011.8  246.24  4046.9  241.16  4075.4  241.93  4096.3  239.92
  4337.7  233.89  4450.7   235.3  4755.8  230.44  4763.5   229.1  4839.7  230.39
  4968.7  229.83  4975.9  226.49    5004  226.49  5013.1  232.07  5027.8   232.1
  5097.6  230.45  5285.9   230.5  5389.7  229.77  5404.1  227.23  5617.7  236.48
  5774.3  235.35    5863  236.55  5964.1   240.9    6186  245.17  6546.9  244.21
  6974.9  247.82  7006.2  246.36  7450.6  257.78  7458.4  258.02  7549.1  260.21
#Mann= 9 ,-1 , 0
  3961.8     .11       0  4839.7     .15       0  4968.7     .09       0
  5013.1     .15       0  5027.8     .11       0  5285.9     .15       0
  5389.7     .11       0  7450.6     .17       0  7458.4     .11       0
Bank Sta=4968.7,5013.1
XS Rating Curve= 0 ,0
Exp/Cntr=0.3,0.1

Type RM Length L Ch R = 1 ,12627   ,803,803,803
BEGIN DESCRIPTION:
ROBINSON CREEK 18.0
END DESCRIPTION:
XS GIS Cut Line= 3
      3774791.95     10217099.96      3774563.75     10217834.93
      3773047.39     10220646.39
#Sta/Elev= 30
  3658.8  280.29  4070.6  259.82  4132.1  256.23  4152.1  257.01  4164.7  253.54
  4183.5  252.24  4229.8   251.8    4295  246.35  4451.9  240.01  4543.1  233.85
  4548.9  233.91  4681.4  227.98  4768.1  229.04  4769.2  229.01  4877.5  228.86
  4910.8  230.23  4969.4  229.54  4976.5  227.03  5000.1  224.64  5029.1  224.64
  5036.5     229  5048.9  228.79  5331.7   229.8  5610.6  235.33  6031.5  236.26
  6348.5  242.45  6878.9  244.53  7245.7  254.34  7284.2  255.33  7622.7  262.59
#Mann= 12 ,-1 , 0
  3658.8     .11       0  4070.6     .17       0  4543.1     .11       0
  4548.9     .17       0  4768.1     .15       0  4769.2     .17       0
  4877.5     .15       0  4969.4     .09       0  5036.5     .12       0
  5048.9     .15       0  7245.7     .17       0  7284.2     .11       0
Bank Sta=4969.4,5036.5
XS Rating Curve= 0 ,0
Exp/Cntr=0.3,0.1

Type RM Length L Ch R = 1 ,11824   ,458,458,458
BEGIN DESCRIPTION:
ROBINSON CREEK 17.0
END DESCRIPTION:
XS GIS Cut Line= 3
       3774640.9     10216990.56       3774250.3      10217271.8
      3772703.43     10220469.71
#Sta/Elev= 30
  3798.4  275.64  4195.9  248.39  4414.7   239.8  4828.1  227.91    4901  227.02
  4962.4   229.3    5001  226.43  5052.8  229.18  5245.3  226.62  5253.1  220.84
  5282.6  221.34  5284.3  226.37    5448  229.38  5470.5  228.26  5611.9     231
  6067.5  232.46  6181.3  232.43  6385.3  236.76  6600.6   238.5  6616.8  239.02
  6639.4   242.7  6661.9  240.56  6667.5  242.15  6712.7  242.43  6752.3  239.18
  6878.3  241.25  7311.5  251.87  7350.8  254.73  7508.9  259.58  7832.1  266.33
#Mann= 7 ,-1 , 0
  3798.4     .11       0  4828.1     .15       0  4962.4     .09       0
  5052.8     .15       0  5282.6     .15       0  6067.5     .17       0
  6181.3     .11       0
Bank Sta=4962.4,5052.8
XS Rating Curve= 0 ,0
Exp/Cntr=0.3,0.1

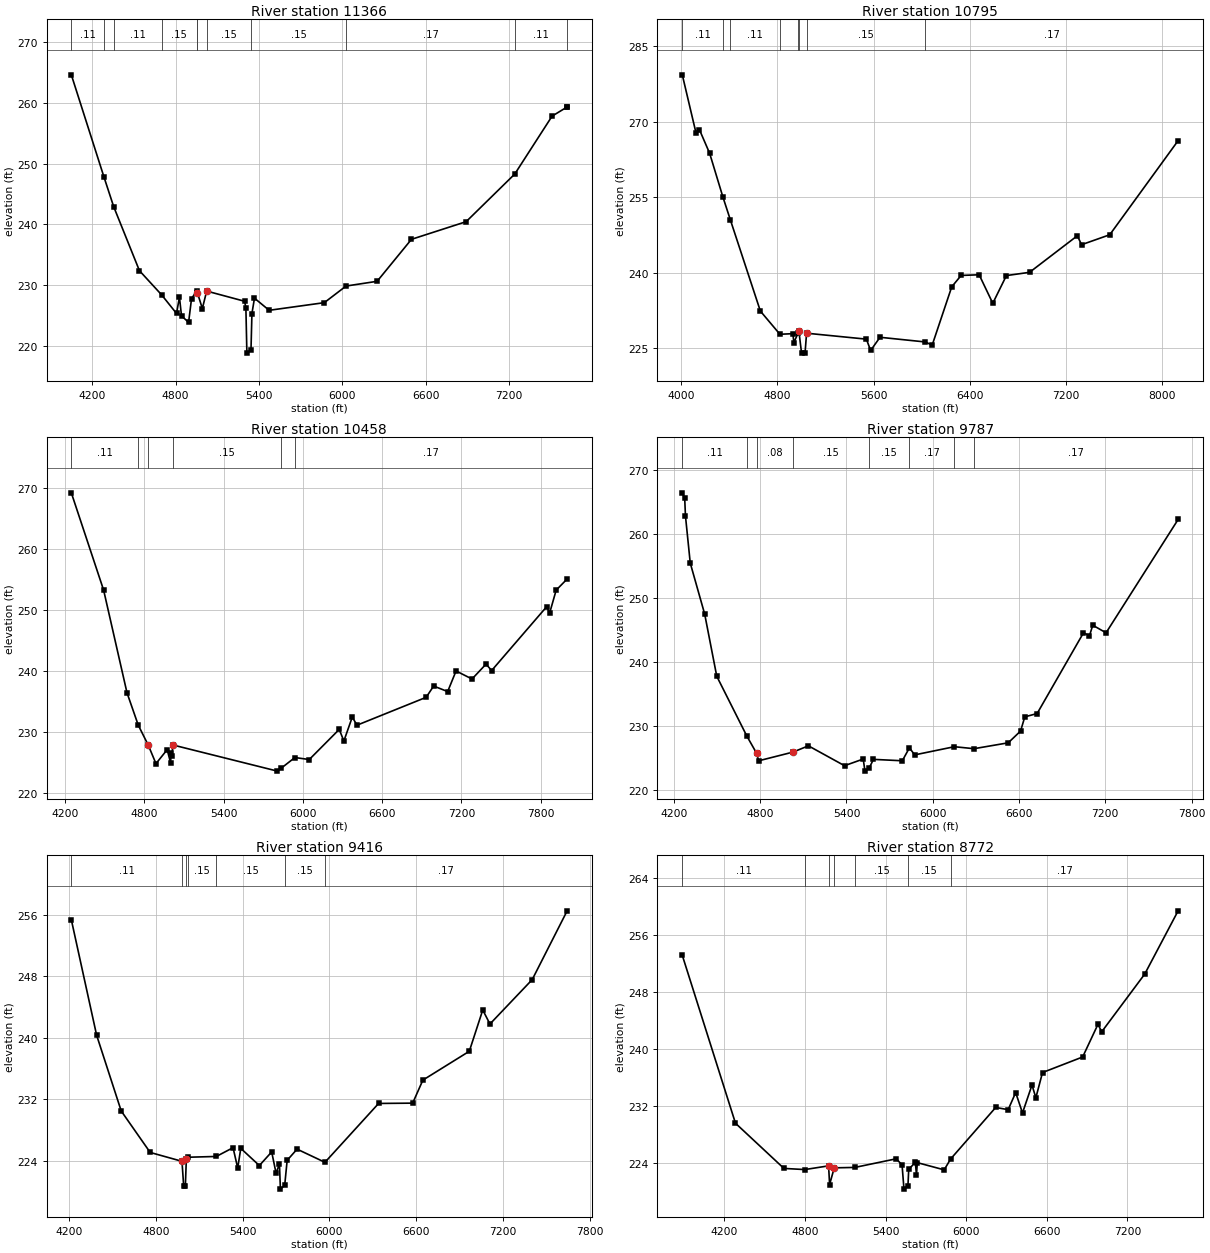
Type RM Length L Ch R = 1 ,11366   ,571,571,571
BEGIN DESCRIPTION:
ROBINSON CREEK 16.0
END DESCRIPTION:
XS GIS Cut Line= 3
      3774117.83     10216861.11      3773586.79     10217649.18
      3772567.85     10220061.08
#Sta/Elev= 30
  4049.7  264.65  4284.1  247.84  4354.3  242.93  4539.9  232.36  4699.8  228.37
  4806.8  225.31  4827.8     228  4842.7   224.9  4893.7  223.85  4914.7  227.73
  4950.7  229.02  4956.7  228.74  4992.7  226.12  5023.8     229  5296.7  227.32
    5306  226.23  5313.2  218.77  5342.7  219.27  5349.5   225.3  5367.8  227.83
  5473.5  225.83  5870.5  227.09    6027  229.83  6250.5  230.61  6497.6  237.53
  6891.2  240.44  7241.4   248.3  7509.7  257.84  7618.1  259.35  7618.3  259.35
#Mann= 11 ,-1 , 0
  4049.7     .11       0  4284.1     .17       0  4354.3     .11       0
  4699.8     .15       0  4950.7     .12       0  4956.7     .09       0
  5023.8     .15       0  5342.7     .15       0    6027     .17       0
  7241.4     .11       0  7618.1     .17       0
Bank Sta=4956.7,5023.8
XS Rating Curve= 0 ,0
Exp/Cntr=0.3,0.1

Type RM Length L Ch R = 1 ,10795   ,337,337,337
BEGIN DESCRIPTION:
ROBINSON CREEK 15.0
END DESCRIPTION:
XS GIS Cut Line= 3
      3774117.83      10216661.1      3773516.47     10217448.66
      3771517.83      10219861.1
#Sta/Elev= 30
  4009.1  279.33  4122.4  267.85  4151.4  268.44  4236.7  263.72    4346   255.1
  4408.9  250.49  4658.5  232.35    4821  227.74  4928.7  227.86  4936.9  226.09
  4972.3  227.97  4978.6  228.42    5001  223.99    5030  223.99  5042.8  227.95
  5540.3  226.77  5575.5  224.52  5653.6  227.14  6030.6  226.21  6087.3  225.57
  6250.1  237.18  6328.3  239.44  6478.1  239.57  6591.4   233.9  6704.7  239.41
  6897.5  240.06  7294.7  247.33  7329.8  245.55  7564.3  247.53  8132.8  266.24
#Mann= 8 ,-1 , 0
  4009.1     .11       0    4346     .17       0  4408.9     .11       0
    4821     .15       0  4972.3     .12       0  4978.6     .09       0
  5042.8     .15       0  6030.6     .17       0
Bank Sta=4978.6,5042.8
XS Rating Curve= 0 ,0
Exp/Cntr=0.3,0.1

Type RM Length L Ch R = 1 ,10458   ,671,671,671
BEGIN DESCRIPTION:
ROBINSON CREEK 14.0
END DESCRIPTION:
XS GIS Cut Line= 3
       3773880.5     10216678.06      3772610.89     10217884.52
      3771139.58     10219240.55
#Sta/Elev= 30
  4248.4  269.16  4492.9   253.2  4669.6  236.39  4754.6  231.09 4830.86  227.78
  4888.9  224.77  4973.8  227.06  5000.2  224.85  5002.1  226.55  5009.4  226.08
  5016.3  227.83  5808.3  223.54  5837.8  224.04  5940.2  225.77    6049  225.44
  6275.8  230.38  6310.9  228.48  6374.5   232.4  6410.2  231.07  6933.6  235.64
  6990.3  237.49  7096.4  236.58  7159.9  239.96  7280.7  238.64  7386.7  241.08
  7429.2  240.03  7846.6  250.52  7867.6  249.42  7917.5  253.21  8000.7  255.04
#Mann= 6 ,-1 , 0
  4248.4     .11       0  4754.6     .15       0 4830.86     .09       0
  5016.3     .15       0  5837.8     .15       0  5940.2     .17       0
Bank Sta=4830.86,5016.3
XS Rating Curve= 0 ,0
Exp/Cntr=0.3,0.1

Type RM Length L Ch R = 1 ,9787    ,371,371,371
BEGIN DESCRIPTION:
ROBINSON CREEK 13.0
END DESCRIPTION:
XS GIS Cut Line= 3
      3773667.89     10216611.06      3772956.25     10216819.35
      3770767.89     10218411.05
#Sta/Elev= 30
  4258.5   266.5  4275.3  265.66  4280.5  262.89  4313.9  255.51  4414.2  247.53
  4498.2   237.8  4707.7  228.43  4774.5  225.78  4789.9  224.58  5028.7  225.94
  5135.3  226.92  5386.5  223.81  5516.3  224.85  5528.8  222.96  5558.4  223.46
  5587.4   224.8  5788.3  224.58  5837.8  226.61  5874.1   225.5  6150.1  226.78
  6286.8  226.47  6524.8  227.39  6610.6  229.23    6640  231.45  6725.7  231.97
    7048   244.6  7089.7  244.14  7112.5  245.79  7204.9   244.6    7706  262.33
#Mann= 8 ,-1 , 0
  4258.5     .11       0  4707.7     .15       0  4774.5     .08       0
  5028.7     .15       0  5558.4     .15       0  5837.8     .17       0
  6150.1     .11       0  6286.8     .17       0
Bank Sta=4774.5,5028.7
XS Rating Curve= 0 ,0
Exp/Cntr=0.3,0.1

Type RM Length L Ch R = 1 ,9416    ,644,644,644
BEGIN DESCRIPTION:
ROBINSON CREEK 12.0
END DESCRIPTION:
XS GIS Cut Line= 3
      3773594.08     10216183.25       3771875.3      10216834.3
      3770896.14      10218089.5
#Sta/Elev= 30
  4214.3  255.32  4389.2  240.34  4559.4   230.5  4759.8  225.12  4979.7  223.97
  4991.4  220.77  5003.1  220.77  5009.8  224.23    5023   224.5  5217.2   224.6
  5333.1  225.74  5365.2  223.09  5386.5  225.65  5514.9  223.42  5600.3  225.19
  5630.5  222.43  5653.9  223.63  5660.7  220.36  5690.3  220.86  5707.3   224.1
  5775.9  225.55  5968.7  223.84  6339.9  231.48  6575.5  231.52  6646.1  234.51
  6967.2  238.25  7060.3  243.61  7110.1  241.79  7402.3  247.55  7644.2  256.48
#Mann= 7 ,-1 , 0
  4214.3     .11       0  4979.7     .07       0  5009.8     .11       0
    5023     .15       0  5217.2     .15       0  5690.3     .15       0
  5968.7     .17       0
Bank Sta=4979.7,5009.8
XS Rating Curve= 0 ,0
Exp/Cntr=0.3,0.1

Type RM Length L Ch R = 1 ,8772    ,459,459,459
BEGIN DESCRIPTION:
ROBINSON CREEK 11.0
END DESCRIPTION:
XS GIS Cut Line= 3
      3773217.82     10215211.11      3772440.29     10216008.89
      3770817.87     10218011.05
#Sta/Elev= 30
    3886  253.13  4281.9  229.61  4642.6  223.28  4798.2  223.12  4975.1  223.64
  4982.6  221.02    5017  223.36  5170.7  223.42    5479  224.63  5522.1  223.76
  5536.2  220.38  5565.9  220.88  5571.7  223.18  5621.2  224.11  5629.2  222.37
  5635.6  224.09  5835.4  223.08  5883.9  224.61  6219.1  231.82  6311.8  231.51
  6367.8   233.9  6418.6  231.05  6489.2  234.96    6518  233.18  6567.5  236.71
  6866.4  238.89    6980  243.45  7008.7  242.43  7328.4   250.5    7577  259.36
#Mann= 7 ,-1 , 0
    3886     .11       0  4798.2     .15       0  4975.1     .08       0
    5017     .15       0  5170.7     .15       0  5565.9     .15       0
  5883.9     .17       0
Bank Sta=4975.1,5017
XS Rating Curve= 0 ,0
Exp/Cntr=0.3,0.1

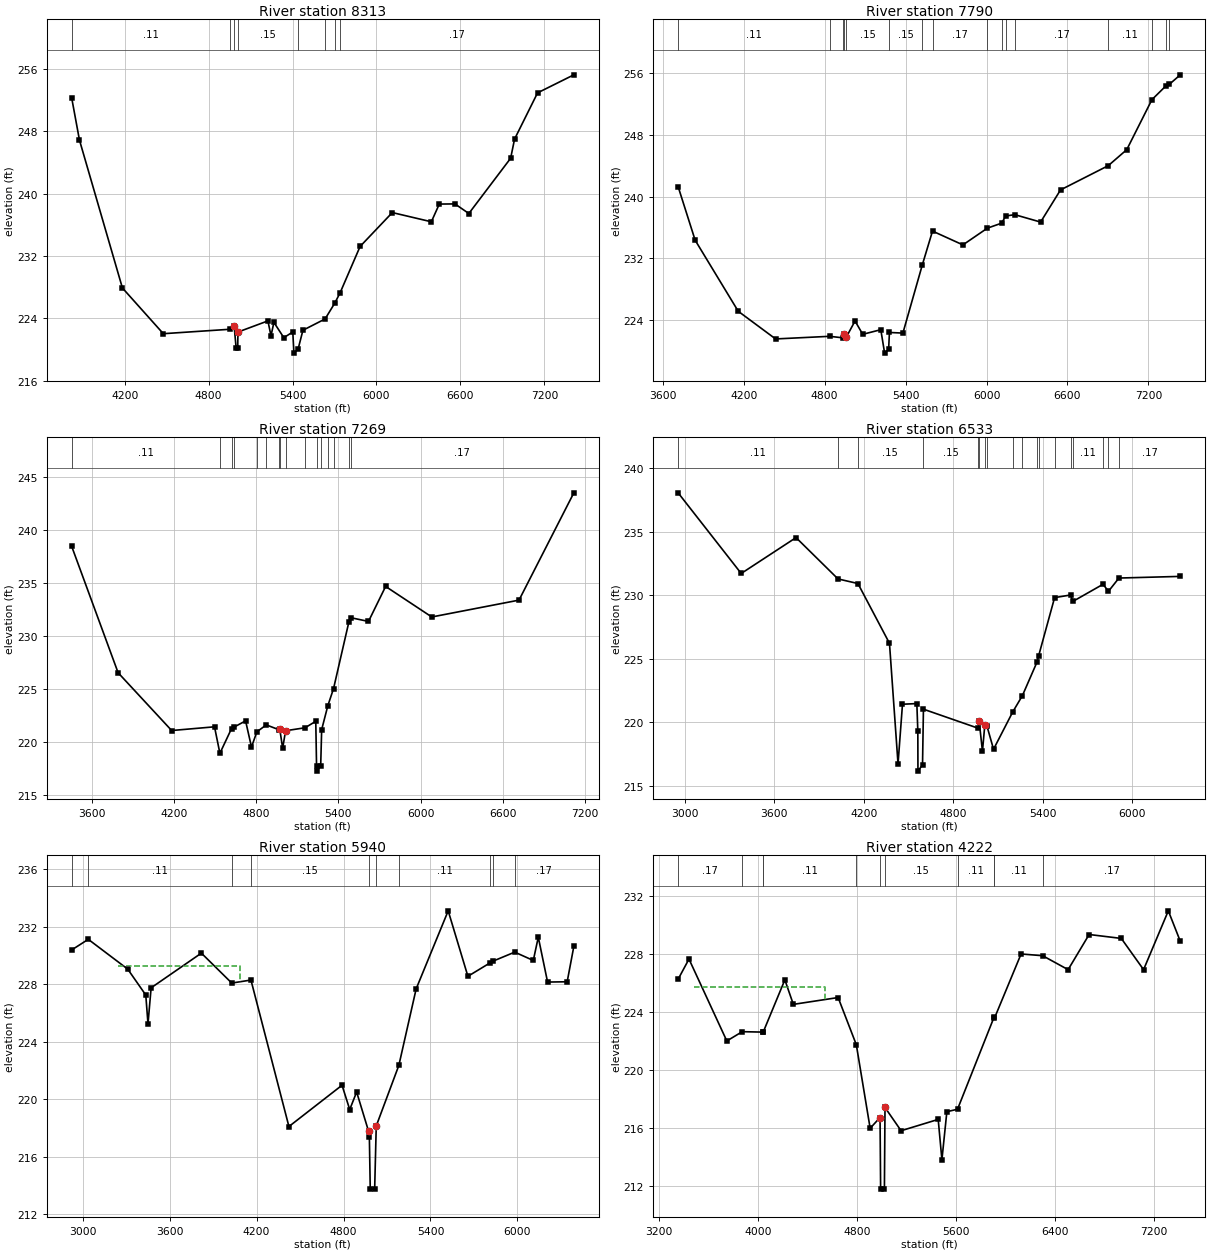
Type RM Length L Ch R = 1 ,8313    ,523,523,523
BEGIN DESCRIPTION:
ROBINSON CREEK 10.0
END DESCRIPTION:
XS GIS Cut Line= 3
      3773026.34     10215011.38      3771705.91     10216034.83
      3770853.38     10217753.25
#Sta/Elev= 30
  3821.4  252.28  3877.2  246.85  4184.1   227.9  4476.5  222.04  4954.8  222.61
  4982.6  223.04  4996.6  220.26  5008.3  220.26  5009.7  222.25  5223.9  223.68
    5246  221.78  5266.8  223.49  5337.7  221.53  5401.7  222.26  5409.8  219.55
  5439.5  220.05  5474.2  222.48  5632.7  223.93  5701.9  225.96  5740.4   227.3
  5882.8  233.22    6113  237.56    6392  236.38  6448.7  238.65  6560.8  238.67
  6659.9  237.44  6958.6  244.52  6986.6  246.97  7151.1   252.9  7410.3  255.21
#Mann= 8 ,-1 , 0
  3821.4     .11       0  4954.8     .15       0  4982.6     .09       0
  5009.7     .15       0  5439.5     .15       0  5632.7     .17       0
  5701.9     .11       0  5740.4     .17       0
Bank Sta=4982.6,5009.7
XS Rating Curve= 0 ,0
Exp/Cntr=0.3,0.1

Type RM Length L Ch R = 1 ,7790    ,521,521,521
BEGIN DESCRIPTION:
ROBINSON CREEK 9.0
END DESCRIPTION:
XS GIS Cut Line= 3
      3772724.22     10214579.12      3771429.28     10215673.97
      3770828.42     10217610.34
#Sta/Elev= 30
  3713.5   241.3  3839.7  234.35  4159.2  225.13  4436.1  221.54  4836.2  221.88
  4932.8  221.69  4939.7  222.16  4961.3   221.8  5025.1  223.87  5082.2  222.14
  5216.2  222.74  5244.5   219.7  5274.2   220.2  5280.2  222.38    5380   222.3
  5524.4  231.17  5599.5  235.53    5825  233.74  6006.2  235.91    6112  236.56
  6142.5  237.49  6209.6  237.66  6400.9   236.7  6548.6  240.87  6902.8  244.02
  7039.6  246.09  7226.3  252.58  7327.9  254.33  7354.7  254.56  7436.7   255.8
#Mann= 16 ,-1 , 0
  3713.5     .11       0  4836.2     .15       0  4932.8     .12       0
  4939.7     .09       0  4961.3     .15       0  5274.2     .15       0
  5524.4     .11       0  5599.5     .17       0  6006.2     .11       0
    6112     .17       0  6142.5     .11       0  6209.6     .17       0
  6902.8     .11       0  7226.3     .17       0  7327.9     .11       0
  7354.7     .17       0
Bank Sta=4939.7,4961.3
XS Rating Curve= 0 ,0
Exp/Cntr=0.3,0.1

Type RM Length L Ch R = 1 ,7269    ,736,736,736
BEGIN DESCRIPTION:
ROBINSON CREEK 8.0
END DESCRIPTION:
XS GIS Cut Line= 3
      3772317.99     10214073.91      3771120.19     10215525.45
       3770224.5     10217066.52
#Sta/Elev= 30
  3454.3  238.45  3793.3  226.52  4184.1  221.07  4496.8  221.42    4536  218.92
  4621.2  221.26    4636  221.37  4723.5  221.98  4766.5  219.51  4805.9  220.95
  4874.7   221.6  4965.9  221.15  4972.4  221.24    4994   219.4  5015.4  221.05
  5157.4  221.33  5235.6  221.94  5241.3  217.74  5241.8  217.24  5271.5  217.74
  5278.6  221.15  5323.6  223.41  5365.4  225.03  5476.6  231.28  5491.9  231.71
  5620.3  231.36  5745.3  234.66  6082.2  231.78  6718.7  233.37  7118.7  243.49
#Mann= 16 ,-1 , 0
  3454.3     .11       0    4536     .15       0  4621.2     .11       0
    4636     .15       0  4805.9     .11       0  4874.7     .15       0
  4965.9     .12       0  4972.4     .09       0  5015.4     .15       0
  5157.4     .15       0  5241.3     .09       0  5271.5     .15       0
  5323.6     .11       0  5365.4     .17       0  5476.6     .11       0
  5491.9     .17       0
Bank Sta=4972.4,5015.4
XS Rating Curve= 0 ,0
Exp/Cntr=0.3,0.1

Type RM Length L Ch R = 1 ,6533    ,593,593,593
BEGIN DESCRIPTION:
ROBINSON CREEK 7.0
END DESCRIPTION:
XS GIS Cut Line= 3
      3771828.41      10213025.3       3770829.1     10214809.17
      3770238.17     10215990.51
#Sta/Elev= 30
  2955.3  238.05  3378.1  231.71  3745.6  234.53  4026.9  231.28  4160.2  230.92
  4371.8  226.22  4429.1  216.74    4459  221.43  4555.2  221.48  4561.8  219.31
  4562.6  216.17  4593.3  216.67  4599.4  221.04    4967  219.54  4972.7  220.12
  4994.9  217.73  5010.8  219.81  5024.5  219.74  5069.2  217.89  5196.7   220.8
  5262.8  222.11  5361.5  224.77  5370.6   225.2  5478.4  229.81  5586.2  230.02
  5600.5  229.51    5803  230.86  5839.5  230.31  5909.6  231.35  6320.9  231.48
#Mann= 18 ,-1 , 0
  2955.3     .11       0  4026.9     .17       0  4160.2     .15       0
  4593.3     .15       0    4967     .12       0  4972.7     .09       0
  5010.8     .12       0  5024.5     .15       0  5196.7     .11       0
  5262.8     .17       0  5361.5     .11       0  5370.6     .17       0
  5478.4     .11       0  5586.2     .17       0  5600.5     .11       0
    5803     .17       0  5839.5     .11       0  5909.6     .17       0
Bank Sta=4972.7,5010.8
XS Rating Curve= 0 ,0
Exp/Cntr=0.3,0.1

Type RM Length L Ch R = 1 ,5940    ,1718,1718,1718
BEGIN DESCRIPTION:
ROBINSON CREEK 6.0
END DESCRIPTION:
XS GIS Cut Line= 3
      3771139.57     10212594.76       3770342.6     10214511.25
      3769794.37     10215787.59
#Sta/Elev= 30
  2924.4  230.37  3039.1  231.11  3311.1  229.04  3435.8  227.24  3451.1  225.24
  3472.7  227.74  3819.3  230.15  4029.1  228.07  4161.4  228.28  4423.4   218.1
  4789.8  220.97  4842.9  219.28  4890.6   220.5    4973  217.77  4978.4  217.37
  4984.5  213.75  5014.9  213.75  5025.9  218.14  5181.8  222.35  5301.3  227.67
  5522.2  233.09  5658.2  228.54  5812.2  229.48  5830.8  229.59  5981.3  230.22
  6109.4  229.64  6143.8  231.26  6207.9  228.14  6343.1  228.16  6389.1  230.62
#Mann= 10 ,-1 , 0
  2924.4     .17       0  3039.1     .11       0  4029.1     .17       0
  4161.4     .15       0    4973     .09       0  5025.9     .15       0
  5181.8     .11       0  5812.2     .17       0  5830.8     .11       0
  5981.3     .17       0
#XS Ineff= 1 ,-1
    3245  4086.2  229.25
Permanent Ineff=
       F
Bank Sta=4973,5025.9
XS Rating Curve= 0 ,0
Exp/Cntr=0.3,0.1

Type RM Length L Ch R = 1 ,4222    ,500,500,500
BEGIN DESCRIPTION:
ROBINSON CREEK 5.0
END DESCRIPTION:
XS GIS Cut Line= 3
      3769765.93     10211684.98      3769502.03     10213004.44
      3769536.73     10215717.93
#Sta/Elev= 30
  3351.9  226.26  3439.7  227.65  3745.6  222.01  3870.2  222.65  4039.5  222.62
  4039.6  222.62  4214.7  226.22  4283.2  224.53  4645.3     225  4792.4  221.75
  4904.1     216  4984.1  216.74  4988.8  211.81  5019.4  211.81  5024.2  217.43
  5154.2  215.83  5454.2  216.61  5484.2  213.83  5524.2  217.14  5610.4  217.31
  5905.3  223.64    5908  223.56  6124.2     228  6298.6  227.88  6504.3  226.92
  6674.3  229.34  6934.3  229.07  7114.3  226.92  7314.3  230.97  7411.2  228.87
#Mann= 11 ,-1 , 0
  3351.9     .17       0  3870.2     .11       0  4039.5     .15       0
  4039.6     .11       0  4792.4     .15       0  4984.1     .09       0
  5024.2     .15       0  5610.4     .11       0  5905.3     .17       0
    5908     .11       0  6298.6     .17       0
#XS Ineff= 1 ,-1
    3480  4538.2  225.75
Permanent Ineff=
       F
Bank Sta=4984.1,5024.2
XS Rating Curve= 0 ,0
Exp/Cntr=0.3,0.1