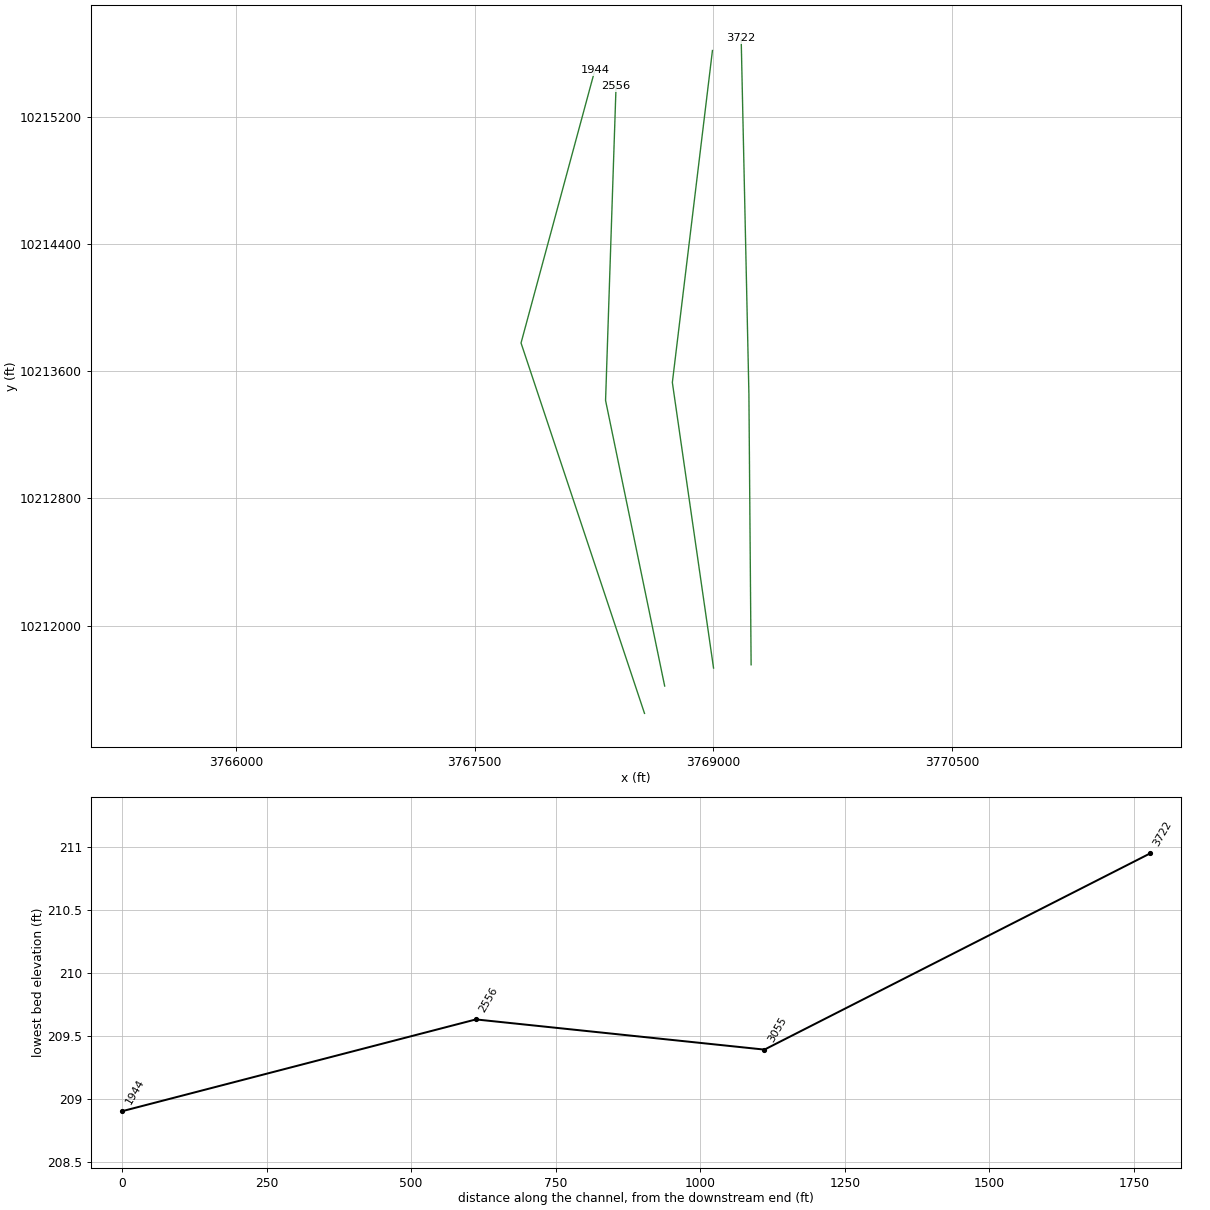
HEC-RAS study ROBINSON CREEK.prj: ROBINSON CREEK Base Level Engineering

--- ROBINSON CREEK.g01 (geometry) --- (continued)

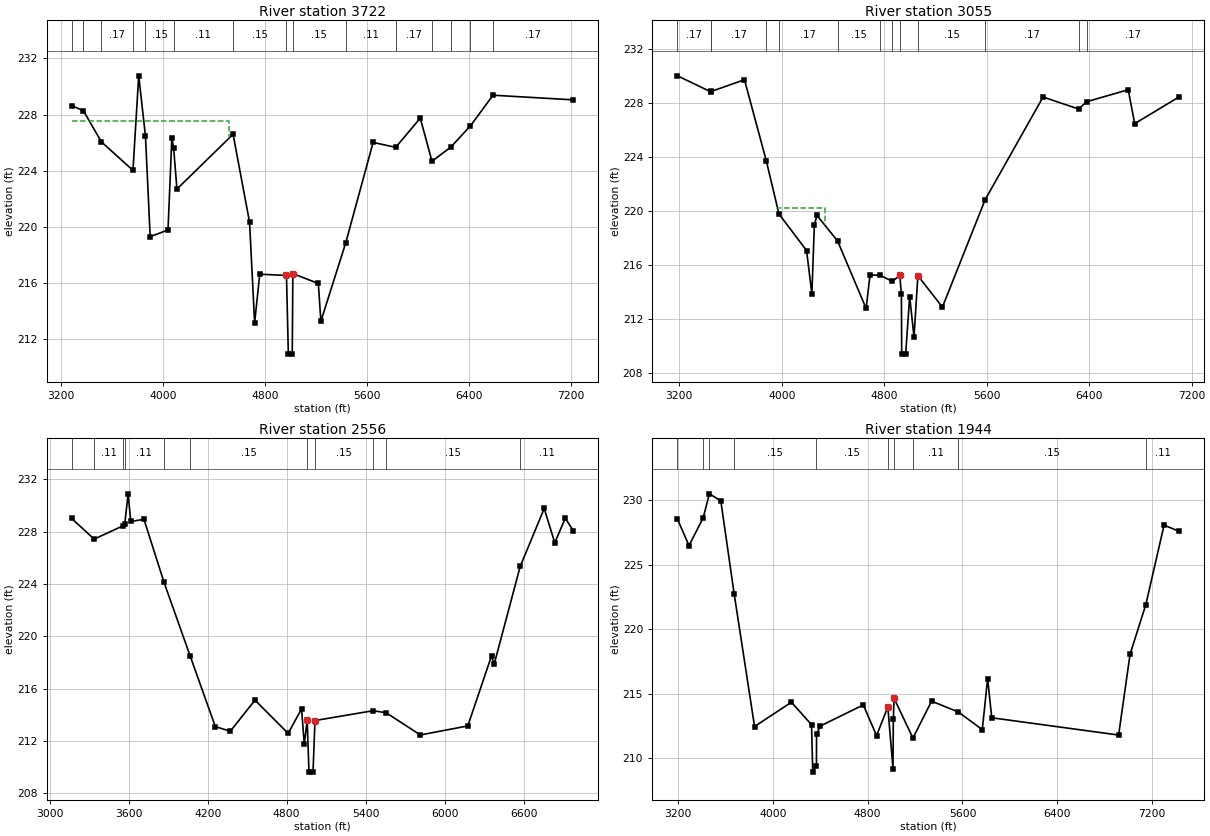
Type RM Length L Ch R = 1 ,3722    ,667,667,667
BEGIN DESCRIPTION:
ROBINSON CREEK 4.0
END DESCRIPTION:
XS GIS Cut Line= 3
      3769238.14     10211754.42      3769224.26     10213455.83
      3769175.64     10215691.93
#Sta/Elev= 30
  3281.5  228.64  3373.9  228.28  3515.1  226.06  3763.1  224.03  3808.2  230.76
  3861.3  226.46  3898.2  219.31  4038.2  219.79  4068.2  226.33  4082.3  225.62
  4108.2   222.7    4549   226.6  4678.2  220.35  4718.2  213.18  4758.2  216.64
  4968.2  216.55  4982.9  210.95  5013.5  210.95  5018.2  216.68  5218.3  215.98
  5238.3  213.29    5433  218.86  5648.4  226.02  5825.8  225.67  6018.5  227.75
  6110.4  224.68  6257.6  225.68  6412.5   227.2  6589.6  229.38  7219.6  229.05
#Mann= 15 ,-1 , 0
  3281.5     .17       0  3373.9     .11       0  3515.1     .17       0
  3763.1     .11       0  3861.3     .15       0  4082.3     .11       0
    4549     .15       0  4968.2     .09       0  5018.2     .15       0
    5433     .11       0  5825.8     .17       0  6110.4     .15       0
  6257.6     .17       0  6412.5     .11       0  6589.6     .17       0
#XS Ineff= 1 ,-1
    3285  4518.2  227.57
Permanent Ineff=
       F
Bank Sta=4968.2,5018.2
XS Rating Curve= 0 ,0
Exp/Cntr=0.3,0.1

Type RM Length L Ch R = 1 ,3055    ,499,499,499
BEGIN DESCRIPTION:
ROBINSON CREEK 3.0
END DESCRIPTION:
XS GIS Cut Line= 3
      3769002.03     10211733.65      3768743.08     10213528.77
      3768995.08      10215615.5
#Sta/Elev= 30
  3186.3     230  3447.9  228.81  3448.5  228.84  3709.1  229.71  3879.6   223.7
  3978.3  219.77    4194  217.06  4235.3  213.84  4254.7  218.96  4274.9  219.66
  4435.5  217.78  4658.8  212.77  4689.1  215.26  4768.2  215.22  4863.7  214.78
  4921.5  215.22  4934.1  213.81  4936.5  209.39  4967.2  209.39  4998.6  213.65
  5032.5  210.66  5062.8   215.2  5254.1  212.87  5587.5  220.82  6039.8  228.43
  6318.2  227.54  6379.1  228.08  6704.6  228.97    6755  226.46  7101.9  228.44
#Mann= 13 ,-1 , 0
  3186.3     .17       0  3447.9     .11       0  3448.5     .17       0
  3879.6     .11       0  3978.3     .17       0  4435.5     .15       0
  4768.2     .11       0  4863.7     .15       0  4921.5     .09       0
  5062.8     .15       0  5587.5     .17       0  6318.2     .11       0
  6379.1     .17       0
#XS Ineff= 1 ,-1
    3955  4335.5  220.23
Permanent Ineff=
       F
Bank Sta=4921.5,5062.8
XS Rating Curve= 0 ,0
Exp/Cntr=0.3,0.1

Type RM Length L Ch R = 1 ,2556    ,612,612,612
BEGIN DESCRIPTION:
ROBINSON CREEK 2.0
END DESCRIPTION:
XS GIS Cut Line= 3
      3768694.74     10211620.77      3768323.29     10213415.74
      3768389.19     10215391.64
#Sta/Elev= 30
    3167  229.01  3338.1  227.43  3555.8  228.44  3570.2  228.56  3596.2  230.89
    3616  228.78  3716.4  228.94  3868.8  224.13    4068  218.48  4258.4  213.11
  4372.3  212.75  4559.6  215.13  4811.4  212.59  4913.5  214.46    4934  211.75
  4956.2  213.61  4969.7  209.63  5000.4  209.63  5015.3  213.57  5456.6  214.32
    5555  214.17  5815.8  212.47    6176  213.16  6356.1  218.51  6376.1  217.87
  6573.9  225.34  6756.3  229.77  6836.4  227.15  6916.4  229.03    6977  228.07
#Mann= 11 ,-1 , 0
    3167     .17       0  3338.1     .11       0  3555.8     .15       0
  3570.2     .11       0  3868.8     .17       0    4068     .15       0
  4956.2     .08       0  5015.3     .15       0  5456.6     .17       0
    5555     .15       0  6573.9     .11       0
Bank Sta=4956.2,5015.3
XS Rating Curve= 0 ,0
Exp/Cntr=0.3,0.1

Type RM Length L Ch R = 1 ,1944    ,0,0,0
BEGIN DESCRIPTION:
ROBINSON CREEK 1.0
END DESCRIPTION:
XS GIS Cut Line= 3
      3768568.01     10211448.86      3767791.96     10213777.01
       3768255.5     10215490.53
#Sta/Elev= 30
  3197.2  228.54  3294.4  226.49    3414  228.65  3465.9  230.51  3562.3  229.97
  3674.9  222.75  3846.9  212.44  4157.8  214.33  4327.4  212.58  4337.5   208.9
  4368.7   209.4  4369.6  211.84  4401.2  212.48    4764  214.12  4875.5  211.73
  4970.4  213.96  5014.2  209.15  5016.9  212.99  5023.1  214.64  5182.1  211.54
  5339.3  214.41  5565.1  213.57  5766.9   212.2    5812  216.17  5846.7  213.12
  6916.3  211.78  7012.6  218.05  7145.7  221.91  7299.4  228.08  7426.4   227.6
#Mann= 10 ,-1 , 0
  3197.2     .17       0    3414     .11       0  3465.9     .17       0
  3674.9     .15       0  4368.7     .15       0  4970.4     .09       0
  5023.1     .15       0  5182.1     .11       0  5565.1     .15       0
  7145.7     .11       0
Bank Sta=4970.4,5023.1
XS Rating Curve= 0 ,0
Exp/Cntr=0.3,0.1

Chan Stop Cuts=-1
Use User Specified Reach Order=0
Composite Channel Slope=5