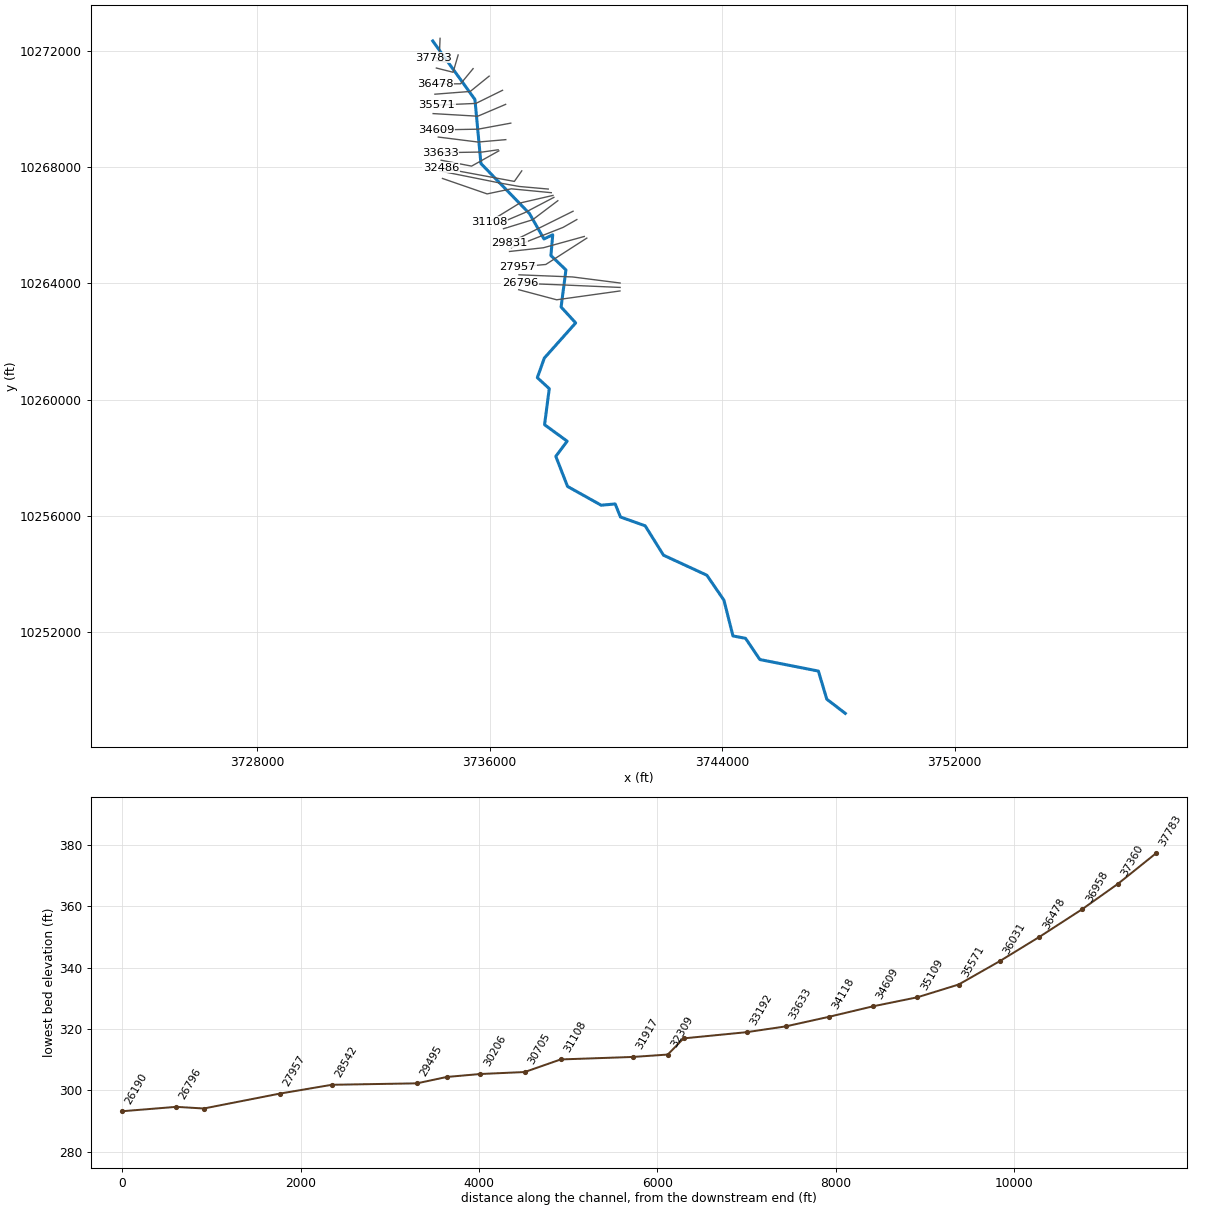
--- ROCKY CREEK.prj (project) ---

Proj Title=ROCKY CREEK Base Level Engineering
Current Plan=p01
Default Exp/Contr=0.3,0.1
English Units
Geom File=g01
Flow File=f01
Plan File=p01
Y Axis Title=Elevation
X Axis Title(PF)=Main Channel Distance
X Axis Title(XS)=Station
BEGIN DESCRIPTION:
ROCKY CREEK
END DESCRIPTION:
DSS Export Rating Curves= 0
DSS Export Rating Curve Sorted= 0
DSS Export Volume Flow Curves= 0
DXF OffsetX= 0
DXF OffsetY= 0
DXF ScaleX= 1
DXF ScaleY= 10

--- ROCKY CREEK.p01 (plan) ---

Plan Title=Multiple Run
Program Version=4.10
Short Identifier=Multiple
Geom File=g01
Flow File=f01
Subcritical Flow
K Sum by GR= 0
Std Step Tol= 0.01
Critical Tol= 0.01
Num of Std Step Trials= 20
Max Error Tol= 0.3
Flow Tol Ratio= 0.001
Split Flow NTrial= 30
Split Flow Tol= 0.02
Split Flow Ratio= 0.02
Log Output Level= 0
Friction Slope Method= 1
Unsteady Friction Slope Method= 2
Unsteady Bridges Friction Slope Method= 1
Parabolic Critical Depth
Global Vel Dist= 1 , 1 , 1
Global Log Level= 0
CheckData=True
Encroach Param=-1 ,0,0, 0
BEGIN DESCRIPTION:
Multiple Run
END DESCRIPTION:
Computation Interval=1HOUR
Output Interval=1HOUR
Run HTab= 0
Run UNet= 0
Run PostProcess= 0
Run WQNet= 0
UNET Theta= 1
UNET Theta Warmup= 1
UNET ZTol= 0.02
UNET ZSATol= 0.05
UNET MxIter= 20
UNET MaxInSteps= 0
UNET DtIC= 0
UNET DtMin= 0
UNET MaxCRTS= 20
UNET WFStab= 2
UNET SFStab= 1
UNET WFX= 1
UNET SFX= 1
UNET DSS MLevel= 4
UNET DZMax Abort= 100
UNET Convert EG Bridges= 0
UNET Use Existing IB Tables=-1
UNET Froude Reduction=False
UNET Froude Limit= 1
UNET Froude Power= 10
UNET Time Slicing=0,0, 5
UNET Junction Losses=0
Instantaneous Interval=1HOUR
Write IC File= 0
Write IC File at Sim End=0
Echo Input=False
Echo Parameters=False
Echo Output=False
Write Detailed= 0
WQ AD Non Conservative
WQ ULTIMATE=-1
WQ Max Comp Step=1HOUR
WQ Output Interval=15MIN
WQ Output Selected Increments= 0
WQ Output face flow=0
WQ Output face velocity=0
WQ Output face area=0
WQ Output face dispersion=0
WQ Output cell volume=0
WQ Output cell surface area=0
WQ Output cell continuity=0
WQ Output cumulative cell continuity=0
WQ Output face conc=0
WQ Output face dconc_dx=0
WQ Output face courant=0
WQ Output face peclet=0
WQ Output face adv mass=0
WQ Output face disp mass=0
WQ Output cell mass=0
WQ Output cell source sink temp=0
WQ Output cell source sink nsm=0
WQ Output MaxMinRange=-1
WQ Daily Max Min Mean=-1
WQ Daily Range=0
WQ Daily Time=0
WQ Create Restart=0
WQ Fixed Restart=0
WQ System Summary=0
WQ Use Fixed Temperature=0
Sorting and Armoring Iterations= 10
XS Update Threshold= 0.02
Hydraulics Update Threshold= 0.02
Energy Slope Method= 1
Volume Change Method= 0
XS Weighting Method= 0
Number of US Weighted Cross Sections= 1
Number of DS Weighted Cross Sections= 1
Upstream XS Weight=0.25
Main XS Weight=0.5
Downstream XS Weight=0.25
Number of DS XS's Weighted with US Boundary= 1
Upstream Boundary Weight= 1
Weight of XSs Associated with US Boundary= 0
Number of US XS's Weighted with DS Boundary= 1
Downstream Boundary Weight= 0.5
Weight of XSs Associated with DS Boundary= 0.5
Sediment Output Level= 4
Mass or Volume Output= 0
Output Increment Type= 1
Profile and TS Output Increment= 10
XS Output Flag= 0
XS Output Increment= 10
Disregard all LS=0
Disregard all Conn=0
Disregard all Breaches=0
Disregard all Pumps=0

--- ROCKY CREEK.f01 (steady flow) ---

Flow Title=Multiple
Program Version=4.10
Number of Profiles= 7
Profile Names=10-year,25-year,50-year,1pct_min,100-year,1pct_plu,500-year
River Rch & RM=ROCKY CREEK,Reach-1         ,37783
     916    1288    1786     816    2464    7441    4844
River Rch & RM=ROCKY CREEK,Reach-1         ,31108
    1083    1522    2107     959    2895    8743    5657
River Rch & RM=ROCKY CREEK,Reach-1         ,27105
    1618    2311    3237    1488    4493   13569    8959
River Rch & RM=ROCKY CREEK,Reach-1         ,25147
    1618    2311    3237    1488    4493   13569    8959
River Rch & RM=ROCKY CREEK,Reach-1         ,22815
    2025    2909    4091    1884    5690   17184   11404
River Rch & RM=ROCKY CREEK,Reach-1         ,22336
    2025    2909    4091    1884    5690   17184   11404
River Rch & RM=ROCKY CREEK,Reach-1         ,19875
    2056    2933    4101    1878    5671   17126   11228
River Rch & RM=ROCKY CREEK,Reach-1         ,17374
    2056    2933    4101    1878    5671   17126   11228
River Rch & RM=ROCKY CREEK,Reach-1         ,13055
    1887    2663    3696    1679    5071   15314    9887
River Rch & RM=ROCKY CREEK,Reach-1         ,11262
    2490    3556    4976    2277    6877   20768   13603
River Rch & RM=ROCKY CREEK,Reach-1         ,9609
    2490    3556    4976    2277    6877   20768   13603
River Rch & RM=ROCKY CREEK,Reach-1         ,6032
    2685    3842    5384    2467    7450   22499   14771
River Rch & RM=ROCKY CREEK,Reach-1         ,2828
    3045    4364    6121    2806    8473   25588   16816
River Rch & RM=ROCKY CREEK,Reach-1         ,1923
    3045    4364    6121    2806    8473   25588   16816
Boundary for River Rch & Prof#=ROCKY CREEK,Reach-1         , 1
Up Type= 0
Dn Type= 3
Dn Slope=0.002
Boundary for River Rch & Prof#=ROCKY CREEK,Reach-1         , 2
Up Type= 0
Dn Type= 3
Dn Slope=0.002
Boundary for River Rch & Prof#=ROCKY CREEK,Reach-1         , 3
Up Type= 0
Dn Type= 3
Dn Slope=0.002
Boundary for River Rch & Prof#=ROCKY CREEK,Reach-1         , 4
Up Type= 0
Dn Type= 3
Dn Slope=0.002
Boundary for River Rch & Prof#=ROCKY CREEK,Reach-1         , 5
Up Type= 0
Dn Type= 3
Dn Slope=0.002
Boundary for River Rch & Prof#=ROCKY CREEK,Reach-1         , 6
Up Type= 0
Dn Type= 3
Dn Slope=0.002
Boundary for River Rch & Prof#=ROCKY CREEK,Reach-1         , 7
Up Type= 0
Dn Type= 3
Dn Slope=0.002
DSS Import GetInterval= 0
DSS Import GetPeak= 0
DSS Import FillOption= 0

--- ROCKY CREEK.g01 (geometry) ---

Geom Title=Existing Conditions
Program Version=4.10

River Reach=ROCKY CREEK     ,Reach-1
Reach XY= 30
      3734043.99     10272341.75      3735495.11     10270328.72
      3735701.37     10268125.28      3737372.03     10266403.14
       3737870.7      10265529.9      3738171.82     10265673.39
      3738109.46     10264959.11      3738626.56     10264465.19
       3738459.7     10263189.31      3738961.35     10262641.94
      3737882.75     10261430.88      3737641.94     10260757.34
      3738052.63      10260380.2      3737890.64     10259139.13
      3738667.59      10258572.5      3738277.89     10258049.81
      3738681.18      10257015.5      3739839.06     10256368.89
      3740321.45      10256412.9      3740501.66     10255963.05
      3741352.36     10255660.55      3741983.87     10254648.18
      3743474.35     10253960.22      3744063.42     10253099.88
      3744372.97     10251871.54      3744805.52     10251789.39
      3745298.83     10251058.67       3747312.2     10250662.34
      3747601.65     10249694.29      3748238.23     10249206.84

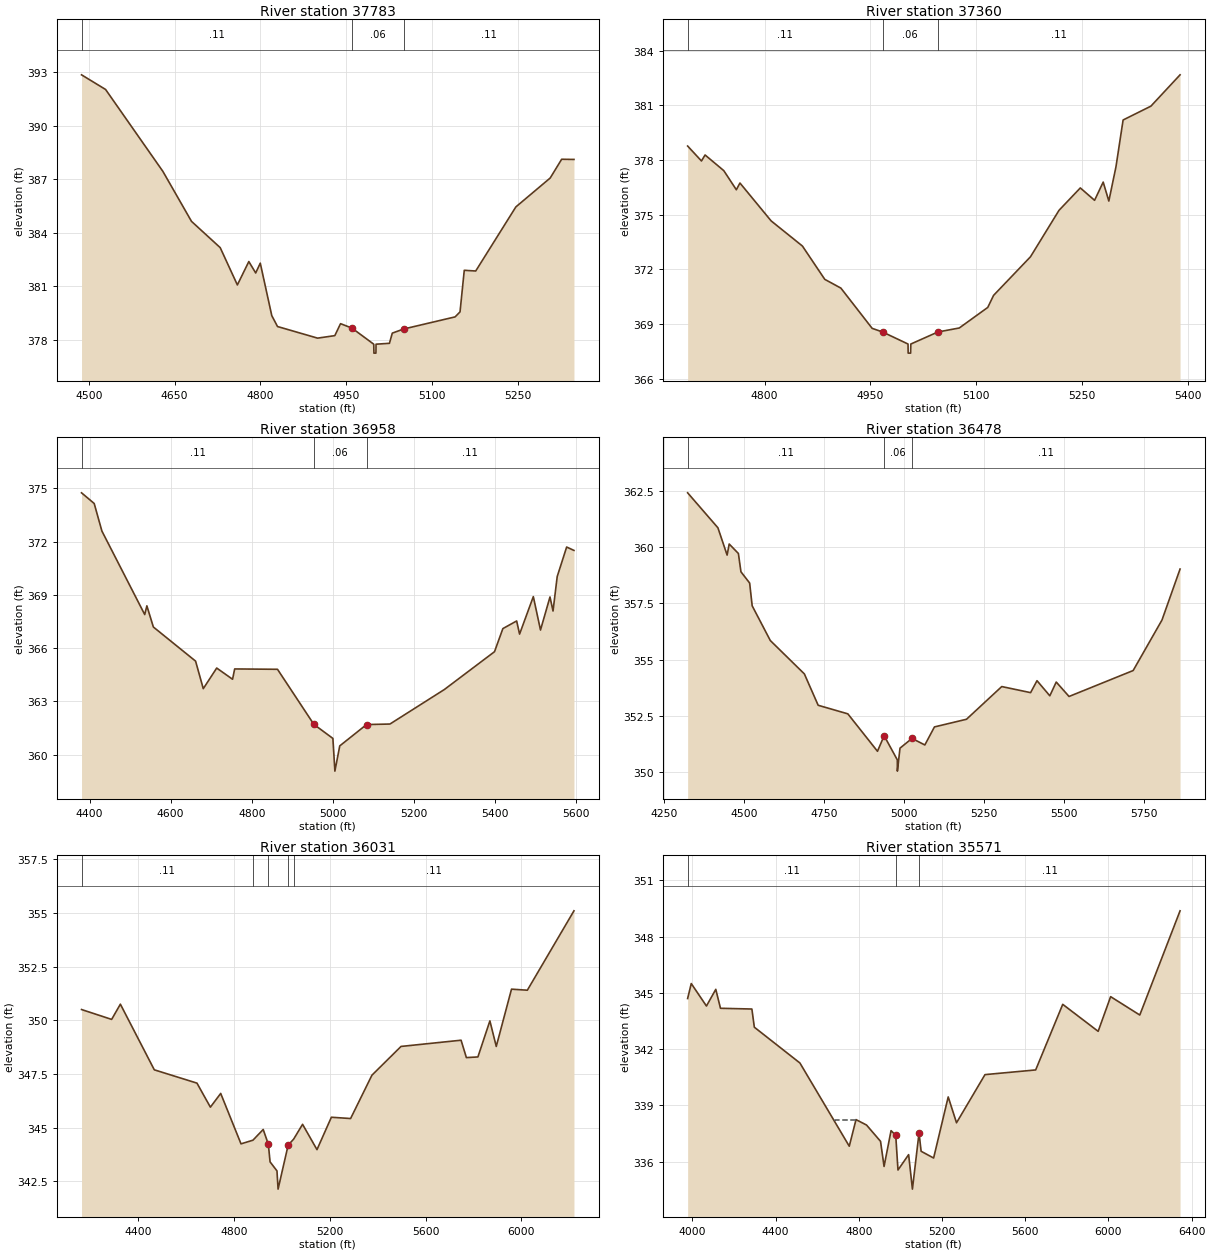
Type RM Length L Ch R = 1 ,37783   ,423,423,423
BEGIN DESCRIPTION:
WFSJR 077 24.0
END DESCRIPTION:
XS GIS Cut Line= 3
      3734295.55     10272433.04      3734267.77     10271775.03
      3734066.34     10271769.82
#Sta/Elev= 30
  4487.5  392.85  4529.5  392.03  4629.6  387.44  4679.6  384.64  4729.7  383.17
  4759.7  381.08  4779.7  382.39  4791.7  381.75  4799.7   382.3  4819.8  379.36
  4829.8  378.75  4899.8   378.1  4929.9  378.24  4939.9  378.91  4959.9  378.66
  4997.9  377.76  4998.2  377.26  5001.7  377.26  5001.9  377.76  5025.3  377.81
  5030.3  378.38    5050  378.61    5140  379.29  5148.6  379.57    5156   381.9
    5176  381.86  5246.1  385.45  5306.1  387.07  5326.1  388.12  5347.6  388.11
#Mann= 3 , 0 , 0
  4487.5     .11       0  4959.9     .06       0    5050     .11       0
Bank Sta=4959.9,5050
XS Rating Curve= 0 ,0
Exp/Cntr=0.3,0.1

Type RM Length L Ch R = 1 ,37360   ,403,403,403
BEGIN DESCRIPTION:
WFSJR 077 23.0
END DESCRIPTION:
XS GIS Cut Line= 3
      3734617.85     10271911.08      3734552.97     10271608.97
      3734167.87     10271661.07
#Sta/Elev= 30
    4691  378.77  4710.6  377.95  4715.7  378.28  4742.2  377.42    4760  376.37
  4765.1  376.74  4809.3  374.66  4853.6  373.28  4885.3  371.45  4908.1  370.97
  4952.4  368.76  4967.2  368.56  5003.2   367.9  5003.4   367.4  5006.9   367.4
  5007.2   367.9  5045.5  368.56  5075.8  368.78  5116.2  369.91  5124.4  370.57
  5176.7  372.69  5217.1  375.24  5247.3  376.47  5267.5  375.79  5279.7  376.79
  5287.7  375.75  5297.8  377.63  5307.9   380.2  5347.3  380.96  5388.6  382.68
#Mann= 3 , 0 , 0
    4691     .11       0  4967.2     .06       0  5045.5     .11       0
Bank Sta=4967.2,5045.5
XS Rating Curve= 0 ,0
Exp/Cntr=0.3,0.1

Type RM Length L Ch R = 1 ,36958   ,480,480,480
BEGIN DESCRIPTION:
WFSJR 077 22.0
END DESCRIPTION:
XS GIS Cut Line= 3
      3734917.84     10271861.05      3734744.28     10271266.05
      3734167.85     10271411.07
#Sta/Elev= 30
  4380.2  374.74  4411.4  374.14  4430.4  372.59    4536  367.89  4541.3  368.38
  4557.3  367.19  4661.4  365.27  4680.4  363.72  4713.5  364.88  4752.6  364.25
  4757.8  364.83  4863.4  364.81  4953.1  361.71    5000  360.92  5004.9  359.08
  5016.9   360.5    5083   361.7  5140.7  361.73  5274.7  363.67  5398.5   365.8
  5419.1   367.1  5453.1  367.53  5460.3  366.79  5494.2   368.9  5511.9  367.02
  5535.3  368.88  5542.8  368.09  5553.1  370.03  5576.4  371.69  5594.4   371.5
#Mann= 3 ,-1 , 0
  4380.2     .11       0  4953.1     .06       0    5083     .11       0
Bank Sta=4953.1,5083
XS Rating Curve= 0 ,0
Exp/Cntr=0.3,0.1

Type RM Length L Ch R = 1 ,36478   ,446,446,446
BEGIN DESCRIPTION:
WFSJR 077 21.0
END DESCRIPTION:
XS GIS Cut Line= 3
      3735431.86     10271390.34      3735002.98     10270868.97
       3734141.5     10270863.23
#Sta/Elev= 30
  4324.9   362.4  4419.4  360.85  4448.1  359.64  4454.6  360.13  4483.3  359.71
  4491.2   358.9  4518.4   358.4  4526.3  357.39  4582.9  355.85  4689.2  354.37
  4732.2  352.98  4824.8   352.6  4917.3  350.94  4938.1  351.63  4979.2  350.56
  4979.4  350.06  4987.6  351.08  5025.1  351.51  5065.1  351.22  5095.1  352.02
  5195.1  352.36  5305.1  353.81  5395.1  353.54  5415.1  354.07  5455.1   353.4
  5475.1  354.01  5515.1  353.37  5715.1  354.52  5805.1  356.76  5861.5  359.02
#Mann= 3 ,-1 , 0
  4324.9     .11       0  4938.1     .06       0  5025.1     .11       0
Bank Sta=4938.1,5025.1
XS Rating Curve= 0 ,0
Exp/Cntr=0.3,0.1

Type RM Length L Ch R = 1 ,36031   ,460,460,460
BEGIN DESCRIPTION:
WFSJR 077 20.0
END DESCRIPTION:
XS GIS Cut Line= 3
      3735983.88     10271132.46      3735333.87     10270605.46
      3734117.83     10270511.07
#Sta/Elev= 30
  4163.2   350.5  4288.9  350.04  4325.4  350.75  4467.1  347.69  4645.3  347.07
  4701.3  345.95  4744.4  346.59  4829.2  344.24    4879  344.41  4921.9  344.91
  4943.4  344.22  4950.6   343.4  4979.4  342.98    4984  342.13  5026.1  344.18
    5049  344.46  5086.3  345.15  5146.5  343.97  5206.6  345.48  5286.9  345.42
    5376  347.44  5497.5  348.78  5748.3  349.07  5770.4  348.26  5818.5  348.29
  5868.6  349.97  5895.2  348.78  5958.9  351.45    6025   351.4  6219.7   355.1
#Mann= 5 ,-1 , 0
  4163.2     .11       0    4879     .11       0  4943.4     .06       0
  5026.1     .11       0    5049     .11       0
Bank Sta=4943.4,5026.1
XS Rating Curve= 0 ,0
Exp/Cntr=0.3,0.1

Type RM Length L Ch R = 1 ,35571   ,462,462,462
BEGIN DESCRIPTION:
WFSJR 077 19.0
END DESCRIPTION:
XS GIS Cut Line= 3
      3736444.87     10270645.52      3735527.59     10270193.95
      3734184.48      10270135.1
#Sta/Elev= 30
  3977.6   344.7    3995   345.5    4068   344.3  4112.9  345.19  4135.4  344.18
  4286.4  344.14  4298.2  343.17  4517.3  341.26  4754.5  336.82  4786.9  338.24
  4837.4  337.95  4904.8  337.08  4921.7  335.74  4955.3  337.65  4977.8   337.4
  4988.6  335.55  5039.8  336.37    5058  334.53  5089.8  337.53  5099.8  336.55
  5159.9  336.19    5230  339.45    5270  338.07  5406.8  340.64  5650.4  340.89
  5780.5  344.39  5950.7  342.95  6010.7   344.8  6150.8  343.82  6344.4  349.38
#Mann= 3 ,-1 , 0
  3977.6     .11       0  4977.8     .06       0  5089.8     .11       0
#XS Ineff= 2 ,-1
    4684  4786.9  338.24    4835  4955.3  337.65
Permanent Ineff=
       F       F
Bank Sta=4977.8,5089.8
XS Rating Curve= 0 ,0
Exp/Cntr=0.3,0.1

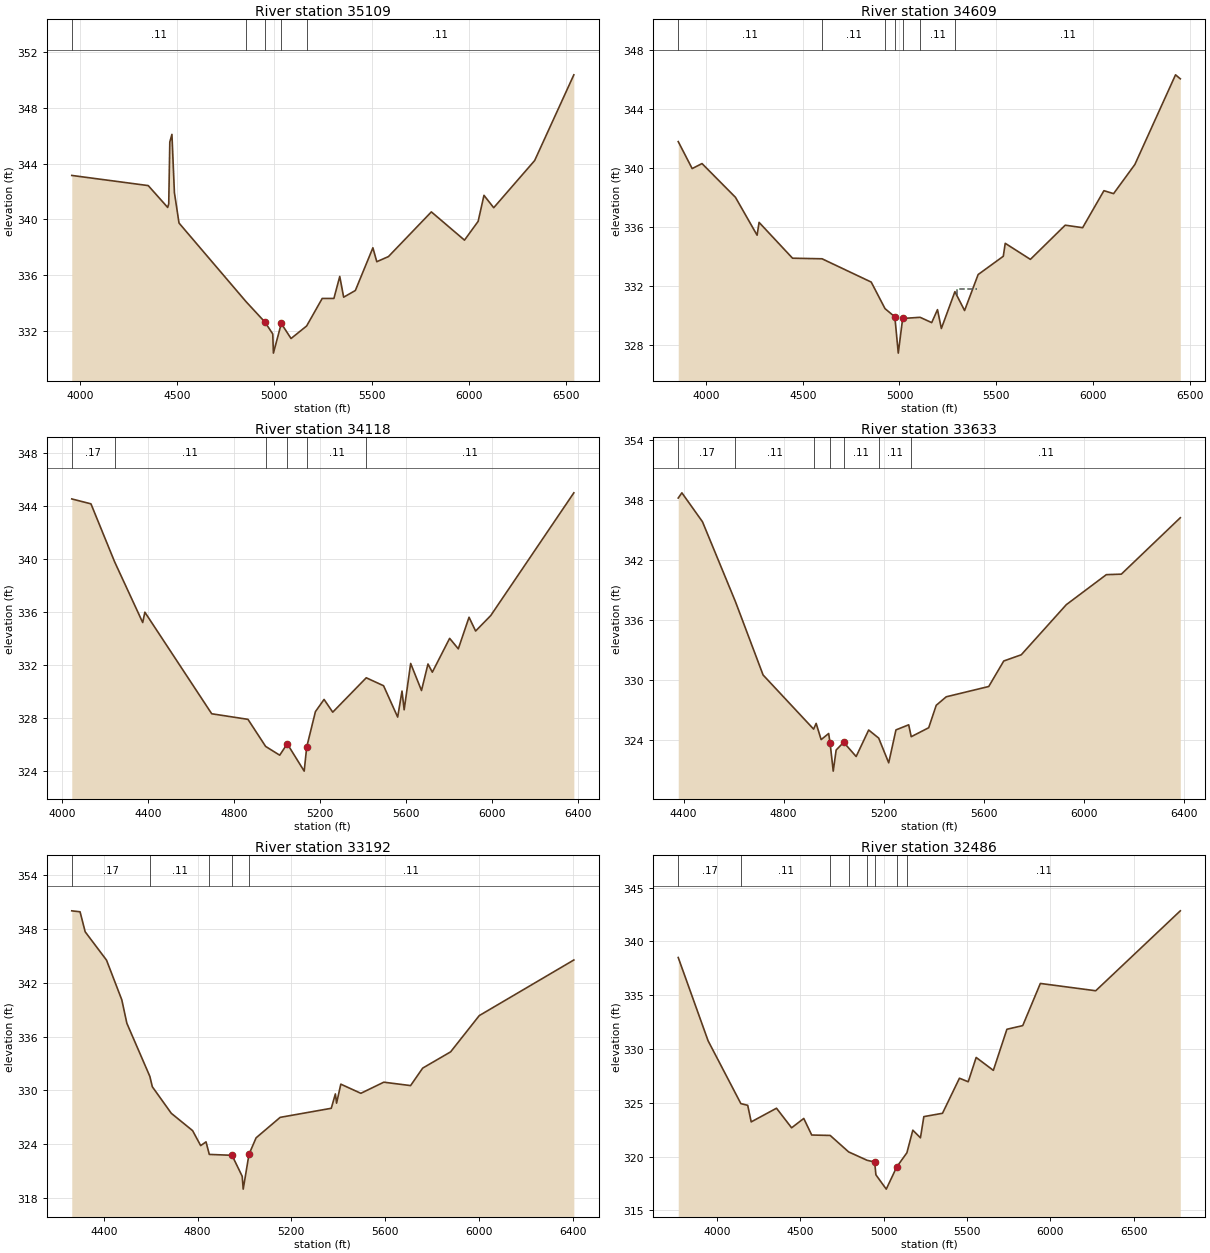
Type RM Length L Ch R = 1 ,35109   ,500,500,500
BEGIN DESCRIPTION:
WFSJR 077 18.0
END DESCRIPTION:
XS GIS Cut Line= 3
      3736551.59     10270161.12      3735593.26     10269753.55
      3734056.79     10269843.43
#Sta/Elev= 30
  3958.6  343.15  4351.6  342.42  4451.6  340.85    4457  341.11  4462.5  345.55
  4473.4   346.1  4486.1  341.92  4509.8  339.73  4853.7  334.09  4951.5  332.61
  4991.6  331.76    4995  330.38  5035.5  332.51  5085.6  331.43  5165.7  332.33
  5245.8  334.31  5305.9  334.31    5336  335.89    5356   334.4  5416.1  334.88
  5506.3  337.95  5526.3  336.95  5586.4  337.32  5806.8  340.53  5977.1   338.5
  6047.2  339.85  6077.2  341.72  6127.3  340.83  6337.7  344.22  6539.1  350.38
#Mann= 5 ,-1 , 0
  3958.6     .11       0  4853.7     .11       0  4951.5     .06       0
  5035.5     .11       0  5165.7     .11       0
Bank Sta=4951.5,5035.5
XS Rating Curve= 0 ,0
Exp/Cntr=0.3,0.1

Type RM Length L Ch R = 1 ,34609   ,491,491,491
BEGIN DESCRIPTION:
WFSJR 077 17.0
END DESCRIPTION:
XS GIS Cut Line= 3
      3736728.69      10269515.3      3735604.51     10269307.64
      3734153.16     10269280.93
#Sta/Elev= 30
  3856.8  341.77  3928.8  339.94  3979.7  340.28  4152.6  337.99  4264.4  335.42
  4274.6  336.29  4447.5  333.86    4600  333.82  4854.2  332.24  4925.4  330.44
  4976.3  329.88    4994  327.42  5016.7  329.77  5106.7  329.85  5166.7  329.49
  5196.7  330.37  5216.7  329.09  5286.7  331.59  5336.7  330.31  5406.7  332.75
  5536.7  333.99  5546.8  334.87  5676.8  333.78  5856.8   336.1  5946.8  335.93
  6056.8  338.44  6106.8  338.24  6216.9  340.22  6426.9   346.3  6451.6  346.03
#Mann= 7 ,-1 , 0
  3856.8     .11       0    4600     .11       0  4925.4     .11       0
  4976.3     .06       0  5016.7     .11       0  5106.7     .11       0
  5286.7     .11       0
#XS Ineff= 1 ,-1
  5296.7    5400  331.78
Permanent Ineff=
       F
Bank Sta=4976.3,5016.7
XS Rating Curve= 0 ,0
Exp/Cntr=0.3,0.1

Type RM Length L Ch R = 1 ,34118   ,486,486,486
BEGIN DESCRIPTION:
WFSJR 077 16.0
END DESCRIPTION:
XS GIS Cut Line= 3
       3736556.8     10268947.59      3735604.52     10268864.54
      3734234.21      10269036.1
#Sta/Elev= 30
  4044.1  344.52  4133.4  344.15  4243.4  339.79  4374.3  335.21  4384.3  335.99
  4695.5  328.34  4864.2  327.92  4946.5  325.88    5012  325.22    5047  326.08
  5125.9  324.02  5137.7  325.84  5178.2   328.5  5218.4  329.42  5258.8  328.46
  5414.8  331.05  5495.4  330.45    5561  328.09  5581.2  330.05  5591.2  328.64
  5621.5  332.13  5671.9  330.09  5702.1  332.09  5722.3  331.47  5802.9  334.02
  5843.2  333.23  5893.2  335.61  5923.8  334.57  5994.4  335.74    6381  344.98
#Mann= 6 ,-1 , 0
  4044.1     .17       0  4243.4     .11       0  4946.5     .11       0
    5047     .06       0  5137.7     .11       0  5414.8     .11       0
Bank Sta=5047,5137.7
XS Rating Curve= 0 ,0
Exp/Cntr=0.3,0.1

Type RM Length L Ch R = 1 ,33633   ,440,440,440
BEGIN DESCRIPTION:
WFSJR 077 15.0
END DESCRIPTION:
XS GIS Cut Line= 3
      3736293.81     10268598.64      3735752.95     10268521.57
      3734292.07     10268497.09
#Sta/Elev= 30
  4378.7  348.19  4393.3  348.71  4475.6  345.82  4607.6  337.82    4718   330.5
    4920  325.09  4930.1  325.66  4950.1  324.04  4980.1  324.65 4985.85   323.7
  4998.4  320.89  5010.1     323  5040.1  323.77  5090.1  322.35  5140.1     325
  5180.2  324.19  5220.2  321.72  5249.2  325.01  5300.2  325.52  5310.2  324.33
  5380.2  325.23  5410.2  327.47  5450.2  328.32  5620.2  329.35  5680.2   331.9
  5750.2  332.52  5930.3  337.53  6090.3  340.53  6150.3  340.58  6386.1  346.22
#Mann= 7 ,-1 , 0
  4378.7     .17       0  4607.6     .11       0    4920     .11       0
 4985.85     .06       0  5040.1     .11       0  5180.2     .11       0
  5310.2     .11       0
Bank Sta=4985.85,5040.1
XS Rating Curve= 0 ,0
Exp/Cntr=0.3,0.1

Type RM Length L Ch R = 1 ,33192   ,706,706,706
BEGIN DESCRIPTION:
WFSJR 077 14.0
END DESCRIPTION:
XS GIS Cut Line= 3
      3736317.88     10268561.09      3735379.75     10268036.14
      3734331.52     10268239.02
#Sta/Elev= 30
  4262.9  350.02  4298.3  349.91  4320.2  347.68  4411.3  344.52  4476.4   340.1
  4498.1  337.48  4596.1  331.57  4606.7  330.41  4687.7  327.45  4778.6  325.52
    4813  323.85  4835.9  324.27  4849.8  322.87  4946.9  322.77  4990.3  320.43
  4994.6     319  5019.2  322.88  5049.6  324.72  5152.4     327  5370.4  328.01
  5387.9  329.61    5393  328.58  5411.1   330.7  5496.6  329.68  5594.5  330.92
  5708.8  330.54  5760.6  332.49  5879.7   334.3  6001.9  338.34  6405.6  344.54
#Mann= 5 ,-1 , 0
  4262.9     .17       0  4596.1     .11       0  4849.8     .11       0
  4946.9     .06       0  5019.2     .11       0
Bank Sta=4946.9,5019.2
XS Rating Curve= 0 ,0
Exp/Cntr=0.3,0.1

Type RM Length L Ch R = 1 ,32486   ,177,177,177
BEGIN DESCRIPTION:
WFSJR 077 13.0
END DESCRIPTION:
XS GIS Cut Line= 3
      3737106.33      10267872.1      3736851.11      10267510.1
      3734325.06     10267978.85
#Sta/Elev= 30
  3768.2  338.51  3947.3  330.77  4143.9  324.93    4185  324.77    4206  323.23
  4357.7   324.5  4448.4  322.68  4521.3  323.55    4569  322.01  4679.8  321.97
  4790.5  320.44  4901.3  319.66  4946.7   319.5  4954.1  318.31  5016.2  316.98
    5079  319.04    5140  320.36  5175.6  322.46  5221.3  321.75  5241.7  323.72
  5353.6  324.03  5455.3  327.29  5507.9  326.96  5555.6  329.22  5658.7  328.02
    5740  331.84    5835  332.18  5940.7   336.1  6272.9  335.42  6780.3  342.85
#Mann= 8 ,-1 , 0
  3768.2     .17       0  4143.9     .11       0  4679.8     .11       0
  4790.5     .11       0  4901.3     .11       0  4946.7     .06       0
    5079     .11       0    5140     .11       0
Bank Sta=4946.7,5079
XS Rating Curve= 0 ,0
Exp/Cntr=0.3,0.1

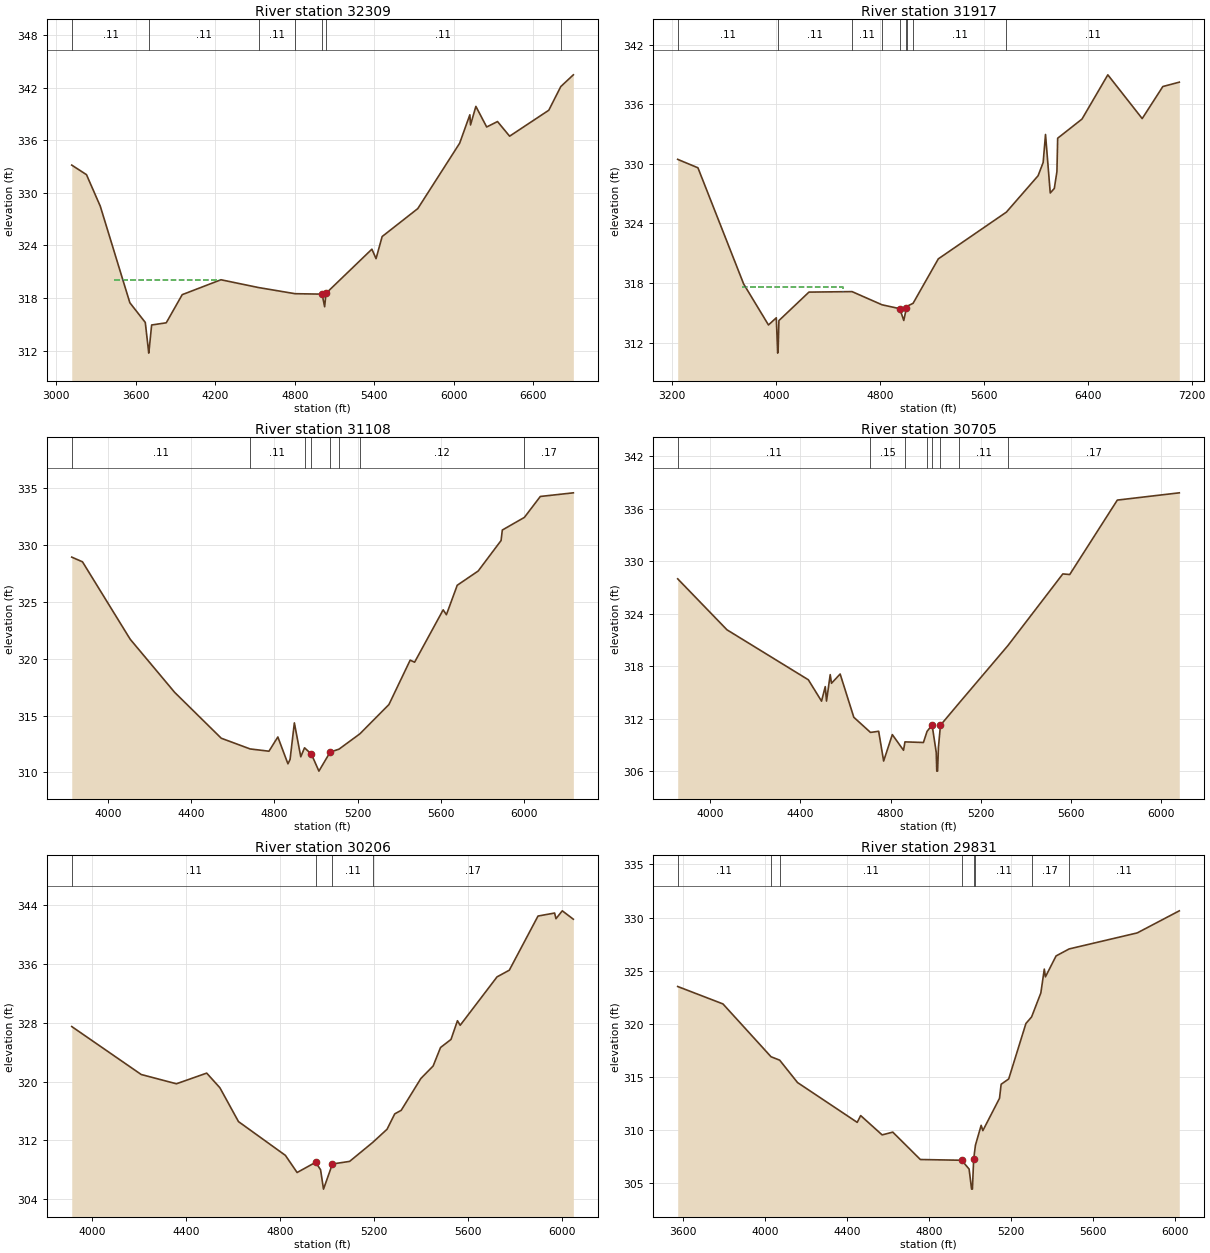
Type RM Length L Ch R = 1 ,32309   ,392,392,392
BEGIN DESCRIPTION:
WFSJR 077 12.0
END DESCRIPTION:
XS GIS Cut Line= 4
      3738018.86     10267247.07      3737024.02     10267335.62
      3736392.77      10267447.6      3734285.97     10267869.48
#Sta/Elev= 30
  3116.1  333.16  3227.5  332.07  3331.7  328.47  3554.9  317.46  3671.6  315.21
  3697.7  311.71  3701.4  312.21  3719.5  314.92  3829.9  315.17  3950.4  318.38
    4243  320.08  4527.4  319.19    4803  318.49  5006.9  318.44  5026.2     317
  5036.4  318.53  5383.1  323.57  5414.5  322.49  5460.4  325.01  5729.8   328.2
    6046  335.66  6122.9   338.9    6128  337.74  6168.4  339.86    6250  337.51
  6331.8  338.13  6423.3  336.46  6719.1  339.42  6809.7  342.12  6904.6  343.46
#Mann= 7 ,-1 , 0
  3116.1     .11       0  3701.4     .11       0  4527.4     .11       0
    4803     .11       0  5006.9     .07       0  5036.4     .11       0
  6809.7     .17       0
#XS Ineff= 1 ,-1
    3435    4235  320.04
Permanent Ineff=
       T
Bank Sta=5006.9,5036.4
XS Rating Curve= 0 ,0
Exp/Cntr=0.3,0.1

Type RM Length L Ch R = 1 ,31917   ,809,809,809
BEGIN DESCRIPTION:
WFSJR 077 11.0
END DESCRIPTION:
XS GIS Cut Line= 4
      3738122.95     10267122.08      3736746.04     10267255.31
      3735914.65     10267080.41      3734378.23     10267611.64
#Sta/Elev= 30
    3246  330.46  3401.8  329.61  3753.5   317.9  3944.3  313.77  4004.6  314.49
  4015.2  310.93    4019  311.43  4024.7  314.21  4255.8  317.08  4587.3  317.13
  4818.2   315.8  4954.5  315.41  4985.2  314.22  5005.6  315.48  5012.5  315.67
  5056.7  315.95  5250.8  320.43  5774.4  325.14  6018.5  328.81  6057.5  330.15
  6075.5  332.97    6112  327.07  6143.2  327.53  6163.3  329.23    6169  332.59
  6356.1  334.52  6554.8  338.98  6819.3  334.57    6978   337.8  7104.6  338.24
#Mann= 9 ,-1 , 0
    3246     .11       0    4019     .11       0  4587.3     .11       0
  4818.2     .11       0  4954.5     .07       0  5005.6     .11       0
  5012.5     .11       0  5056.7     .11       0  5774.4     .11       0
#XS Ineff= 1 ,-1
    3740    4517  317.61
Permanent Ineff=
       T
Bank Sta=4954.5,5005.6
XS Rating Curve= 0 ,0
Exp/Cntr=0.3,0.1

Type RM Length L Ch R = 1 ,31108   ,403,403,403
BEGIN DESCRIPTION:
WFSJR 077 10.0
END DESCRIPTION:
XS GIS Cut Line= 3
      3738180.31     10267028.33      3737036.88     10266764.39
      3735982.58       10266117.
#Sta/Elev= 30
  3826.5  328.92  3878.1  328.51  4107.3  321.71  4321.1  317.04  4545.1  313.01
  4683.6  312.07  4774.3  311.87    4817  313.12  4865.6  310.76  4875.8  311.15
  4896.4  314.36  4927.2  311.38  4945.3  312.17  4978.5  311.61  5014.4  310.12
  5068.3  311.79  5110.9  312.05  5211.5   313.4  5350.9  315.97    5453  319.87
  5474.3  319.69  5611.6  324.29  5627.1  323.86  5679.2  326.45  5779.8   327.7
  5889.9  330.38  5895.8   331.3  6001.8  332.41  6078.5  334.25  6237.2  334.57
#Mann= 8 ,-1 , 0
  3826.5     .11       0  4683.6     .11       0  4945.3     .11       0
  4978.5     .07       0  5068.3     .11       0  5110.9     .12       0
  5211.5     .12       0  6001.8     .17       0
#XS Ineff= 1 ,-1
    4445  4896.4  314.36
Permanent Ineff=
       T
Bank Sta=4978.5,5068.3
XS Rating Curve= 0 ,0
Exp/Cntr=0.3,0.1

Type RM Length L Ch R = 1 ,30705   ,499,499,499
BEGIN DESCRIPTION:
WFSJR 077 9.0
END DESCRIPTION:
XS GIS Cut Line= 3
      3738211.49      10266960.6       3737197.4     10266429.39
      3736201.97     10266007.86
#Sta/Elev= 30
  3855.2  327.98  4073.8  322.16    4435  316.45  4493.5  314.01    4510  315.67
  4515.6  314.02    4532  317.04  4537.7  316.05  4576.1  317.11  4636.7  312.17
  4710.7  310.44    4747  310.57  4769.1  307.17  4807.6  310.19  4857.3   308.4
  4863.7  309.36  4945.6  309.29  4961.8  310.56  4984.1  311.29  5002.5  308.15
  5004.9  306.02  5008.5  306.02  5012.2  308.73  5021.2  311.26  5104.2   313.8
    5320  320.34  5564.2  328.54  5594.8  328.47    5806  336.97    6081   337.8
#Mann= 8 ,-1 , 0
  3855.2     .11       0  4710.7     .15       0  4863.7     .15       0
  4961.8     .15       0  4984.1     .07       0  5021.2     .15       0
  5104.2     .11       0    5320     .17       0
Bank Sta=4984.1,5021.2
XS Rating Curve= 0 ,0
Exp/Cntr=0.3,0.1

Type RM Length L Ch R = 1 ,30206   ,375,375,375
BEGIN DESCRIPTION:
WFSJR 077 8.0
END DESCRIPTION:
XS GIS Cut Line= 3
      3738346.91     10266846.01      3737479.65     10266190.21
      3736477.12     10265882.48
#Sta/Elev= 30
  3912.7  327.47  4208.6  320.95  4358.4  319.69  4487.4  321.14  4543.6  319.15
  4622.7  314.55  4822.5  309.96  4872.4  307.63  4951.5  309.02  4972.3     308
  4984.8  305.37  5022.8  308.79    5096  309.14  5194.4  311.72  5255.4  313.51
  5288.1   315.6  5315.6  316.08  5399.4  320.41  5451.7  322.11  5483.1  324.62
  5527.7  325.72  5555.2  328.26  5566.8  327.64  5723.7  334.22    5776  335.13
  5898.2  342.49  5968.9   342.9  5974.7  342.13  6001.6   343.2  6048.7  342.06
#Mann= 4 ,-1 , 0
  3912.7     .11       0  4951.5     .06       0  5022.8     .11       0
  5194.4     .17       0
Bank Sta=4951.5,5022.8
XS Rating Curve= 0 ,0
Exp/Cntr=0.3,0.1

Type RM Length L Ch R = 1 ,29831   ,336,336,336
BEGIN DESCRIPTION:
WFSJR 077 7.0
END DESCRIPTION:
XS GIS Cut Line= 2
      3738871.21     10266484.04      3736679.41     10265394.65
#Sta/Elev= 30
  3574.8   323.5  3795.6  321.86  4030.4  316.88  4072.5  316.56  4159.6  314.45
  4450.8   310.7  4467.6  311.34  4572.4  309.52  4624.4  309.78  4758.8   307.2
  4960.5  307.13  4996.8   306.3  5008.8  304.41  5012.9  304.41  5019.1  307.24
  5027.7  308.55  5055.6  310.42  5063.8  309.92  5145.2  312.97  5153.1  314.29
    5190  314.79  5274.1  320.02  5301.6  320.63  5346.8  322.89  5363.7  325.14
  5369.3  324.41  5421.1  326.38    5485  327.04  5817.3  328.55  6022.4  330.63
#Mann= 8 ,-1 , 0
  3574.8     .11       0  4030.4     .15       0  4072.5     .11       0
  4960.5     .06       0  5019.1     .09       0  5027.7     .11       0
  5301.6     .17       0    5485     .11       0
Bank Sta=4960.5,5019.1
XS Rating Curve= 0 ,0
Exp/Cntr=0.3,0.1

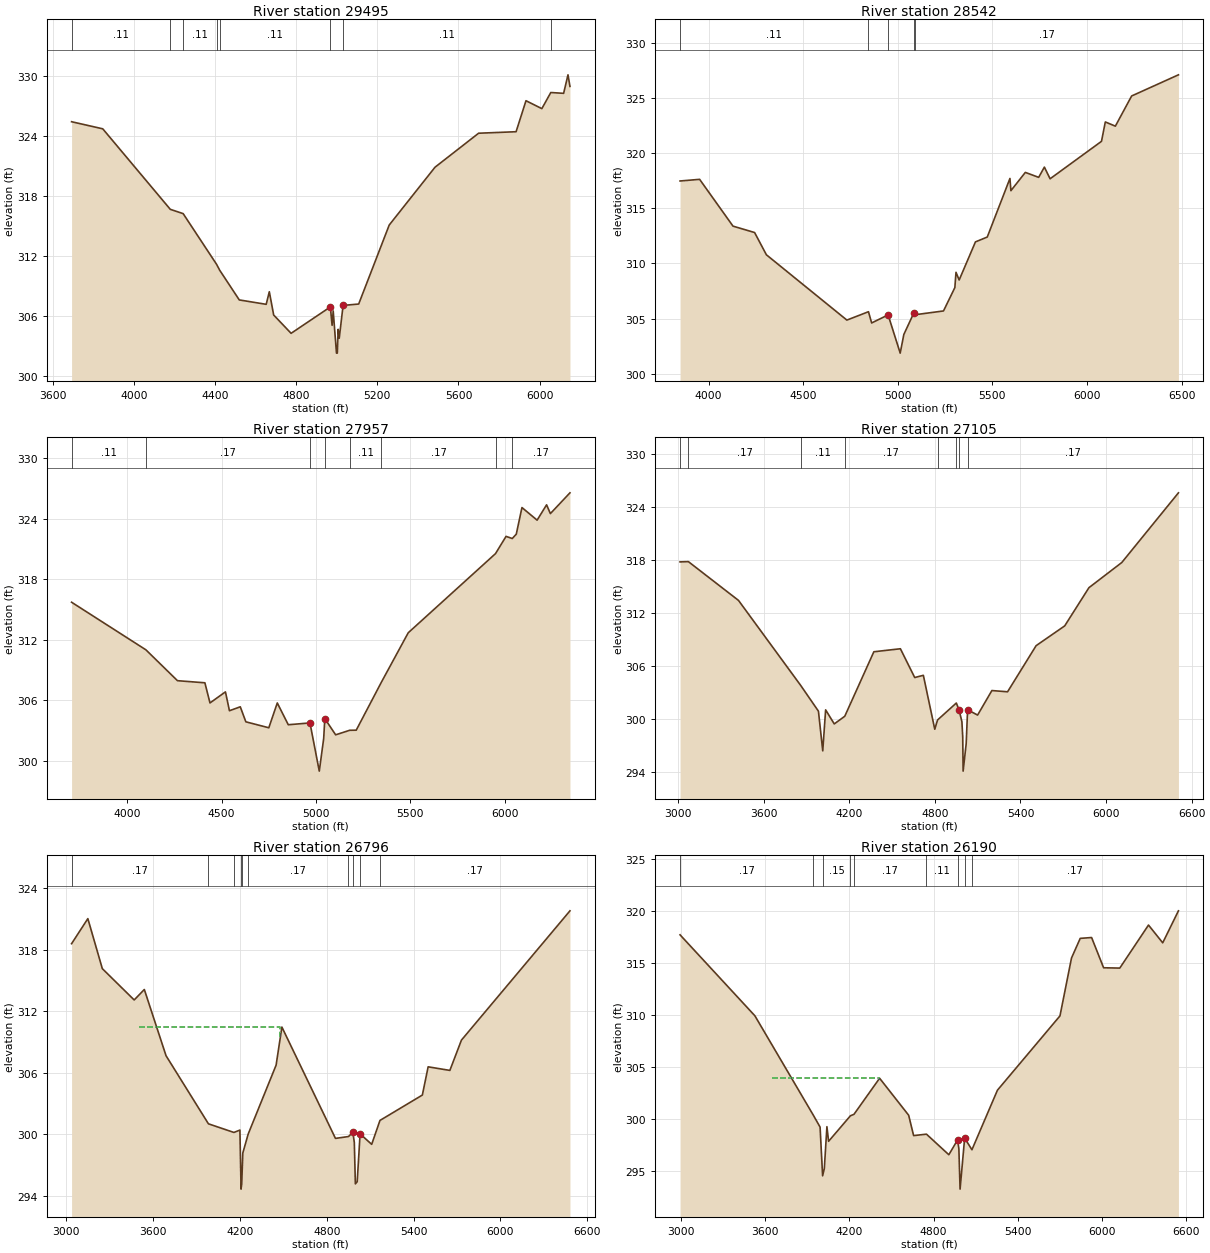
Type RM Length L Ch R = 1 ,29495   ,953,953,953
BEGIN DESCRIPTION:
WFSJR 077 6.0
END DESCRIPTION:
XS GIS Cut Line= 3
      3739001.48     10266197.61      3738528.36      10265928.5
      3736748.86     10265227.51
#Sta/Elev= 30
  3692.6  325.47  3846.3  324.76  4179.2  316.71  4242.6  316.28  4407.4  311.21
  4422.8  310.62  4519.3  307.65    4652  307.21  4667.4  308.47  4688.9  306.14
  4774.8  304.31  4968.3  306.95  4976.9  305.11  4982.3  306.55  4998.5  302.33
  5002.6  302.33  5006.7  304.71  5012.1  303.82  5031.1   307.1    5108  307.24
  5258.5  315.14  5484.2  320.92  5699.2  324.32  5883.9  324.47  5932.7  327.57
  6010.9  326.78    6055  328.39  6118.3  328.31  6139.8  330.16  6149.5     329
#Mann= 8 ,-1 , 0
  3692.6     .11       0  4179.2     .15       0  4242.6     .11       0
  4407.4     .15       0  4422.8     .11       0  4968.3     .06       0
  5031.1     .11       0    6055     .17       0
Bank Sta=4968.3,5031.1
XS Rating Curve= 0 ,0
Exp/Cntr=0.3,0.1

Type RM Length L Ch R = 1 ,28542   ,585,585,585
BEGIN DESCRIPTION:
WFSJR 077 5.0
END DESCRIPTION:
XS GIS Cut Line= 3
      3739257.54       10265616.      3737851.28     10265227.51
      3736683.72      10265099.5
#Sta/Elev= 30
  3849.5  317.49  3952.9  317.64  4129.3  313.39  4243.4  312.81  4305.7  310.79
    4731  304.86  4845.1  305.62  4861.9   304.6  4948.9  305.33  5012.8  301.86
  5031.9  303.55  5083.5  305.46  5088.7  305.34  5241.6  305.69  5301.6  307.81
  5307.6   309.2  5324.3   308.5  5410.4  311.96  5472.8   312.4  5592.7  317.72
  5597.7  316.61    5674  318.27  5744.5  317.82  5774.6  318.75  5804.8  317.69
  6076.4  321.09  6096.6  322.85  6149.7  322.47  6235.8  325.21    6483  327.13
#Mann= 5 ,-1 , 0
  3849.5     .11       0  4845.1     .17       0  4948.9     .09       0
  5083.5     .12       0  5088.7     .17       0
Bank Sta=4948.9,5083.5
XS Rating Curve= 0 ,0
Exp/Cntr=0.3,0.1

Type RM Length L Ch R = 1 ,27957   ,852,852,852
BEGIN DESCRIPTION:
WFSJR 077 4.0
END DESCRIPTION:
XS GIS Cut Line= 3
      3739344.36     10265559.59      3737933.74     10264652.46
      3736974.59     10264565.65
#Sta/Elev= 30
  3705.6  315.73  4099.3  311.01  4266.5  307.95  4411.8  307.74  4438.8  305.74
  4520.7  306.84  4541.9  304.97  4599.3  305.36  4628.8  303.87  4750.5  303.28
  4795.3  305.74  4853.6  303.58  4968.5  303.76  5017.8  298.98  5041.1  302.21
  5047.1  304.19  5104.5  302.58  5178.9  303.03  5213.5  303.04    5346  307.77
    5489   312.7  5951.4  320.55  6007.2  322.26  6040.2  322.05  6061.4  322.48
  6091.5  325.12  6171.8  323.87    6222  325.39  6242.1  324.52  6345.8  326.58
#Mann= 8 ,-1 , 0
  3705.6     .11       0  4099.3     .17       0  4968.5     .09       0
  5047.1     .17       0  5178.9     .11       0    5346     .17       0
  5951.4     .11       0  6040.2     .17       0
#XS Ineff= 1 ,-1
    4500  4795.3  305.74
Permanent Ineff=
       F
Bank Sta=4968.5,5047.1
XS Rating Curve= 0 ,0
Exp/Cntr=0.3,0.1

Type RM Length L Ch R = 1 ,27105   ,309,309,309
BEGIN DESCRIPTION:
WFSJR 077 3.0
END DESCRIPTION:
XS GIS Cut Line= 3
      3740490.17     10264014.44      3738853.88     10264222.77
      3737011.05     10264296.48
#Sta/Elev= 30
  3013.8  317.76  3072.1  317.79  3423.5  313.41  3859.5  303.81  3983.9   300.9
  4014.1  296.42  4034.3  301.05  4094.8  299.46  4168.6  300.33  4372.4  307.61
  4558.5  307.95  4658.8   304.7  4719.4  304.95  4799.4  298.86  4819.1  299.91
  4950.5  301.82  4969.6  301.05  4989.6  299.72  4995.4  297.98  4998.2  294.13
  5019.6  297.22  5029.6  301.06  5099.7  300.46  5199.8  303.23  5309.8  303.09
    5510   308.3  5710.2  310.53  5880.3  314.85  6110.5  317.69  6507.6  325.56
#Mann= 8 ,-1 , 0
  3013.8     .11       0  3072.1     .17       0  3859.5     .11       0
  4168.6     .17       0  4819.1     .11       0  4950.5     .17       0
  4969.6     .09       0  5029.6     .17       0
#XS Ineff= 1 ,-1
    3550  4558.5  307.95
Permanent Ineff=
       F
Bank Sta=4969.6,5029.6
XS Rating Curve= 0 ,0
Exp/Cntr=0.3,0.1

Type RM Length L Ch R = 1 ,26796   ,606,606,606
BEGIN DESCRIPTION:
WFSJR 077 2.0
END DESCRIPTION:
XS GIS Cut Line= 3
      3740490.17     10263862.53      3738528.22     10263947.84
      3737048.35     10264005.75
#Sta/Elev= 30
  3036.2  318.57  3148.6  321.01  3248.7  316.14  3468.9  313.09    3539  314.11
  3689.1  307.66  3982.1  301.03  4158.1  300.19  4199.6  300.42    4207  295.17
  4207.4  294.67  4212.2  295.17  4219.6  298.18  4257.1  300.04  4449.8  306.74
  4489.9  310.45  4860.2  299.61  4950.1  299.79  4980.3  300.19  4990.4  299.23
  4997.7  295.18  5010.4  295.39  5030.4  300.05  5110.5  299.03  5167.8  301.36
  5460.7  303.83  5500.8  306.58  5650.9  306.23  5730.9  309.18    6481  321.77
#Mann= 10 ,-1 , 0
  3036.2     .17       0  3982.1     .11       0  4158.1     .15       0
    4207     .11       0  4212.2     .15       0  4257.1     .17       0
  4950.1     .15       0  4980.3     .07       0  5030.4     .15       0
  5167.8     .17       0
#XS Ineff= 1 ,-1
    3500  4479.9  310.42
Permanent Ineff=
       F
Bank Sta=4980.3,5030.4
XS Rating Curve= 0 ,0
Exp/Cntr=0.3,0.1

Type RM Length L Ch R = 1 ,26190   ,1043,1043,1043
BEGIN DESCRIPTION:
WFSJR 077 1.0
END DESCRIPTION:
XS GIS Cut Line= 3
      3740485.83       10263741.      3738307.01     10263437.18
      3737001.73      10263784.1
#Sta/Elev= 30
  2993.4  317.71  3526.5  309.92  3943.9  300.33  3990.9  299.21    4009  294.52
  4021.2  295.22  4039.6  299.25  4051.5  297.84  4207.3   300.3  4232.5  300.44
    4415  303.91    4622  300.35  4657.3  298.39  4748.7  298.53  4908.2  296.55
  4970.3  297.97  4979.7  297.13  4988.3  293.24  5020.8  298.15  5072.8  297.03
  5254.5  302.76  5699.9  309.91  5782.2  315.48  5844.3  317.37  5925.3  317.45
  6010.8  314.54  6126.1  314.51  6330.6  318.65  6431.9  316.94  6543.9  320.02
#Mann= 9 ,-1 , 0
  2993.4     .17       0  3943.9     .11       0    4009     .15       0
  4207.3     .11       0  4232.5     .17       0  4748.7     .11       0
  4970.3     .07       0  5020.8     .11       0  5072.8     .17       0
#XS Ineff= 1 ,-1
    3650  4407.4  303.91
Permanent Ineff=
       F
Bank Sta=4970.3,5020.8
XS Rating Curve= 0 ,0
Exp/Cntr=0.3,0.1