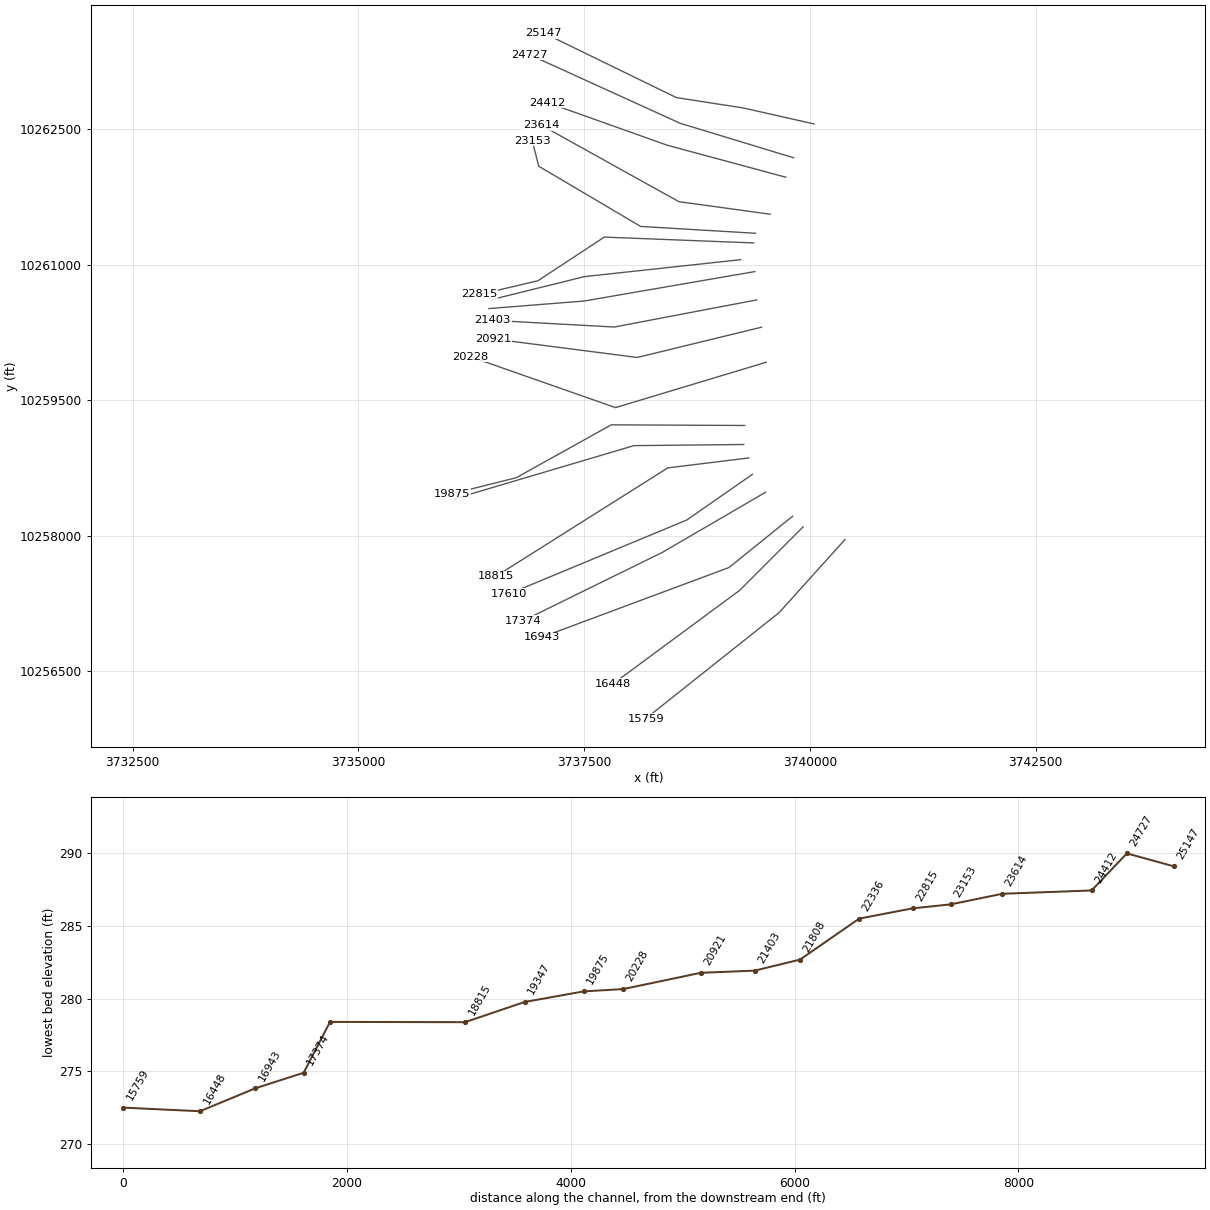
HEC-RAS study ROCKY CREEK.prj: ROCKY CREEK Base Level Engineering

--- ROCKY CREEK.g01 (geometry) --- (continued)

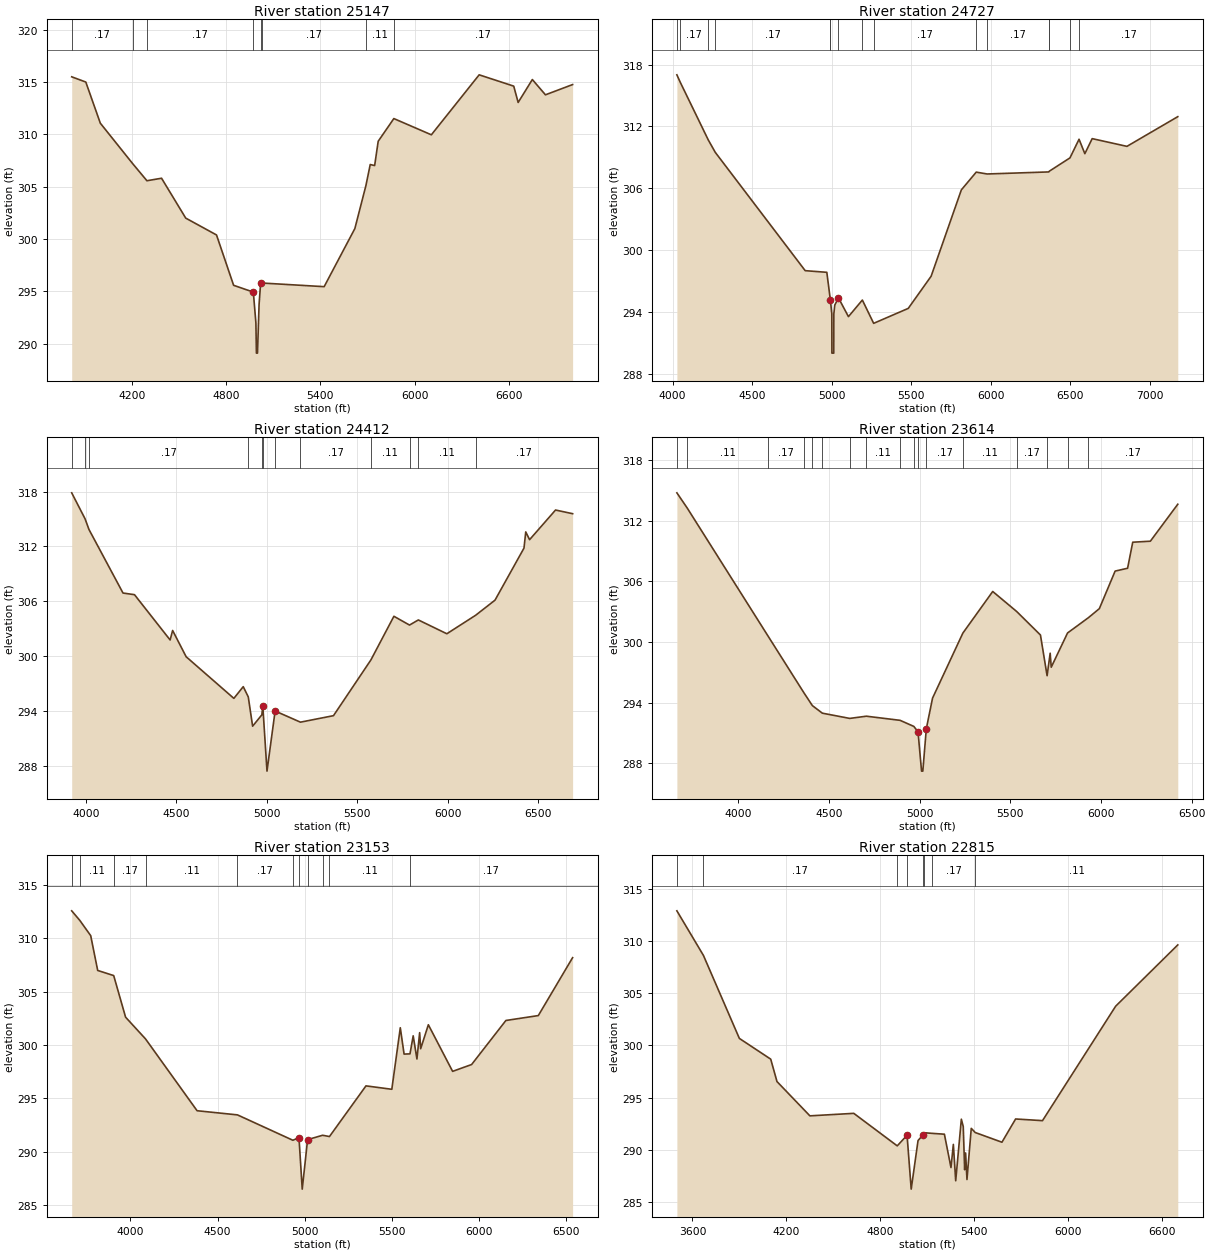
Type RM Length L Ch R = 1 ,25147   ,420,420,420
BEGIN DESCRIPTION:
ROCKY CREEK 42.0
END DESCRIPTION:
XS GIS Cut Line= 4
      3740045.36      10262561.5      3739260.59      10262738.6
      3738521.01     10262853.18      3737052.59      10263568.3
#Sta/Elev= 30
  3818.7  315.51  3908.4  315.01  4000.7  311.08  4206.2  307.22  4297.2  305.58
  4390.2  305.82    4544  302.01  4739.8   300.4  4848.6  295.59    4974  294.94
  4990.3     292  4993.6  289.11  5000.4  289.11  5010.5  293.75  5020.6  295.84
  5026.6  295.81  5424.5  295.46  5619.8  301.01  5690.3  305.13  5717.6  307.13
  5745.7  307.03  5768.2  309.35  5867.8  311.52  6106.4  309.97  6410.5   315.7
  6630.4  314.62  6658.5  313.06  6748.7  315.25  6832.2  313.79  7004.9  314.77
#Mann= 8 ,-1 , 0
  3818.7     .17       0  4206.2     .11       0  4297.2     .17       0
    4974     .09       0  5020.6     .15       0  5026.6     .17       0
  5690.3     .11       0  5867.8     .17       0
Bank Sta=4974,5020.6
XS Rating Curve= 0 ,0
Exp/Cntr=0.3,0.1

Type RM Length L Ch R = 1 ,24727   ,315,315,315
BEGIN DESCRIPTION:
ROCKY CREEK 41.0
END DESCRIPTION:
XS GIS Cut Line= 3
       3739819.6     10262186.52      3738561.88     10262568.93
      3736892.68     10263328.81
#Sta/Elev= 30
  4027.1     317    4047  316.32  4224.2  310.69  4268.4  309.48  4833.7     298
  4969.6  297.84  4990.9  295.28  4991.9  295.16    5001  293.81  5001.5     290
  5013.2     290  5013.7  293.81  5019.6  294.66  5042.8  295.36  5105.5  293.54
  5192.9  295.15    5264  292.89  5481.5  294.34  5625.3  297.46  5815.3  305.84
  5908.8  307.56  5977.1  307.38  6365.4  307.58  6368.2  307.65  6497.9  308.94
  6555.1  310.75  6591.5  309.35  6637.6  310.81  6856.1  310.06  7175.7  312.94
#Mann= 15 ,-1 , 0
  4027.1     .11       0    4047     .17       0  4224.2     .11       0
  4268.4     .17       0  4990.9     .17       0  4991.9     .09       0
  5042.8     .17       0  5192.9     .17       0    5264     .17       0
  5908.8     .11       0  5977.1     .17       0  6365.4     .11       0
  6368.2     .17       0  6497.9     .11       0  6555.1     .17       0
Bank Sta=4991.9,5042.8
XS Rating Curve= 0 ,0
Exp/Cntr=0.3,0.1

Type RM Length L Ch R = 1 ,24412   ,798,798,798
BEGIN DESCRIPTION:
ROCKY CREEK 40.0
END DESCRIPTION:
XS GIS Cut Line= 3
       3739732.8     10261971.24      3738420.31      10262325.4
       3737093.9     10262797.63
#Sta/Elev= 30
  3922.7  317.86  3996.5  315.02  4018.2  313.85  4206.1  306.91  4269.6  306.73
  4466.4  301.78  4480.3  302.82  4554.9  299.95  4818.6   295.4  4870.4  296.68
  4898.2  295.56  4922.2  292.36  4973.2   293.6  4978.4  294.59  5001.6  287.45
  5046.5  294.02  5186.4   292.8    5369  293.51  5575.7   299.6  5702.8  304.37
    5789  303.41  5837.8  303.97  5995.2  302.46  6154.3  304.48  6261.3  306.13
  6421.5  311.82  6431.2  313.59  6452.4  312.74  6595.8  315.98  6690.1  315.58
#Mann= 12 ,-1 , 0
  3922.7     .17       0  3996.5     .11       0  4018.2     .17       0
  4898.2     .15       0  4973.2     .12       0  4978.4     .09       0
  5046.5     .15       0  5186.4     .17       0  5575.7     .11       0
    5789     .17       0  5837.8     .11       0  6154.3     .17       0
Bank Sta=4978.4,5046.5
XS Rating Curve= 0 ,0
Exp/Cntr=0.3,0.1

Type RM Length L Ch R = 1 ,23614   ,461,461,461
BEGIN DESCRIPTION:
ROCKY CREEK 39.0
END DESCRIPTION:
XS GIS Cut Line= 3
      3739559.16     10261561.52      3738548.79      10261700.4
      3737025.89     10262546.84
#Sta/Elev= 30
  3661.4  314.78  3718.5  313.27  4162.9  300.63  4363.3  294.94  4408.5  293.71
  4463.5  292.96  4614.7  292.44  4706.1  292.66  4892.2  292.25  4967.9  291.65
  4991.2  291.12  5010.6  287.22  5017.6  287.22    5037  291.43  5071.3  294.45
  5238.5  300.89  5403.1  305.01  5535.1  303.03  5666.3   300.7  5702.9  296.67
  5719.9   298.9  5725.7  297.51  5815.7   300.9  5931.1  302.42    5991  303.31
  6078.1  307.03  6146.8  307.31  6175.2  309.89  6272.4  309.99  6423.6  313.65
#Mann= 17 ,-1 , 0
  3661.4     .17       0  3718.5     .11       0  4162.9     .17       0
  4363.3     .11       0  4408.5     .17       0  4463.5     .11       0
  4614.7     .17       0  4706.1     .11       0  4892.2     .17       0
  4967.9     .15       0  4991.2     .09       0    5037     .17       0
  5238.5     .11       0  5535.1     .17       0  5702.9     .15       0
  5815.7     .11       0  5931.1     .17       0
Bank Sta=4991.2,5037
XS Rating Curve= 0 ,0
Exp/Cntr=0.3,0.1

Type RM Length L Ch R = 1 ,23153   ,338,338,338
BEGIN DESCRIPTION:
ROCKY CREEK 38.0
END DESCRIPTION:
XS GIS Cut Line= 4
      3739396.84     10261350.44      3738125.18      10261426.1
       3736996.7     10262092.76      3736923.96      10262376.8
#Sta/Elev= 30
  3662.4  312.58  3709.6  311.67  3771.6  310.25  3811.7  306.99  3903.6  306.51
  3971.9  302.61  4086.6  300.57  4382.7  293.84  4614.7  293.45  4933.2  291.07
  4968.1  291.32  4986.8  286.49  5017.6  291.13  5104.1  291.54  5143.3  291.42
  5353.1  296.17  5501.5  295.85  5550.2  301.62    5572  299.15  5605.9  299.17
  5624.3  300.86  5645.8  298.69  5661.4  301.16  5667.2  299.65  5711.4   301.9
  5850.8  297.53  5959.9  298.17  6156.9   302.3  6343.2  302.76  6540.2  308.19
#Mann= 11 ,-1 , 0
  3662.4     .17       0  3709.6     .11       0  3903.6     .17       0
  4086.6     .11       0  4614.7     .17       0  4933.2     .15       0
  4968.1     .09       0  5017.6     .15       0  5104.1     .17       0
  5143.3     .11       0  5605.9     .17       0
Bank Sta=4968.1,5017.6
XS Rating Curve= 0 ,0
Exp/Cntr=0.3,0.1

Type RM Length L Ch R = 1 ,22815   ,479,479,479
BEGIN DESCRIPTION:
ROCKY CREEK 37.0
END DESCRIPTION:
XS GIS Cut Line= 4
      3739376.58      10261243.4       3737722.4     10261308.04
      3736987.09     10260824.18      3736341.66     10260672.91
#Sta/Elev= 30
  3500.7  312.92  3670.3  308.64  3899.7  300.68  4099.9  298.69  4139.9  296.54
  4350.1  293.25  4630.3  293.49  4907.8  290.37  4970.6  291.39    4997  286.22
  5040.6  290.88  5070.6  291.39  5081.8  291.63  5130.7  291.57  5208.9  291.49
    5251  288.29  5266.1  290.51  5281.2  287.02  5317.2  292.93  5329.3  292.23
  5338.4  288.08  5344.4  289.69  5353.1  287.14  5380.5  292.05  5405.9  291.65
  5576.4  290.72  5663.7  292.95  5835.4  292.79  6302.6  303.77  6699.3  309.65
#Mann= 8 ,-1 , 0
  3500.7     .11       0  3670.3     .17       0  4907.8     .15       0
  4970.6     .09       0  5070.6     .12       0  5081.8     .15       0
  5130.7     .17       0  5405.9     .11       0
Bank Sta=4970.6,5070.6
XS Rating Curve= 0 ,0
Exp/Cntr=0.3,0.1

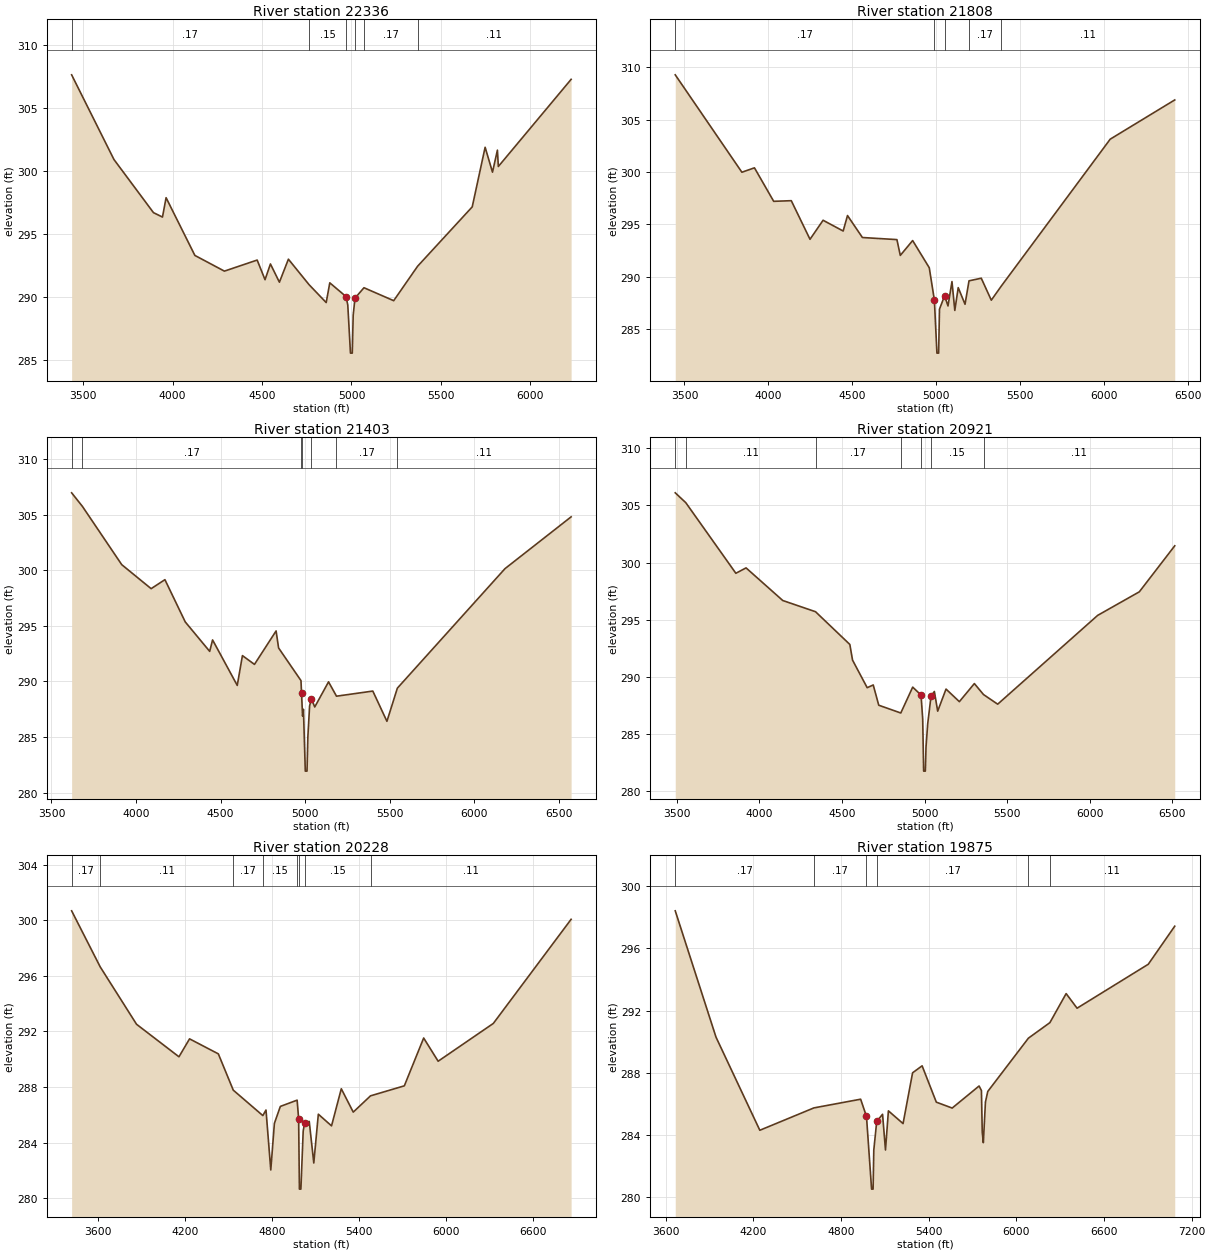
Type RM Length L Ch R = 1 ,22336   ,528,528,528
BEGIN DESCRIPTION:
ROCKY CREEK 36.0
END DESCRIPTION:
XS GIS Cut Line= 3
      3739232.83     10261058.04      3737503.65     10260870.54
      3736481.11     10260617.51
#Sta/Elev= 30
  3435.5  307.64  3671.9  300.91  3893.1  296.68  3943.4  296.33  3963.6  297.87
  4124.5  293.28  4289.6  292.03  4472.8  292.91  4516.8  291.35    4547   292.6
  4597.2  291.15  4647.5  292.98  4763.2  290.95  4858.8  289.53  4878.9   291.1
  4969.4  290.01  4979.5  289.34  4994.5  285.51  5004.6  285.51  5009.7  288.52
  5019.7  289.88    5070  290.71  5236.2  289.68  5369.9  292.42  5675.3  297.14
  5747.4  301.88  5788.6   299.9  5816.1  301.65  5821.3  300.35  6228.2  307.28
#Mann= 6 ,-1 , 0
  3435.5     .17       0  4763.2     .15       0  4969.4     .09       0
  5019.7     .15       0    5070     .17       0  5369.9     .11       0
Bank Sta=4969.4,5019.7
XS Rating Curve= 0 ,0
Exp/Cntr=0.3,0.1

Type RM Length L Ch R = 1 ,21808   ,405,405,405
BEGIN DESCRIPTION:
ROCKY CREEK 35.0
END DESCRIPTION:
XS GIS Cut Line= 3
       3739389.1      10260926.1      3737499.95     10260600.14
      3736444.64     10260516.38
#Sta/Elev= 30
  3445.1  309.29  3842.1  299.98    3917   300.4  4031.6   297.2  4136.4  297.26
    4248  293.57  4325.8  295.39  4445.5  294.36  4471.3  295.84  4560.1  293.74
  4765.6  293.54  4785.9  292.03  4859.4  293.45  4958.4  290.85  4988.8  287.77
  5004.1  282.69  5014.2  282.69  5019.3  286.89  5049.7  288.17    5070   287.2
  5093.7  289.53  5110.6  286.77  5130.9  288.95  5171.5  287.36  5195.2   289.6
  5268.2  289.85    5328  287.75  5387.1  289.09  6036.4  303.14  6420.8  306.89
#Mann= 5 ,-1 , 0
  3445.1     .17       0  4988.8     .09       0  5049.7     .15       0
  5195.2     .17       0  5387.1     .11       0
Bank Sta=4988.8,5049.7
XS Rating Curve= 0 ,0
Exp/Cntr=0.3,0.1

Type RM Length L Ch R = 1 ,21403   ,482,482,482
BEGIN DESCRIPTION:
ROCKY CREEK 34.0
END DESCRIPTION:
XS GIS Cut Line= 3
      3739409.48      10260612.3        3737833.     10260312.01
      3736487.55     10260385.73
#Sta/Elev= 30
  3619.2  306.96  3682.9  305.74  3915.3   300.5  4089.1  298.34  4170.6  299.15
  4290.7  295.35  4435.2   292.7  4452.3  293.73  4598.1  289.64  4628.7  292.32
  4699.9  291.53  4827.7  294.54  4842.4  293.01  4974.8  290.07    4978  288.98
  4984.2  286.88  4989.3  287.49  5000.3  281.93  5010.4  281.93  5015.5  285.03
  5025.7  287.78  5035.9  288.45  5056.2   287.7  5137.7  289.96  5184.7  288.67
  5399.4  289.13  5482.8  286.41  5544.4  289.39  6180.6  300.14  6571.5   304.8
#Mann= 7 ,-1 , 0
  3619.2     .11       0  3682.9     .17       0  4974.8     .12       0
    4978     .09       0  5035.9     .15       0  5184.7     .17       0
  5544.4     .11       0
#XS Ineff= 1 ,-1
    4300  4827.7  294.54
Permanent Ineff=
       F
Bank Sta=4978,5035.9
XS Rating Curve= 0 ,0
Exp/Cntr=0.3,0.1

Type RM Length L Ch R = 1 ,20921   ,693,693,693
BEGIN DESCRIPTION:
ROCKY CREEK 33.0
END DESCRIPTION:
XS GIS Cut Line= 3
      3739464.11      10260310.2      3738087.77     10259974.94
       3736495.4       10260180.
#Sta/Elev= 30
  3491.6   306.1  3555.3  305.24  3858.3  299.07    3920  299.54  4142.1  296.69
  4340.3  295.71  4547.9  292.85  4564.3  291.48  4652.9  289.07  4689.5  289.31
  4722.8  287.54  4856.2  286.86  4928.3  289.12  4978.7  288.43  4988.8  286.33
  4994.5  281.78  5004.7  281.78  5008.9   283.9    5019  285.91  5039.2  288.33
  5059.3  288.74  5079.5  287.02  5129.9  288.95  5210.6  287.85  5301.3  289.43
  5356.8  288.47  5442.5  287.63  6047.4  295.39  6299.5  297.45  6513.7  301.47
#Mann= 7 ,-1 , 0
  3491.6     .17       0  3555.3     .11       0  4340.3     .17       0
  4856.2     .15       0  4978.7     .09       0  5039.2     .15       0
  5356.8     .11       0
Bank Sta=4978.7,5039.2
XS Rating Curve= 0 ,0
Exp/Cntr=0.3,0.1

Type RM Length L Ch R = 1 ,20228   ,353,353,353
BEGIN DESCRIPTION:
ROCKY CREEK 32.0
END DESCRIPTION:
XS GIS Cut Line= 3
      3739516.25     10259922.19      3737846.96     10259419.59
      3736242.83     10259982.07
#Sta/Elev= 30
    3419  300.68  3615.8  296.65  3866.4  292.52  4158.8  290.18  4231.9  291.47
  4430.3  290.39  4533.2  287.78  4737.1  285.95  4758.8  286.35  4791.8  282.04
  4816.7  285.39  4857.8  286.61  4973.4  287.06  4983.8  285.73  4989.1  280.66
  4999.4  280.66  5015.2  284.83  5025.6  285.44  5056.9  285.53  5088.3  282.54
  5119.6  286.05  5210.6  285.21  5277.9  287.88  5360.3   286.2  5479.3  287.37
  5712.4  288.09  5845.8  291.53  5945.5  289.86    6326  292.58  6862.2  300.07
#Mann= 8 ,-1 , 0
    3419     .17       0  3615.8     .11       0  4533.2     .17       0
  4737.1     .15       0  4973.4     .12       0  4983.8     .09       0
  5025.6     .15       0  5479.3     .11       0
Bank Sta=4983.8,5025.6
XS Rating Curve= 0 ,0
Exp/Cntr=0.3,0.1

Type RM Length L Ch R = 1 ,19875   ,528,528,528
BEGIN DESCRIPTION:
ROCKY CREEK 31.0
END DESCRIPTION:
XS GIS Cut Line= 4
      3739276.67     10259221.67      3737800.01     10259228.85
      3736748.01     10258643.54      3736032.33     10258463.97
#Sta/Elev= 30
  3665.4  298.42  3944.2  290.29  4244.2  284.29  4614.2  285.73  4934.2  286.29
  4974.2  285.18  5009.1   280.5  5019.4   280.5  5024.2  283.01  5044.2  284.86
  5084.2  285.32  5104.2  283.02  5124.2  285.54  5224.5  284.72  5289.7  287.99
  5354.9  288.44  5452.1   286.1  5560.7  285.72  5744.8  287.14  5760.8  286.85
  5766.5  284.16  5773.9  283.49  5788.3  286.11  5804.3  286.79  6082.4  290.22
  6229.4  291.22  6340.6  293.09  6415.4  292.15  6902.8  294.98  7083.8  297.43
#Mann= 6 ,-1 , 0
  3665.4     .17       0  4614.2     .17       0  4974.2     .09       0
  5044.2     .17       0  6082.4     .15       0  6229.4     .11       0
#XS Ineff= 1 ,-1
  5354.9    5950  288.44
Permanent Ineff=
       F
Bank Sta=4974.2,5044.2
XS Rating Curve= 0 ,0
Exp/Cntr=0.3,0.1

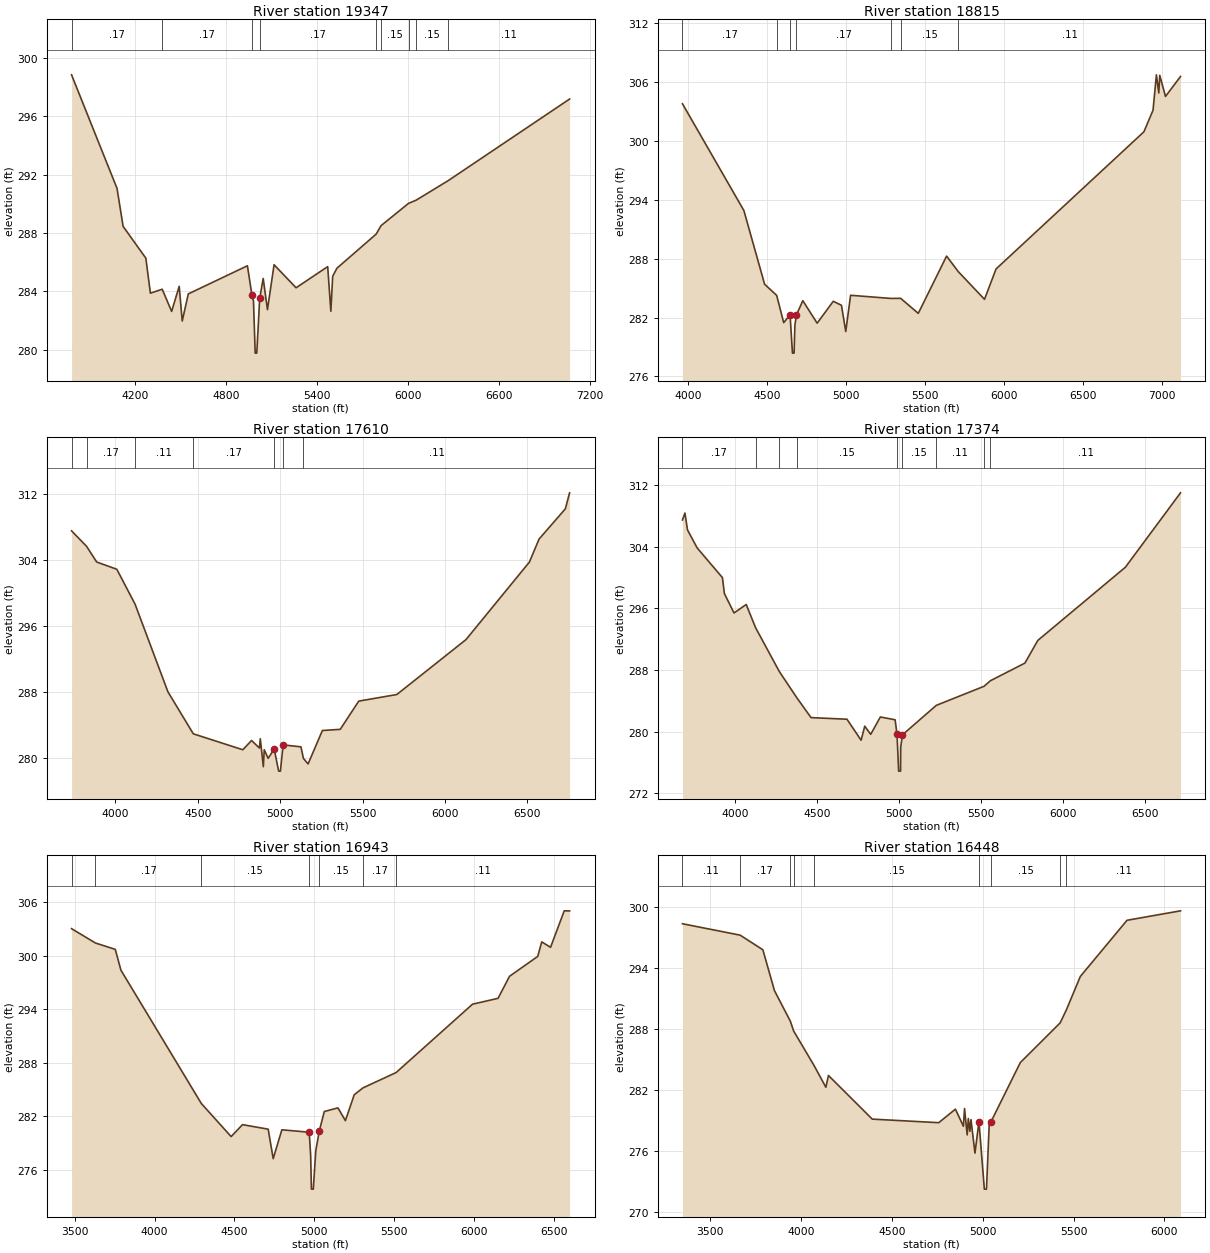
Type RM Length L Ch R = 1 ,19347   ,532,532,532
BEGIN DESCRIPTION:
ROCKY CREEK 30.0
END DESCRIPTION:
XS GIS Cut Line= 3
      3739267.81     10259011.07      3738050.17     10258998.42
      3736067.85     10258411.07
#Sta/Elev= 30
  3782.3  298.85  4082.3  291.06  4122.3  288.46  4272.3  286.28  4302.3  283.88
  4380.3  284.15  4442.3  282.63  4492.3  284.35  4512.3  281.97  4552.3  283.83
  4942.3  285.76  4972.3  283.73  4982.3  283.34  4993.5  279.77  5003.9  279.77
  5023.3  283.53  5046.4  284.89  5074.4  282.75  5118.1  285.83  5263.2  284.25
  5471.8   285.7  5492.6  282.64  5504.7  285.04  5532.7  285.59  5791.5  287.93
  5823.8  288.51  6005.3  290.04  6054.2  290.25  6267.3   291.6  7067.5  297.19
#Mann= 9 ,-1 , 0
  3782.3     .17       0  4380.3     .17       0  4972.3     .09       0
  5023.3     .17       0  5791.5     .17       0  5823.8     .15       0
  6005.3     .11       0  6054.2     .15       0  6267.3     .11       0
Bank Sta=4972.3,5023.3
XS Rating Curve= 0 ,0
Exp/Cntr=0.3,0.1

Type RM Length L Ch R = 1 ,18815   ,1205,1205,1205
BEGIN DESCRIPTION:
ROCKY CREEK 29.0
END DESCRIPTION:
XS GIS Cut Line= 3
      3739323.57      10258862.3      3738425.38     10258751.81
      3736525.61     10257553.47
#Sta/Elev= 30
    3964  303.77  4352.6   292.9  4483.6   285.4  4560.1  284.26  4604.5  281.48
  4644.8  282.29  4659.8  278.38  4670.2  278.38  4675.2  281.21  4685.1  282.27
  4725.4  283.72  4816.1  281.43  4918.2  283.66    4970  283.25  4997.1  280.58
  5027.7  284.27  5282.7  283.95  5344.4  283.96    5456  282.43    5635  288.26
  5709.6  286.67    5875  283.86    5948  286.95  6883.6  300.92  6941.3  303.12
  6962.5  306.72  6977.7  304.87  6983.7  306.67  7020.1  304.52  7115.1  306.55
#Mann= 7 ,-1 , 0
    3964     .17       0  4560.1     .17       0  4644.8     .09       0
  4685.1     .17       0  5282.7     .17       0  5344.4     .15       0
  5709.6     .11       0
#XS Ineff= 1 ,-1
    5635    6085  288.26
Permanent Ineff=
       F
Bank Sta=4644.8,4685.1
XS Rating Curve= 0 ,0
Exp/Cntr=0.3,0.1

Type RM Length L Ch R = 1 ,17610   ,236,236,236
BEGIN DESCRIPTION:
ROCKY CREEK 28.0
END DESCRIPTION:
XS GIS Cut Line= 3
      3739362.57     10258679.99      3738636.03     10258174.79
      3736662.48     10257354.65
#Sta/Elev= 30
  3734.4   307.5  3825.5  305.63  3886.9  303.73  4009.1  302.85  4119.8  298.62
    4319  288.01  4473.1  282.92  4773.4  280.99  4826.5  282.11  4874.2   281.2
  4879.6  282.32  4898.1  278.94  4903.5  280.99  4927.3  279.95  4963.9  281.08
  4991.1   278.4  5001.7   278.4    5018  281.58  5126.3  281.34  5141.3  279.94
  5169.6  279.27  5256.3  283.32  5364.6  283.46  5477.1  286.88  5708.1  287.68
  6127.7  294.33  6512.4  303.72  6571.2  306.51  6730.6  310.17  6756.5  312.11
#Mann= 7 ,-1 , 0
  3734.4     .11       0  3825.5     .17       0  4119.8     .11       0
  4473.1     .17       0  4963.9     .09       0    5018     .15       0
  5141.3     .11       0
Bank Sta=4963.9,5018
XS Rating Curve= 0 ,0
Exp/Cntr=0.3,0.1

Type RM Length L Ch R = 1 ,17374   ,431,431,431
BEGIN DESCRIPTION:
ROCKY CREEK 27.0
END DESCRIPTION:
XS GIS Cut Line= 3
      3739508.46     10258482.11      3738367.05     10257816.91
      3736826.12     10257060.21
#Sta/Elev= 30
  3678.9  307.47  3693.9  308.37  3709.6  306.18  3768.4  303.85  3922.7  299.99
  3934.6  297.93  3993.3  295.41  4067.8  296.51  4124.4  293.52  4270.1   287.8
  4378.2  284.36  4463.2  281.84  4682.3  281.63  4768.4  278.91  4790.7  280.73
  4827.1  279.67  4885.8  281.92  4975.9  281.56  4987.5  279.69  4997.5   274.9
  5009.1   274.9  5010.2  278.01  5020.2   279.6  5227.2  283.43  5518.3   285.9
  5556.9  286.62  5767.7  288.91  5846.3  291.85  6380.4  301.34  6716.7  310.99
#Mann= 9 ,-1 , 0
  3678.9     .17       0  4124.4     .11       0  4270.1     .17       0
  4378.2     .15       0  4987.5     .09       0  5020.2     .15       0
  5227.2     .11       0  5518.3     .17       0  5556.9     .11       0
Bank Sta=4987.5,5020.2
XS Rating Curve= 0 ,0
Exp/Cntr=0.3,0.1

Type RM Length L Ch R = 1 ,16943   ,495,495,495
BEGIN DESCRIPTION:
ROCKY CREEK 26.0
END DESCRIPTION:
XS GIS Cut Line= 3
      3739807.91     10258216.47      3739103.57     10257648.41
      3737027.69      10256875.7
#Sta/Elev= 30
  3480.3  303.03  3630.2  301.42  3754.2  300.71  3789.4  298.38  4293.2  283.43
  4479.9  279.72  4551.3  281.06    4712  280.55  4743.4  277.25  4797.6  280.48
    4969  280.21  4978.1  277.59  4982.8  273.83  4994.5  273.83  5010.1  278.13
  5031.5   280.3  5063.5  282.53  5148.9  282.94  5195.7  281.51    5251  284.41
  5305.7  285.18  5513.5   286.9  5991.8  294.56  6151.9  295.22  6223.9  297.69
  6400.5  299.92  6425.6  301.55  6480.9  300.94  6566.6  305.03  6600.2  305.02
#Mann= 7 ,-1 , 0
  3480.3     .11       0  3630.2     .17       0  4293.2     .15       0
    4969     .09       0  5031.5     .15       0  5305.7     .17       0
  5513.5     .11       0
Bank Sta=4969,5031.5
XS Rating Curve= 0 ,0
Exp/Cntr=0.3,0.1

Type RM Length L Ch R = 1 ,16448   ,689,689,689
BEGIN DESCRIPTION:
ROCKY CREEK 25.0
END DESCRIPTION:
XS GIS Cut Line= 3
      3739925.07     10258099.26      3739222.58     10257396.25
      3737818.35     10256359.71
#Sta/Elev= 30
  3349.2  298.33  3666.5  297.21  3791.4  295.77  3855.1  291.76  3942.3  288.76
  3960.7  287.79  4074.5  284.35  4137.9  282.26  4152.1  283.42  4393.1  279.13
  4758.6  278.78  4850.4  280.11  4894.3  278.43  4900.5  280.17  4915.1  277.58
  4921.4  279.19  4929.8  277.93    4936  279.08  4957.9  275.79  4979.9  278.89
  5009.5  272.25  5021.2  272.25  5036.2  278.59  5044.6  278.82  5207.4  284.69
  5426.6  288.59  5461.2  289.89  5537.4  293.15  5794.2  298.67  6088.4   299.6
#Mann= 9 ,-1 , 0
  3349.2     .11       0  3666.5     .17       0  3942.3     .11       0
  3960.7     .17       0  4074.5     .15       0  4979.9     .09       0
  5044.6     .15       0  5426.6     .17       0  5461.2     .11       0
Bank Sta=4979.9,5044.6
XS Rating Curve= 0 ,0
Exp/Cntr=0.3,0.1

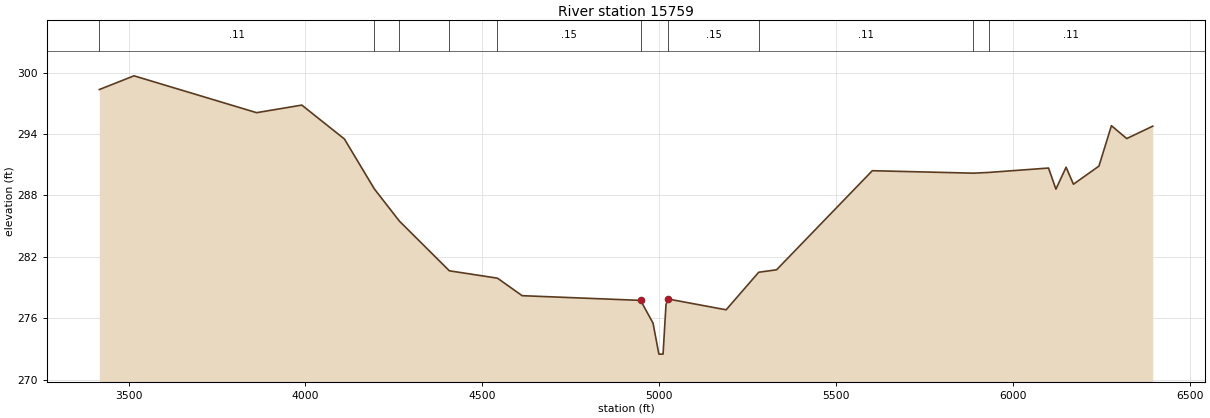
Type RM Length L Ch R = 1 ,15759   ,379,379,379
BEGIN DESCRIPTION:
ROCKY CREEK 24.0
END DESCRIPTION:
XS GIS Cut Line= 3
      3740388.62     10257958.64      3739657.95     10257148.23
      3738180.29     10255974.27
#Sta/Elev= 30
  3417.1  298.35  3515.1  299.69  3861.8  296.09  3989.6  296.83    4110  293.52
  4194.5  288.65  4265.4   285.5  4406.8  280.64  4542.8  279.92  4612.6  278.21
  4947.4  277.75  4982.6  275.53  4999.2   272.5    5011   272.5  5019.3  277.36
  5025.9  277.88  5189.3  276.83  5281.4   280.5  5331.9  280.74  5602.6  290.42
  5888.7  290.18  5931.5  290.25  6100.9  290.68  6121.7  288.62  6150.5  290.76
  6171.3   289.1  6243.4  290.87  6278.7  294.82  6321.9  293.56  6395.5  294.77
#Mann= 10 ,-1 , 0
  3417.1     .11       0  4194.5     .17       0  4265.4     .11       0
  4406.8     .17       0  4542.8     .15       0  4947.4     .09       0
  5025.9     .15       0  5281.4     .11       0  5888.7     .17       0
  5931.5     .11       0
Bank Sta=4947.4,5025.9
XS Rating Curve= 0 ,0
Exp/Cntr=0.3,0.1