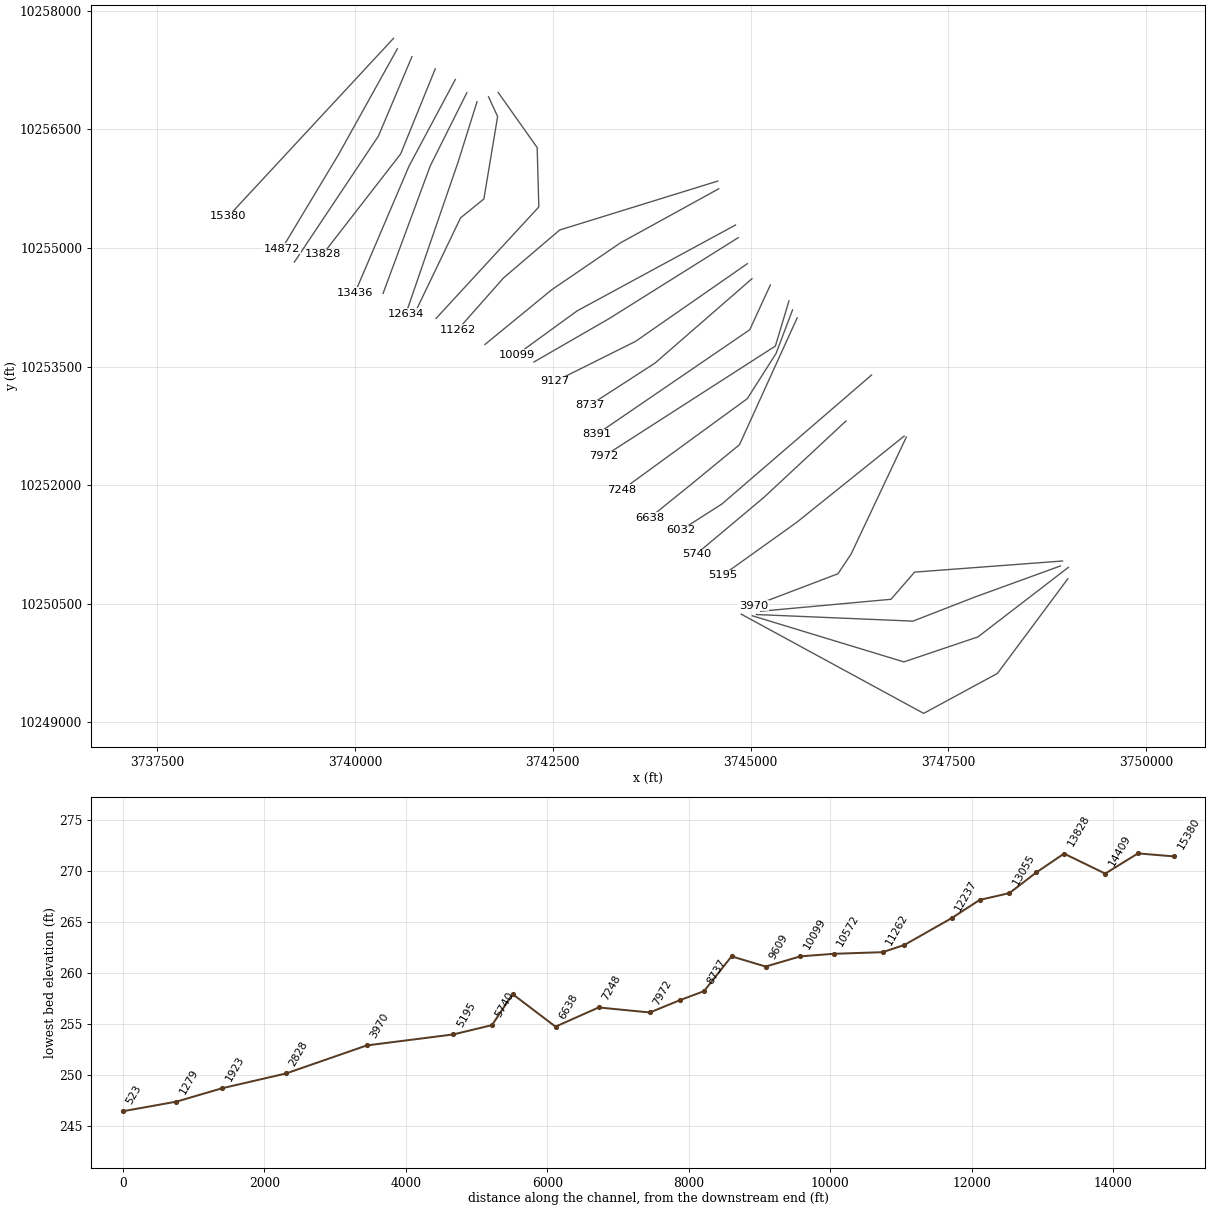
HEC-RAS study ROCKY CREEK.prj: ROCKY CREEK Base Level Engineering

--- ROCKY CREEK.g01 (geometry) --- (continued)

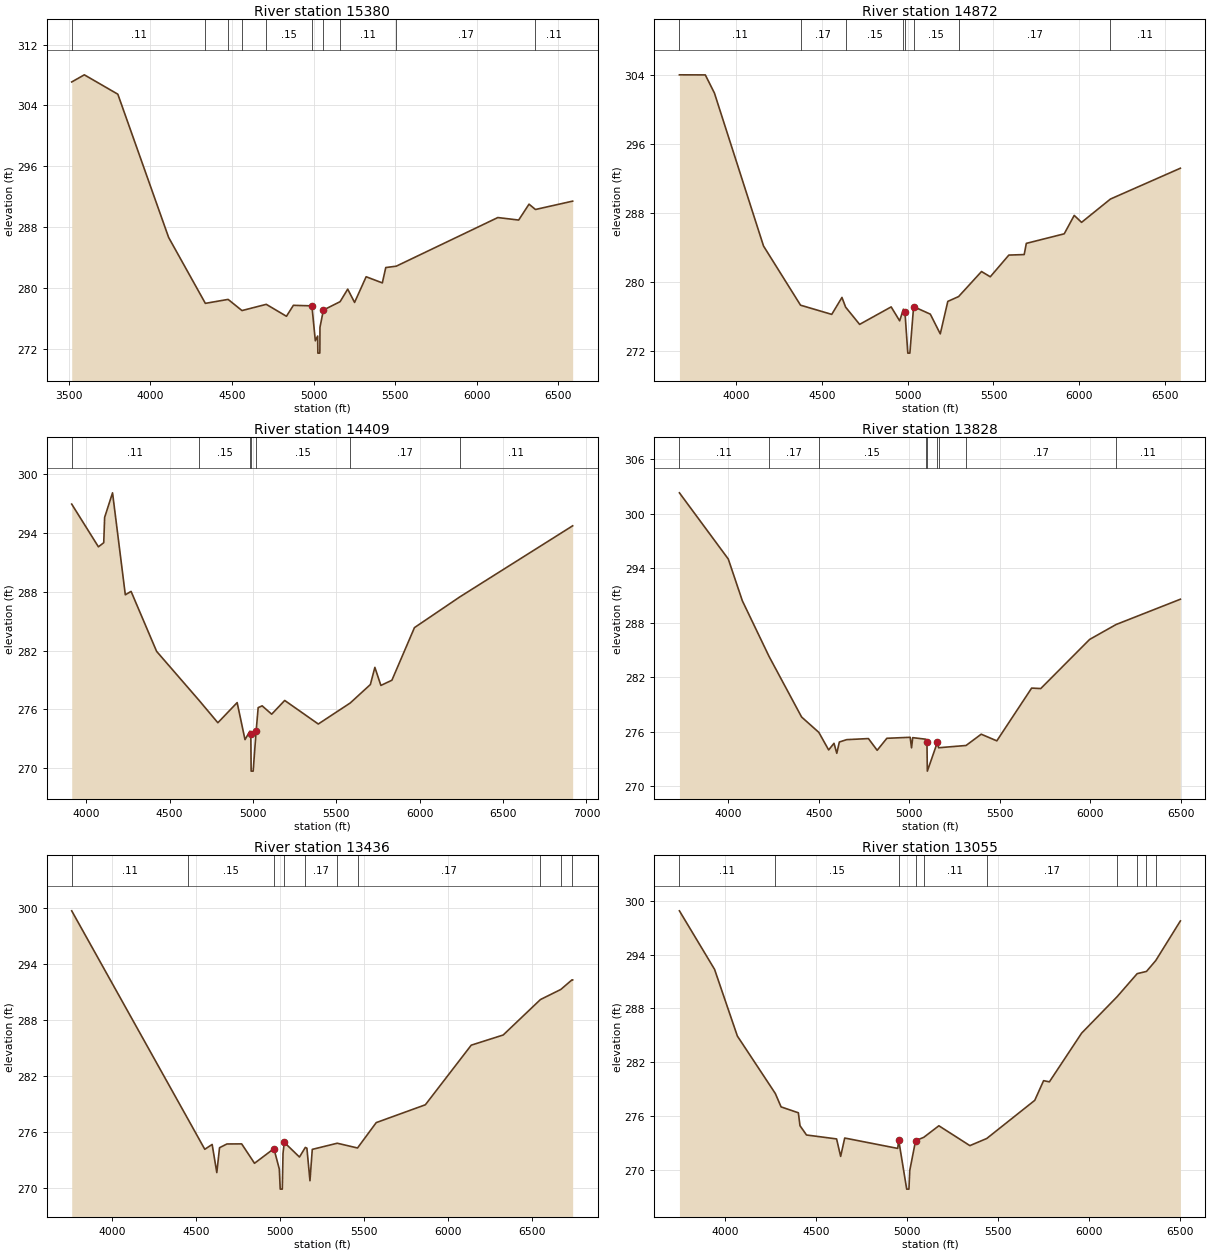
Type RM Length L Ch R = 1 ,15380   ,508,508,508
BEGIN DESCRIPTION:
ROCKY CREEK 23.0
END DESCRIPTION:
XS GIS Cut Line= 2
      3740486.73     10257651.37       3738399.9     10255401.34
#Sta/Elev= 30
  3518.8  307.09  3596.1  308.03  3801.4  305.48  4112.6  286.63  4337.5  277.96
  4476.9  278.48  4561.9  277.01  4710.7  277.83  4834.3  276.26  4876.8   277.7
  4990.2  277.63  5011.2  273.03  5025.4  273.66  5026.8  271.41  5038.6  271.41
  5039.1  271.91  5039.6   274.8  5060.6  277.08  5162.9  278.18  5209.6  279.83
  5251.6  278.08  5322.5  281.46  5421.7  280.65  5442.7  282.67  5506.9  282.85
  6129.2  289.25  6256.8  288.92  6320.3  291.01  6359.7  290.31  6587.6  291.41
#Mann= 10 ,-1 , 0
  3518.8     .11       0  4337.5     .17       0  4476.9     .11       0
  4561.9     .17       0  4710.7     .15       0  4990.2     .09       0
  5060.6     .15       0  5162.9     .11       0  5506.9     .17       0
  6359.7     .11       0
Bank Sta=4990.2,5060.6
XS Rating Curve= 0 ,0
Exp/Cntr=0.3,0.1

Type RM Length L Ch R = 1 ,14872   ,463,463,463
BEGIN DESCRIPTION:
ROCKY CREEK 22.0
END DESCRIPTION:
XS GIS Cut Line= 3
      3740535.34     10257519.42      3739792.28     10256182.61
        3739077.     10254991.64
#Sta/Elev= 30
  3670.2  304.03  3821.1  304.02  3874.2  301.91  4160.3  284.14  4375.9  277.27
  4557.7   276.2  4617.2  278.17  4638.6  277.04  4720.1  275.04  4903.9  277.07
  4953.4  275.45  4975.2   276.8    4984  276.53  5000.9   271.7  5012.9   271.7
  5034.7   277.1  5131.9  276.23    5190  273.94    5234  277.71  5296.8  278.27
  5430.3  281.18  5481.4  280.57  5589.6  283.09    5679  283.15  5691.4  284.45
  5912.2  285.56  5970.5   287.7  6013.2  286.89  6181.5   289.6  6588.9  293.18
#Mann= 8 ,-1 , 0
  3670.2     .11       0  4375.9     .17       0  4638.6     .15       0
  4975.2     .12       0    4984     .09       0  5034.7     .15       0
  5296.8     .17       0  6181.5     .11       0
Bank Sta=4984,5034.7
XS Rating Curve= 0 ,0
Exp/Cntr=0.3,0.1

Type RM Length L Ch R = 1 ,14409   ,581,581,581
BEGIN DESCRIPTION:
ROCKY CREEK 21.0
END DESCRIPTION:
XS GIS Cut Line= 3
      3740719.35     10257418.69      3740296.69     10256417.12
      3739233.26     10254821.52
#Sta/Elev= 30
  3912.9  296.92  4073.1  292.57    4105  292.99  4110.4  295.57  4157.8  298.07
  4234.4  287.68  4268.9  288.03  4422.1  281.92  4676.7  276.93  4789.5  274.65
  4905.2   276.7  4952.3  272.93  4981.8  273.79  4987.2  273.54  4989.1  269.72
  5001.2  269.72  5019.1  273.81  5031.3  276.19  5055.2  276.37  5112.3  275.52
  5190.4  276.92  5391.8  274.52  5583.3  276.66  5704.2  278.54  5731.2  280.29
  5767.3  278.45  5833.4  278.98  5968.7  284.34  6240.9  287.47  6917.5  294.71
#Mann= 7 ,-1 , 0
  3912.9     .11       0  4676.7     .15       0  4981.8     .12       0
  4987.2     .09       0  5019.1     .15       0  5583.3     .17       0
  6240.9     .11       0
#XS Ineff= 1 ,-1
  5731.2    5870  280.29
Permanent Ineff=
       F
Bank Sta=4987.2,5019.1
XS Rating Curve= 0 ,0
Exp/Cntr=0.3,0.1

Type RM Length L Ch R = 1 ,13828   ,392,392,392
BEGIN DESCRIPTION:
ROCKY CREEK 20.0
END DESCRIPTION:
XS GIS Cut Line= 3
      3741014.49     10257265.93        3740577.     10256189.55
      3739594.34     10254922.16
#Sta/Elev= 30
  3730.8  302.28  4000.6     295  4078.2  290.41    4226  284.28  4405.3  277.63
  4500.5  275.94  4554.7  274.01  4584.2  274.74  4599.6  273.64  4613.7  274.88
  4653.6  275.14  4774.3  275.26  4822.5  273.97    4876  275.29  5004.6   275.4
  5012.3  274.24  5018.7  275.36  5091.1  275.19  5097.4  274.83  5099.5  271.68
  5155.4  274.87  5161.7  274.25  5313.2   274.5  5396.9  275.74  5483.1  275.01
  5675.3  280.81  5725.7  280.76  5995.4  286.16  6141.5   287.8  6496.4  290.58
#Mann= 9 ,-1 , 0
  3730.8     .11       0    4226     .17       0  4500.5     .15       0
  5091.1     .12       0  5097.4     .09       0  5155.4     .12       0
  5161.7     .15       0  5313.2     .17       0  6141.5     .11       0
Bank Sta=5097.4,5155.4
XS Rating Curve= 0 ,0
Exp/Cntr=0.3,0.1

Type RM Length L Ch R = 1 ,13436   ,381,381,381
BEGIN DESCRIPTION:
ROCKY CREEK 19.0
END DESCRIPTION:
XS GIS Cut Line= 3
      3741267.97     10257130.52      3740683.04     10256035.79
      3740000.61     10254436.07
#Sta/Elev= 30
  3758.8  299.67  4449.1  277.39  4550.5  274.11  4594.4  274.63    4622  271.61
  4638.3  274.28  4682.2  274.68    4770  274.69  4846.4  272.61  4961.8  274.18
    4994  271.99  4999.4  269.84  5011.7  269.84    5016  273.69  5023.7  274.85
  5113.8  273.28  5148.7  274.31  5158.1  274.23  5176.3  270.74    5190   274.1
  5338.7  274.76  5459.2  274.25  5570.5  276.97  5862.8  278.88  6135.8  285.27
  6325.9  286.36  6547.5  290.16  6668.5  291.24  6735.8  292.28  6739.2  292.26
#Mann= 10 ,-1 , 0
  3758.8     .11       0  4449.1     .15       0  4961.8     .09       0
  5023.7     .15       0  5148.7     .17       0  5338.7     .15       0
  5459.2     .17       0  6547.5     .11       0  6668.5     .17       0
  6735.8     .11       0
Bank Sta=4961.8,5023.7
XS Rating Curve= 0 ,0
Exp/Cntr=0.3,0.1

Type RM Length L Ch R = 1 ,13055   ,421,421,421
BEGIN DESCRIPTION:
ROCKY CREEK 18.0
END DESCRIPTION:
XS GIS Cut Line= 3
      3741413.81     10256963.88        3740952.     10256040.25
      3740354.86      10254425.9
#Sta/Elev= 30
  3750.1  298.91  3943.3  292.37  4068.6  284.92  4277.2   278.5    4309     277
    4404  276.34  4412.9   274.9  4448.7  273.86  4614.1  273.42  4636.5  271.47
  4658.8  273.52  4950.2  272.36  4955.5   273.3  4999.5  267.81  5011.8  267.81
  5016.4   269.9  5048.4  273.22  5093.4   273.6  5176.4  274.89    5347  272.67
  5439.7  273.47  5703.4  277.73  5752.1  279.93    5784   279.8  5961.1  285.24
  6156.1  289.31  6266.6  291.89  6317.8  292.14  6368.6  293.35    6504  297.78
#Mann= 10 ,-1 , 0
  3750.1     .11       0  4277.2     .15       0  4955.5     .09       0
  5048.4     .15       0  5093.4     .11       0  5439.7     .17       0
  6156.1     .11       0  6266.6     .17       0  6317.8     .11       0
  6368.6     .17       0
Bank Sta=4955.5,5048.4
XS Rating Curve= 0 ,0
Exp/Cntr=0.3,0.1

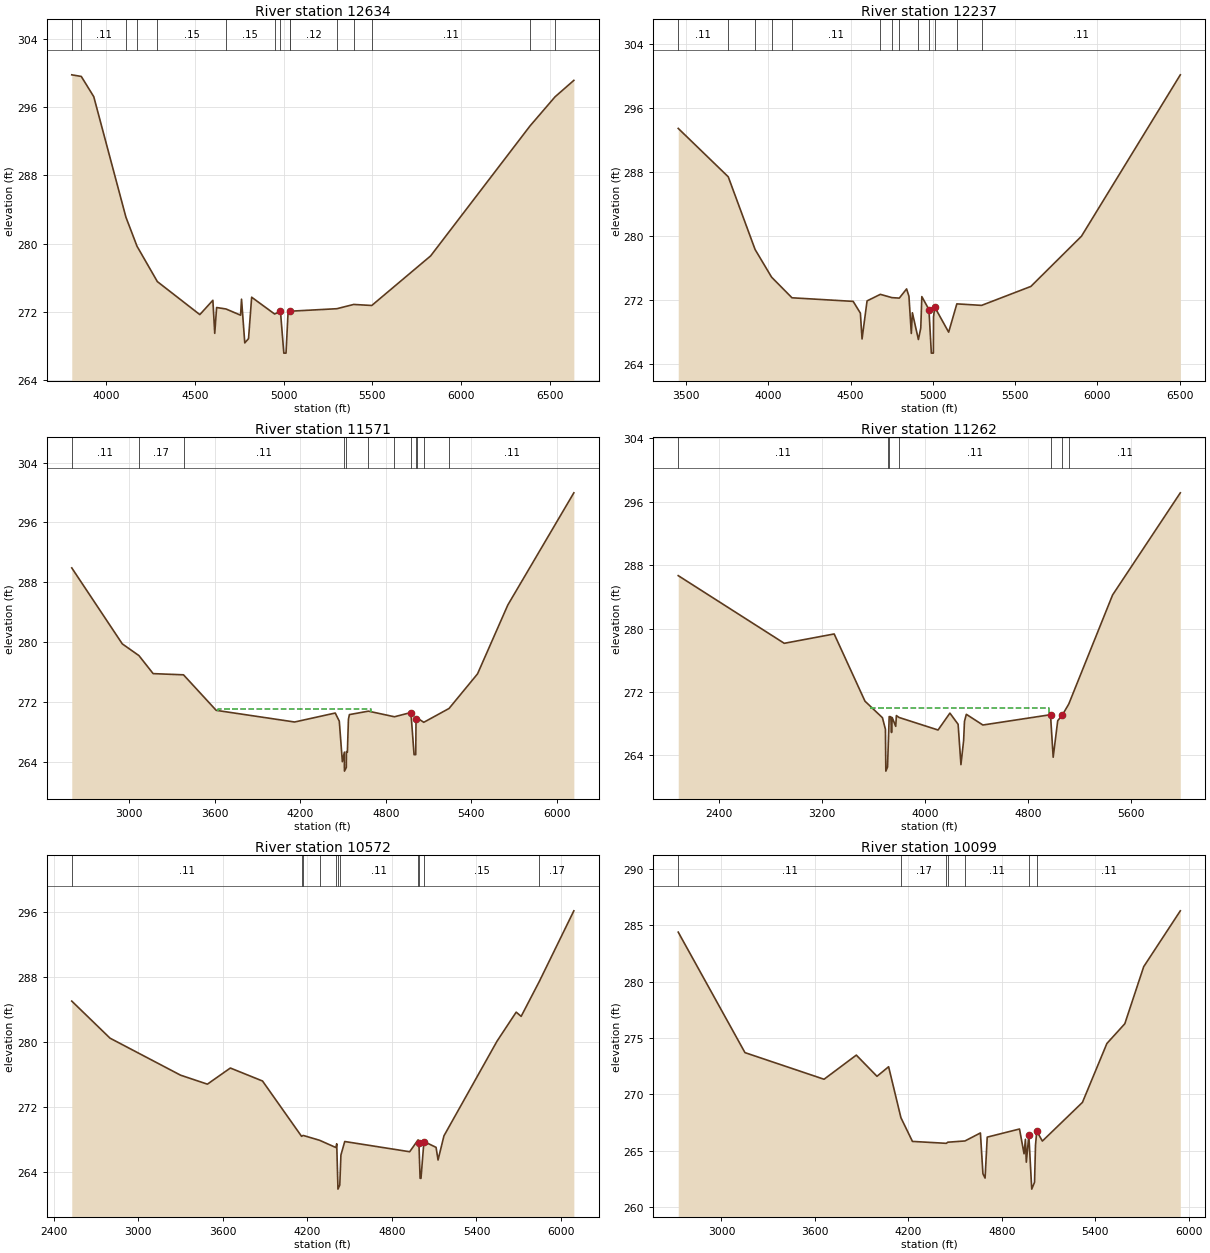
Type RM Length L Ch R = 1 ,12634   ,397,397,397
BEGIN DESCRIPTION:
ROCKY CREEK 17.0
END DESCRIPTION:
XS GIS Cut Line= 3
      3741542.27     10256849.25      3741306.17      10256095.8
      3740642.97      10254168.7
#Sta/Elev= 30
  3807.2  299.79  3860.8   299.6    3931  297.23  4112.2  283.09  4174.7  279.68
  4289.3  275.53  4528.4  271.66  4601.9  273.34  4612.4  269.46  4622.9  272.49
  4675.8  272.32  4757.9  271.59  4763.2  273.47  4781.6  268.34  4802.7  268.84
  4820.3   273.7  4949.5  271.73  4982.5  272.04  5001.5  267.14  5013.8  267.14
  5024.8  271.68  5033.6  272.05  5038.9  272.06  5299.8  272.35  5394.9  272.85
  5496.8  272.73  5828.5  278.55  6387.9  293.79  6528.9  297.21  6634.8  299.14
#Mann= 15 ,-1 , 0
  3807.2     .17       0  3860.8     .11       0  4112.2     .15       0
  4174.7     .11       0  4289.3     .15       0  4675.8     .15       0
  4949.5     .12       0  4982.5     .07       0  5033.6     .11       0
  5038.9     .12       0  5299.8     .11       0  5394.9     .11       0
  5496.8     .11       0  6387.9     .17       0  6528.9     .11       0
Bank Sta=4982.5,5033.6
XS Rating Curve= 0 ,0
Exp/Cntr=0.3,0.1

Type RM Length L Ch R = 1 ,12237   ,666,666,666
BEGIN DESCRIPTION:
ROCKY CREEK 16.0
END DESCRIPTION:
XS GIS Cut Line= 5
      3741688.09     10256911.82      3741802.69     10256661.77
      3741629.08     10255620.11      3741333.94     10255380.52
      3740754.08     10254172.19
#Sta/Elev= 30
  3452.8  293.45  3756.8   287.4  3919.9  278.31  4020.2  274.85  4144.1  272.27
    4516  271.82  4559.9  270.35    4570  267.12  4600.4  271.88  4681.1   272.7
  4751.6  272.29  4796.4  272.23  4840.7  273.38    4855  272.46  4869.4  267.81
  4875.9   270.4  4912.5  267.05  4926.9  268.49  4933.3  272.42  4976.5   270.8
  4991.1  265.35  5003.4  265.35  5004.4  269.87  5011.7  271.11  5096.4  267.97
  5146.1  271.51  5296.5  271.32    5596  273.69  5903.6  279.97  6504.3  300.15
#Mann= 13 ,-1 , 0
  3452.8     .11       0  3756.8     .17       0  3919.9     .15       0
  4020.2     .17       0  4144.1     .11       0  4681.1     .15       0
  4751.6     .11       0  4796.4     .15       0  4912.5     .11       0
  4976.5     .06       0  5011.7     .11       0  5146.1     .11       0
  5296.5     .11       0
#XS Ineff= 1 ,-1
    4065  4840.7  273.38
Permanent Ineff=
       F
Bank Sta=4976.5,5011.7
XS Rating Curve= 0 ,0
Exp/Cntr=0.3,0.1

Type RM Length L Ch R = 1 ,11571   ,309,309,309
BEGIN DESCRIPTION:
ROCKY CREEK 15.0
END DESCRIPTION:
XS GIS Cut Line= 4
      3741809.63     10256967.35      3742302.69     10256269.41
      3742323.53     10255519.41      3741024.93      10254109.7
#Sta/Elev= 30
  2597.3  289.91  2951.7  279.75  3068.5  278.18  3168.2  275.77    3381  275.61
  3610.2  270.86  4160.4   269.3  4445.3   270.5  4473.7  269.41  4495.2  263.99
  4509.4  265.27  4509.5  263.23    4510  262.73    4523  263.23  4523.6  265.34
  4530.4  265.25  4537.8  269.67  4544.6  270.29  4678.1  270.75  4860.6     270
  4976.1  270.57  4998.2  264.93  5009.9  264.93  5011.9  269.68  5018.7  269.85
  5066.4  269.26  5243.5  271.11  5443.4  275.74  5655.5  284.94  6118.8  299.95
#Mann= 12 ,-1 , 0
  2597.3     .11       0  3068.5     .17       0    3381     .11       0
  4509.5     .09       0    4523     .11       0  4678.1     .15       0
  4860.6     .12       0  4976.1     .07       0  5011.9     .11       0
  5018.7     .12       0  5066.4     .15       0  5243.5     .11       0
#XS Ineff= 1 ,-1
    3620  4693.2  271.02
Permanent Ineff=
       T
Bank Sta=4976.1,5011.9
XS Rating Curve= 0 ,0
Exp/Cntr=0.3,0.1

Type RM Length L Ch R = 1 ,11262   ,690,690,690
BEGIN DESCRIPTION:
ROCKY CREEK 14.0
END DESCRIPTION:
XS GIS Cut Line= 4
       3744583.9     10255845.79      3742587.42     10255227.51
      3741879.81     10254623.75      3741299.25     10253967.36
#Sta/Elev= 30
  2084.6  286.69  2907.5  278.15  3294.8  279.33  3533.8  270.85  3669.4  268.76
  3692.6   267.3  3695.8  262.02  3708.8  262.52  3721.8   268.9  3734.5  268.88
  3739.9  266.89  3745.1  268.78  3772.5  267.67  3777.7  269.03  3798.5  268.79
  4100.9  267.21    4193  269.34  4256.7  267.93  4278.7  262.84  4299.5  265.89
  4306.1   268.3  4320.4  269.19  4448.8  267.84  4973.7  269.14  4994.5  263.77
  5029.6  268.38  5065.9  269.11  5115.2  270.48  5455.5  284.25  5981.1  297.14
#Mann= 7 ,-1 , 0
  2084.6     .11       0  3708.8     .11       0  3721.8     .15       0
  3798.5     .11       0  4973.7     .09       0  5065.9     .15       0
  5115.2     .11       0
#XS Ineff= 1 ,-1
    3575  4959.4     270
Permanent Ineff=
       T
Bank Sta=4973.7,5065.9
XS Rating Curve= 0 ,0
Exp/Cntr=0.3,0.1

Type RM Length L Ch R = 1 ,10572   ,473,473,473
BEGIN DESCRIPTION:
ROCKY CREEK 13.0
END DESCRIPTION:
XS GIS Cut Line= 4
      3744597.81     10255748.57      3743354.78     10255064.55
      3742486.26     10254471.31        3741643.     10253779.85
#Sta/Elev= 30
  2529.4  285.04  2800.9  280.47  3300.9  275.91  3491.3   274.8  3654.2  276.79
  3882.4  275.19  4159.3  268.37  4170.8  268.48  4287.3  267.88  4403.8  266.98
  4408.6  267.45  4416.8  262.36  4417.3  261.86  4430.3  262.36  4438.4  266.06
  4465.5  267.73  4926.1  266.47  4985.7  267.93  4991.8  267.49    5000   263.2
  5006.3  263.18  5027.2  267.73  5113.3  267.01  5127.3  265.45  5169.2  268.43
    5546  280.11  5681.6  283.68  5716.8  283.16  5844.9  287.44  6090.5  296.17
#Mann= 11 ,-1 , 0
  2529.4     .11       0  4159.3     .17       0  4170.8     .11       0
  4287.3     .17       0  4403.8     .11       0  4416.8     .09       0
  4430.3     .11       0  4985.7     .12       0  4991.8     .09       0
  5027.2     .15       0  5844.9     .17       0
#XS Ineff= 1 ,-1
    4160  4985.7  267.93
Permanent Ineff=
       F
Bank Sta=4991.8,5027.2
XS Rating Curve= 0 ,0
Exp/Cntr=0.3,0.1

Type RM Length L Ch R = 1 ,10099   ,490,490,490
BEGIN DESCRIPTION:
ROCKY CREEK 12.0
END DESCRIPTION:
XS GIS Cut Line= 3
      3744809.64     10255290.25      3742807.44     10254204.39
      3742042.54     10253648.08
#Sta/Elev= 30
  2722.3  284.39  3150.8  273.71  3658.4  271.35  3865.7  273.49  3998.4  271.61
    4073  272.46  4152.1  267.94    4226  265.84  4443.1  265.67  4453.3  265.77
  4563.3  265.88  4662.4  266.59  4678.6  262.97  4692.4  262.59  4706.1  266.22
  4913.4  266.94  4942.6  264.74  4951.4  266.03  4957.1     264  4973.3  266.39
  4991.9  261.61  5009.9  262.22  5016.1   265.5  5024.2  266.75  5060.1  265.87
  5317.5   269.3  5474.4  274.52  5589.5  276.27  5710.8  281.33  5945.8  286.28
#Mann= 7 ,-1 , 0
  2722.3     .11       0  4152.1     .17       0  4443.1     .11       0
  4453.3     .15       0  4563.3     .11       0  4973.3     .06       0
  5024.2     .11       0
Bank Sta=4973.3,5024.2
XS Rating Curve= 0 ,0
Exp/Cntr=0.3,0.1

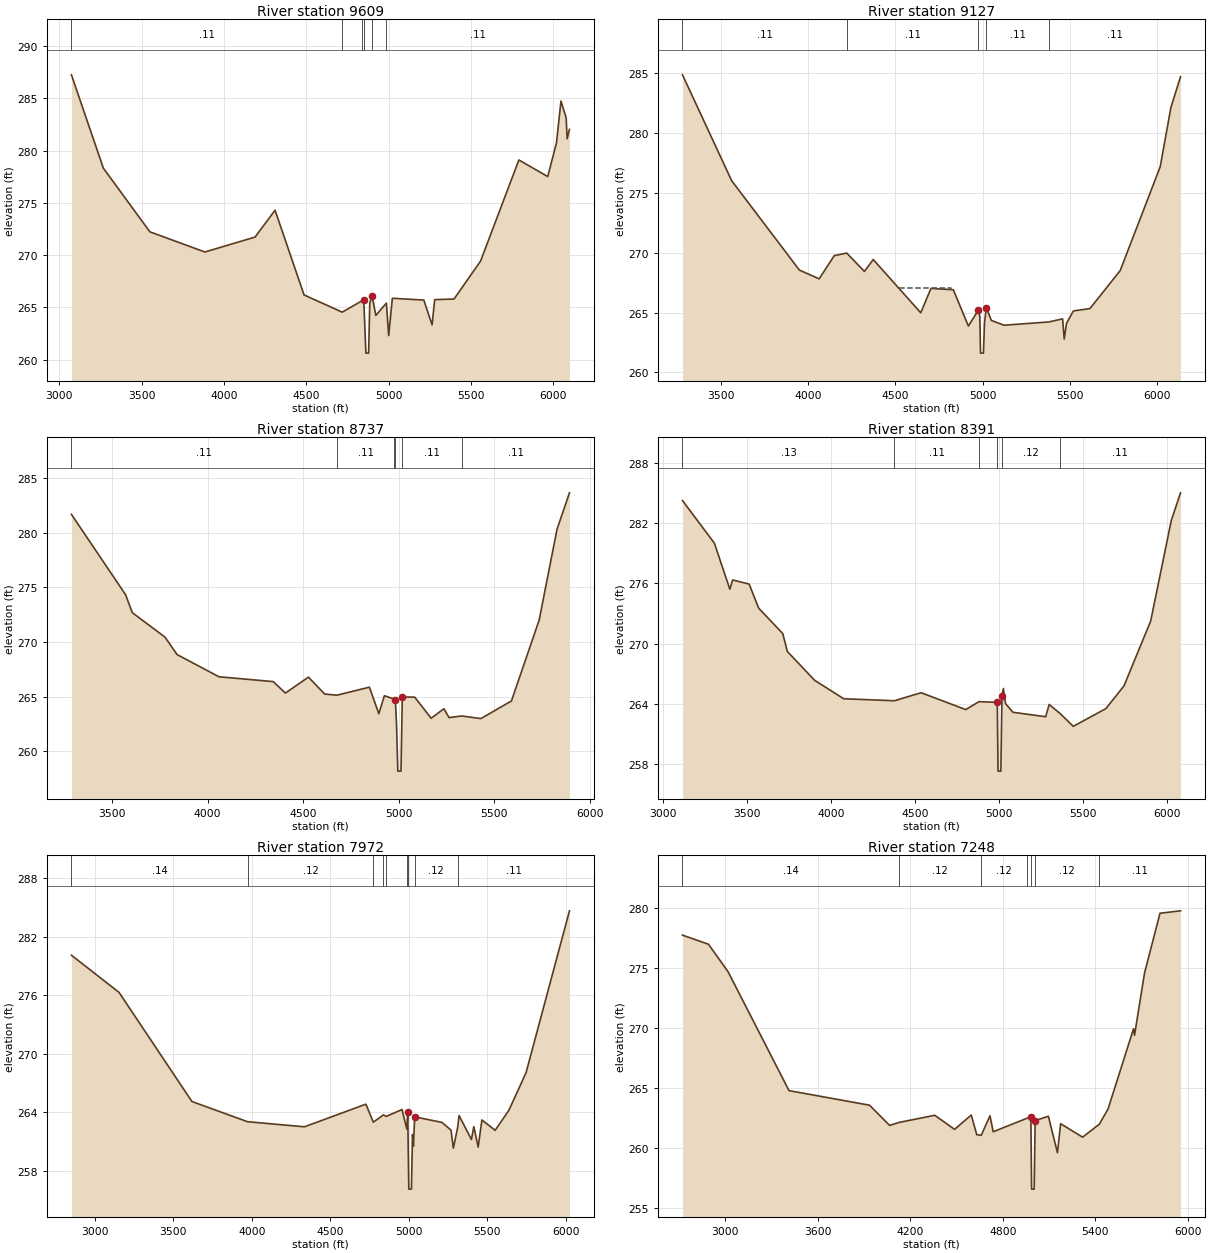
Type RM Length L Ch R = 1 ,9609    ,482,482,482
BEGIN DESCRIPTION:
ROCKY CREEK 11.0
END DESCRIPTION:
XS GIS Cut Line= 3
      3744844.35     10255130.52      3743212.17     10254106.73
      3742261.96     10253558.14
#Sta/Elev= 30
  3073.3  287.25  3266.9  278.32  3549.7  272.22  3883.7  270.29  4188.3  271.72
  4309.7  274.29  4485.7  266.18  4717.4  264.53  4839.8  265.64  4848.2  265.71
  4861.1  260.61  4877.7  260.61  4884.7   265.4  4898.9   266.1  4921.3  264.22
  4985.6   265.4  4999.6  262.29  5021.8  265.86  5212.8  265.69  5263.1  263.32
  5278.8  265.73  5396.6  265.79  5557.4  269.42  5790.2   279.1  5965.2  277.51
  6018.3  280.73  6045.7  284.74  6077.2  283.13    6083  281.13  6097.2  282.03
#Mann= 6 ,-1 , 0
  3073.3     .11       0  4717.4     .13       0  4839.8     .09       0
  4848.2     .06       0  4898.9     .13       0  4985.6     .11       0
Bank Sta=4848.2,4898.9
XS Rating Curve= 0 ,0
Exp/Cntr=0.3,0.1

Type RM Length L Ch R = 1 ,9127    ,390,390,390
BEGIN DESCRIPTION:
ROCKY CREEK 10.0
END DESCRIPTION:
XS GIS Cut Line= 3
      3744959.34     10254801.42      3743546.36     10253818.91
      3742531.15     10253312.98
#Sta/Elev= 30
    3279  284.84    3561     276  3949.3  268.54  4062.8  267.81  4149.2  269.75
  4220.8  269.96    4322  268.43  4372.7  269.42    4645  264.98  4703.5  267.01
  4831.8   266.9  4918.2  263.87  4974.9  265.19  4983.7  264.66  4987.7  261.61
  5004.3  261.61  5010.7  264.15  5020.7   265.4  5049.9  264.34  5122.6  263.94
  5378.2  264.21  5458.4  264.47  5467.6  262.79  5480.8   264.1    5520  265.13
  5615.1  265.33  5788.5   268.5    6018  277.17  6079.5  282.13  6134.3  284.68
#Mann= 5 ,-1 , 0
    3279     .11       0  4220.8     .11       0  4974.9     .06       0
  5020.7     .11       0  5378.2     .11       0
#XS Ineff= 1 ,-1
    4520  4816.9  267.02
Permanent Ineff=
       T
Bank Sta=4974.9,5020.7
XS Rating Curve= 0 ,0
Exp/Cntr=0.3,0.1

Type RM Length L Ch R = 1 ,8737    ,346,346,346
BEGIN DESCRIPTION:
ROCKY CREEK 9.0
END DESCRIPTION:
XS GIS Cut Line= 3
      3745017.82     10254611.05      3743791.06     10253543.54
      3742967.85     10253011.07
#Sta/Elev= 30
  3287.1  281.66  3570.5  274.32  3605.6  272.68  3776.5  270.45  3840.1  268.85
  4059.4  266.82  4343.4  266.38    4407  265.33  4527.5  266.79  4612.7  265.24
  4676.6  265.14  4846.6  265.87  4895.9  263.45  4925.1  265.09  4976.5  264.78
  4982.5  264.69  4988.6  262.51  4995.3   258.2  5011.9   258.2  5018.7  264.97
  5083.9  264.96  5169.8  263.03  5236.4   263.9  5263.5  263.09  5330.1  263.24
  5429.7     263    5590  264.61  5735.1     272  5828.7  280.31  5893.7  283.63
#Mann= 6 ,-1 , 0
  3287.1     .11       0  4676.6     .11       0  4976.5     .09       0
  4982.5     .06       0  5018.7     .11       0  5330.1     .11       0
#XS Ineff= 2 ,-1
    4038  4527.5  266.79    4570  4846.6  265.87
Permanent Ineff=
       T       T
Bank Sta=4982.5,5018.7
XS Rating Curve= 0 ,0
Exp/Cntr=0.3,0.1

Type RM Length L Ch R = 1 ,8391    ,419,419,419
BEGIN DESCRIPTION:
Mapping XS 9da61389
END DESCRIPTION:
XS GIS Cut Line= 3
      3745250.53      10254532.7      3744989.24     10253965.33
      3743057.24     10252645.01
#Sta/Elev= 30
  3116.6  284.25  3306.7     280  3398.5  275.42  3415.6  276.34  3513.3  275.93
  3570.3  273.53  3713.6     271  3740.8  269.22  3902.9  266.35  4076.3  264.51
  4378.4  264.31  4536.9  265.11    4803  263.43  4881.5  264.22  4990.5  264.15
  4995.1   257.3  5011.8   257.3  5018.4   264.8  5026.8  265.53  5039.4  264.03
  5084.1  263.16  5278.5  262.72  5299.5  263.94  5365.2  263.03    5443  261.76
  5637.4  263.53  5745.1   265.8  5903.6  272.24  6026.2  282.25  6081.3  285.02
#Mann= 6 ,-1 , 0
  3116.6     .13       0  4378.4     .11       0  4881.5     .12       0
  4990.5     .08       0  5018.4     .12       0  5365.2     .11       0
#XS Ineff= 1 ,-1
  5026.8    5740  265.53
Permanent Ineff=
       T
Bank Sta=4990.5,5018.4
XS Rating Curve= 0 ,0
Exp/Cntr=0.3,0.1

Type RM Length L Ch R = 1 ,7972    ,724,724,724
BEGIN DESCRIPTION:
ROCKY CREEK 8.0
END DESCRIPTION:
XS GIS Cut Line= 3
      3745485.68     10254331.12      3745313.98     10253760.04
      3743149.06     10252367.77
#Sta/Elev= 30
  2851.9  280.09  3154.8  276.28    3619  265.09    3973  263.02  4335.3   262.5
  4726.5  264.82  4773.5  262.97  4837.5  263.72  4856.6  263.57  4956.3  264.27
  4986.7  262.27  4992.6  263.99  4999.5  256.11  5016.2  256.11    5023  261.71
  5028.9  260.51  5036.8  263.52  5210.5  262.95    5268  262.16  5283.2  260.31
  5310.3  262.43  5319.5  263.65  5398.1   261.2  5413.3  262.52  5441.1  260.42
  5464.8   263.2  5549.3  262.14  5637.2  264.21  5746.1  268.06  6022.2  284.64
#Mann= 9 ,-1 , 0
  2851.9     .14       0    3973     .12       0  4773.5     .12       0
  4837.5     .12       0  4856.6     .12       0  4986.7     .11       0
  4992.6     .08       0  5036.8     .12       0  5310.3     .11       0
#XS Ineff= 1 ,-1
    3665  4726.5  264.82
Permanent Ineff=
       T
Bank Sta=4992.6,5036.8
XS Rating Curve= 0 ,0
Exp/Cntr=0.3,0.1

Type RM Length L Ch R = 1 ,7248    ,610,610,610
BEGIN DESCRIPTION:
Mapping XS d687d0c5
END DESCRIPTION:
XS GIS Cut Line= 4
      3745530.99     10254217.75      3745322.67     10253666.58
      3744958.09     10253093.66      3743373.86     10251939.12
#Sta/Elev= 30
  2724.2  277.72  2892.8  276.96    3020  274.67  3414.8  264.79  3936.3  263.58
    4067   261.9  4129.7  262.15  4359.9  262.74  4487.8  261.57  4596.3  262.76
  4631.8  261.13    4661  261.08  4717.6   262.7  4738.5  261.37  4955.2  262.48
  4982.7  262.63  4987.4   256.6  5004.1   256.6  5010.4   262.3  5096.2  262.66
  5154.9  259.63  5175.7  262.04  5317.9  260.92  5426.8     262  5483.2  263.27
  5648.5  269.94  5654.7  269.39  5719.6  274.57    5820  279.54  5952.8  279.74
#Mann= 7 ,-1 , 0
  2724.2     .14       0  4129.7     .12       0    4661     .12       0
  4955.2     .12       0  4982.7     .08       0  5010.4     .12       0
  5426.8     .11       0
Bank Sta=4982.7,5010.4
XS Rating Curve= 0 ,0
Exp/Cntr=0.3,0.1

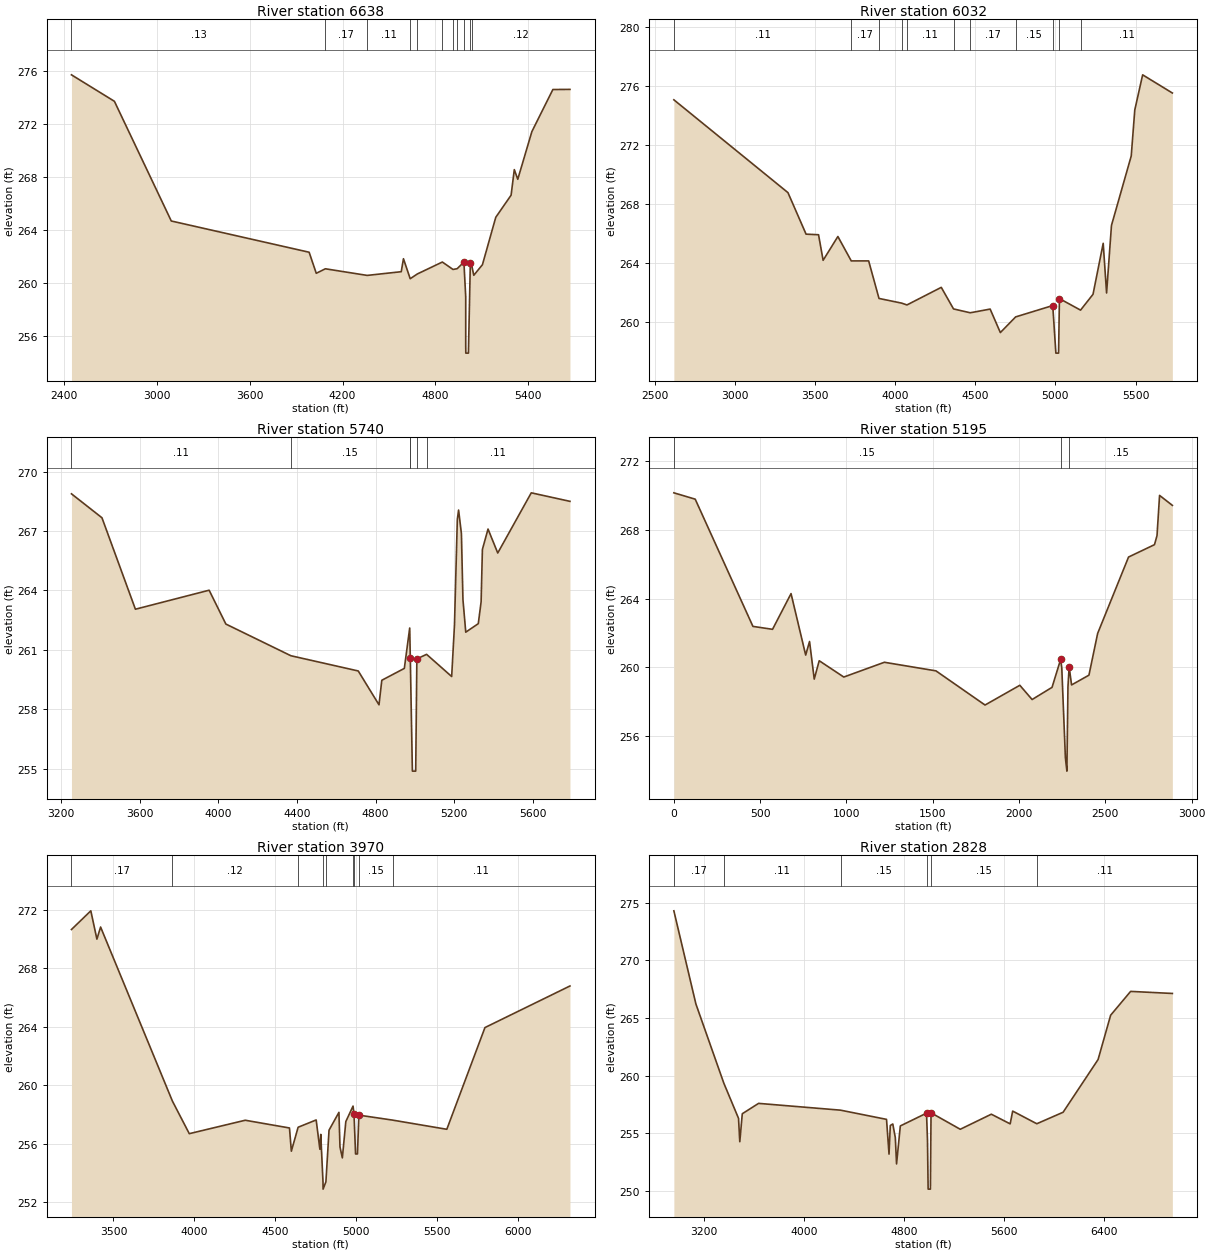
Type RM Length L Ch R = 1 ,6638    ,606,606,606
BEGIN DESCRIPTION:
ROCKY CREEK 7.0
END DESCRIPTION:
XS GIS Cut Line= 4
      3745589.17     10254116.24        3744860.     10252512.06
      3744247.43     10252009.44      3743725.48     10251587.61
#Sta/Elev= 30
  2445.5  275.74  2723.4  273.74  3091.4   264.7  3983.4  262.34  4029.5  260.75
  4088.5  261.09    4359  260.59  4579.4  260.87  4593.7  261.85  4637.4  260.34
  4683.7   260.7  4845.2   261.6  4914.5  261.04  4941.7   261.1  4984.8   261.6
  4996.5  258.99  4996.7  255.22  4997.2  254.72  5014.1  254.72  5026.4  261.49
  5034.4   261.4  5048.8   260.6  5104.8   261.4  5191.1  264.98  5290.2  266.65
    5311  268.58  5333.4  267.85  5424.6  271.45  5560.5  274.63  5671.1  274.64
#Mann= 11 ,-1 , 0
  2445.5     .13       0  4088.5     .17       0    4359     .11       0
  4637.4     .17       0  4683.7     .15       0  4845.2     .11       0
  4914.5     .15       0  4941.7     .12       0  4984.8     .08       0
  5026.4     .11       0  5034.4     .12       0
Bank Sta=4984.8,5026.4
XS Rating Curve= 0 ,0
Exp/Cntr=0.3,0.1

Type RM Length L Ch R = 1 ,6032    ,292,292,292
BEGIN DESCRIPTION:
ROCKY CREEK 6.0
END DESCRIPTION:
XS GIS Cut Line= 3
      3746529.26     10253393.13      3744637.77     10251762.06
      3744121.64     10251432.12
#Sta/Elev= 30
  2619.7  275.05  3331.5  268.77  3444.5  265.96  3522.4  265.92  3550.9  264.19
    3643   265.8  3726.5  264.15    3835  264.15  3899.6  261.61  4041.8  261.29
    4074  261.17  4288.1  262.36  4364.5   260.9  4468.8  260.64  4593.1  260.89
  4656.7   259.3  4752.1  260.36  4983.6  261.13  5003.1  257.91    5020  257.91
  5025.3   261.6  5157.1  260.82  5234.9  261.89  5298.4  265.34  5319.5  261.98
    5350  266.55  5473.3  271.25  5495.4  274.36  5544.5  276.74  5729.9  275.51
#Mann= 11 ,-1 , 0
  2619.7     .11       0  3726.5     .17       0  3899.6     .12       0
  4041.8     .17       0    4074     .11       0  4364.5     .15       0
  4468.8     .17       0  4752.1     .15       0  4983.6     .09       0
  5025.3     .15       0  5157.1     .11       0
#XS Ineff= 2 ,-1
    3860  4288.1  262.36  5298.4    5345  265.34
Permanent Ineff=
       F       F
Bank Sta=4983.6,5025.3
XS Rating Curve= 0 ,0
Exp/Cntr=0.3,0.1

Type RM Length L Ch R = 1 ,5740    ,545,545,545
BEGIN DESCRIPTION:
ROCKY CREEK 5.0
END DESCRIPTION:
XS GIS Cut Line= 3
      3746206.05     10252811.92      3745172.14     10251848.93
      3744313.66     10251128.55
#Sta/Elev= 30
  3253.9  268.88  3408.9  267.67  3578.9  263.05  3953.6  264.01  4038.7   262.3
    4369   260.7  4711.5  259.93  4816.9  258.22  4831.2  259.46  4945.7  260.06
    4973   262.1    4976 260.596  4986.6  254.87  5003.5  254.87  5009.4  260.54
  5058.8  260.77  5186.3  259.65  5200.6  262.26    5215  267.58  5221.5  268.06
  5235.8  266.87  5243.6  263.54  5257.9  261.89  5321.6  262.32  5335.9  263.42
  5342.5  266.07  5371.1   267.1  5420.5  265.89  5590.9  268.93  5787.5   268.5
#Mann= 6 ,-1 , 0
  3253.9     .11       0    4369     .15       0    4973     .12       0
    4976     .09       0  5009.4     .15       0  5058.8     .11       0
#XS Ineff= 2 ,-1
    3530  3953.6  264.01  5221.5    5600  268.06
Permanent Ineff=
       F       F
Bank Sta=4976,5009.4
XS Rating Curve= 0 ,0
Exp/Cntr=0.3,0.1

Type RM Length L Ch R = 1 ,5195    ,1225,1225,1225
XS GIS Cut Line= 3
      3746941.81     10252621.49      3745578.75     10251526.82
      3744649.93     10250862.76
#Sta/Elev= 30
       0  270.17   123.7   269.8   458.1  262.39   571.7  262.22   678.9   264.3
   763.7  260.72   786.1  261.51   813.3  259.32   842.1  260.39   984.5  259.44
  1219.7   260.3  1518.5   259.8  1802.9  257.81  2004.4  258.96  2075.6  258.13
  2191.1  258.84    2241  260.47  2247.6  259.96  2268.5  254.73  2277.1  253.96
  2283.3  258.87  2290.2  260.04  2304.2  258.98  2404.9  259.55  2455.3  261.98
  2634.4  266.43  2784.6  267.15  2799.3  267.68  2814.1  270.02  2888.2  269.44
#Mann= 3 , 0 , 0
       0     .15       0    2241     .09       0  2290.2     .15       0
Bank Sta=2241,2290.2
XS Rating Curve= 0 ,0
Exp/Cntr=0.3,0.1

Type RM Length L Ch R = 1 ,3970    ,1142,1142,1142
BEGIN DESCRIPTION:
Mapping XS f3a9fd31
END DESCRIPTION:
XS GIS Cut Line= 4
      3746969.46     10252609.11      3746271.53      10251129.9
      3746104.86      10250879.9      3745037.19     10250473.66
#Sta/Elev= 30
  3240.7  270.67  3360.2  271.95  3397.8  270.01  3420.6  270.84  3864.2  258.91
  3968.3  256.68  4313.7   257.6    4587  257.07  4598.6  255.48  4640.4  257.12
  4751.9  257.62  4774.7  255.61  4780.2  256.63    4794  253.38  4794.5  252.88
    4812  253.38  4831.3  256.92  4892.4  258.14  4898.9  255.77  4913.5  255.02
    4935  257.51  4979.6  258.57  4985.6     258  4995.1  255.29  5006.8  255.29
  5015.6  257.95  5223.4  257.61  5558.7  256.98  5794.1  263.95  6319.1   266.8
#Mann= 9 ,-1 , 0
  3240.7     .17       0  3864.2     .12       0  4640.4     .15       0
    4794     .12       0    4812     .15       0  4979.6     .12       0
  4985.6     .09       0  5015.6     .15       0  5223.4     .11       0
Bank Sta=4985.6,5015.6
XS Rating Curve= 0 ,0
Exp/Cntr=0.3,0.1

Type RM Length L Ch R = 1 ,2828    ,905,905,905
BEGIN DESCRIPTION:
Mapping XS 7203a07f
END DESCRIPTION:
XS GIS Cut Line= 4
      3748943.43     10251041.36      3747073.61     10250900.73
      3746775.33      10250557.2      3745126.41     10250406.01
#Sta/Elev= 30
  2961.4  274.31  3137.5  266.22  3360.7  259.34  3478.4  256.28  3488.5  254.25
  3508.5  256.68  3638.9  257.58  4294.3  256.99  4661.8  256.19  4681.8  253.17
  4691.9  255.66  4711.9  255.79    4732  254.61    4742  252.32  4772.1  255.62
  4981.7  256.73  4989.3  254.37  4994.5  250.13  5012.6  250.13  5017.8  256.76
  5251.4  255.33  5499.8  256.64  5650.4   255.8  5670.5  256.91  5863.3  255.81
  6073.8  256.81  6353.4  261.39  6453.8  265.24  6613.7  267.31  6947.3  267.13
#Mann= 6 ,-1 , 0
  2961.4     .17       0  3360.7     .11       0  4294.3     .15       0
  4981.7     .09       0  5017.8     .15       0  5863.3     .11       0
Bank Sta=4981.7,5017.8
XS Rating Curve= 0 ,0
Exp/Cntr=0.3,0.1

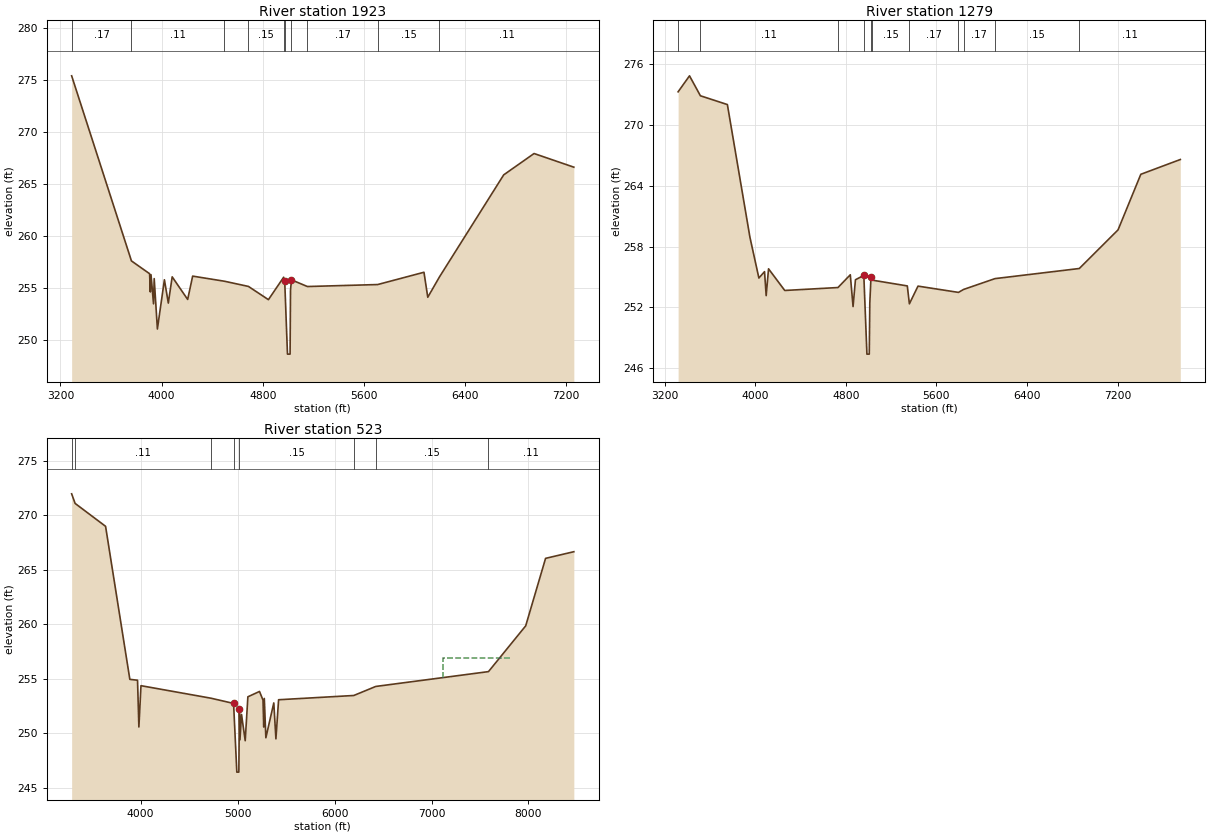
Type RM Length L Ch R = 1 ,1923    ,644,644,644
BEGIN DESCRIPTION:
ROCKY CREEK 3.0
END DESCRIPTION:
XS GIS Cut Line= 4
      3748917.35     10250978.86      3747828.82     10250583.03
      3747052.78     10250280.94      3745073.56     10250364.28
#Sta/Elev= 30
  3288.3   275.4  3761.2  257.63  3904.9   256.4  3910.6  254.65  3915.9  256.31
  3935.9  253.51  3941.2  255.93  3966.5  251.09    4022  255.82  4052.9  253.58
  4083.5   256.1  4205.9  253.93  4245.4  256.17  4496.2  255.68  4686.5  255.18
  4844.7  253.91    4965  256.06  4973.4  255.74  4995.3  248.68    5016  248.68
  5019.4  254.83  5027.1  255.81  5153.1  255.17  5708.8  255.36    6075  256.54
    6105  254.14  6197.3  256.09  6705.5  265.89  6945.7  267.94  7260.3  266.63
#Mann= 10 ,-1 , 0
  3288.3     .17       0  3761.2     .11       0  4496.2     .17       0
  4686.5     .15       0    4965     .12       0  4973.4     .09       0
  5027.1     .15       0  5153.1     .17       0  5708.8     .15       0
  6197.3     .11       0
Bank Sta=4973.4,5027.1
XS Rating Curve= 0 ,0
Exp/Cntr=0.3,0.1

Type RM Length L Ch R = 1 ,1279    ,756,756,756
BEGIN DESCRIPTION:
ROCKY CREEK 2.0
END DESCRIPTION:
XS GIS Cut Line= 4
      3749017.82     10250961.05      3747874.18     10250081.35
      3746938.19     10249765.32       3745022.2     10250348.45
#Sta/Elev= 30
  3320.1  273.29  3420.7  274.87  3516.8   272.9    3755  272.03  3954.3  258.91
  4033.2  254.89    4083  255.52  4097.5  253.15  4118.4   255.8  4261.6  253.66
  4731.4  253.95  4840.1  255.21  4864.6  252.07  4885.7  254.72  4959.6  255.15
    4987  247.37  5007.7  247.37  5012.4  252.41  5022.9  254.98  5028.9  254.69
  5343.5  254.11  5361.8  252.34  5437.9  254.09    5795  253.47  5840.1  253.76
  6117.1  254.83  6861.8  255.83  7204.1  259.65    7405  265.14  7753.6   266.6
#Mann= 11 ,-1 , 0
  3320.1     .17       0  3516.8     .11       0  4731.4     .15       0
  4959.6     .09       0  5022.9     .12       0  5028.9     .15       0
  5361.8     .17       0    5795     .15       0  5840.1     .17       0
  6117.1     .15       0  6861.8     .11       0
Bank Sta=4959.6,5022.9
XS Rating Curve= 0 ,0
Exp/Cntr=0.3,0.1

Type RM Length L Ch R = 1 ,523     ,0,0,0
BEGIN DESCRIPTION:
ROCKY CREEK 1.0
END DESCRIPTION:
XS GIS Cut Line= 4
      3749011.12     10250817.42      3748120.49     10249619.48
      3747188.19     10249114.28      3744881.91     10250368.94
#Sta/Elev= 30
  3289.1  271.96  3324.8  271.08  3638.9  268.98  3889.2  254.94  3968.5  254.86
  3982.4  250.57    4004  254.36  4726.4  253.21    4959  252.73  4992.4  246.43
  5013.2  246.43  5018.9  252.21  5024.6  249.39  5040.8  251.72  5078.9  249.31
  5106.4  253.34  5226.3  253.83  5262.5  253.03    5270  250.57  5275.7  253.19
  5291.9  249.58  5373.6  252.78  5395.5  249.48  5423.1  253.07  6198.7  253.46
  6425.2  254.29  7587.5  255.65  7971.4  259.85  8176.3  266.04  8467.7  266.65
#Mann= 8 ,-1 , 0
  3289.1     .17       0  3324.8     .11       0  4726.4     .15       0
    4959     .09       0  5018.9     .15       0  6198.7     .17       0
  6425.2     .15       0  7587.5     .11       0
#XS Ineff= 1 ,-1
  7122.9    7810  256.87
Permanent Ineff=
       F
Bank Sta=4959,5018.9
XS Rating Curve= 0 ,0
Exp/Cntr=0.3,0.1
Stream Node=ROCKY CREEK     ,Reach-1         , 0 , 0 ,Upstream end
Stream Node=ROCKY CREEK     ,Reach-1         , 0 , 1 ,Downstream end
Stream Node=WFSJR 077       ,Reach-1         , 0 , 0 ,Upstream end
Stream Node=WFSJR 077       ,Reach-1         , 0 , 1 ,Downstream end

Chan Stop Cuts=-1
Use User Specified Reach Order=0
Composite Channel Slope=5