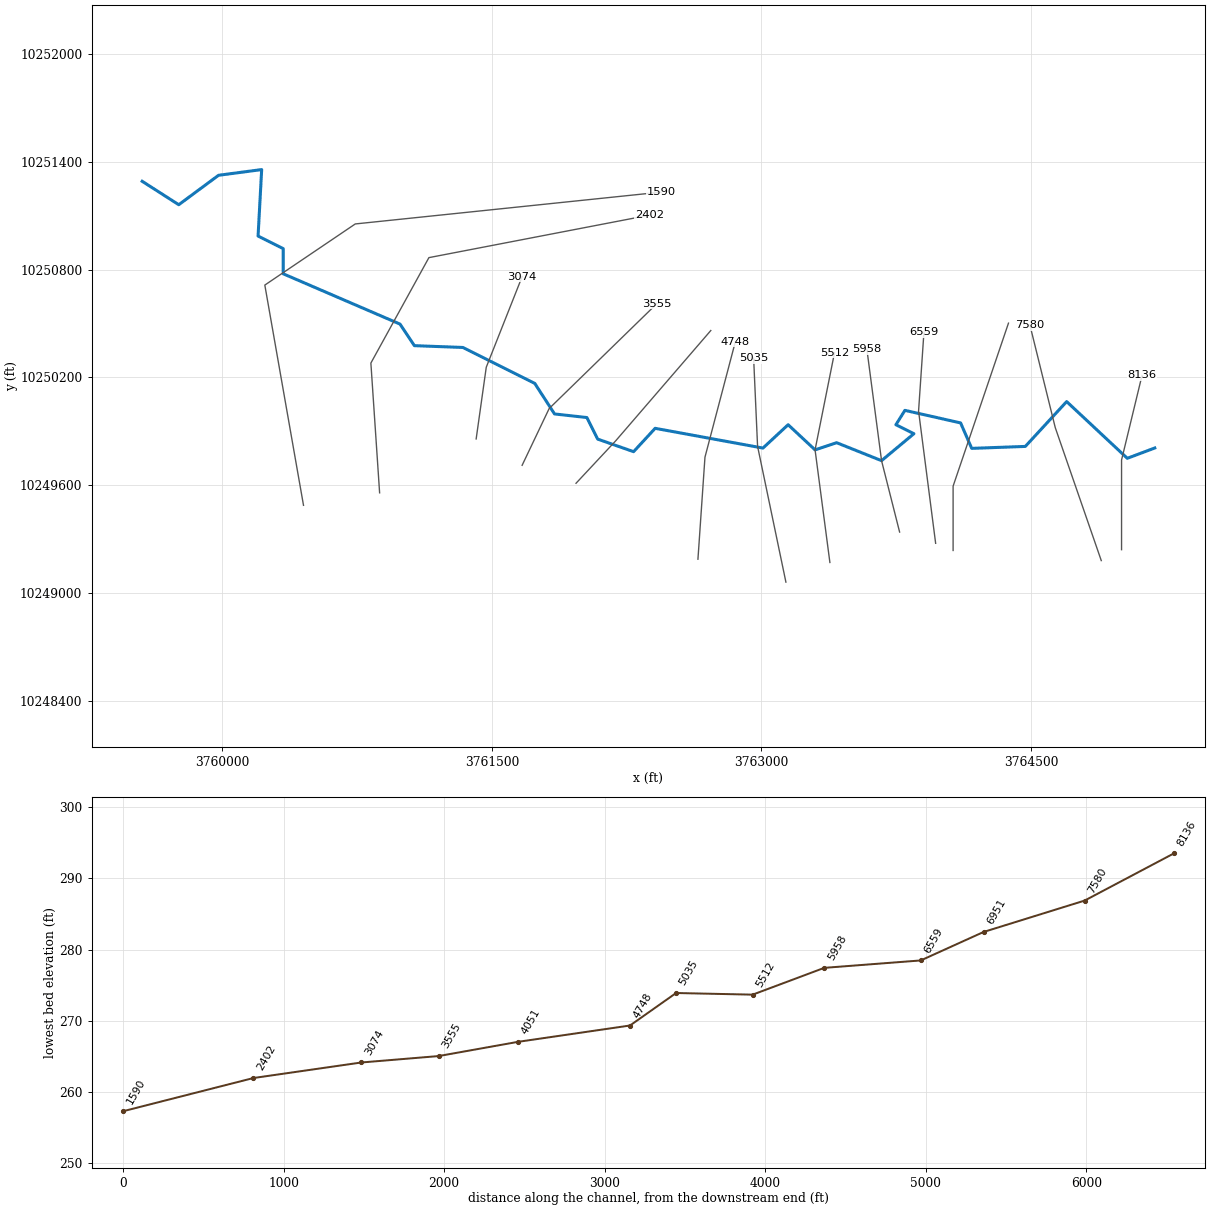
--- SCOTT BRANCH 01.prj (project) ---

Proj Title=SCOTT BRANCH 01 Base Level Engineering
Current Plan=p01
Default Exp/Contr=0.3,0.1
English Units
Geom File=g01
Flow File=f01
Plan File=p01
Y Axis Title=Elevation
X Axis Title(PF)=Main Channel Distance
X Axis Title(XS)=Station
BEGIN DESCRIPTION:
SCOTT BRANCH 01
END DESCRIPTION:
DSS Export Rating Curves= 0
DSS Export Rating Curve Sorted= 0
DSS Export Volume Flow Curves= 0
DXF OffsetX= 0
DXF OffsetY= 0
DXF ScaleX= 1
DXF ScaleY= 10

--- SCOTT BRANCH 01.p01 (plan) ---

Plan Title=Multiple Run
Program Version=4.10
Short Identifier=Multiple
Geom File=g01
Flow File=f01
Subcritical Flow
K Sum by GR= 0
Std Step Tol= 0.01
Critical Tol= 0.01
Num of Std Step Trials= 20
Max Error Tol= 0.3
Flow Tol Ratio= 0.001
Split Flow NTrial= 30
Split Flow Tol= 0.02
Split Flow Ratio= 0.02
Log Output Level= 0
Friction Slope Method= 1
Unsteady Friction Slope Method= 2
Unsteady Bridges Friction Slope Method= 1
Parabolic Critical Depth
Global Vel Dist= 1 , 1 , 1
Global Log Level= 0
CheckData=True
Encroach Param=-1 ,0,0, 0
BEGIN DESCRIPTION:
Multiple Run
END DESCRIPTION:
Computation Interval=1HOUR
Output Interval=1HOUR
Run HTab= 0
Run UNet= 0
Run PostProcess= 0
Run WQNet= 0
UNET Theta= 1
UNET Theta Warmup= 1
UNET ZTol= 0.02
UNET ZSATol= 0.05
UNET MxIter= 20
UNET MaxInSteps= 0
UNET DtIC= 0
UNET DtMin= 0
UNET MaxCRTS= 20
UNET WFStab= 2
UNET SFStab= 1
UNET WFX= 1
UNET SFX= 1
UNET DSS MLevel= 4
UNET DZMax Abort= 100
UNET Convert EG Bridges= 0
UNET Use Existing IB Tables=-1
UNET Froude Reduction=False
UNET Froude Limit= 1
UNET Froude Power= 10
UNET Time Slicing=0,0, 5
UNET Junction Losses=0
Instantaneous Interval=1HOUR
Write IC File= 0
Write IC File at Sim End=0
Echo Input=False
Echo Parameters=False
Echo Output=False
Write Detailed= 0
WQ AD Non Conservative
WQ ULTIMATE=-1
WQ Max Comp Step=1HOUR
WQ Output Interval=15MIN
WQ Output Selected Increments= 0
WQ Output face flow=0
WQ Output face velocity=0
WQ Output face area=0
WQ Output face dispersion=0
WQ Output cell volume=0
WQ Output cell surface area=0
WQ Output cell continuity=0
WQ Output cumulative cell continuity=0
WQ Output face conc=0
WQ Output face dconc_dx=0
WQ Output face courant=0
WQ Output face peclet=0
WQ Output face adv mass=0
WQ Output face disp mass=0
WQ Output cell mass=0
WQ Output cell source sink temp=0
WQ Output cell source sink nsm=0
WQ Output MaxMinRange=-1
WQ Daily Max Min Mean=-1
WQ Daily Range=0
WQ Daily Time=0
WQ Create Restart=0
WQ Fixed Restart=0
WQ System Summary=0
WQ Use Fixed Temperature=0
Sorting and Armoring Iterations= 10
XS Update Threshold= 0.02
Hydraulics Update Threshold= 0.02
Energy Slope Method= 1
Volume Change Method= 0
XS Weighting Method= 0
Number of US Weighted Cross Sections= 1
Number of DS Weighted Cross Sections= 1
Upstream XS Weight=0.25
Main XS Weight=0.5
Downstream XS Weight=0.25
Number of DS XS's Weighted with US Boundary= 1
Upstream Boundary Weight= 1
Weight of XSs Associated with US Boundary= 0
Number of US XS's Weighted with DS Boundary= 1
Downstream Boundary Weight= 0.5
Weight of XSs Associated with DS Boundary= 0.5
Sediment Output Level= 4
Mass or Volume Output= 0
Output Increment Type= 1
Profile and TS Output Increment= 10
XS Output Flag= 0
XS Output Increment= 10
Disregard all LS=0
Disregard all Conn=0
Disregard all Breaches=0
Disregard all Pumps=0

--- SCOTT BRANCH 01.f01 (steady flow) ---

Flow Title=Multiple
Program Version=4.10
Number of Profiles= 7
Profile Names=10-year,25-year,50-year,1pct_min,100-year,1pct_plu,500-year
River Rch & RM=SCOTT BRANCH 01,Reach-1         ,8136
    1017    1421    1962     891    2690    8124    5231
Boundary for River Rch & Prof#=SCOTT BRANCH 01,Reach-1         , 1
Up Type= 0
Dn Type= 3
Dn Slope=0.006
Boundary for River Rch & Prof#=SCOTT BRANCH 01,Reach-1         , 2
Up Type= 0
Dn Type= 3
Dn Slope=0.006
Boundary for River Rch & Prof#=SCOTT BRANCH 01,Reach-1         , 3
Up Type= 0
Dn Type= 3
Dn Slope=0.006
Boundary for River Rch & Prof#=SCOTT BRANCH 01,Reach-1         , 4
Up Type= 0
Dn Type= 3
Dn Slope=0.006
Boundary for River Rch & Prof#=SCOTT BRANCH 01,Reach-1         , 5
Up Type= 0
Dn Type= 3
Dn Slope=0.006
Boundary for River Rch & Prof#=SCOTT BRANCH 01,Reach-1         , 6
Up Type= 0
Dn Type= 3
Dn Slope=0.006
Boundary for River Rch & Prof#=SCOTT BRANCH 01,Reach-1         , 7
Up Type= 0
Dn Type= 3
Dn Slope=0.006
DSS Import GetInterval= 0
DSS Import GetPeak= 0
DSS Import FillOption= 0

--- SCOTT BRANCH 01.g01 (geometry) ---

Geom Title=Existing Conditions
Program Version=4.10

River Reach=SCOTT BRANCH 01 ,Reach-1
Reach XY= 30
      3765188.94     10249807.41      3765035.95      10249749.9
      3764698.49     10250065.66      3764468.46     10249816.09
      3764170.06     10249805.24      3764108.23     10249946.84
      3763798.23     10250016.84      3763748.23     10249936.84
      3763848.23     10249886.84      3763668.23     10249736.84
      3763418.23     10249836.84      3763298.23     10249796.84
      3763148.23     10249936.84      3763008.23     10249806.84
      3762408.23     10249916.84      3762288.23     10249786.84
      3762088.23     10249856.84      3762028.23     10249976.84
      3761848.23     10249996.84      3761738.23     10250166.84
      3761338.23     10250366.84      3761068.23     10250376.84
      3760988.23     10250496.84      3760338.23     10250776.84
      3760338.23     10250916.84      3760198.23     10250986.84
      3760218.23     10251356.84      3759978.12      10251325.1
      3759756.77     10251161.26      3759553.16     10251291.78

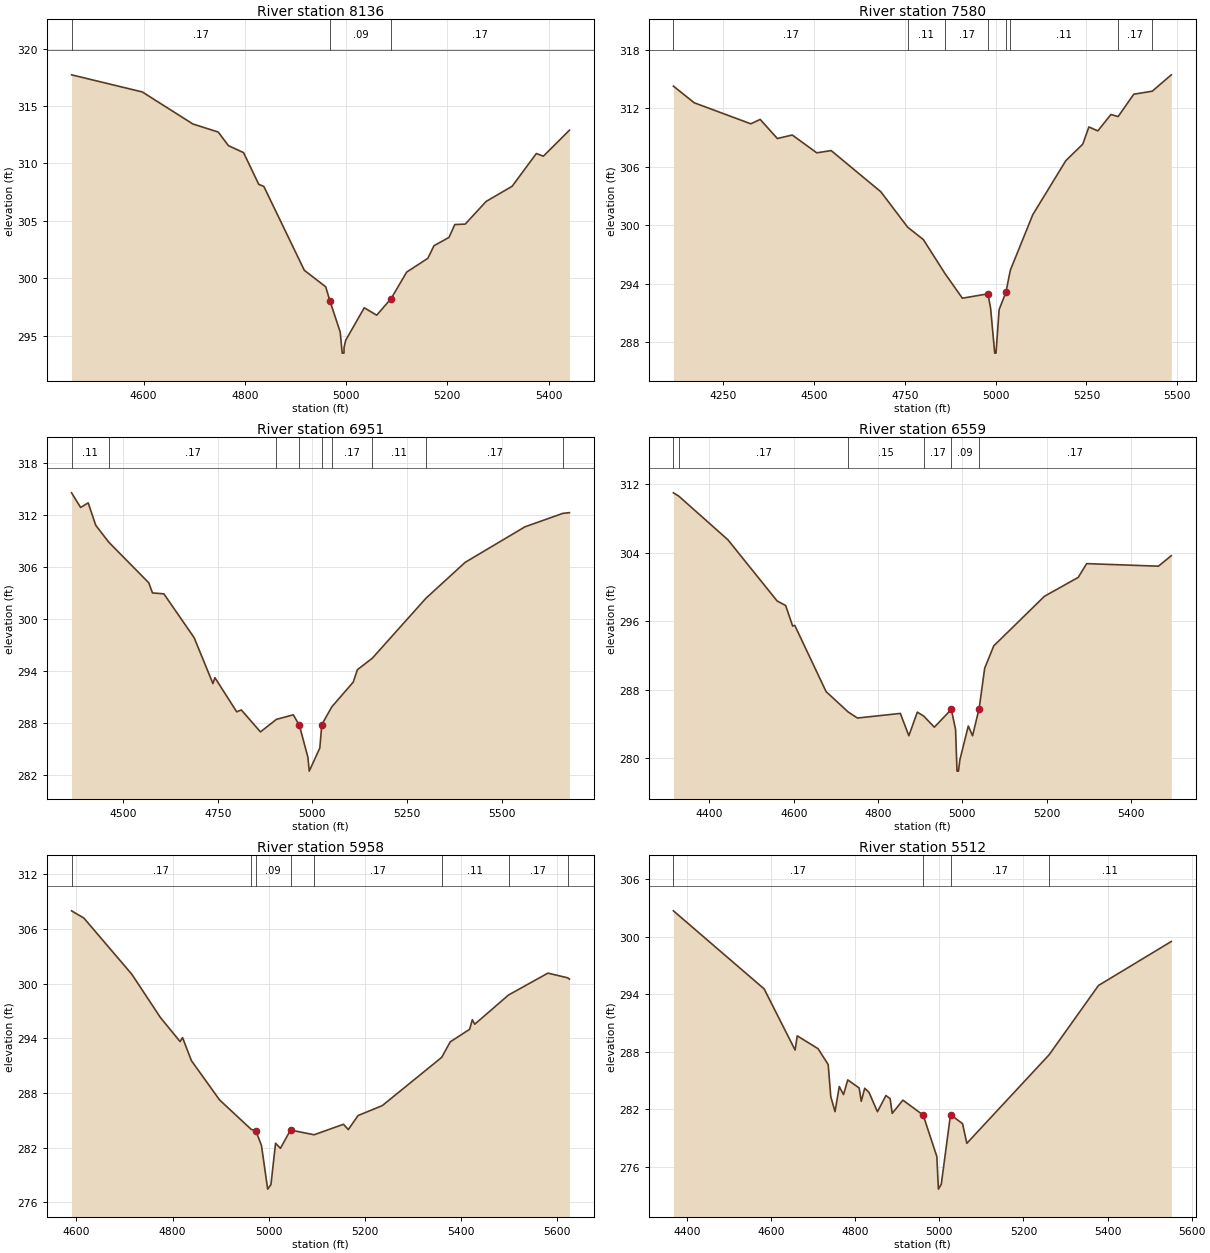
Type RM Length L Ch R = 1 ,8136    ,556,556,556
BEGIN DESCRIPTION:
SCOTT BRANCH 01 11.0
END DESCRIPTION:
XS GIS Cut Line= 3
        3765004.     10249241.38        3765004.     10249740.48
      3765117.86      10250211.1
#Sta/Elev= 30
  4457.8  317.71  4597.5  316.22  4697.5  313.43  4747.5  312.73  4767.5  311.55
  4797.5  310.94  4827.5  308.18  4837.5     308  4917.5   300.7  4959.8  299.26
  4967.8  298.07  4988.4  295.32  4992.3  293.49  4995.8  293.49    4996  293.99
  4999.2  294.61  5035.9  297.44  5060.4  296.79  5088.8  298.23  5119.6  300.54
  5161.4  301.74  5173.6  302.84  5203.2  303.56  5214.7  304.68  5235.3  304.72
  5276.5  306.69  5327.9  308.01  5375.7  310.86  5389.6  310.63  5441.1  312.89
#Mann= 3 ,-1 , 0
  4457.8     .17       0  4967.8     .09       0  5088.8     .17       0
Bank Sta=4967.8,5088.8
XS Rating Curve= 0 ,0
Exp/Cntr=0.3,0.1

Type RM Length L Ch R = 1 ,7580    ,629,629,629
BEGIN DESCRIPTION:
SCOTT BRANCH 01 10.0
END DESCRIPTION:
XS GIS Cut Line= 3
      3764891.14     10249180.59      3764635.07      10249920.6
      3764494.01     10250491.37
#Sta/Elev= 30
  4112.7  314.29    4170  312.58  4325.8  310.42  4351.7  310.87  4398.9  308.91
  4439.9  309.27  4507.5  307.44  4547.1  307.67  4683.9  303.44  4757.8   299.8
    4801  298.53  4860.4  295.05  4908.4  292.51  4978.7  292.96  4986.1  291.49
  4997.5  286.87    5001  286.87  5009.6  291.34 5028.18   293.1  5040.5  295.39
  5102.3  301.09  5193.3  306.64  5239.9  308.33  5256.8   310.1  5281.3  309.69
  5317.6  311.38  5337.2  311.16  5380.4  313.46  5431.3  313.77  5483.7  315.45
#Mann= 8 ,-1 , 0
  4112.7     .17       0  4757.8     .11       0  4860.4     .17       0
  4978.7     .09       0 5028.18     .17       0  5040.5     .11       0
  5337.2     .17       0  5431.3     .11       0
Bank Sta=4978.7,5028.18
XS Rating Curve= 0 ,0
Exp/Cntr=0.3,0.1

Type RM Length L Ch R = 1 ,6951    ,392,392,392
BEGIN DESCRIPTION:
SCOTT BRANCH 01 9.0
END DESCRIPTION:
XS GIS Cut Line= 3
       3764066.5     10249237.05       3764066.5     10249595.08
      3764374.67     10250502.24
#Sta/Elev= 30
  4363.3   314.6  4387.3  312.91  4407.3  313.44  4427.3  310.85  4461.5  308.91
  4567.3  304.22  4577.3  303.04  4607.3  302.94  4687.3  297.88    4737  292.58
  4742.3  293.26  4799.8  289.32  4812.1  289.53  4862.6     287  4904.9  288.45
  4949.4  288.97  4965.5 287.765  4988.1  284.06  4991.6  282.47  5019.5  285.14
  5024.8  287.84  5051.2  289.89  5107.9  292.75  5118.9  294.18  5158.4  295.51
  5300.1  302.43  5403.6  306.57    5562  310.68    5662  312.23  5679.4  312.31
#Mann= 9 ,-1 , 0
  4363.3     .11       0  4461.5     .17       0  4904.9     .15       0
  4965.5     .09       0  5024.8     .15       0  5051.2     .17       0
  5158.4     .11       0  5300.1     .17       0    5662     .11       0
Bank Sta=4965.5,5024.8
XS Rating Curve= 0 ,0
Exp/Cntr=0.3,0.1

Type RM Length L Ch R = 1 ,6559    ,601,601,601
BEGIN DESCRIPTION:
SCOTT BRANCH 01 8.0
END DESCRIPTION:
XS GIS Cut Line= 3
      3763969.28     10249276.89      3763874.23      10250013.1
      3763904.17     10250451.46
#Sta/Elev= 30
  4314.4  311.02    4327  310.64  4443.7  305.53  4560.6  298.37  4580.8  297.84
  4597.4  295.44  4602.4  295.52  4676.8  287.77  4729.1  285.39  4751.1  284.68
    4853  285.22  4873.2  282.61  4893.3  285.37  4908.2  284.92  4933.7  283.61
    4974  285.69  4984.1  283.33  4987.5  278.47    4991  278.47  4994.3   279.8
  5014.3  283.75  5024.4  282.61    5040  285.79  5053.2  290.51  5074.7  293.12
    5195  298.92  5275.2  301.13  5295.2  302.74  5465.6  302.44  5496.1  303.67
#Mann= 6 ,-1 , 0
  4314.4     .11       0    4327     .17       0  4729.1     .15       0
  4908.2     .17       0    4974     .09       0    5040     .17       0
Bank Sta=4974,5040
XS Rating Curve= 0 ,0
Exp/Cntr=0.3,0.1

Type RM Length L Ch R = 1 ,5958    ,446,446,446
BEGIN DESCRIPTION:
SCOTT BRANCH 01 7.0
END DESCRIPTION:
XS GIS Cut Line= 3
      3763768.75     10249339.46      3763668.23     10249736.84
      3763586.56     10250356.89
#Sta/Elev= 30
  4590.1  307.99  4615.8  307.19  4715.5  301.02  4774.8  296.28  4815.8  293.63
  4820.9  294.07  4839.3  291.54  4897.8  287.23  4963.5     284  4973.4  283.82
    4985  282.22  4997.9  277.43  5004.7  277.93  5014.3  282.47  5024.4  281.91
  5045.4  283.92  5094.4   283.4  5155.6  284.55  5165.6  283.97  5185.8  285.51
  5236.2   286.6  5359.8   291.9  5377.5   293.6  5417.8  294.98  5423.5  296.03
  5428.5  295.54  5498.8  298.75  5580.7  301.15    5622  300.63  5625.4  300.49
#Mann= 8 ,-1 , 0
  4590.1     .17       0  4963.5     .15       0  4973.4     .09       0
  5045.4     .15       0  5094.4     .17       0  5359.8     .11       0
  5498.8     .17       0    5622     .11       0
Bank Sta=4973.4,5045.4
XS Rating Curve= 0 ,0
Exp/Cntr=0.3,0.1

Type RM Length L Ch R = 1 ,5512    ,477,477,477
BEGIN DESCRIPTION:
SCOTT BRANCH 01 6.0
END DESCRIPTION:
XS GIS Cut Line= 3
      3763380.73     10249170.15      3763298.23     10249796.84
      3763406.43     10250337.73
#Sta/Elev= 30
  4367.9  302.72  4583.6  294.57  4657.2  288.19  4662.3  289.67  4711.8  288.33
  4735.9  286.67    4742  283.33  4752.1  281.76  4762.2  284.38  4772.3  283.54
  4782.4  285.07  4809.5  284.23  4814.5  282.84  4822.7   284.2  4832.8  283.78
    4853  281.75  4873.1  283.44  4883.1  283.12  4888.1  281.58  4913.5  282.96
  4961.7   281.4  4994.2  277.07  4997.9  273.67  5004.7  274.17  5026.7  281.45
  5055.3   280.5  5065.5  278.45    5261  287.69  5378.5  294.93  5551.6  299.52
#Mann= 4 ,-1 , 0
  4367.9     .17       0  4961.7     .09       0  5026.7     .17       0
    5261     .11       0
Bank Sta=4961.7,5026.7
XS Rating Curve= 0 ,0
Exp/Cntr=0.3,0.1

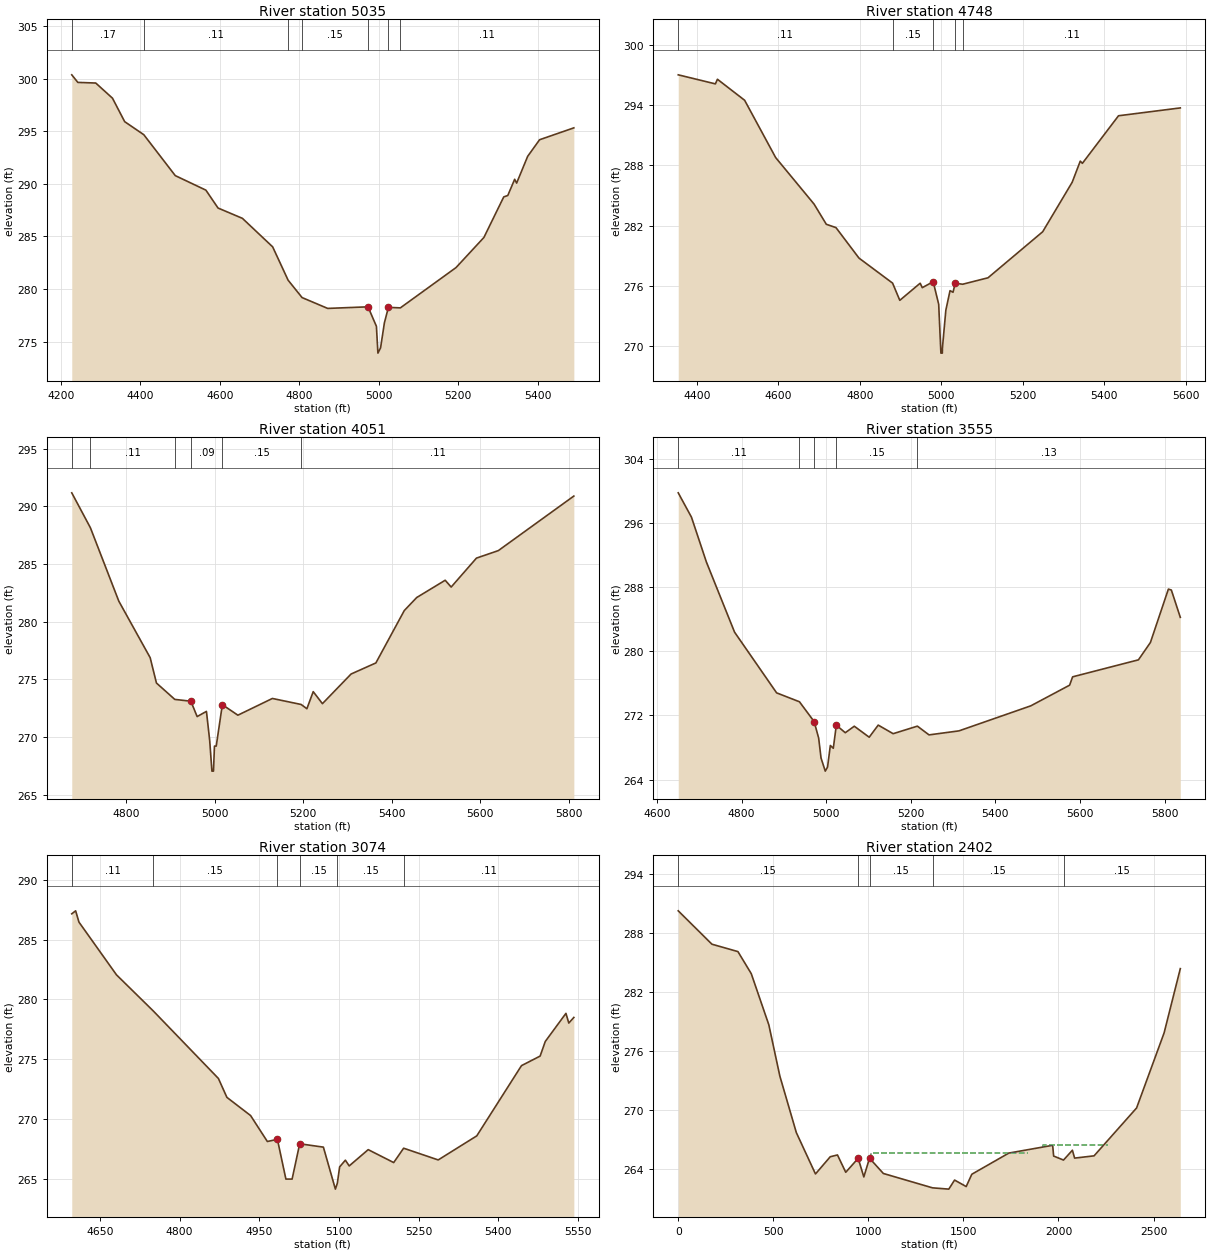
Type RM Length L Ch R = 1 ,5035    ,287,287,287
BEGIN DESCRIPTION:
SCOTT BRANCH 01 5.0
END DESCRIPTION:
XS GIS Cut Line= 3
      3763135.93     10249060.82      3762978.23     10249816.84
       3762956.3     10250307.15
#Sta/Elev= 30
  4227.7  300.35    4243  299.63    4288  299.57  4330.1  298.13  4360.8   295.9
  4408.9  294.66  4488.1  290.77  4565.1  289.39  4595.7  287.69    4657  286.71
  4733.1     284    4772  280.83  4807.1  279.18  4871.5  278.15    4973   278.3
  4994.1  276.45  4997.9   273.9  5004.6   274.4  5014.2  276.78  5024.3  278.25
  5054.3   278.2  5194.4  282.03  5264.5  284.89  5314.5  288.75  5324.6  288.88
  5341.9  290.42  5346.9  290.06  5374.6   292.6  5404.6  294.18  5490.8  295.31
#Mann= 7 ,-1 , 0
  4227.7     .17       0  4408.9     .11       0    4772     .17       0
  4807.1     .15       0    4973     .09       0  5024.3     .15       0
  5054.3     .11       0
Bank Sta=4973,5024.3
XS Rating Curve= 0 ,0
Exp/Cntr=0.3,0.1

Type RM Length L Ch R = 1 ,4748    ,697,697,697
BEGIN DESCRIPTION:
SCOTT BRANCH 01 4.0
END DESCRIPTION:
XS GIS Cut Line= 3
      3762646.36     10249188.43      3762685.42      10249756.1
      3762854.27     10250397.74
#Sta/Elev= 30
  4354.4  297.01  4445.6  296.11  4450.6  296.57  4517.4  294.48  4593.6  288.78
  4687.8  284.16  4717.9  282.15  4741.6  281.82  4798.1  278.79  4880.6   276.3
  4898.3  274.59  4948.3  276.29  4953.5  275.85  4980.3  276.44  4993.8  274.19
  4999.2  269.34  5002.7  269.34  5002.9  269.84  5011.3   273.6  5021.6  275.55
    5029  275.39  5034.2  276.29  5052.6  276.19  5114.8  276.83  5249.1  281.41
  5321.5  286.33  5341.3  288.43  5346.5  288.21  5435.2  292.94  5586.9  293.72
#Mann= 5 ,-1 , 0
  4354.4     .11       0  4880.6     .15       0  4980.3     .09       0
  5034.2     .15       0  5052.6     .11       0
Bank Sta=4980.3,5034.2
XS Rating Curve= 0 ,0
Exp/Cntr=0.3,0.1

Type RM Length L Ch R = 1 ,4051    ,496,496,496
BEGIN DESCRIPTION:
SCOTT BRANCH 01 3.0
END DESCRIPTION:
XS GIS Cut Line= 3
      3761967.87     10249611.09      3762188.23     10249846.84
      3762717.83     10250461.05
#Sta/Elev= 30
  4677.3  291.18  4719.4  288.15  4783.5  281.79  4854.3  276.89  4868.5  274.69
  4909.9  273.27  4946.2  273.11  4960.4  271.78  4981.4  272.23  4988.7  269.72
  4993.8  267.05  4997.3  267.05  4999.5  269.22  5003.5  269.22  5017.3  272.81
  5052.4   271.9  5130.3  273.35  5195.2  272.83  5208.2  272.46  5222.5  273.94
  5243.3   272.9    5308  275.47    5364  276.43  5428.1  280.97  5456.1   282.1
  5520.5   283.6    5534  283.01  5591.1  285.52  5640.5  286.17    5811   290.9
#Mann= 6 ,-1 , 0
  4677.3     .17       0  4719.4     .11       0  4909.9     .15       0
  4946.2     .09       0  5017.3     .15       0  5195.2     .11       0
Bank Sta=4946.2,5017.3
XS Rating Curve= 0 ,0
Exp/Cntr=0.3,0.1

Type RM Length L Ch R = 1 ,3555    ,481,481,481
BEGIN DESCRIPTION:
SCOTT BRANCH 01 2.0
END DESCRIPTION:
XS GIS Cut Line= 3
      3761667.83     10249711.03      3761818.23     10250026.84
      3762417.87     10250611.09
#Sta/Elev= 30
  4650.2  299.76  4681.5  296.72  4716.7  291.14  4783.4  282.38  4882.8  274.81
  4936.8   273.7  4971.5  271.23  4982.2  269.17  4987.8  266.69  4997.8  265.05
  5003.2  265.55  5009.8  268.25  5016.8   267.9    5024  270.78  5045.1  269.84
  5066.4  270.65  5101.7  269.28    5123  270.79  5158.3  269.72  5215.6  270.66
  5243.1  269.57  5313.9  270.07  5483.6  273.19  5575.5  275.77  5582.6  276.81
  5738.2  278.93  5766.5  281.09    5809  287.75    5816  287.64  5837.2  284.23
#Mann= 5 ,-1 , 0
  4650.2     .11       0  4936.8     .15       0  4971.5     .09       0
    5024     .15       0  5215.6     .13       0
Bank Sta=4971.5,5024
XS Rating Curve= 0 ,0
Exp/Cntr=0.3,0.1

Type RM Length L Ch R = 1 ,3074    ,672,672,672
BEGIN DESCRIPTION:
SCOTT BRANCH 01 1.0
END DESCRIPTION:
XS GIS Cut Line= 3
      3761411.98     10249857.69      3761468.23     10250256.84
      3761667.85     10250761.07
#Sta/Elev= 30
  4596.9  287.16  4604.2  287.41  4610.4  286.47  4681.1  282.06  4750.4  279.04
    4873   273.4    4889  271.82  4933.6   270.3  4965.2  268.13  4984.1  268.31
  5000.1  264.99  5011.8  264.99  5026.1  267.94  5070.7  267.66  5093.3  264.15
    5097  264.65  5101.3  266.01  5112.1  266.57  5119.3  266.09  5155.1  267.45
  5203.1  266.37  5221.8  267.57  5286.9  266.59  5359.5   268.6  5443.7  274.47
  5478.8  275.27  5488.5  276.49  5527.4  278.84  5532.8  278.03  5542.3   278.5
#Mann= 6 ,-1 , 0
  4596.9     .11       0  4750.4     .15       0  4984.1     .09       0
  5026.1     .15       0    5097     .15       0  5221.8     .11       0
Bank Sta=4984.1,5026.1
XS Rating Curve= 0 ,0
Exp/Cntr=0.3,0.1

Type RM Length L Ch R = 1 ,2402    ,812,812,812
XS GIS Cut Line= 4
      3760874.67      10249557.8      3760826.06     10250280.02
      3761148.98     10250866.82      3762374.67     10251102.94
#Sta/Elev= 30
       0  290.23   177.3  286.84     314  286.09   384.1  283.85   476.6  278.65
   534.5  273.45   621.2  267.71   721.9  263.51   799.7  265.26   837.6  265.44
   881.1  263.68   946.5   265.1   976.2  263.21  1006.1  265.11  1078.9  263.56
  1337.6   262.1  1423.1  261.97  1453.6  262.89  1514.7  262.23  1544.2  263.48
  1738.8  265.63  1969.5  266.42  1974.6  265.33  2026.5  264.92  2073.3  265.92
    2085  265.12  2187.3  265.35  2410.9  270.21  2555.6  277.83  2640.9  284.36
#Mann= 5 ,-1 , 0
       0     .15       0   946.5     .09       0  1006.1     .15       0
  1337.6     .15       0  2026.5     .15       0
#XS Ineff= 3 ,-1
     650   837.6  265.44  1011.9    1840  265.59  1917.6    2260  266.44
Permanent Ineff=
       T       T       F
Bank Sta=946.5,1006.1
XS Rating Curve= 0 ,0
Exp/Cntr=0.3,0.1

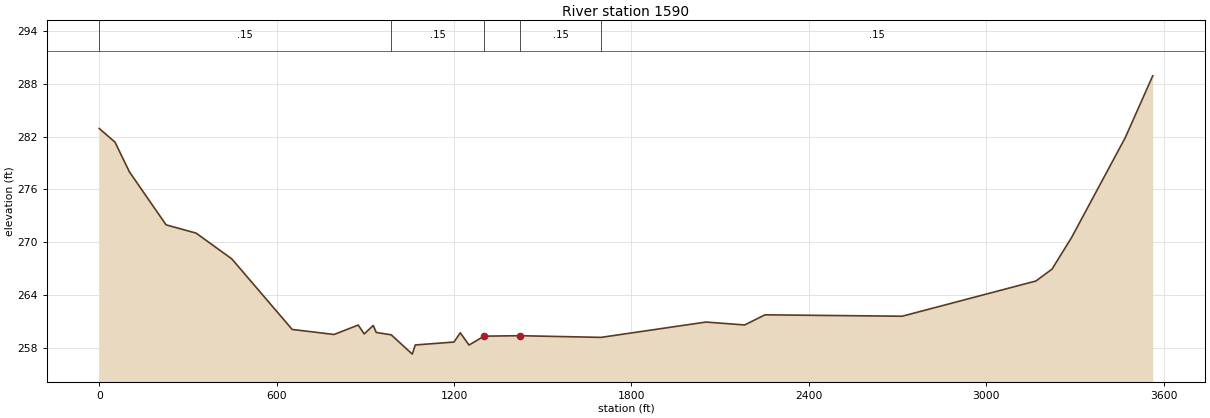
Type RM Length L Ch R = 1 ,1590    ,0,0,0
XS GIS Cut Line= 4
      3760451.06     10249488.35      3760235.78     10250714.05
      3760739.25     10251054.32      3762440.64     10251231.41
#Sta/Elev= 30
       0  282.92    53.5  281.36   102.2  277.99   226.1  271.98   327.7  271.04
   448.3  268.12   652.6  260.11   794.3  259.54   875.9  260.61   896.2   259.6
   926.7  260.56   936.8  259.77   987.6   259.5  1058.7  257.31  1068.8  258.35
  1199.7  258.68  1221.1  259.73  1250.5  258.34  1301.5  259.35  1424.3   259.4
  1697.1  259.21  2051.8  260.95  2182.5  260.62  2251.6  261.77  2715.4  261.61
  3167.8  265.61  3222.2  266.96  3288.4  270.55  3469.4  281.85  3562.7  288.89
#Mann= 5 ,-1 , 0
       0     .15       0   987.6     .15       0  1301.5     .09       0
  1424.3     .15       0  1697.1     .15       0
#XS Ineff= 1 ,-1
     600   926.7  260.56
Permanent Ineff=
       T
Bank Sta=1301.5,1424.3
XS Rating Curve= 0 ,0
Exp/Cntr=0.3,0.1

Chan Stop Cuts=-1
Use User Specified Reach Order=0
Composite Channel Slope=5