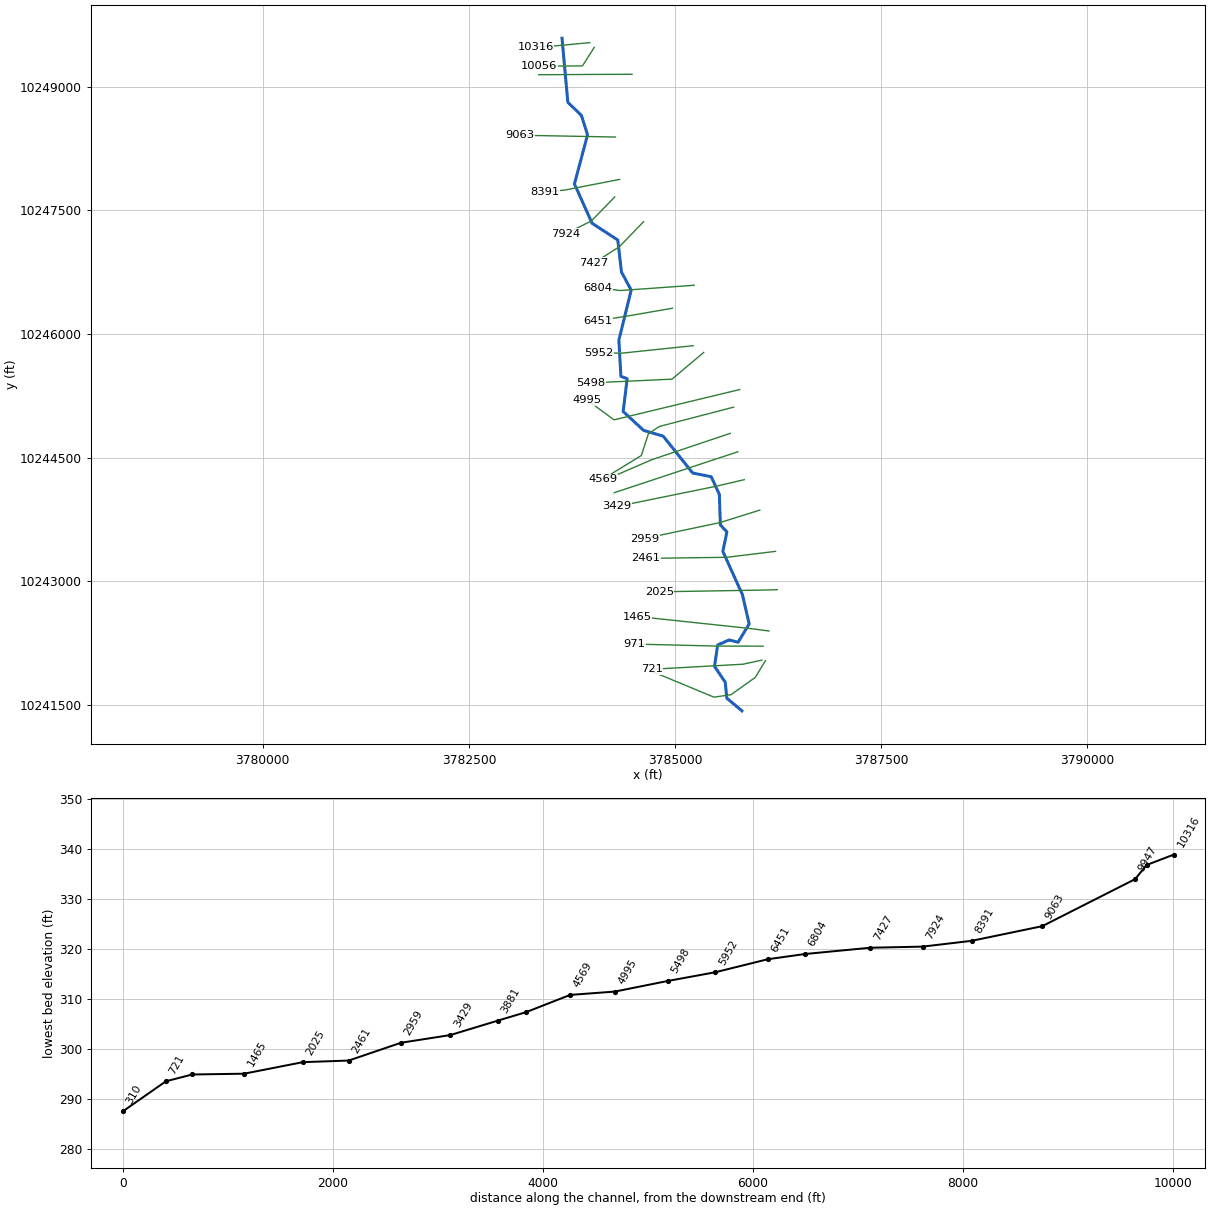
--- TRIBUTARY 4.prj (project) ---

Proj Title=TRIBUTARY 4 Base Level Engineering
Current Plan=p01
Default Exp/Contr=0.3,0.1
English Units
Geom File=g01
Flow File=f01
Plan File=p01
Y Axis Title=Elevation
X Axis Title(PF)=Main Channel Distance
X Axis Title(XS)=Station
BEGIN DESCRIPTION:
TRIBUTARY 4
END DESCRIPTION:
DSS Export Rating Curves= 0
DSS Export Rating Curve Sorted= 0
DSS Export Volume Flow Curves= 0
DXF OffsetX= 0
DXF OffsetY= 0
DXF ScaleX= 1
DXF ScaleY= 10

--- TRIBUTARY 4.p01 (plan) ---

Plan Title=Multiple Run
Program Version=4.10
Short Identifier=Multiple
Geom File=g01
Flow File=f01
Subcritical Flow
K Sum by GR= 0
Std Step Tol= 0.01
Critical Tol= 0.01
Num of Std Step Trials= 20
Max Error Tol= 0.3
Flow Tol Ratio= 0.001
Split Flow NTrial= 30
Split Flow Tol= 0.02
Split Flow Ratio= 0.02
Log Output Level= 0
Friction Slope Method= 1
Unsteady Friction Slope Method= 2
Unsteady Bridges Friction Slope Method= 1
Parabolic Critical Depth
Global Vel Dist= 1 , 1 , 1
Global Log Level= 0
CheckData=True
Encroach Param=-1 ,0,0, 0
BEGIN DESCRIPTION:
Multiple Run
END DESCRIPTION:
Computation Interval=1HOUR
Output Interval=1HOUR
Run HTab= 0
Run UNet= 0
Run PostProcess= 0
Run WQNet= 0
UNET Theta= 1
UNET Theta Warmup= 1
UNET ZTol= 0.02
UNET ZSATol= 0.05
UNET MxIter= 20
UNET MaxInSteps= 0
UNET DtIC= 0
UNET DtMin= 0
UNET MaxCRTS= 20
UNET WFStab= 2
UNET SFStab= 1
UNET WFX= 1
UNET SFX= 1
UNET DSS MLevel= 4
UNET DZMax Abort= 100
UNET Convert EG Bridges= 0
UNET Use Existing IB Tables=-1
UNET Froude Reduction=False
UNET Froude Limit= 1
UNET Froude Power= 10
UNET Time Slicing=0,0, 5
UNET Junction Losses=0
Instantaneous Interval=1HOUR
Write IC File= 0
Write IC File at Sim End=0
Echo Input=False
Echo Parameters=False
Echo Output=False
Write Detailed= 0
WQ AD Non Conservative
WQ ULTIMATE=-1
WQ Max Comp Step=1HOUR
WQ Output Interval=15MIN
WQ Output Selected Increments= 0
WQ Output face flow=0
WQ Output face velocity=0
WQ Output face area=0
WQ Output face dispersion=0
WQ Output cell volume=0
WQ Output cell surface area=0
WQ Output cell continuity=0
WQ Output cumulative cell continuity=0
WQ Output face conc=0
WQ Output face dconc_dx=0
WQ Output face courant=0
WQ Output face peclet=0
WQ Output face adv mass=0
WQ Output face disp mass=0
WQ Output cell mass=0
WQ Output cell source sink temp=0
WQ Output cell source sink nsm=0
WQ Output MaxMinRange=-1
WQ Daily Max Min Mean=-1
WQ Daily Range=0
WQ Daily Time=0
WQ Create Restart=0
WQ Fixed Restart=0
WQ System Summary=0
WQ Use Fixed Temperature=0
Sorting and Armoring Iterations= 10
XS Update Threshold= 0.02
Hydraulics Update Threshold= 0.02
Energy Slope Method= 1
Volume Change Method= 0
XS Weighting Method= 0
Number of US Weighted Cross Sections= 1
Number of DS Weighted Cross Sections= 1
Upstream XS Weight=0.25
Main XS Weight=0.5
Downstream XS Weight=0.25
Number of DS XS's Weighted with US Boundary= 1
Upstream Boundary Weight= 1
Weight of XSs Associated with US Boundary= 0
Number of US XS's Weighted with DS Boundary= 1
Downstream Boundary Weight= 0.5
Weight of XSs Associated with DS Boundary= 0.5
Sediment Output Level= 4
Mass or Volume Output= 0
Output Increment Type= 1
Profile and TS Output Increment= 10
XS Output Flag= 0
XS Output Increment= 10
Disregard all LS=0
Disregard all Conn=0
Disregard all Breaches=0
Disregard all Pumps=0

--- TRIBUTARY 4.f01 (steady flow) ---

Flow Title=Multiple
Program Version=4.10
Number of Profiles= 7
Profile Names=10-year,25-year,50-year,1pct_min,100-year,1pct_plu,500-year
River Rch & RM=TRIBUTARY 4,Reach-1         ,10316
     507     678     910     403    1216    3672    2241
River Rch & RM=TRIBUTARY 4,Reach-1         ,9063
    1168    1634    2259    1026    3097    9353    6020
River Rch & RM=TRIBUTARY 4,Reach-1         ,4148
    1679    2384    3326    1522    4597   13883    9083
Boundary for River Rch & Prof#=TRIBUTARY 4,Reach-1         , 1
Up Type= 0
Dn Type= 3
Dn Slope=0.014
Boundary for River Rch & Prof#=TRIBUTARY 4,Reach-1         , 2
Up Type= 0
Dn Type= 3
Dn Slope=0.014
Boundary for River Rch & Prof#=TRIBUTARY 4,Reach-1         , 3
Up Type= 0
Dn Type= 3
Dn Slope=0.014
Boundary for River Rch & Prof#=TRIBUTARY 4,Reach-1         , 4
Up Type= 0
Dn Type= 3
Dn Slope=0.014
Boundary for River Rch & Prof#=TRIBUTARY 4,Reach-1         , 5
Up Type= 0
Dn Type= 3
Dn Slope=0.014
Boundary for River Rch & Prof#=TRIBUTARY 4,Reach-1         , 6
Up Type= 0
Dn Type= 3
Dn Slope=0.014
Boundary for River Rch & Prof#=TRIBUTARY 4,Reach-1         , 7
Up Type= 0
Dn Type= 3
Dn Slope=0.014
DSS Import GetInterval= 0
DSS Import GetPeak= 0
DSS Import FillOption= 0

--- TRIBUTARY 4.g01 (geometry) ---

Geom Title=Existing Conditions
Program Version=4.10

River Reach=TRIBUTARY 4     ,Reach-1
Reach XY= 30
      3783628.75     10249587.44      3783699.28     10248810.14
      3783864.26     10248650.02      3783938.24     10248415.58
      3783779.53     10247819.22      3783993.52     10247342.16
      3784305.04      10247138.4      3784349.74     10246749.44
      3784467.65     10246530.95      3784318.26     10245924.44
      3784342.84     10245484.15      3784418.58     10245456.75
      3784370.25     10245058.42      3784618.27     10244828.82
       3784855.9     10244759.01      3785213.54     10244311.85
      3785438.46      10244266.7      3785536.64     10244050.97
      3785549.18     10243681.06      3785628.28     10243596.97
      3785579.09     10243361.06      3785816.32     10242835.99
      3785898.53      10242480.8      3785763.53     10242258.57
      3785655.36      10242286.4      3785516.15     10242224.82
      3785478.16     10241965.77      3785608.26     10241773.01
      3785627.14     10241579.45      3785810.19     10241426.48

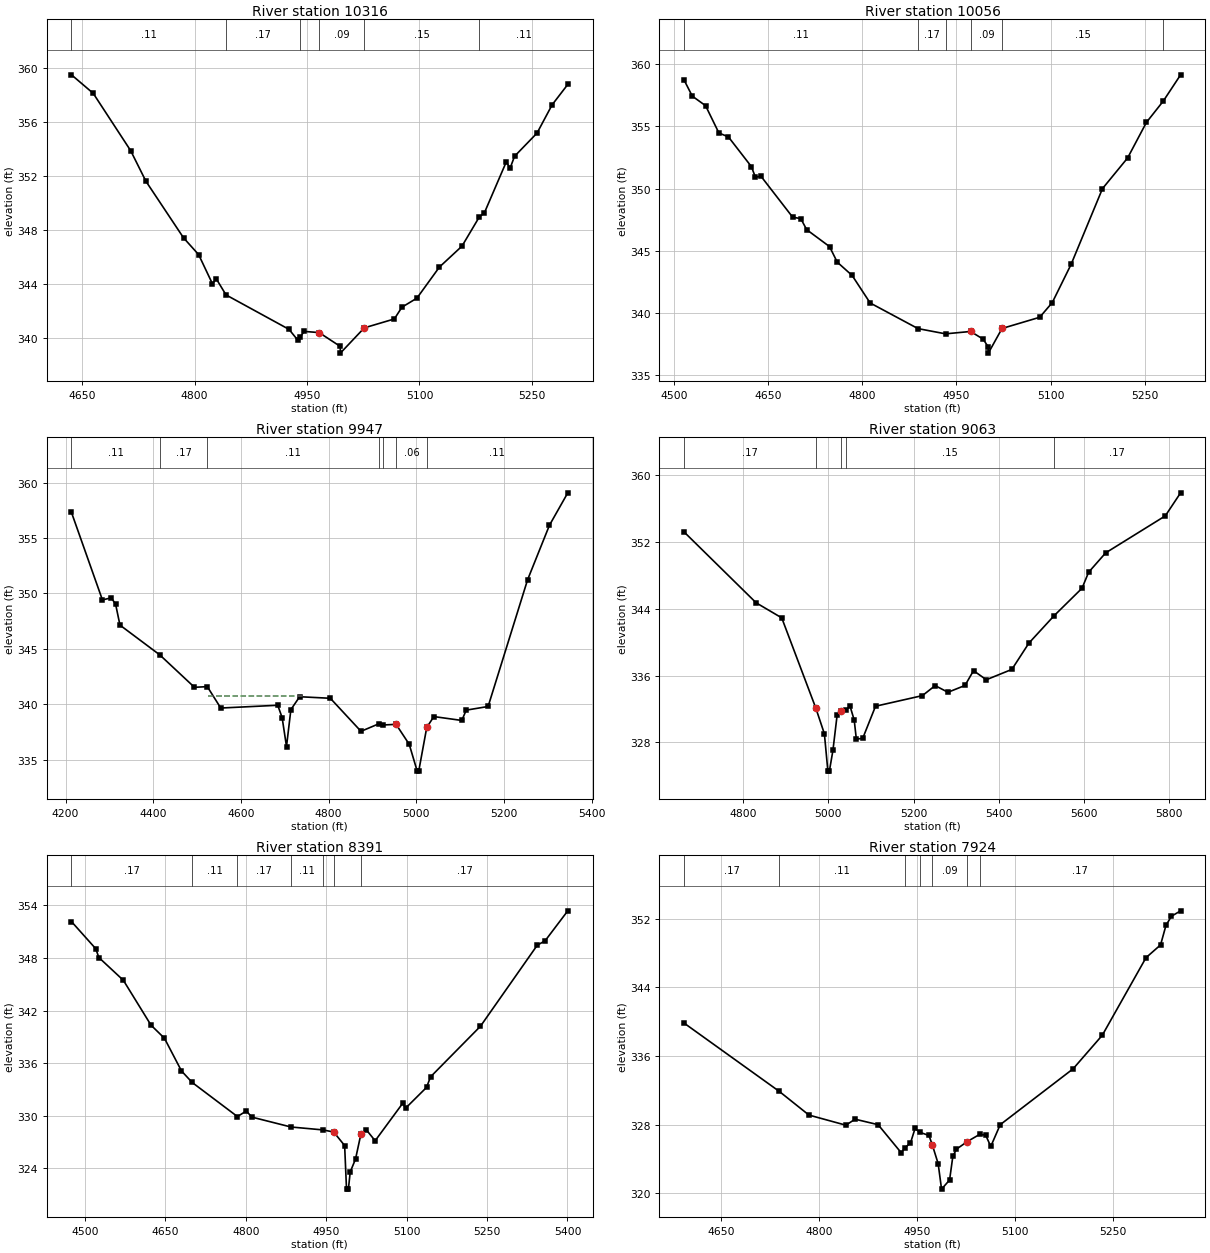
Type RM Length L Ch R = 1 ,10316   ,260,260,260
BEGIN DESCRIPTION:
TRIBUTARY 4 19.0
END DESCRIPTION:
XS GIS Cut Line= 3
      3783966.69     10249533.83      3783556.96     10249495.63
      3783306.96     10249481.74
#Sta/Elev= 30
  4635.9  359.49  4664.9  358.12  4714.8  353.88  4735.2  351.61  4785.4  347.42
  4805.5  346.18  4823.9  344.02  4828.9   344.4    4842   343.2    4926  340.65
    4938  339.83  4940.8  340.06  4946.1   340.5  4966.2  340.41  4994.3  339.39
  4994.5  338.89  5026.4  340.76  5066.5  341.42  5076.6  342.29  5096.6  342.96
  5126.6  345.26  5156.7  346.81  5179.8  348.97  5186.7  349.29  5215.8  353.05
  5220.8  352.57  5226.8  353.46  5256.8  355.18  5276.9  357.27  5297.8  358.78
#Mann= 6 ,-1 , 0
  4635.9     .11       0    4842     .17       0  4940.8     .15       0
  4966.2     .09       0  5026.4     .15       0  5179.8     .11       0
Bank Sta=4966.2,5026.4
XS Rating Curve= 0 ,0
Exp/Cntr=0.3,0.1

Type RM Length L Ch R = 1 ,10056   ,109,109,109
BEGIN DESCRIPTION:
Mapping XS a4d7d545
END DESCRIPTION:
XS GIS Cut Line= 3
      3784019.66      10249476.8       3783876.5     10249251.04
      3783353.42     10249249.21
#Sta/Elev= 30
  4516.6   358.7  4529.3  357.44  4550.5  356.67  4571.7  354.48  4586.9  354.16
  4623.4  351.78  4629.9  350.92  4638.6  351.01  4689.2  347.71  4702.1   347.6
  4711.5  346.71  4747.9  345.35  4760.2   344.1  4783.9  343.03  4812.6  340.82
  4888.8  338.76  4932.6  338.34  4972.6  338.53  4992.6  337.91  5000.6  337.29
  5000.8  336.79  5022.6  338.77  5082.6  339.67  5102.6  340.85  5132.6  343.92
  5182.6  350.01  5222.6  352.47  5252.6  355.33  5279.4  357.04    5307  359.15
#Mann= 6 ,-1 , 0
  4516.6     .11       0  4888.8     .17       0  4932.6     .15       0
  4972.6     .09       0  5022.6     .15       0  5279.4     .11       0
Bank Sta=4972.6,5022.6
XS Rating Curve= 0 ,0
Exp/Cntr=0.3,0.1

Type RM Length L Ch R = 1 ,9947    ,884,884,884
BEGIN DESCRIPTION:
Mapping XS 514bdcea
END DESCRIPTION:
XS GIS Cut Line= 2
      3784478.44      10249150.1      3783346.05     10249144.59
#Sta/Elev= 30
  4213.4   357.3    4284  349.41    4304   349.6    4314  349.04    4324  347.14
    4415  344.45    4494  341.53  4523.3  341.59    4554  339.66    4684  339.91
    4694   338.8    4704  336.19    4714  339.52    4734  340.68    4804  340.54
    4874  337.56  4915.9  338.26    4924  338.13    4954  338.19    4984  336.39
  5002.2  333.97  5005.7  333.97    5024  337.91  5040.2  338.89    5104  338.54
    5114  339.47    5164   339.8    5254  351.22    5304  356.15  5345.8  359.07
#Mann= 7 ,-1 , 0
  4213.4     .11       0    4415     .17       0  4523.3     .11       0
  4915.9     .15       0    4924     .11       0    4954     .06       0
    5024     .11       0
#XS Ineff= 1 ,-1
    4525    4744  340.77
Permanent Ineff=
       F
Bank Sta=4954,5024
XS Rating Curve= 0 ,0
Exp/Cntr=0.3,0.1

Type RM Length L Ch R = 1 ,9063    ,672,672,672
BEGIN DESCRIPTION:
TRIBUTARY 4 18.0
END DESCRIPTION:
XS GIS Cut Line= 2
      3784276.55     10248388.44      3783111.96     10248410.45
#Sta/Elev= 30
  4661.9  353.17  4830.6  344.71  4890.6  342.91  4970.7  332.09  4990.7  329.03
  4998.9  324.56  5002.4  324.56  5010.7  327.03  5020.7  331.32  5030.7   331.8
  5042.4  331.91  5050.7  332.37  5060.7  330.67  5065.7  328.39  5080.7  328.49
  5110.7  332.33  5220.7   333.6  5250.7   334.8  5280.7     334  5320.7  334.82
  5340.7  336.59  5370.7   335.5  5430.7  336.74  5470.7  339.89  5529.5  343.15
  5595.4  346.46  5610.8  348.37  5650.8  350.69  5790.8  355.12  5826.7  357.88
#Mann= 5 ,-1 , 0
  4661.9     .17       0  4970.7     .09       0  5030.7     .17       0
  5042.4     .15       0  5529.5     .17       0
Bank Sta=4970.7,5030.7
XS Rating Curve= 0 ,0
Exp/Cntr=0.3,0.1

Type RM Length L Ch R = 1 ,8391    ,467,467,467
BEGIN DESCRIPTION:
TRIBUTARY 4 17.0
END DESCRIPTION:
XS GIS Cut Line= 3
      3784328.01     10247874.56      3783667.36     10247745.88
      3783415.81     10247720.38
#Sta/Elev= 30
  4474.7  352.16  4519.9  349.07  4525.8  348.06  4571.5  345.46  4623.1  340.34
  4648.1  338.85  4679.9  335.12  4699.7  333.81  4784.3  329.91  4800.9  330.55
  4811.1  329.85  4884.2  328.72  4943.5  328.39  4963.9  328.15  4984.3   326.6
  4987.8  321.63  4991.3  321.63  4994.7  323.59  5004.6  325.06  5014.8  327.96
    5025  328.38  5041.2  327.15  5092.8  331.44  5097.9  330.86  5137.1  333.24
  5144.5  334.44  5237.7  340.22  5343.7  349.47  5358.3  349.97  5400.6  353.39
#Mann= 7 ,-1 , 0
  4474.7     .17       0  4699.7     .11       0  4784.3     .17       0
  4884.2     .11       0  4943.5     .17       0  4963.9     .09       0
  5014.8     .17       0
Bank Sta=4963.9,5014.8
XS Rating Curve= 0 ,0
Exp/Cntr=0.3,0.1

Type RM Length L Ch R = 1 ,7924    ,497,497,497
BEGIN DESCRIPTION:
TRIBUTARY 4 16.0
END DESCRIPTION:
XS GIS Cut Line= 3
      3784267.86     10247661.08      3783984.25     10247369.86
      3783667.86     10247211.07
#Sta/Elev= 30
  4593.5   339.8  4739.2  331.85  4784.5   329.1  4841.1  327.92  4855.2  328.62
  4890.5  327.98  4925.9  324.71  4931.5  325.28  4940.1  325.85  4947.1  327.54
  4954.2   327.1  4968.4  326.72  4973.4  325.66  4982.5  323.44  4987.7  320.47
    5000  321.53    5005  324.29  5010.6  325.13  5027.3  326.02  5045.9  326.84
  5055.3  326.77  5063.1  325.44  5077.6  327.98  5189.3  334.49    5234   338.4
    5301  347.44  5323.3  348.93  5331.6  351.21    5340  352.27    5354   352.9
#Mann= 7 ,-1 , 0
  4593.5     .17       0  4739.2     .11       0  4931.5     .17       0
  4954.2     .15       0  4973.4     .09       0  5027.3     .15       0
  5045.9     .17       0
Bank Sta=4973.4,5027.3
XS Rating Curve= 0 ,0
Exp/Cntr=0.3,0.1

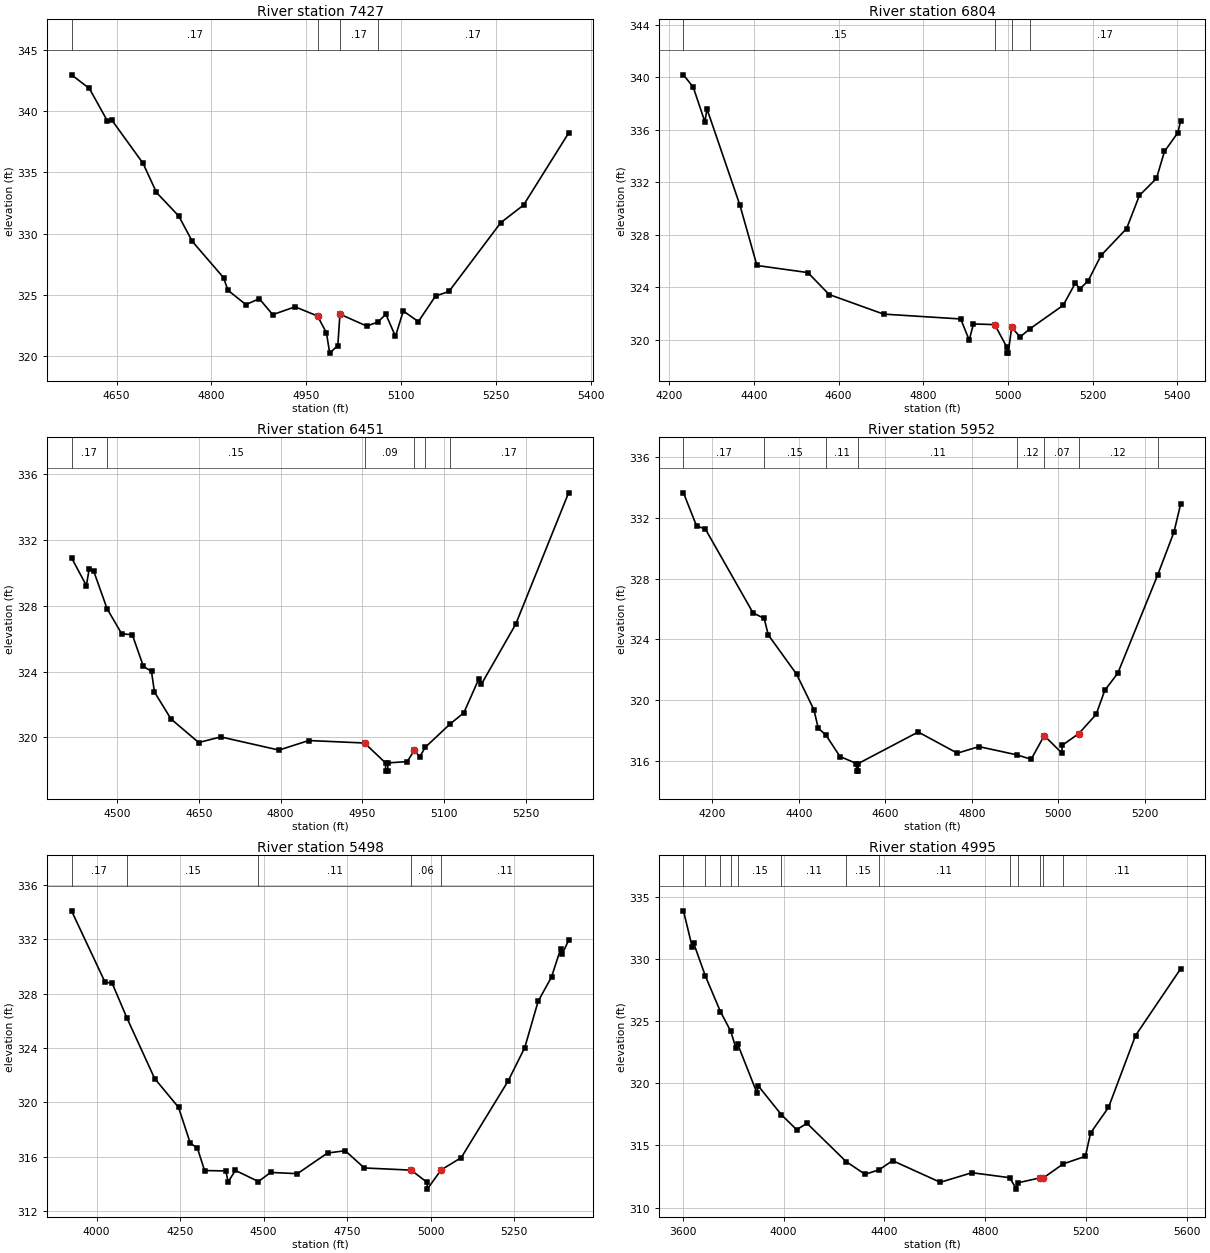
Type RM Length L Ch R = 1 ,7427    ,623,623,623
BEGIN DESCRIPTION:
TRIBUTARY 4 15.0
END DESCRIPTION:
XS GIS Cut Line= 3
      3784617.85     10247361.07      3784325.08     10247058.27
      3784017.82     10246861.05
#Sta/Elev= 30
  4578.8  342.96    4607  341.85  4635.3  339.22  4642.5  339.27  4691.9  335.74
  4713.2  333.36  4748.5  331.43  4769.8  329.37  4819.2  326.41  4826.4  325.37
  4854.7  324.21  4875.8  324.69  4897.1  323.39  4932.4  324.03  4967.9  323.28
    4982  321.91  4987.2  320.25    5000  320.87  5003.4  323.43  5045.6  322.46
  5063.2  322.78    5076  323.42  5091.2  321.62  5103.6  323.69  5127.4  322.82
  5154.6  324.91  5175.8  325.28  5257.7  330.89  5293.8  332.33  5365.1  338.21
#Mann= 4 ,-1 , 0
  4578.8     .17       0  4967.9     .09       0  5003.4     .17       0
  5063.2     .17       0
Bank Sta=4967.9,5003.4
XS Rating Curve= 0 ,0
Exp/Cntr=0.3,0.1

Type RM Length L Ch R = 1 ,6804    ,353,353,353
BEGIN DESCRIPTION:
TRIBUTARY 4 14.0
END DESCRIPTION:
XS GIS Cut Line= 3
      3785230.95     10246589.83      3784336.49     10246526.19
      3784061.42     10246560.29
#Sta/Elev= 30
  4233.6  340.17  4256.8  339.22  4284.2  336.59  4289.2  337.57    4367  330.24
  4407.1  325.66  4527.4  325.12  4577.6  323.45  4706.1  321.96  4888.3  321.59
  4908.4  319.98  4918.4  321.21  4968.6  321.16  4996.5  319.49  4996.8  318.99
  5000.4  318.99  5008.7  320.95  5028.7  320.22  5051.6  320.84  5130.3  322.63
  5159.2  324.33  5169.3  323.86  5189.4   324.5  5219.6  326.42  5280.1  328.47
  5310.3  330.99  5350.6  332.29  5369.5  334.34    5401  335.76  5407.5  336.63
#Mann= 4 ,-1 , 0
  4233.6     .15       0  4968.6     .09       0  5008.7     .15       0
  5051.6     .17       0
Bank Sta=4968.6,5008.7
XS Rating Curve= 0 ,0
Exp/Cntr=0.3,0.1

Type RM Length L Ch R = 1 ,6451    ,499,499,499
BEGIN DESCRIPTION:
TRIBUTARY 4 13.0
END DESCRIPTION:
XS GIS Cut Line= 3
      3784967.81     10246311.06      3784392.47     10246211.42
      3784067.85     10246161.07
#Sta/Elev= 30
  4416.1  330.92  4443.4  329.23  4448.5  330.25  4456.6  330.13  4481.4  327.82
  4508.2   326.3  4527.7  326.24    4548  324.32  4562.9  324.01  4568.3  322.76
  4598.7  321.12  4649.5  319.69  4690.1  320.03  4796.8  319.23  4851.5  319.81
  4953.9  319.66  4992.4  318.45  4992.7  317.95  4996.4  317.95  4996.7  318.45
  5032.4  318.53  5045.2  319.22  5055.3  318.82  5065.4   319.4  5110.1  320.79
  5136.2   321.5  5163.5  323.54  5168.5  323.24  5231.5  326.89  5328.5  334.87
#Mann= 6 ,-1 , 0
  4416.1     .17       0  4481.4     .15       0  4953.9     .09       0
  5045.2     .15       0  5065.4     .11       0  5110.1     .17       0
Bank Sta=4953.9,5045.2
XS Rating Curve= 0 ,0
Exp/Cntr=0.3,0.1

Type RM Length L Ch R = 1 ,5952    ,454,454,454
BEGIN DESCRIPTION:
TRIBUTARY 4 12.0
END DESCRIPTION:
XS GIS Cut Line= 3
       3785218.1     10245856.46      3784355.81     10245766.26
      3784072.56     10245771.82
#Sta/Elev= 30
    4133  333.63  4163.4  331.45  4183.5  331.26  4294.1  325.74  4319.8  325.38
  4329.2   324.3  4394.7  321.72  4434.9  319.38  4444.9  318.17  4462.6  317.72
  4495.2  316.31  4533.3  315.85  4533.6  315.35  4537.3  315.35  4537.6  315.85
  4676.2  317.92  4766.7  316.53    4817  316.96  4904.1  316.42  4937.6  316.13
  4967.8  317.68  5008.7  316.54  5009.2  317.04    5048  317.82    5088  319.08
    5108  320.66    5138  321.78  5230.3  328.23    5268  331.05  5283.3  332.87
#Mann= 8 ,-1 , 0
    4133     .17       0  4319.8     .15       0  4462.6     .11       0
  4537.6     .11       0  4904.1     .12       0  4967.8     .07       0
    5048     .12       0  5230.3     .17       0
Bank Sta=4967.8,5048
XS Rating Curve= 0 ,0
Exp/Cntr=0.3,0.1

Type RM Length L Ch R = 1 ,5498    ,503,503,503
BEGIN DESCRIPTION:
TRIBUTARY 4 11.0
END DESCRIPTION:
XS GIS Cut Line= 3
       3785346.1     10245773.99      3784961.99     10245450.64
      3783976.74     10245405.07
#Sta/Elev= 30
  3924.8  334.11  4025.4  328.84  4046.2  328.79  4090.6  326.22  4173.7  321.75
  4245.2  319.63  4280.3  316.99  4301.6  316.63  4323.2  314.97    4387  314.94
  4393.5  314.13  4415.6  314.98  4484.3  314.16    4521  314.83  4601.2  314.74
  4691.3  316.26  4744.3  316.43  4801.4  315.16  4941.6     315  4989.5   314.1
  4989.8   313.6  5031.7  315.02  5091.7  315.92  5231.9  321.56  5281.9  324.03
    5322  327.45    5362  329.23  5389.3  331.31  5394.3  330.94  5413.2  331.94
#Mann= 5 ,-1 , 0
  3924.8     .17       0  4090.6     .15       0  4484.3     .11       0
  4941.6     .06       0  5031.7     .11       0
Bank Sta=4941.6,5031.7
XS Rating Curve= 0 ,0
Exp/Cntr=0.3,0.1

Type RM Length L Ch R = 1 ,4995    ,426,426,426
BEGIN DESCRIPTION:
TRIBUTARY 4 10.0
END DESCRIPTION:
XS GIS Cut Line= 3
      3785784.52     10245324.79      3784259.76     10244957.12
      3783933.82     10245196.39
#Sta/Elev= 30
  3602.3  333.86  3637.2  330.93  3642.3  331.28  3689.2  328.62  3748.9  325.76
  3789.9  324.18  3809.9  322.85  3817.6  323.13  3893.7  319.23  3898.9  319.79
  3991.1  317.46  4051.5  316.26  4092.6  316.77  4247.6   313.7  4323.1  312.67
  4379.1  313.04  4432.1  313.77  4621.5  312.03  4747.2   312.8  4896.8   312.4
  4923.9  311.48    4928  311.98  5018.4  312.39  5031.1  312.39  5109.5  313.51
  5197.3  314.12  5218.1     316  5289.1  318.05  5396.4  323.83  5575.1  329.19
#Mann= 13 ,-1 , 0
  3602.3     .15       0  3689.2     .11       0  3748.9     .15       0
  3789.9     .11       0  3817.6     .15       0  3991.1     .11       0
  4247.6     .15       0  4379.1     .11       0  4896.8     .15       0
    4928     .15       0  5018.4     .09       0  5031.1     .15       0
  5109.5     .11       0
Bank Sta=5018.4,5031.1
XS Rating Curve= 0 ,0
Exp/Cntr=0.3,0.1

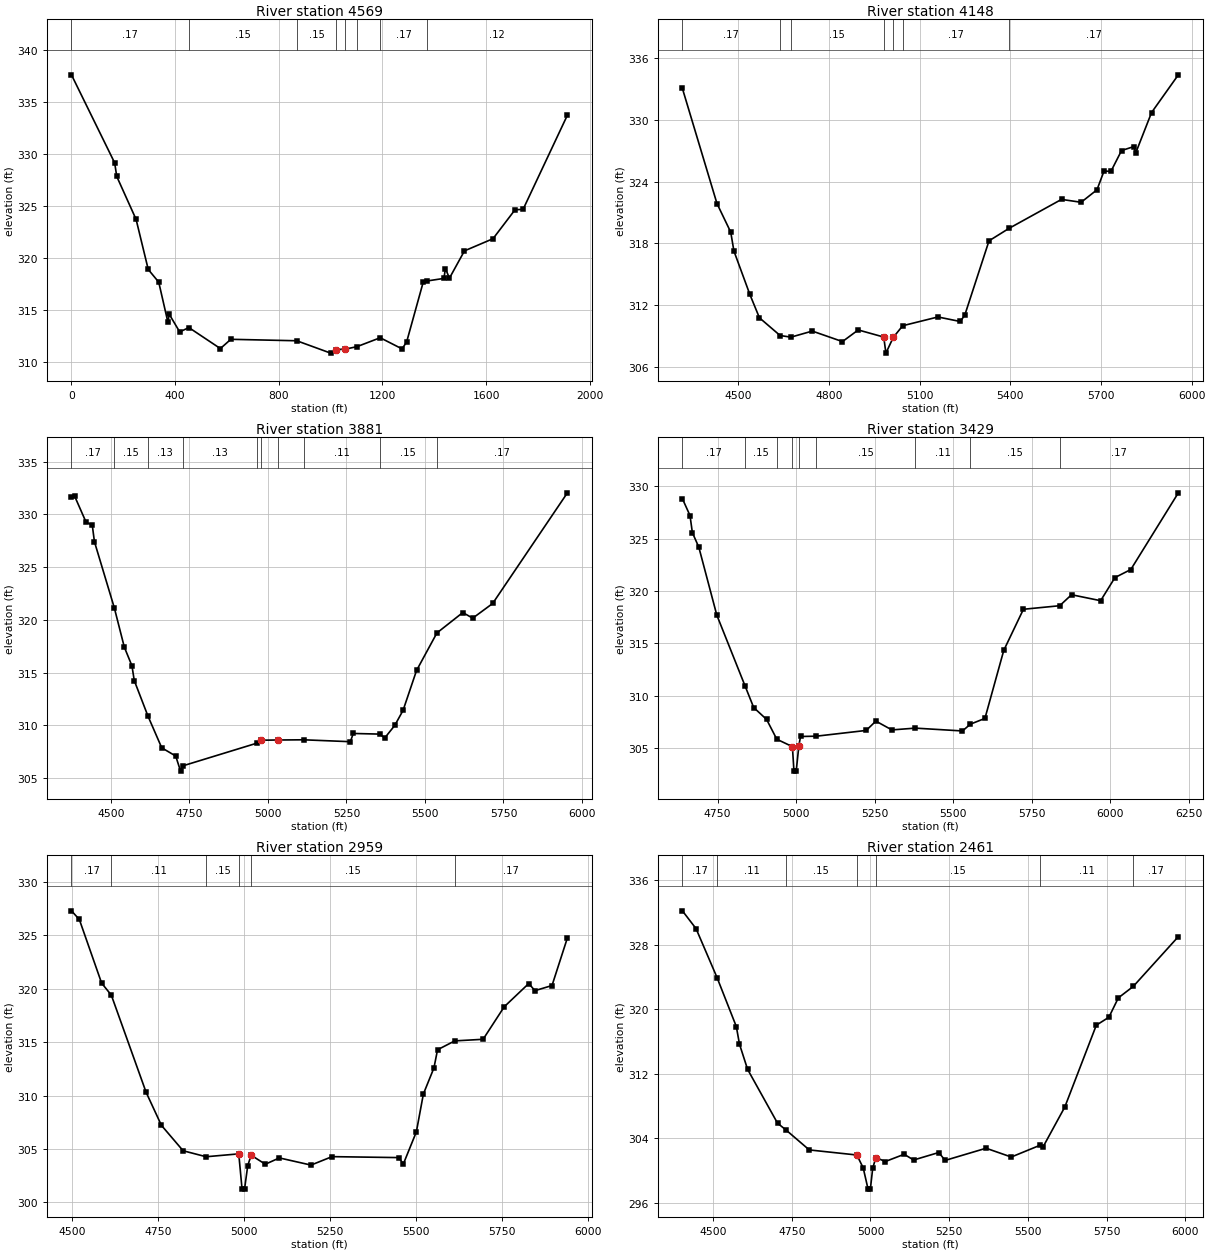
Type RM Length L Ch R = 1 ,4569    ,421,421,421
XS GIS Cut Line= 5
      3785709.18     10245110.91      3784809.08     10244876.34
      3784676.27      10244787.8      3784590.87     10244524.49
      3784124.46     10244238.09
#Sta/Elev= 30
       0  337.59   166.7  329.12   174.8  327.81   249.4  323.68   296.3  318.86
   336.8  317.64   372.2  313.78   377.3  314.55   417.8  312.85   453.1  313.27
   574.6  311.25   615.1  312.14   869.4     312  1000.3  310.81  1021.3  311.15
  1057.3   311.2  1101.5  311.43  1191.5  312.29  1275.6  311.22  1293.3  311.87
  1357.3  317.63  1371.3  317.75  1437.3     318  1443.2  318.95  1458.6  318.02
  1516.6  320.65  1626.8  321.82  1711.9  324.61  1742.8  324.64  1913.9  333.71
#Mann= 8 ,-1 , 0
       0     .17       0   453.1     .15       0   869.4     .15       0
  1021.3     .08       0  1057.3     .15       0  1101.5     .15       0
  1191.5     .17       0  1371.3     .12       0
Bank Sta=1021.3,1057.3
XS Rating Curve= 0 ,0
Exp/Cntr=0.3,0.1

Type RM Length L Ch R = 1 ,4148    ,267,267,267
BEGIN DESCRIPTION:
TRIBUTARY 4 9.0
END DESCRIPTION:
XS GIS Cut Line= 3
      3785669.49      10244793.1      3784718.93     10244474.08
      3784133.04     10244220.19
#Sta/Elev= 30
  4314.8  333.04  4429.2  321.87  4474.8  319.09  4485.3  317.26    4538  313.05
  4569.7  310.78  4638.1  309.06  4673.9   308.9  4744.6  309.49  4844.5  308.47
  4896.7   309.6  4981.1  308.91  4988.3  307.35  5012.7  308.88  5043.9  310.01
  5160.4  310.86  5234.2  310.42  5249.2  311.03  5329.5  318.25  5395.8  319.46
  5569.4  322.27  5634.3  321.99  5686.7   323.2  5710.2  325.03  5732.8  324.98
    5768  327.01  5809.1   327.4    5815  326.78  5867.4   330.7    5956  334.36
#Mann= 7 ,-1 , 0
  4314.8     .17       0  4638.1     .15       0  4673.9     .15       0
  4981.1     .08       0  5012.7     .15       0  5043.9     .17       0
  5395.8     .17       0
Bank Sta=4981.1,5012.7
XS Rating Curve= 0 ,0
Exp/Cntr=0.3,0.1

Type RM Length L Ch R = 1 ,3881    ,452,452,452
BEGIN DESCRIPTION:
TRIBUTARY 4 8.0
END DESCRIPTION:
XS GIS Cut Line= 2
      3785760.65     10244569.58       3784261.9     10244072.89
#Sta/Elev= 30
  4374.6  331.67  4384.3  331.76  4421.2  329.26  4440.8     329  4447.7  327.42
  4511.1  321.14  4542.8  317.43  4567.2  315.65  4574.5  314.26  4618.1  310.89
    4662  307.88  4706.5   307.1  4721.9  305.67    4729  306.17  4964.8  308.32
    4978   308.6  5030.7  308.62  5113.4  308.64  5262.5  308.46  5271.8  309.24
  5355.5  309.18  5372.1  308.82  5403.8     310  5430.3  311.43  5473.2  315.21
  5538.1  318.77  5620.4   320.7  5652.1  320.17  5715.5  321.56  5953.5  332.05
#Mann= 10 ,-1 , 0
  4374.6     .17       0  4511.1     .15       0  4618.1     .13       0
    4729     .13       0  4964.8     .13       0    4978     .09       0
  5030.7     .13       0  5113.4     .11       0  5355.5     .15       0
  5538.1     .17       0
Bank Sta=4978,5030.7
XS Rating Curve= 0 ,0
Exp/Cntr=0.3,0.1

Type RM Length L Ch R = 1 ,3429    ,470,470,470
BEGIN DESCRIPTION:
TRIBUTARY 4 7.0
END DESCRIPTION:
XS GIS Cut Line= 3
      3785838.75     10244231.03      3785486.39     10244148.93
      3784294.95     10243905.78
#Sta/Elev= 30
  4638.2  328.82  4662.4  327.21  4669.9  325.58  4690.5  324.18  4747.6   317.7
    4838  310.89    4865  308.86  4906.1  307.72  4938.5  305.83  4988.2  305.12
  4993.1  302.78  5000.3  302.78  5008.7   305.2    5014  306.09  5064.3  306.12
    5223  306.67  5253.7  307.56  5304.7  306.72  5379.2  306.89  5529.2  306.62
  5554.6  307.27  5600.7  307.82  5660.6  314.32  5723.1  318.25  5838.6  318.59
  5876.2  319.64  5968.8  319.07  6014.3  321.28  6064.8  322.05    6216  329.38
#Mann= 9 ,-1 , 0
  4638.2     .17       0    4838     .15       0  4938.5     .11       0
  4988.2     .07       0  5008.7     .11       0  5064.3     .15       0
  5379.2     .11       0  5554.6     .15       0  5838.6     .17       0
Bank Sta=4988.2,5008.7
XS Rating Curve= 0 ,0
Exp/Cntr=0.3,0.1

Type RM Length L Ch R = 1 ,2959    ,498,498,498
BEGIN DESCRIPTION:
TRIBUTARY 4 6.0
END DESCRIPTION:
XS GIS Cut Line= 3
      3786027.49     10243862.09      3785548.26     10243711.28
      3784627.83     10243517.06
#Sta/Elev= 30
  4497.6  327.28  4520.5  326.47  4585.3  320.52  4613.6  319.39  4714.8   310.3
  4759.3  307.21  4822.5  304.83  4889.5  304.27  4984.4  304.54    4994  301.24
  5001.2  301.24  5010.6  303.45  5020.5  304.41  5061.7  303.57  5102.6  304.16
  5194.6  303.49  5255.9  304.28  5450.1  304.19  5463.3  303.59  5501.2   306.6
  5521.6  310.14  5552.3  312.58  5562.8  314.28  5612.9  315.11  5695.4  315.26
  5756.8   318.3  5828.3  320.48  5846.1  319.81  5895.9  320.29  5940.7  324.75
#Mann= 6 ,-1 , 0
  4497.6     .17       0  4613.6     .11       0  4889.5     .15       0
  4984.4     .09       0  5020.5     .15       0  5612.9     .17       0
Bank Sta=4984.4,5020.5
XS Rating Curve= 0 ,0
Exp/Cntr=0.3,0.1

Type RM Length L Ch R = 1 ,2461    ,436,436,436
BEGIN DESCRIPTION:
TRIBUTARY 4 5.0
END DESCRIPTION:
XS GIS Cut Line= 3
      3786217.83     10243361.07      3785624.87     10243289.15
      3784647.36     10243276.16
#Sta/Elev= 30
  4402.7  332.18  4446.1  329.97  4512.8   323.9  4573.9  317.84    4584  315.65
  4609.7  312.53  4704.9  305.85  4731.2  305.03  4805.6  302.54  4956.7  301.91
  4976.9  300.31  4992.3  297.68  4999.6  297.68    5007  300.25    5017   301.6
    5047   301.1    5107     302    5137  301.29    5217  302.22    5237  301.24
  5367.1  302.75  5447.1  301.66  5538.5  303.12  5547.1  302.85  5617.1  307.86
  5717.1     318  5757.1  318.99  5787.1  321.39  5834.5  322.81  5977.6  328.98
#Mann= 7 ,-1 , 0
  4402.7     .17       0  4512.8     .11       0  4731.2     .15       0
  4956.7     .09       0    5017     .15       0  5538.5     .11       0
  5834.5     .17       0
Bank Sta=4956.7,5017
XS Rating Curve= 0 ,0
Exp/Cntr=0.3,0.1

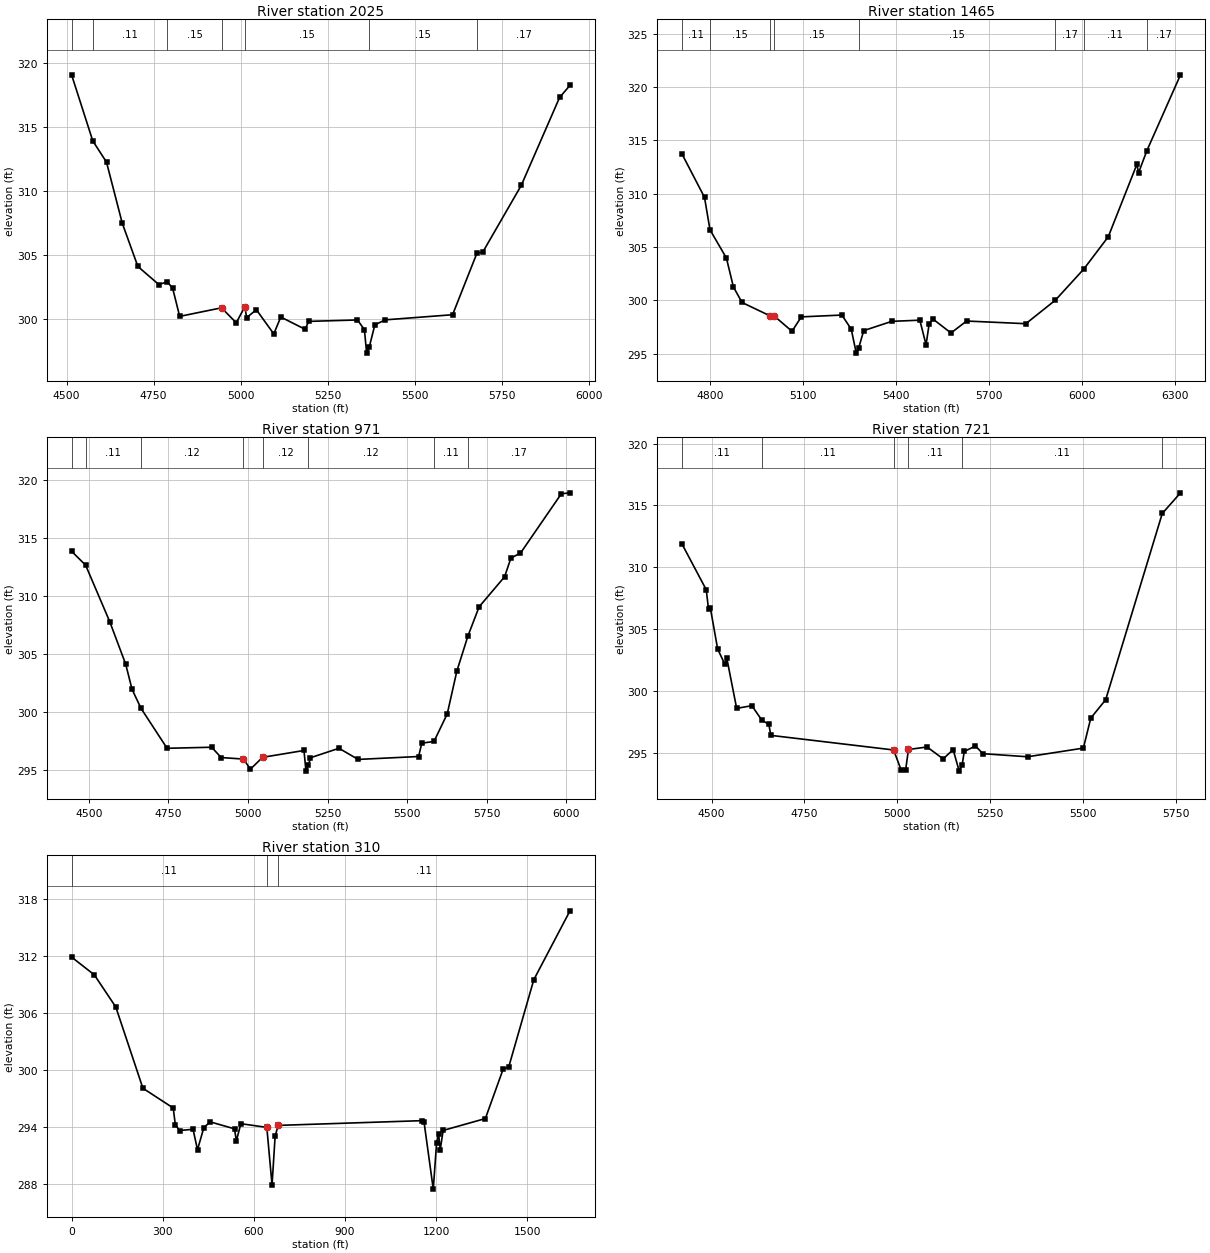
Type RM Length L Ch R = 1 ,2025    ,560,560,560
BEGIN DESCRIPTION:
TRIBUTARY 4 4.0
END DESCRIPTION:
XS GIS Cut Line= 3
      3786238.01     10242896.39      3786092.63     10242892.05
      3784807.95     10242870.35
#Sta/Elev= 30
  4514.5   319.1  4575.3  313.94  4614.7  312.28  4659.8  307.52  4704.7  304.13
  4764.7  302.72  4789.5  302.93  4804.7  302.41  4824.7  300.23  4944.8   300.9
    4987  299.73  5011.8  300.99  5016.8  300.13  5044.8  300.75  5094.8  298.86
  5114.8  300.18  5184.8  299.22  5194.8  299.84  5334.8  299.95  5354.8   299.2
  5361.2  297.36    5369  297.86  5384.8  299.57  5414.8  299.96  5607.9  300.36
  5677.6  305.16  5694.9  305.27  5804.9  310.46  5914.9  317.33  5944.8  318.28
#Mann= 7 ,-1 , 0
  4514.5     .17       0  4575.3     .11       0  4789.5     .15       0
  4944.8     .09       0  5011.8     .15       0    5369     .15       0
  5677.6     .17       0
Bank Sta=4944.8,5011.8
XS Rating Curve= 0 ,0
Exp/Cntr=0.3,0.1

Type RM Length L Ch R = 1 ,1465    ,494,494,494
BEGIN DESCRIPTION:
TRIBUTARY 4 3.0
END DESCRIPTION:
XS GIS Cut Line= 3
      3786139.54     10242395.09      3785888.25      10242427.7
      3784541.92     10242570.77
#Sta/Elev= 30
  4710.2  313.71  4782.5  309.66  4800.1  306.62  4853.1  303.97  4875.8  301.25
  4903.5   299.8  4994.2  298.54  5006.9  298.54  5064.6   297.1  5094.7  298.45
  5225.5  298.62  5255.6   297.3    5272  295.05  5279.9  295.55  5295.9  297.16
  5386.4  298.03  5476.9  298.14    5497  295.83    5507   297.8    5519  298.25
  5577.4  296.94  5627.7  298.06  5818.8  297.81  5914.1  300.02  6005.8  302.94
  6084.5  305.96  6177.1  312.77  6182.1  311.95  6209.1  314.04  6317.5  321.15
#Mann= 8 ,-1 , 0
  4710.2     .11       0  4800.1     .15       0  4994.2     .09       0
  5006.9     .15       0  5279.9     .15       0  5914.1     .17       0
  6005.8     .11       0  6209.1     .17       0
Bank Sta=4994.2,5006.9
XS Rating Curve= 0 ,0
Exp/Cntr=0.3,0.1

Type RM Length L Ch R = 1 ,971     ,250,250,250
BEGIN DESCRIPTION:
TRIBUTARY 4 2.0
END DESCRIPTION:
XS GIS Cut Line= 3
      3786067.81     10242211.07      3785513.61     10242211.96
      3784502.41     10242236.66
#Sta/Elev= 30
  4445.8  313.85  4489.9  312.65  4565.8  307.77  4615.8  304.11  4635.8  301.94
    4664   300.3  4745.8  296.86  4885.8  296.95  4915.8  296.06  4985.8  295.93
  5007.6  295.06  5045.8  296.08  5175.8  296.67  5182.1  294.89    5190  295.39
  5195.8  296.04  5285.8  296.86  5345.9   295.9  5535.9  296.15  5545.9   297.3
  5584.3  297.45  5625.9  299.83    5656  303.51  5690.6  306.52    5726  309.06
    5806  311.65    5826  313.27    5856  313.69  5984.3  318.81  6011.5  318.89
#Mann= 8 ,-1 , 0
  4445.8     .17       0  4489.9     .11       0    4664     .12       0
  4985.8     .08       0  5045.8     .12       0    5190     .12       0
  5584.3     .11       0  5690.6     .17       0
Bank Sta=4985.8,5045.8
XS Rating Curve= 0 ,0
Exp/Cntr=0.3,0.1

Type RM Length L Ch R = 1 ,721     ,411,411,411
BEGIN DESCRIPTION:
TRIBUTARY 4 1.0
END DESCRIPTION:
XS GIS Cut Line= 3
      3786051.39     10242041.35      3785823.12      10241991.9
      3784716.78     10241930.68
#Sta/Elev= 30
  4420.6  311.87  4485.6  308.19  4491.8  306.61  4496.9  306.68  4516.3   303.4
  4535.8  302.16    4541  302.65  4567.5   298.6  4608.4  298.82  4635.2  297.65
  4654.2  297.31  4659.4  296.42  4989.9  295.24  5010.5   293.6  5022.2   293.6
    5030  295.28  5080.1  295.48  5123.4  294.52  5150.2  295.27  5166.5  293.53
  5174.4  294.03  5180.2  295.12  5210.3  295.56  5230.3  294.94  5350.5  294.69
  5500.7  295.39  5520.8  297.82  5560.8   299.3  5713.1  314.35  5762.2  316.02
#Mann= 6 ,-1 , 0
  4420.6     .11       0  4635.2     .11       0  4989.9     .07       0
    5030     .11       0  5174.4     .11       0  5713.1     .17       0
Bank Sta=4989.9,5030
XS Rating Curve= 0 ,0
Exp/Cntr=0.3,0.1

Type RM Length L Ch R = 1 ,310     ,0,0,0
XS GIS Cut Line= 5
      3786095.71     10242035.03      3785972.45     10241831.91
      3785677.31     10241621.84      3785470.71     10241592.33
      3784701.62     10241911.77
#Sta/Elev= 30
       0  311.93    74.8  310.06   145.6  306.67   234.8  298.12   334.6  296.04
   341.4   294.3   355.5  293.67   399.8   293.8   414.5  291.65   435.4  293.98
   456.3  294.58   536.3  293.85   542.4  292.58   557.2  294.39   642.7     294
   659.9  287.93     670  293.07   680.1  294.21    1155  294.71  1160.4  294.53
  1190.6   287.5  1201.5  292.33  1208.1  293.35  1213.5  291.64  1223.1  293.68
  1362.1  294.93  1420.7  300.14  1439.1  300.37  1521.6  309.55  1640.7   316.8
#Mann= 3 , 0 , 0
       0     .11       0   642.7     .07       0   680.1     .11       0
Bank Sta=642.7,680.1
XS Rating Curve= 0 ,0
Exp/Cntr=0.3,0.1

Chan Stop Cuts=-1
Use User Specified Reach Order=0
Composite Channel Slope=5