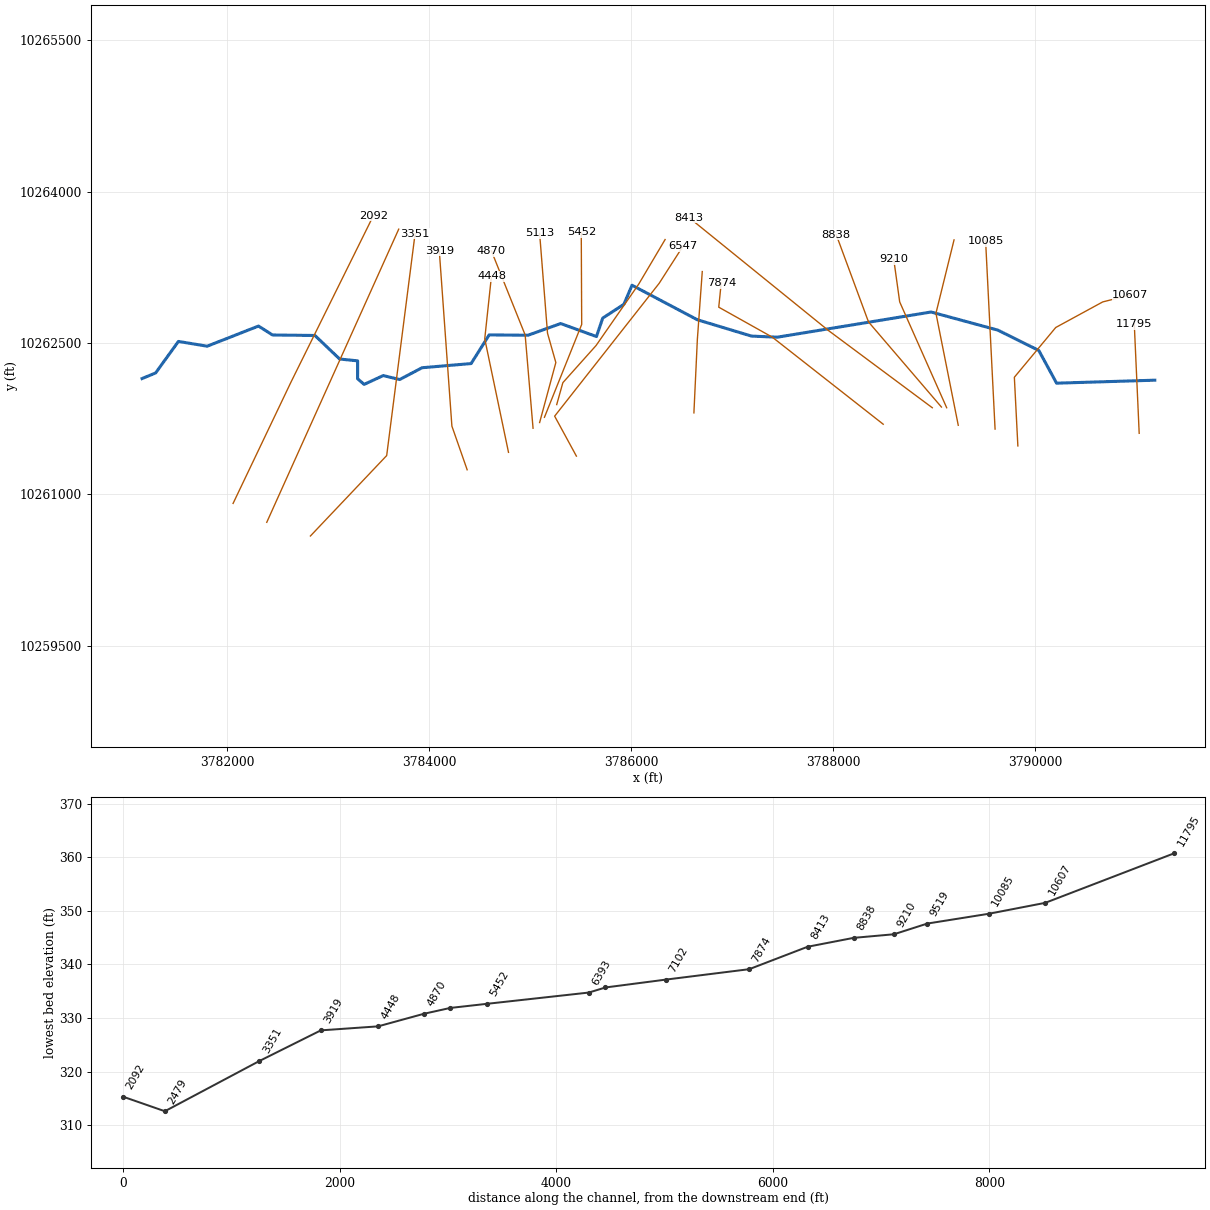
--- TRIBUTARY 5.prj (project) ---

Proj Title=TRIBUTARY 5 Base Level Engineering
Current Plan=p01
Default Exp/Contr=0.3,0.1
English Units
Geom File=g01
Flow File=f01
Plan File=p01
Y Axis Title=Elevation
X Axis Title(PF)=Main Channel Distance
X Axis Title(XS)=Station
BEGIN DESCRIPTION:
TRIBUTARY 5
END DESCRIPTION:
DSS Export Rating Curves= 0
DSS Export Rating Curve Sorted= 0
DSS Export Volume Flow Curves= 0
DXF OffsetX= 0
DXF OffsetY= 0
DXF ScaleX= 1
DXF ScaleY= 10

--- TRIBUTARY 5.p01 (plan) ---

Plan Title=Multiple Run
Program Version=4.10
Short Identifier=Multiple
Geom File=g01
Flow File=f01
Subcritical Flow
K Sum by GR= 0
Std Step Tol= 0.01
Critical Tol= 0.01
Num of Std Step Trials= 20
Max Error Tol= 0.3
Flow Tol Ratio= 0.001
Split Flow NTrial= 30
Split Flow Tol= 0.02
Split Flow Ratio= 0.02
Log Output Level= 0
Friction Slope Method= 1
Unsteady Friction Slope Method= 2
Unsteady Bridges Friction Slope Method= 1
Parabolic Critical Depth
Global Vel Dist= 1 , 1 , 1
Global Log Level= 0
CheckData=True
Encroach Param=-1 ,0,0, 0
BEGIN DESCRIPTION:
Multiple Run
END DESCRIPTION:
Computation Interval=1HOUR
Output Interval=1HOUR
Run HTab= 0
Run UNet= 0
Run PostProcess= 0
Run WQNet= 0
UNET Theta= 1
UNET Theta Warmup= 1
UNET ZTol= 0.02
UNET ZSATol= 0.05
UNET MxIter= 20
UNET MaxInSteps= 0
UNET DtIC= 0
UNET DtMin= 0
UNET MaxCRTS= 20
UNET WFStab= 2
UNET SFStab= 1
UNET WFX= 1
UNET SFX= 1
UNET DSS MLevel= 4
UNET DZMax Abort= 100
UNET Convert EG Bridges= 0
UNET Use Existing IB Tables=-1
UNET Froude Reduction=False
UNET Froude Limit= 1
UNET Froude Power= 10
UNET Time Slicing=0,0, 5
UNET Junction Losses=0
Instantaneous Interval=1HOUR
Write IC File= 0
Write IC File at Sim End=0
Echo Input=False
Echo Parameters=False
Echo Output=False
Write Detailed= 0
WQ AD Non Conservative
WQ ULTIMATE=-1
WQ Max Comp Step=1HOUR
WQ Output Interval=15MIN
WQ Output Selected Increments= 0
WQ Output face flow=0
WQ Output face velocity=0
WQ Output face area=0
WQ Output face dispersion=0
WQ Output cell volume=0
WQ Output cell surface area=0
WQ Output cell continuity=0
WQ Output cumulative cell continuity=0
WQ Output face conc=0
WQ Output face dconc_dx=0
WQ Output face courant=0
WQ Output face peclet=0
WQ Output face adv mass=0
WQ Output face disp mass=0
WQ Output cell mass=0
WQ Output cell source sink temp=0
WQ Output cell source sink nsm=0
WQ Output MaxMinRange=-1
WQ Daily Max Min Mean=-1
WQ Daily Range=0
WQ Daily Time=0
WQ Create Restart=0
WQ Fixed Restart=0
WQ System Summary=0
WQ Use Fixed Temperature=0
Sorting and Armoring Iterations= 10
XS Update Threshold= 0.02
Hydraulics Update Threshold= 0.02
Energy Slope Method= 1
Volume Change Method= 0
XS Weighting Method= 0
Number of US Weighted Cross Sections= 1
Number of DS Weighted Cross Sections= 1
Upstream XS Weight=0.25
Main XS Weight=0.5
Downstream XS Weight=0.25
Number of DS XS's Weighted with US Boundary= 1
Upstream Boundary Weight= 1
Weight of XSs Associated with US Boundary= 0
Number of US XS's Weighted with DS Boundary= 1
Downstream Boundary Weight= 0.5
Weight of XSs Associated with DS Boundary= 0.5
Sediment Output Level= 4
Mass or Volume Output= 0
Output Increment Type= 1
Profile and TS Output Increment= 10
XS Output Flag= 0
XS Output Increment= 10
Disregard all LS=0
Disregard all Conn=0
Disregard all Breaches=0
Disregard all Pumps=0

--- TRIBUTARY 5.f01 (steady flow) ---

Flow Title=Multiple
Program Version=4.10
Number of Profiles= 7
Profile Names=10-year,25-year,50-year,1pct_min,100-year,1pct_plu,500-year
River Rch & RM=TRIBUTARY 5,Reach-1         ,11795
     450     591     783     342    1032    3117    1851
River Rch & RM=TRIBUTARY 5,Reach-1         ,9519
     906    1235    1678     748    2259    6822    4238
Boundary for River Rch & Prof#=TRIBUTARY 5,Reach-1         , 1
Up Type= 0
Dn Type= 3
Dn Slope=0.007
Boundary for River Rch & Prof#=TRIBUTARY 5,Reach-1         , 2
Up Type= 0
Dn Type= 3
Dn Slope=0.007
Boundary for River Rch & Prof#=TRIBUTARY 5,Reach-1         , 3
Up Type= 0
Dn Type= 3
Dn Slope=0.007
Boundary for River Rch & Prof#=TRIBUTARY 5,Reach-1         , 4
Up Type= 0
Dn Type= 3
Dn Slope=0.007
Boundary for River Rch & Prof#=TRIBUTARY 5,Reach-1         , 5
Up Type= 0
Dn Type= 3
Dn Slope=0.007
Boundary for River Rch & Prof#=TRIBUTARY 5,Reach-1         , 6
Up Type= 0
Dn Type= 3
Dn Slope=0.007
Boundary for River Rch & Prof#=TRIBUTARY 5,Reach-1         , 7
Up Type= 0
Dn Type= 3
Dn Slope=0.007
DSS Import GetInterval= 0
DSS Import GetPeak= 0
DSS Import FillOption= 0

--- TRIBUTARY 5.g01 (geometry) ---

Geom Title=Existing Conditions
Program Version=4.10

River Reach=TRIBUTARY 5     ,Reach-1
Reach XY= 30
      3791186.33     10262130.75       3790214.1     10262101.24
      3790037.78     10262425.38      3789632.37     10262626.86
      3788971.16     10262806.39      3787448.23     10262556.84
      3787193.51     10262567.57      3786657.46      10262729.4
      3786009.82     10263071.78      3785929.26     10262882.52
      3785719.74     10262746.04      3785657.76     10262563.33
       3785303.6       10262692.      3784979.78     10262576.16
      3784595.22     10262579.43      3784416.67     10262295.48
        3783931.     10262254.15      3783708.83     10262137.04
      3783546.94     10262176.65      3783357.25     10262089.25
      3783292.66     10262145.19      3783293.22     10262322.46
      3783115.02     10262340.33      3782869.82     10262573.87
       3782450.6     10262578.59      3782311.32     10262667.16
      3781802.87     10262467.49      3781518.31     10262514.81
       3781292.9     10262202.83      3781158.23     10262146.84

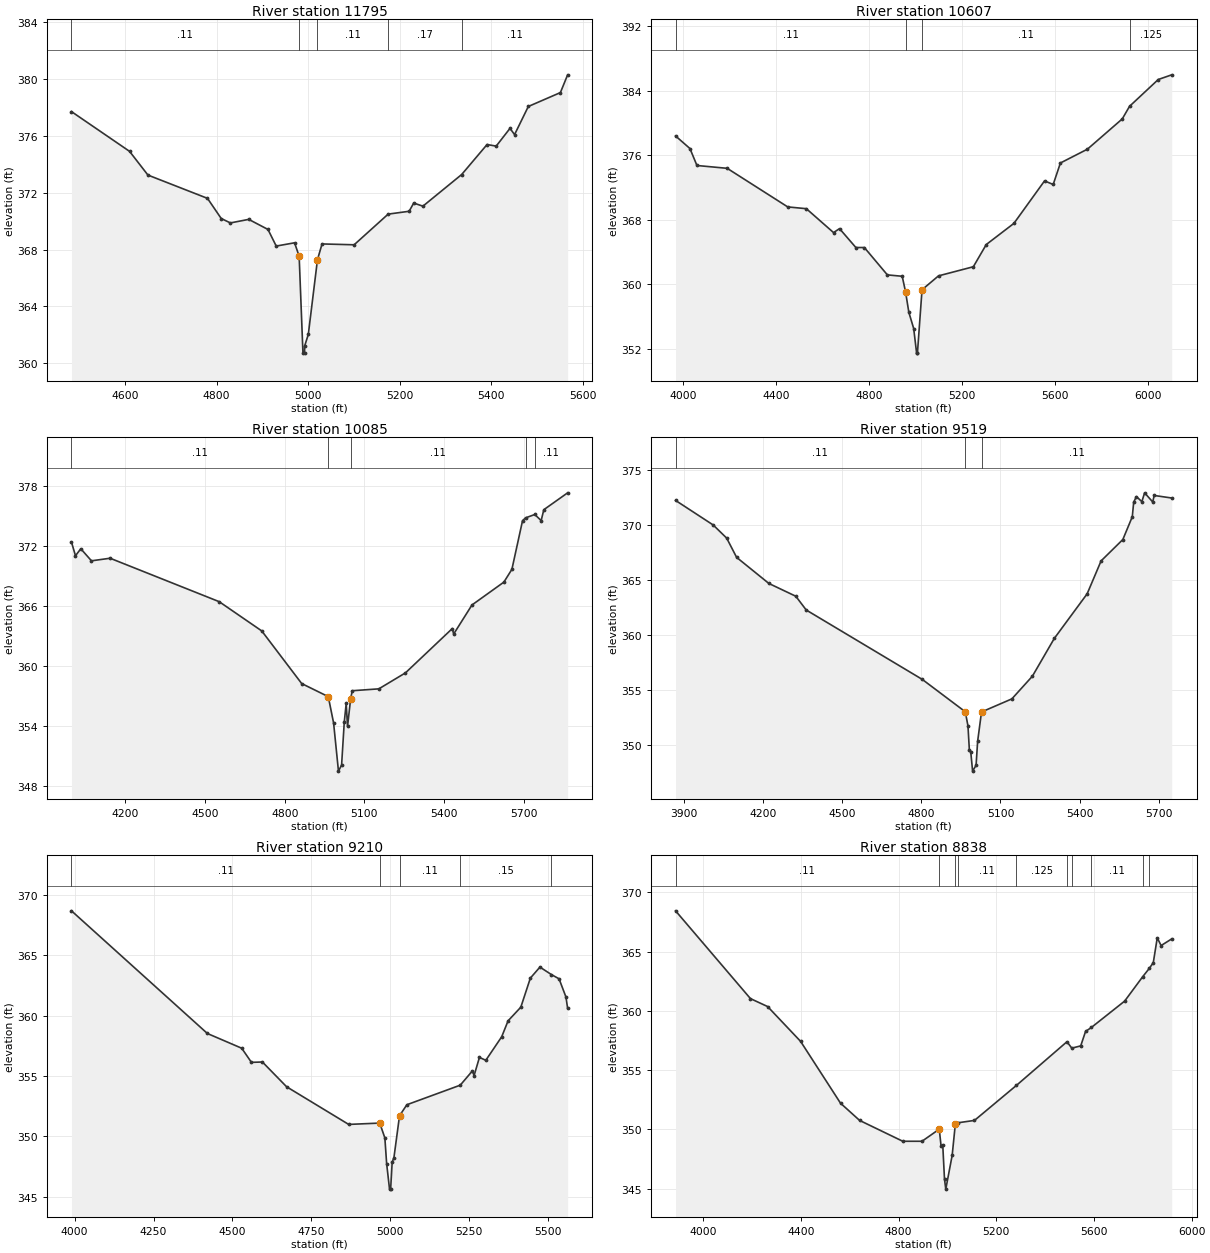
Type RM Length L Ch R = 1 ,11795   ,1188,1188,1188
BEGIN DESCRIPTION:
TRIBUTARY 5 14.0
END DESCRIPTION:
XS GIS Cut Line= 2
      3791031.96     10261604.27      3790983.38     10262686.88
#Sta/Elev= 30
  4483.2  377.72  4610.1  374.92  4650.2  373.25  4780.3  371.61  4810.3  370.19
  4830.3  369.88  4870.4  370.13  4912.4  369.42  4930.4  368.25  4970.5  368.48
  4980.5  367.53  4988.8  360.71  4992.3  360.71  4992.5  361.21  5000.5  362.03
  5020.5  367.29  5030.5   368.4  5100.6  368.34  5174.9   370.5  5220.7   370.7
  5230.7  371.28  5250.8  371.06  5335.5  373.29  5390.9   375.4  5410.9  375.29
    5441  376.54    5451   376.1    5481  378.08  5551.1  379.06  5566.9  380.31
#Mann= 5 ,-1 , 0
  4483.2     .11       0  4980.5     .06       0  5020.5     .11       0
  5174.9     .17       0  5335.5     .11       0
Bank Sta=4980.5,5020.5
XS Rating Curve= 0 ,0
Exp/Cntr=0.3,0.1

Type RM Length L Ch R = 1 ,10607   ,522,522,522
BEGIN DESCRIPTION:
Mapping XS a902e671
END DESCRIPTION:
XS GIS Cut Line= 5
      3789830.57     10261479.23      3789795.85     10262159.83
      3790205.57     10262652.89      3790670.85     10262906.36
      3790944.03     10262975.52
#Sta/Elev= 30
  3967.4  378.39  4029.3  376.83  4059.4  374.73  4189.5  374.38  4449.9   369.6
    4530  369.38    4647  366.42  4672.7  366.91    4743  364.57  4779.5  364.57
  4878.5  361.18  4942.3  361.01  4956.6   359.1  4970.9  356.54  4991.7  354.54
  5004.3  351.49  5007.8  351.49  5027.6  359.34  5098.5  361.06  5248.3  362.19
  5303.9  364.94  5422.8  367.56  5554.5  372.82  5591.8  372.38  5622.8  375.04
    5739  376.75  5888.9   380.5  5920.2  382.06  6043.7  385.38  6101.6  385.96
#Mann= 4 ,-1 , 0
  3967.4     .11       0  4956.6     .06       0  5027.6     .11       0
  5920.2    .125       0
Bank Sta=4956.6,5027.6
XS Rating Curve= 0 ,0
Exp/Cntr=0.3,0.1

Type RM Length L Ch R = 1 ,10085   ,566,566,566
BEGIN DESCRIPTION:
Mapping XS 5e7e477e
END DESCRIPTION:
XS GIS Cut Line= 2
      3789604.87     10261645.99      3789511.12     10263510.54
#Sta/Elev= 30
  3997.7  372.39  4012.8  371.02  4032.8  371.72  4072.9  370.51    4143  370.77
  4553.5  366.42  4713.7  363.49  4863.9  358.22    4964  356.91    4984  354.27
  5002.3  349.45  5014.1  350.06  5024.1  354.35  5031.4  356.23  5036.4  353.93
    5048 356.664  5054.1   357.5  5154.2  357.69  5254.4  359.29  5430.7  363.73
  5435.8  363.18  5504.7  366.09  5624.8  368.38  5654.9  369.66  5694.9  374.53
  5706.1  374.81    5741  375.15    5765  374.54    5775  375.63  5864.6  377.32
#Mann= 5 ,-1 , 0
  3997.7     .11       0    4964     .06       0    5048     .11       0
  5706.1    .125       0    5741     .11       0
Bank Sta=4964,5048
XS Rating Curve= 0 ,0
Exp/Cntr=0.3,0.1

Type RM Length L Ch R = 1 ,9519    ,309,309,309
BEGIN DESCRIPTION:
TRIBUTARY 5 13.0
END DESCRIPTION:
XS GIS Cut Line= 3
      3789240.29     10261684.16      3789019.43     10262793.69
      3789198.62     10263520.94
#Sta/Elev= 30
  3868.7  372.21  4011.3  369.98  4062.4  368.79  4100.1  367.04  4222.4  364.67
  4324.4  363.51  4363.9  362.26  4803.6  355.96  4966.7  353.02  4976.9  351.73
  4982.2  349.51  4987.3  349.41  4994.4  347.63  5007.6  348.16  5013.5  350.34
  5028.2     353  5143.2  354.19    5221  356.25    5304  359.68  5428.5  363.73
  5481.4  366.72  5563.8  368.66  5599.6  370.73  5604.9  372.05  5615.2  372.56
  5635.8   372.1  5646.3   372.9    5677  372.07  5682.6  372.66    5749  372.43
#Mann= 3 , 0 , 0
  3868.7     .11       0  4966.7     .06       0  5028.2     .11       0
Bank Sta=4966.7,5028.2
XS Rating Curve= 0 ,0
Exp/Cntr=0.3,0.1

Type RM Length L Ch R = 1 ,9210    ,372,372,372
BEGIN DESCRIPTION:
TRIBUTARY 5 12.0
END DESCRIPTION:
XS GIS Cut Line= 3
      3789125.69     10261857.79      3788660.43     10262906.36
      3788601.67     10263328.03
#Sta/Elev= 30
  3989.9  368.68  4420.8  358.52  4529.6   357.3  4560.4  356.13  4595.2  356.16
  4671.8  354.11  4868.7  350.99  4967.2   351.1  4983.4  349.87    4989  347.75
  4998.2  345.63  5001.7  345.63  5006.6  347.88  5012.1  348.23  5029.9  351.71
  5053.2  352.62  5222.4  354.24  5261.2  355.43  5266.2  355.03  5283.2  356.54
  5303.4   356.3  5353.8  358.25    5374  359.57  5414.4   360.7  5444.7  363.11
    5475  364.02  5511.4   363.4  5535.6  363.05  5557.5  361.54  5562.8   360.6
#Mann= 5 ,-1 , 0
  3989.9     .11       0  4967.2     .07       0  5029.9     .11       0
  5222.4     .15       0  5511.4    .125       0
Bank Sta=4967.2,5029.9
XS Rating Curve= 0 ,0
Exp/Cntr=0.3,0.1

Type RM Length L Ch R = 1 ,8838    ,425,425,425
BEGIN DESCRIPTION:
TRIBUTARY 5 11.0
END DESCRIPTION:
XS GIS Cut Line= 3
       3789073.6     10261864.72       3788351.4     10262708.44
      3788032.41      10263571.8
#Sta/Elev= 30
  3887.4  368.45    4194  361.04  4264.3  360.37  4399.3  357.43  4562.8  352.21
  4640.8  350.76  4817.5     349  4896.2     349  4966.8  350.02  4974.5  348.56
  4981.1  348.71  4988.3  345.79  4993.6  344.96  5019.7  347.81  5032.8  350.48
  5043.4  350.56    5111  350.76    5283  353.72  5489.5   357.4  5509.4  356.86
  5545.9  357.05  5565.7  358.27  5589.8  358.61  5725.7  360.83  5799.3  362.88
  5827.3  363.61    5843  364.08  5859.2  366.17    5875  365.52  5918.4  366.08
#Mann= 10 ,-1 , 0
  3887.4     .11       0  4966.8     .06       0  5032.8     .11       0
  5043.4     .11       0    5283    .125       0  5489.5     .11       0
  5509.4    .125       0  5589.8     .11       0  5799.3    .125       0
  5827.3     .11       0
Bank Sta=4966.8,5032.8
XS Rating Curve= 0 ,0
Exp/Cntr=0.3,0.1

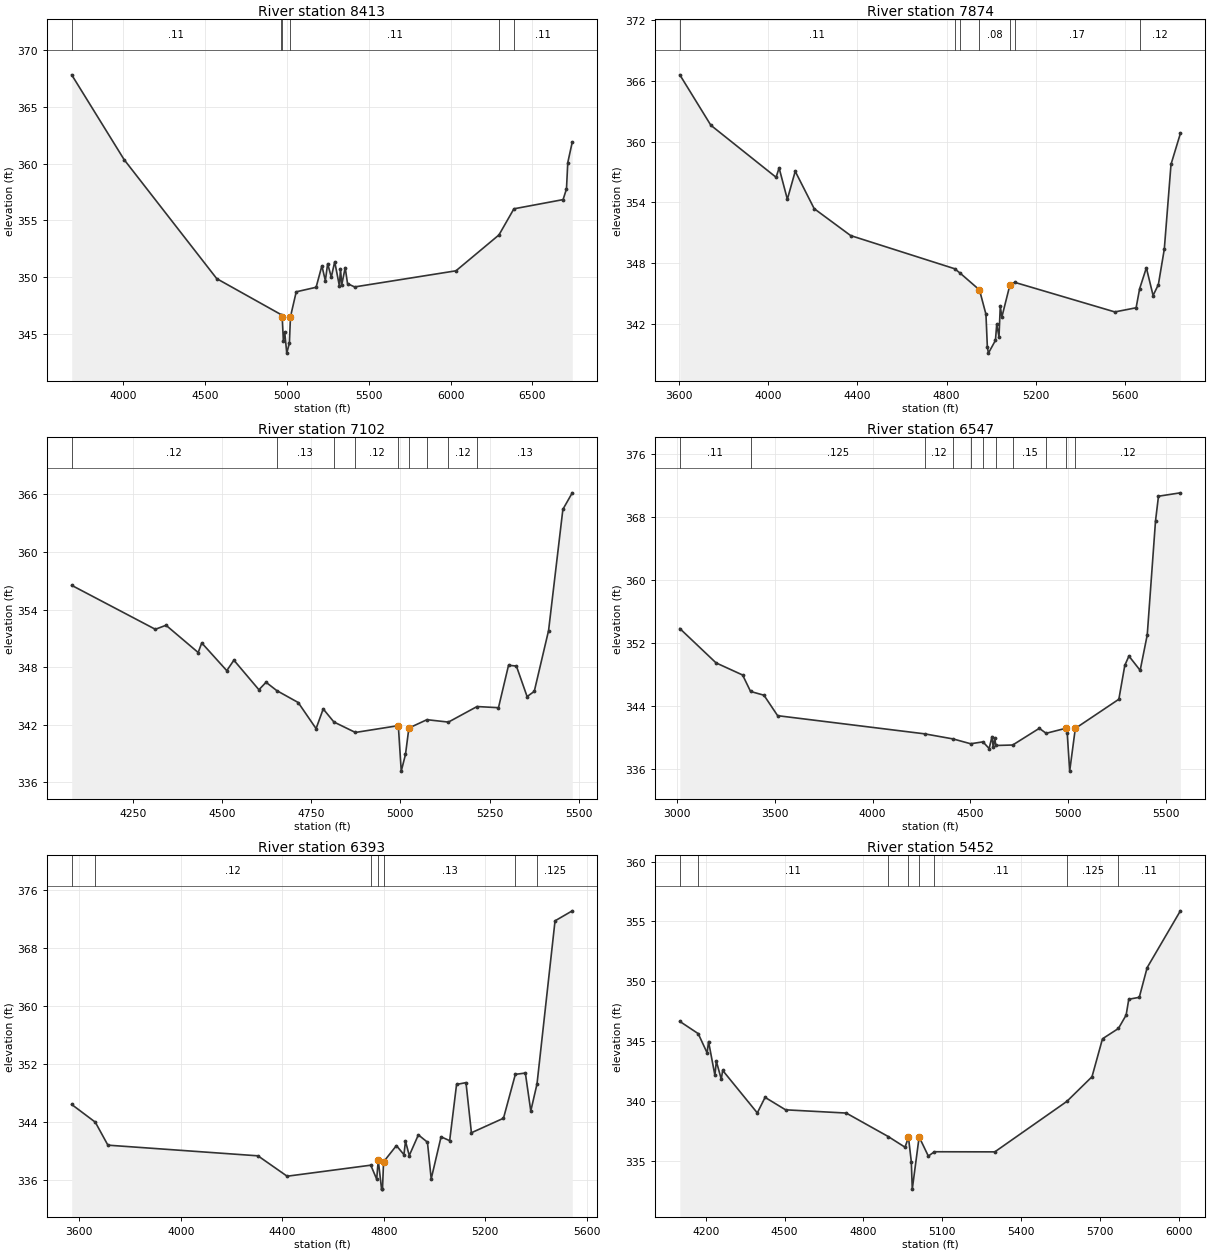
Type RM Length L Ch R = 1 ,8413    ,539,539,539
BEGIN DESCRIPTION:
TRIBUTARY 5 10.0
END DESCRIPTION:
XS GIS Cut Line= 3
      3788983.35     10261857.75       3787952.1     10262625.11
      3786577.12     10263739.67
#Sta/Elev= 30
  3687.5  367.81  4007.6  360.34  4572.8  349.86  4965.8  346.69  4972.5  346.44
  4979.6  344.37  4987.6  345.17  5000.2   343.3  5016.3  344.18  5022.8   346.5
    5058   348.7  5179.4   349.1  5214.6  350.99  5235.8  349.68  5249.8  351.18
  5272.1  349.99  5292.9  351.35  5321.7   349.2  5328.1  350.74    5336  349.33
  5356.9  350.83  5371.2  349.42  5414.4  349.13    6033  350.55  6295.5  353.71
  6386.7  356.01  6686.8  356.82  6707.6  357.76  6715.5  360.08  6742.9  361.89
#Mann= 6 ,-1 , 0
  3687.5     .11       0  4965.8     .11       0  4972.5     .07       0
  5022.8     .11       0  6295.5    .125       0  6386.7     .11       0
Bank Sta=4972.5,5022.8
XS Rating Curve= 0 ,0
Exp/Cntr=0.3,0.1

Type RM Length L Ch R = 1 ,7874    ,772,772,772
BEGIN DESCRIPTION:
TRIBUTARY 5 9.0
END DESCRIPTION:
XS GIS Cut Line= 4
      3788497.25     10261694.54      3787399.53     10262556.67
      3786868.76     10262854.28      3786892.96     10263092.84
#Sta/Elev= 30
  3604.2  366.61  3743.3  361.63  4035.8  356.49  4049.3  357.41  4086.3  354.32
  4121.6  357.08  4206.6  353.39  4370.2  350.73  4835.7  347.46  4858.9  347.06
  4947.7  345.36  4976.6  342.96    4983   339.7  4987.7  339.12  5019.2  340.38
  5024.9  341.96  5035.1  340.75  5040.9  343.77  5047.8  342.67  5084.2  345.87
  5105.9  346.11  5554.4  343.19  5649.8   343.6  5665.6  345.48  5695.8  347.55
  5725.9  344.81  5749.6  345.89  5776.2  349.39  5806.3  357.77  5848.3  360.82
#Mann= 7 ,-1 , 0
  3604.2     .11       0  4835.7    .125       0  4858.9     .12       0
  4947.7     .08       0  5084.2     .12       0  5105.9     .17       0
  5665.6     .12       0
#XS Ineff= 2 ,-1
  5695.8    5775  347.55
Permanent Ineff=
       F       F
Bank Sta=4947.7,5084.2
XS Rating Curve= 0 ,0
Exp/Cntr=0.3,0.1

Type RM Length L Ch R = 1 ,7102    ,555,555,555
BEGIN DESCRIPTION:
TRIBUTARY 5 8.0
END DESCRIPTION:
XS GIS Cut Line= 3
      3786622.71     10261806.95       3786656.8     10262532.69
      3786705.48     10263207.29
#Sta/Elev= 30
  4078.8  356.53  4313.2  351.95  4343.2  352.37  4433.3  349.53  4443.3  350.53
  4513.4  347.64  4533.4  348.73  4603.5  345.65  4623.5  346.43  4653.6  345.56
  4713.6  344.32  4763.7   341.6  4783.7  343.65  4813.7  342.29  4873.9   341.2
  4994.2  341.91  5002.4  337.17  5014.3  338.91  5023.8  341.66  5074.4  342.53
  5134.6  342.28  5214.8   343.9  5274.9  343.78  5303.1   348.2  5325.1  348.12
  5355.1  344.94  5375.2  345.48  5415.3  351.82  5455.4  364.45  5481.7  366.17
#Mann= 9 ,-1 , 0
  4078.8     .12       0  4653.6     .13       0  4813.7     .12       0
  4873.9     .12       0  4994.2     .08       0  5023.8     .12       0
  5074.4     .12       0  5134.6     .12       0  5214.8     .13       0
#XS Ineff= 2 ,-1
    4715  4783.7  343.65  5214.8    5280   343.9
Permanent Ineff=
       F       F
Bank Sta=4994.2,5023.8
XS Rating Curve= 0 ,0
Exp/Cntr=0.3,0.1

Type RM Length L Ch R = 1 ,6547    ,154,154,154
BEGIN DESCRIPTION:
TRIBUTARY 5 7.0
END DESCRIPTION:
XS GIS Cut Line= 4
      3785459.02     10261378.62      3785243.76     10261774.42
      3786278.48     10263090.39      3786514.61     10263458.47
#Sta/Elev= 30
  3013.1  353.84  3198.6  349.47  3334.5  347.93  3375.2  345.84  3443.7  345.36
  3513.7  342.76  4266.1  340.45  4412.2   339.8  4501.4  339.19  4564.5  339.43
  4596.3  338.58  4610.8   340.1  4617.1  338.75  4625.2   339.9  4630.3  338.97
  4716.8  339.03  4852.9  341.15    4888  340.52  4987.6  341.15  4995.7  340.61
  5008.4  335.71  5037.3  341.14  5260.1  344.85  5290.5  349.15  5311.6  350.34
  5369.1  348.52  5405.4  353.03  5447.7  367.52  5462.9  370.66    5575  371.09
#Mann= 11 ,-1 , 0
  3013.1     .11       0  3375.2    .125       0  4266.1     .12       0
  4412.2     .15       0  4501.4    .125       0  4564.5     .15       0
  4630.3    .125       0  4716.8     .15       0    4888     .12       0
  4987.6     .09       0  5037.3     .12       0
Bank Sta=4987.6,5037.3
XS Rating Curve= 0 ,0
Exp/Cntr=0.3,0.1

Type RM Length L Ch R = 1 ,6393    ,941,941,941
BEGIN DESCRIPTION:
TRIBUTARY 5 6.0
END DESCRIPTION:
XS GIS Cut Line= 5
      3785264.25     10261889.02      3785325.01     10262106.01
      3785653.94     10262474.32      3786075.26     10263081.18
       3786337.5     10263524.39
#Sta/Elev= 30
  3569.7  346.43  3662.7  343.99  3712.4  340.82  4303.8  339.35  4418.8  336.54
  4748.5  338.06  4771.8  336.13  4777.9  338.77    4791  334.76  4794.6  334.76
  4798.9  338.52  4849.5  340.76  4879.2  339.51  4885.3  341.36  4900.2  339.39
    4936  342.24  4971.8  341.23  4986.6  336.17  5025.5  341.97  5059.4  341.44
  5086.6  349.19  5123.7  349.44  5145.1  342.53  5271.5  344.53  5318.3  350.58
  5357.7  350.76  5379.1  345.53  5403.6  349.25  5474.7  371.74  5542.6  373.12
#Mann= 7 ,-1 , 0
  3569.7     .13       0  3662.7     .12       0  4748.5     .13       0
  4777.9     .09       0  4798.9     .13       0  5318.3     .11       0
  5403.6    .125       0
#XS Ineff= 2 ,-1
  4849.5    4932  340.76    4936    5065  342.24
Permanent Ineff=
       F       F
Bank Sta=4777.9,4798.9
XS Rating Curve= 0 ,0
Exp/Cntr=0.3,0.1

Type RM Length L Ch R = 1 ,5452    ,339,339,339
BEGIN DESCRIPTION:
TRIBUTARY 5 5.0
END DESCRIPTION:
XS GIS Cut Line= 3
       3785142.7     10261763.09      3785511.64     10262683.27
      3785507.31     10263597.57
#Sta/Elev= 30
  4100.8  346.66  4170.8  345.64  4204.8  344.03  4210.2  344.98  4234.4  342.16
  4239.8  343.34  4258.6  341.84    4264  342.57  4395.8  339.02  4425.4  340.32
  4503.5  339.28  4734.3  339.01  4894.2  337.05  4958.1  336.16  4971.3  336.98
  4982.1  334.95  4985.8  332.66  5011.9  337.02  5046.9  335.42  5070.1  335.78
    5300  335.77  5574.1  339.98    5670  342.04    5710  345.21  5770.6  346.07
    5800  347.19    5810  348.51    5850  348.67    5880  351.15  6006.5  355.89
#Mann= 8 ,-1 , 0
  4100.8    .125       0  4170.8     .11       0  4894.2     .15       0
  4971.3     .09       0  5011.9     .15       0  5070.1     .11       0
  5574.1    .125       0  5770.6     .11       0
Bank Sta=4971.3,5011.9
XS Rating Curve= 0 ,0
Exp/Cntr=0.3,0.1

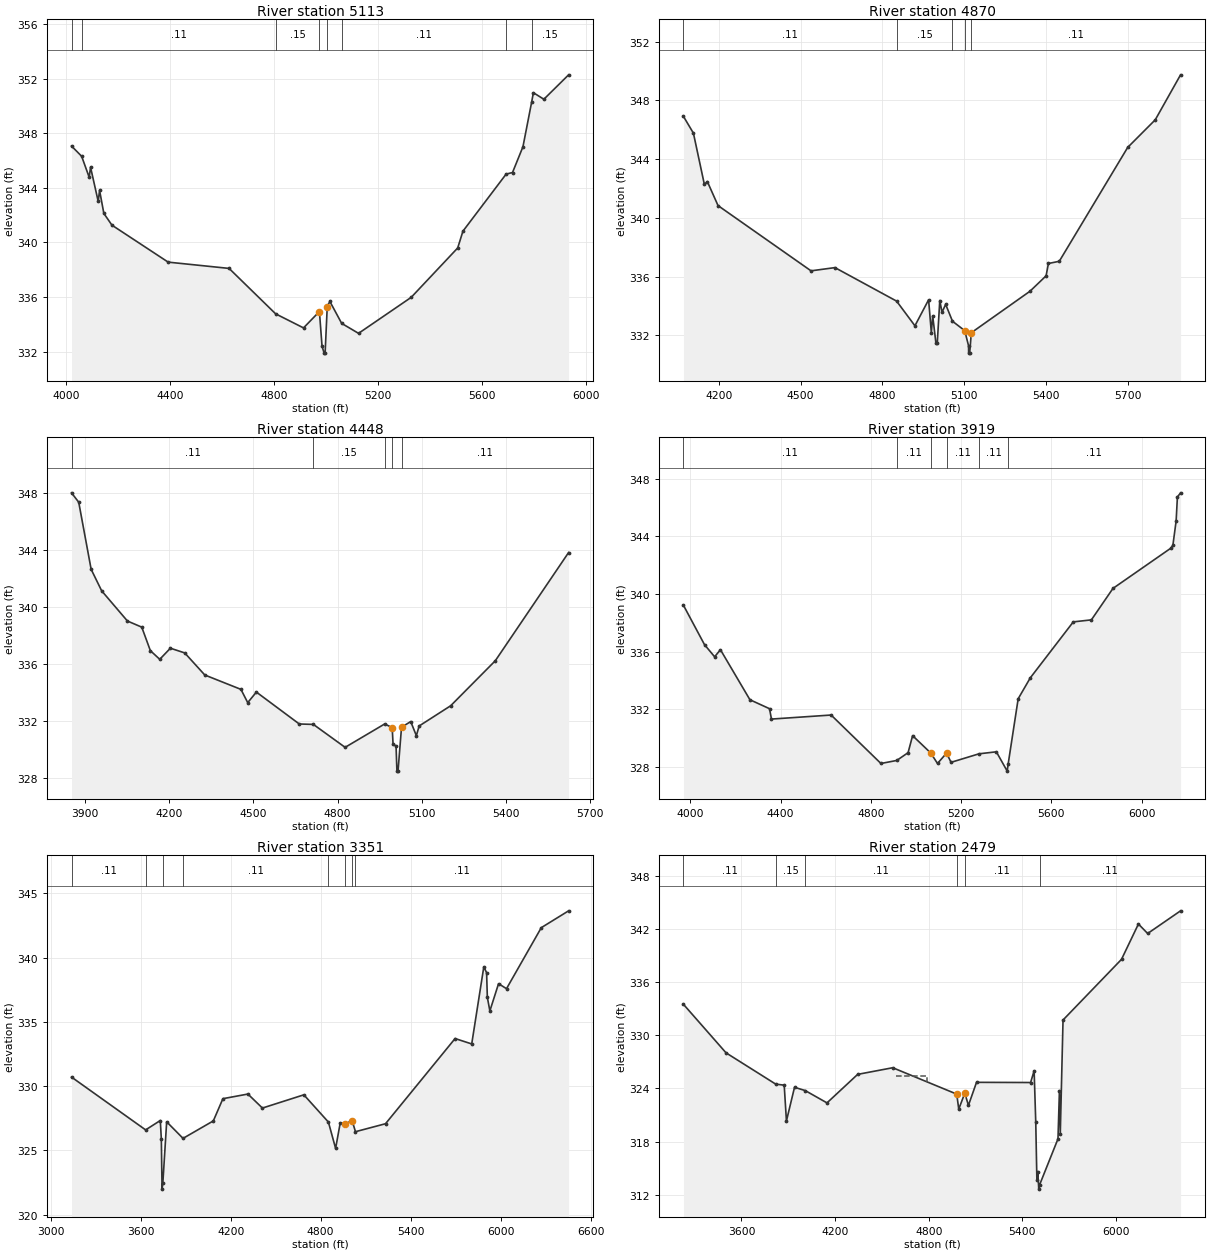
Type RM Length L Ch R = 1 ,5113    ,243,243,243
BEGIN DESCRIPTION:
TRIBUTARY 5 4.0
END DESCRIPTION:
XS GIS Cut Line= 4
      3785094.98     10261711.07      3785255.57     10262305.67
       3785173.1     10262596.47      3785094.98     10263586.02
#Sta/Elev= 30
  4021.1  347.07    4060  346.32    4089  344.78  4094.2  345.52  4123.7  343.01
  4128.9  343.82  4145.4  342.13  4176.5  341.27  4392.6  338.56  4626.8   338.1
  4805.7  334.77  4912.9  333.74    4974  334.94    4984  332.41  4992.1  331.89
  4995.9  331.89  5004.1   335.3  5014.1  335.68  5059.6  334.07  5124.4  333.34
  5326.9  335.98  5505.6   339.6  5525.7  340.83  5691.6  345.01  5716.3  345.13
  5756.4  347.02  5789.9   350.3  5796.5  350.98  5836.8   350.5  5931.9  352.29
#Mann= 8 ,-1 , 0
  4021.1    .125       0    4060     .11       0  4805.7     .15       0
    4974     .09       0  5004.1     .15       0  5059.6     .11       0
  5691.6    .125       0  5789.9     .15       0
Bank Sta=4974,5004.1
XS Rating Curve= 0 ,0
Exp/Cntr=0.3,0.1

Type RM Length L Ch R = 1 ,4870    ,422,422,422
BEGIN DESCRIPTION:
TRIBUTARY 5 3.0
END DESCRIPTION:
XS GIS Cut Line= 3
      3785029.87     10261654.67      3784951.75      10262579.1
      3784617.85     10263411.07
#Sta/Elev= 30
  4070.5  346.91    4107  345.77  4147.2  342.28    4158  342.48  4197.4  340.84
  4538.6   336.4  4626.4  336.62  4852.6  334.34  4919.9  332.66  4970.1  334.43
  4980.1  332.19  4985.1  333.34  4996.7  331.52    5002  331.52  5011.1  334.38
  5019.3  333.58  5032.7  334.12  5057.7  332.97  5102.7  332.33  5116.7   331.3
    5117   330.8  5120.8   330.8  5126.9  332.19    5342  335.01  5401.2  336.06
  5409.8   336.9  5449.6  337.05  5700.7   344.8  5801.9  346.68  5894.7  349.74
#Mann= 5 ,-1 , 0
  4070.5     .11       0  4852.6     .15       0  5057.7     .11       0
  5102.7     .09       0  5126.9     .11       0
Bank Sta=5102.7,5126.9
XS Rating Curve= 0 ,0
Exp/Cntr=0.3,0.1

Type RM Length L Ch R = 1 ,4448    ,529,529,529
BEGIN DESCRIPTION:
TRIBUTARY 5 2.0
END DESCRIPTION:
XS GIS Cut Line= 3
      3784786.83     10261415.87      3784551.63     10262540.64
      3784617.86     10263161.12
#Sta/Elev= 30
  3850.9     348  3876.6  347.34  3920.9  342.63  3958.4  341.12  4050.3     339
  4101.4  338.57  4132.1  336.92  4165.6  336.31  4203.6  337.09  4254.7  336.76
  4326.2  335.21  4455.2   334.2  4479.4  333.27  4510.3  334.01  4663.3  331.77
  4713.6  331.74  4826.8  330.13  4967.7  331.77  4994.7  331.52  4997.7  330.39
  5008.5   330.2  5011.6  328.46  5015.5  328.46    5028 331.541  5060.8  331.94
  5080.9  330.95  5090.9  331.63  5203.3  333.05  5362.5  336.21    5624  343.81
#Mann= 5 ,-1 , 0
  3850.9     .11       0  4713.6     .15       0  4967.7     .11       0
  4994.7     .06       0    5028     .11       0
Bank Sta=4994.7,5028
XS Rating Curve= 0 ,0
Exp/Cntr=0.3,0.1

Type RM Length L Ch R = 1 ,3919    ,568,568,568
BEGIN DESCRIPTION:
Mapping XS 8935a7ae
END DESCRIPTION:
XS GIS Cut Line= 3
      3784377.46     10261243.12       3784226.4     10261675.46
       3784101.4     10263415.01
#Sta/Elev= 30
    3970  339.21  4063.2  336.48    4108  335.64  4133.8  336.13  4264.4  332.66
  4351.1  332.04  4359.8  331.32  4624.1   331.6  4844.7  328.24  4914.8  328.45
    4965  328.99    4985  330.17  5065.2  328.97  5095.3  328.24  5135.4  328.96
  5155.4  328.32  5278.9  328.91    5356  329.05  5404.1  327.71  5408.4  328.21
  5452.7  332.73  5506.4  334.18  5696.8  338.06    5777   338.2  5872.5  340.38
  6127.9  343.16    6138  343.37  6152.4  345.06    6158  346.72    6172  347.01
#Mann= 6 ,-1 , 0
    3970     .11       0  4914.8     .11       0  5065.2     .06       0
  5135.4     .11       0  5278.9     .11       0  5408.4     .11       0
Bank Sta=5065.2,5135.4
XS Rating Curve= 0 ,0
Exp/Cntr=0.3,0.1

Type RM Length L Ch R = 1 ,3351    ,872,872,872
BEGIN DESCRIPTION:
Mapping XS 81b51cef
END DESCRIPTION:
XS GIS Cut Line= 3
      3782825.38     10260586.94      3783580.57     10261383.79
      3783861.82     10263581.72
#Sta/Elev= 30
  3139.2  330.71  3633.2   326.6    3731  327.33  3737.9  325.89  3742.7  321.99
  3748.1  322.49  3773.5  327.23  3882.6  325.94  4084.5   327.3  4148.4  329.03
    4315  329.39  4411.7   328.3    4688  329.33  4851.6  327.21  4899.7  325.16
  4929.9  327.11  4964.7  327.09  5010.6  327.29    5032  326.46  5232.4  327.08
  5696.1  333.71    5807  333.29  5887.7   339.3  5906.2  338.83  5911.2  336.91
    5928  335.86  5985.9  337.98  6038.9  337.59  6270.8  342.34  6452.9  343.65
#Mann= 8 ,-1 , 0
  3139.2     .11       0  3633.2     .15       0  3748.1     .15       0
  3882.6     .11       0  4851.6     .15       0  4964.7     .06       0
  5010.6     .15       0    5032     .11       0
#XS Ineff= 2 ,-1
    3280    4315  329.39    4320    4688  329.33
Permanent Ineff=
       F       F
Bank Sta=4964.7,5010.6
XS Rating Curve= 0 ,0
Exp/Cntr=0.3,0.1

Type RM Length L Ch R = 1 ,2479    ,387,387,387
BEGIN DESCRIPTION:
Mapping XS c131d129
END DESCRIPTION:
XS GIS Cut Line= 2
      3782393.08     10260722.37      3783699.78      10263627.3
#Sta/Elev= 30
  3228.6   333.5  3501.5  328.02  3819.6  324.49  3874.1  324.37  3888.4  320.33
  3940.2  324.13  4008.9  323.76  4148.3  322.37  4344.8  325.59  4569.6  326.34
  4979.6  323.36  4992.6  321.67  5031.4  323.47  5054.6  322.09  5106.4  324.69
  5453.1  324.67  5475.6     326    5486   320.2  5493.3  313.62  5498.8  314.61
  5505.4  312.63    5511  313.13  5628.5  318.31  5637.7  323.75  5643.2  318.91
  5660.8  331.73  6035.5  338.58  6143.9  342.57  6203.1   341.5  6413.9  344.06
#Mann= 6 ,-1 , 0
  3228.6     .11       0  3819.6     .15       0  4008.9     .11       0
  4979.6     .06       0  5031.4     .11       0    5511     .11       0
#XS Ineff= 3 ,-1
    3600  4569.6  326.34                            4590  4788.9  325.44
Permanent Ineff=
       F       F       F
Bank Sta=4979.6,5031.4
XS Rating Curve= 0 ,0
Exp/Cntr=0.3,0.1

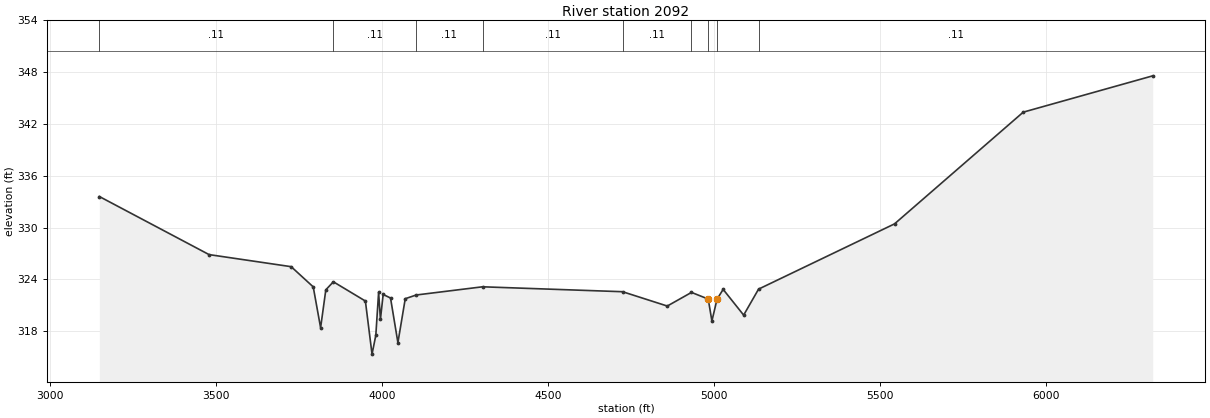
Type RM Length L Ch R = 1 ,2092    ,0,0,0
BEGIN DESCRIPTION:
TRIBUTARY 5 1.0
END DESCRIPTION:
XS GIS Cut Line= 3
      3782059.74     10260909.84      3782632.65     10262111.22
      3783448.62     10263760.52
#Sta/Elev= 30
    3150  333.61  3480.3  326.88  3727.5  325.48  3793.9  323.14  3816.1  318.41
  3831.8   322.8  3854.5  323.73  3950.9   321.5  3970.9  315.35  3982.3  317.53
  3990.7   322.5  3996.2  319.39  4004.4  322.26  4026.6  321.85  4048.8  316.68
  4070.9  321.77  4103.9   322.2  4303.6  323.15  4725.1  322.58  4859.7  320.92
  4932.6   322.5    4983  321.73    4994  319.19  5009.6 321.723  5027.9  322.85
  5089.6  319.87  5134.5  322.88  5543.8  330.44  5931.2  343.38  6321.1  347.59
#Mann= 9 ,-1 , 0
    3150     .11       0  3854.5     .11       0  4103.9     .11       0
  4303.6     .11       0  4725.1     .11       0  4932.6     .11       0
    4983     .06       0  5009.6     .11       0  5134.5     .11       0
Bank Sta=4983,5009.6
XS Rating Curve= 0 ,0
Exp/Cntr=0.3,0.1

Chan Stop Cuts=-1
Use User Specified Reach Order=0
Composite Channel Slope=5