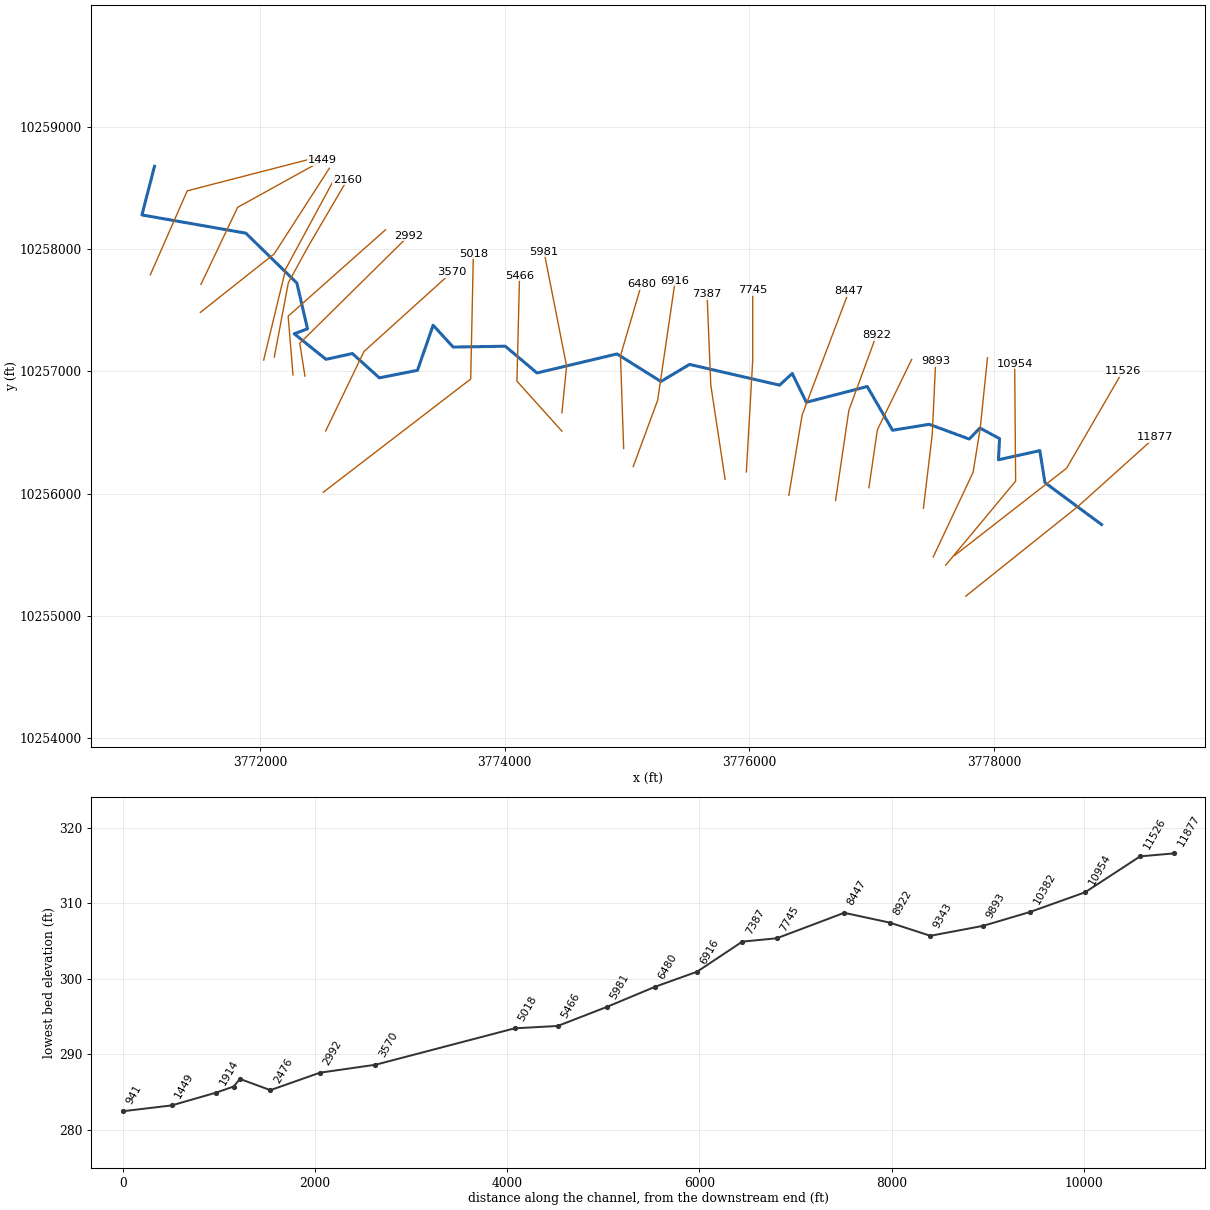
--- TRIBUTARY 6.prj (project) ---

Proj Title=TRIBUTARY 6 Base Level Engineering
Current Plan=p01
Default Exp/Contr=0.3,0.1
English Units
Geom File=g01
Flow File=f01
Plan File=p01
Y Axis Title=Elevation
X Axis Title(PF)=Main Channel Distance
X Axis Title(XS)=Station
BEGIN DESCRIPTION:
TRIBUTARY 6
END DESCRIPTION:
DSS Export Rating Curves= 0
DSS Export Rating Curve Sorted= 0
DSS Export Volume Flow Curves= 0
DXF OffsetX= 0
DXF OffsetY= 0
DXF ScaleX= 1
DXF ScaleY= 10

--- TRIBUTARY 6.p01 (plan) ---

Plan Title=Multiple Run
Program Version=4.10
Short Identifier=Multiple
Geom File=g01
Flow File=f01
Subcritical Flow
K Sum by GR= 0
Std Step Tol= 0.01
Critical Tol= 0.01
Num of Std Step Trials= 20
Max Error Tol= 0.3
Flow Tol Ratio= 0.001
Split Flow NTrial= 30
Split Flow Tol= 0.02
Split Flow Ratio= 0.02
Log Output Level= 0
Friction Slope Method= 1
Unsteady Friction Slope Method= 2
Unsteady Bridges Friction Slope Method= 1
Parabolic Critical Depth
Global Vel Dist= 1 , 1 , 1
Global Log Level= 0
CheckData=True
Encroach Param=-1 ,0,0, 0
BEGIN DESCRIPTION:
Multiple Run
END DESCRIPTION:
Computation Interval=1HOUR
Output Interval=1HOUR
Run HTab= 0
Run UNet= 0
Run PostProcess= 0
Run WQNet= 0
UNET Theta= 1
UNET Theta Warmup= 1
UNET ZTol= 0.02
UNET ZSATol= 0.05
UNET MxIter= 20
UNET MaxInSteps= 0
UNET DtIC= 0
UNET DtMin= 0
UNET MaxCRTS= 20
UNET WFStab= 2
UNET SFStab= 1
UNET WFX= 1
UNET SFX= 1
UNET DSS MLevel= 4
UNET DZMax Abort= 100
UNET Convert EG Bridges= 0
UNET Use Existing IB Tables=-1
UNET Froude Reduction=False
UNET Froude Limit= 1
UNET Froude Power= 10
UNET Time Slicing=0,0, 5
UNET Junction Losses=0
Instantaneous Interval=1HOUR
Write IC File= 0
Write IC File at Sim End=0
Echo Input=False
Echo Parameters=False
Echo Output=False
Write Detailed= 0
WQ AD Non Conservative
WQ ULTIMATE=-1
WQ Max Comp Step=1HOUR
WQ Output Interval=15MIN
WQ Output Selected Increments= 0
WQ Output face flow=0
WQ Output face velocity=0
WQ Output face area=0
WQ Output face dispersion=0
WQ Output cell volume=0
WQ Output cell surface area=0
WQ Output cell continuity=0
WQ Output cumulative cell continuity=0
WQ Output face conc=0
WQ Output face dconc_dx=0
WQ Output face courant=0
WQ Output face peclet=0
WQ Output face adv mass=0
WQ Output face disp mass=0
WQ Output cell mass=0
WQ Output cell source sink temp=0
WQ Output cell source sink nsm=0
WQ Output MaxMinRange=-1
WQ Daily Max Min Mean=-1
WQ Daily Range=0
WQ Daily Time=0
WQ Create Restart=0
WQ Fixed Restart=0
WQ System Summary=0
WQ Use Fixed Temperature=0
Sorting and Armoring Iterations= 10
XS Update Threshold= 0.02
Hydraulics Update Threshold= 0.02
Energy Slope Method= 1
Volume Change Method= 0
XS Weighting Method= 0
Number of US Weighted Cross Sections= 1
Number of DS Weighted Cross Sections= 1
Upstream XS Weight=0.25
Main XS Weight=0.5
Downstream XS Weight=0.25
Number of DS XS's Weighted with US Boundary= 1
Upstream Boundary Weight= 1
Weight of XSs Associated with US Boundary= 0
Number of US XS's Weighted with DS Boundary= 1
Downstream Boundary Weight= 0.5
Weight of XSs Associated with DS Boundary= 0.5
Sediment Output Level= 4
Mass or Volume Output= 0
Output Increment Type= 1
Profile and TS Output Increment= 10
XS Output Flag= 0
XS Output Increment= 10
Disregard all LS=0
Disregard all Conn=0
Disregard all Breaches=0
Disregard all Pumps=0

--- TRIBUTARY 6.f01 (steady flow) ---

Flow Title=Multiple
Program Version=4.10
Number of Profiles= 7
Profile Names=10-year,25-year,50-year,1pct_min,100-year,1pct_plu,500-year
River Rch & RM=TRIBUTARY 6,Reach-1         ,11877
    1147    1593    2190     988    2984    9012    5728
River Rch & RM=TRIBUTARY 6,Reach-1         ,10954
    1147    1593    2190     988    2984    9012    5728
River Rch & RM=TRIBUTARY 6,Reach-1         ,6916
    1243    1736    2395    1085    3276    9893    6340
River Rch & RM=TRIBUTARY 6,Reach-1         ,5018
    1478    2073    2866    1299    3923   11847    7611
River Rch & RM=TRIBUTARY 6,Reach-1         ,3570
    1478    2073    2866    1299    3923   11847    7611
River Rch & RM=TRIBUTARY 6,Reach-1         ,2160
    1543    2169    3003    1363    4116   12430    8007
Boundary for River Rch & Prof#=TRIBUTARY 6,Reach-1         , 1
Up Type= 0
Dn Type= 3
Dn Slope=0.003
Boundary for River Rch & Prof#=TRIBUTARY 6,Reach-1         , 2
Up Type= 0
Dn Type= 3
Dn Slope=0.003
Boundary for River Rch & Prof#=TRIBUTARY 6,Reach-1         , 3
Up Type= 0
Dn Type= 3
Dn Slope=0.003
Boundary for River Rch & Prof#=TRIBUTARY 6,Reach-1         , 4
Up Type= 0
Dn Type= 3
Dn Slope=0.003
Boundary for River Rch & Prof#=TRIBUTARY 6,Reach-1         , 5
Up Type= 0
Dn Type= 3
Dn Slope=0.003
Boundary for River Rch & Prof#=TRIBUTARY 6,Reach-1         , 6
Up Type= 0
Dn Type= 3
Dn Slope=0.003
Boundary for River Rch & Prof#=TRIBUTARY 6,Reach-1         , 7
Up Type= 0
Dn Type= 3
Dn Slope=0.003
DSS Import GetInterval= 0
DSS Import GetPeak= 0
DSS Import FillOption= 0

--- TRIBUTARY 6.g01 (geometry) ---

Geom Title=Existing Conditions
Program Version=4.10

River Reach=TRIBUTARY 6     ,Reach-1
Reach XY= 30
      3778878.23     10255746.84       3778415.5      10256089.7
      3778373.04     10256351.44      3778035.15     10256277.01
      3778044.46     10256449.99      3777883.83     10256536.28
      3777796.25     10256446.49      3777469.42     10256566.88
      3777169.77     10256518.23      3776963.06     10256875.99
      3776465.18     10256746.94      3776350.12     10256982.38
       3776246.4     10256887.25      3775510.56     10257056.79
      3775277.05     10256916.99      3774918.15     10257142.49
      3774264.18     10256987.03      3774004.96     10257205.65
      3773579.05     10257198.62      3773415.53     10257377.28
      3773287.46     10257008.76      3772975.86     10256946.81
       3772755.7     10257145.72      3772539.71     10257098.36
      3772280.12     10257307.79      3772388.67     10257347.76
       3772302.1      10257722.3      3771884.45     10258130.39
      3771035.68     10258279.32      3771138.23     10258676.84

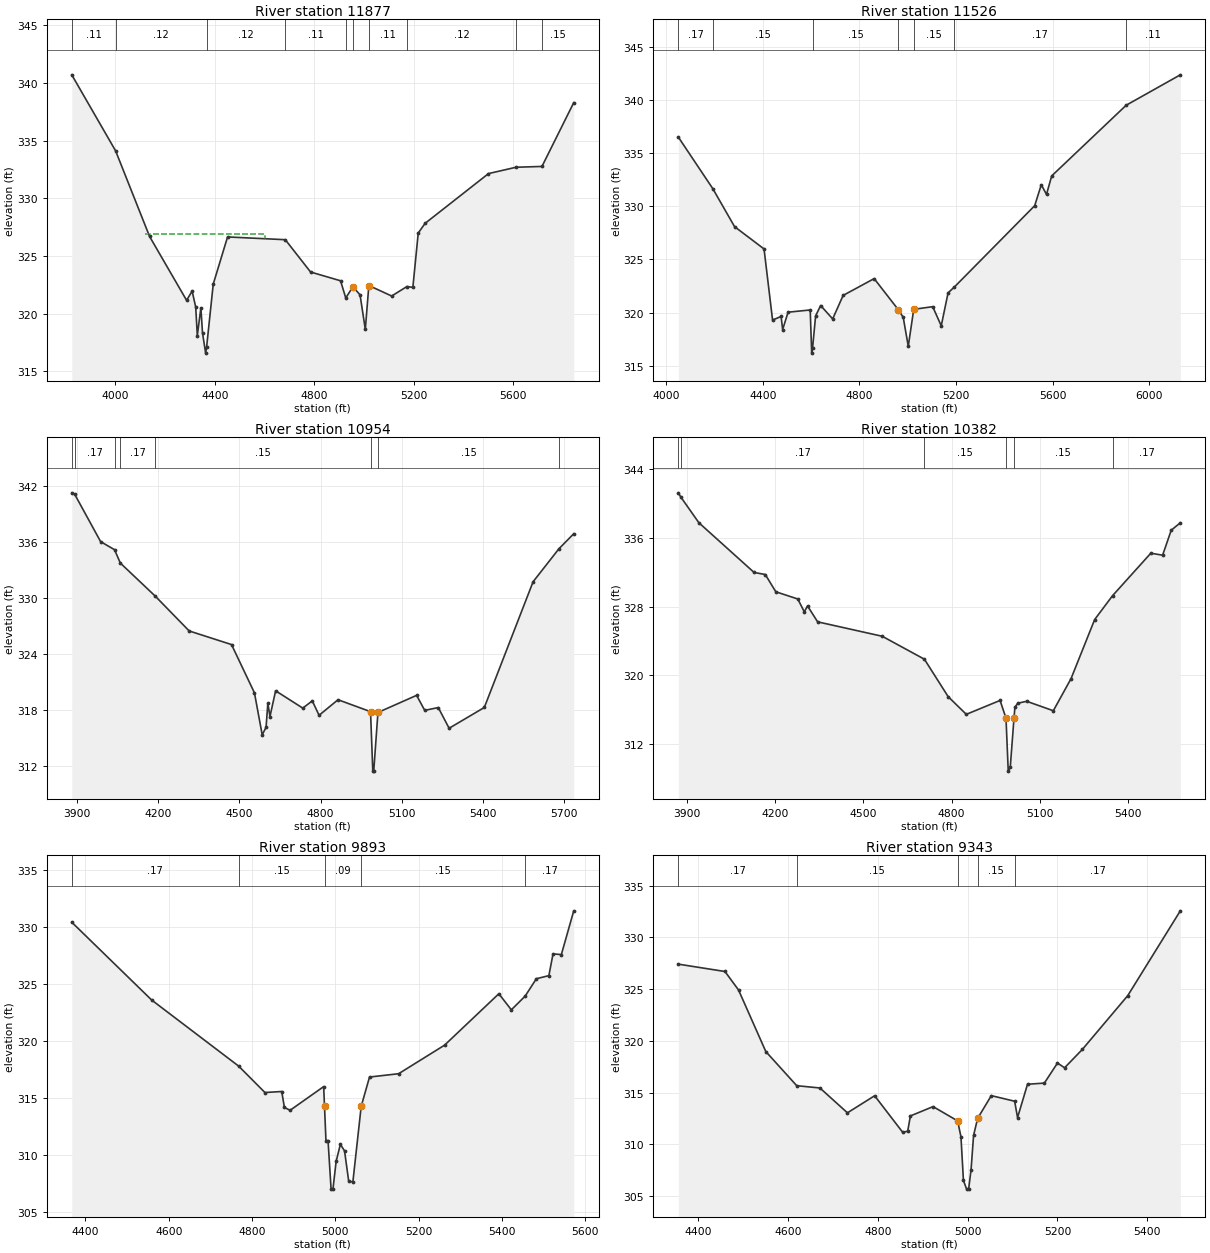
Type RM Length L Ch R = 1 ,11877   ,351,351,351
BEGIN DESCRIPTION:
TRIBUTARY 6 21.0
END DESCRIPTION:
XS GIS Cut Line= 3
      3777767.84     10255161.06      3778685.71      10255895.6
      3779312.79      10256459.9
#Sta/Elev= 30
  3824.4   340.7  4000.8  334.11  4137.4  326.69  4286.2  321.16  4308.6  321.95
    4323  320.57  4329.4   318.1  4343.8  320.51  4350.3  318.33  4362.9  316.58
  4366.7  317.08  4393.5  322.56  4451.1  326.65  4683.4  326.41    4785  323.61
  4905.7  322.85  4926.5  321.36  4955.3  322.33  4984.1  321.63  5005.2  318.63
  5019.4  322.44  5111.3  321.53  5172.5  322.35  5196.5  322.28  5218.1  326.99
  5245.8  327.83  5500.7  332.14  5611.5  332.69  5715.8  332.76  5843.6  338.29
#Mann= 10 ,-1 , 0
  3824.4     .11       0  4000.8     .12       0  4366.7     .12       0
  4683.4     .11       0  4926.5     .11       0  4955.3     .06       0
  5019.4     .11       0  5172.5     .12       0  5611.5     .11       0
  5715.8     .15       0
#XS Ineff= 1 ,-1
    4120    4600  326.91
Permanent Ineff=
       T
Bank Sta=4955.3,5019.4
XS Rating Curve= 0 ,0
Exp/Cntr=0.3,0.1

Type RM Length L Ch R = 1 ,11526   ,572,572,572
BEGIN DESCRIPTION:
TRIBUTARY 6 20.0
END DESCRIPTION:
XS GIS Cut Line= 3
      3777677.41     10255494.45      3778592.28     10256208.14
      3779052.34     10257002.41
#Sta/Elev= 30
  4050.4  336.51  4192.8  331.67  4283.1  328.09  4405.2  325.99  4440.5   319.3
  4475.8  319.64  4482.2  318.41  4504.7  320.04  4596.3  320.25  4602.5  316.19
  4606.2  316.69  4618.7  319.69  4639.5  320.67  4689.3  319.41  4732.7  321.62
  4861.1   323.2  4960.6  320.29  4981.4  319.56  5002.3  316.83  5024.9  320.31
  5103.5  320.56  5138.8  318.76  5167.1  321.86  5192.8   322.4  5525.7  330.06
    5553  332.03  5574.6  331.12  5596.1  332.86  5904.5  339.51  6128.6  342.37
#Mann= 7 ,-1 , 0
  4050.4     .17       0  4192.8     .15       0  4606.2     .15       0
  4960.6     .09       0  5024.9     .15       0  5192.8     .17       0
  5904.5     .11       0
#XS Ineff= 1 ,-1
    4410  4861.1   323.2
Permanent Ineff=
       F
Bank Sta=4960.6,5024.9
XS Rating Curve= 0 ,0
Exp/Cntr=0.3,0.1

Type RM Length L Ch R = 1 ,10954   ,572,572,572
BEGIN DESCRIPTION:
TRIBUTARY 6 19.0
END DESCRIPTION:
XS GIS Cut Line= 3
      3777604.31     10255414.65      3778175.78     10256102.63
      3778167.85     10257061.03
#Sta/Elev= 30
  3881.6   341.3  3891.9  341.17  3988.2  336.06  4039.4   335.2    4061  333.76
  4188.9  330.24    4315  326.48  4471.2  325.02  4555.9  319.84  4584.5  315.34
  4598.8  316.14  4605.3  318.72  4613.2   317.3    4634  320.06  4734.3   318.2
  4769.4  318.98  4794.4  317.43  4864.4   319.1  4984.4  317.82  4992.7  311.44
  4996.2  311.44  5011.7 317.734  5154.4  319.57  5184.4  317.96  5234.4  318.26
  5274.4  316.04  5404.4  318.27  5584.4  331.76  5679.8   335.3  5734.4  336.91
#Mann= 8 ,-1 , 0
  3881.6     .15       0  3891.9     .17       0  4039.4     .15       0
    4061     .17       0  4188.9     .15       0  4984.4     .09       0
  5011.7     .15       0  5679.8     .17       0
Bank Sta=4984.4,5011.7
XS Rating Curve= 0 ,0
Exp/Cntr=0.3,0.1

Type RM Length L Ch R = 1 ,10382   ,489,489,489
BEGIN DESCRIPTION:
TRIBUTARY 6 18.0
END DESCRIPTION:
XS GIS Cut Line= 4
      3777502.89     10255483.36      3777828.06     10256174.18
      3777886.47     10256535.47      3777945.58     10257110.94
#Sta/Elev= 30
  3870.5  341.24  3877.9   340.8  3940.3  337.76  4128.2  331.97  4166.4  331.73
  4202.1  329.72  4276.9  328.88    4299  327.39  4310.1  328.07  4344.4  326.22
  4564.3  324.54  4707.7  321.87  4788.6  317.51  4850.3  315.45  4965.2  317.07
  4985.4     315    4993  308.84    5000  309.34  5012.7 315.083  5015.7  316.28
  5025.7  316.75  5055.9  316.97  5146.4  315.87  5206.7  319.61  5287.1  326.49
  5347.8  329.26  5478.1  334.21  5518.3  333.98  5547.6  336.89  5578.5  337.75
#Mann= 6 ,-1 , 0
  3870.5     .15       0  3877.9     .17       0  4707.7     .15       0
  4985.4     .09       0  5012.7     .15       0  5347.8     .17       0
Bank Sta=4985.4,5012.7
XS Rating Curve= 0 ,0
Exp/Cntr=0.3,0.1

Type RM Length L Ch R = 1 ,9893    ,550,550,550
BEGIN DESCRIPTION:
TRIBUTARY 6 17.0
END DESCRIPTION:
XS GIS Cut Line= 3
      3777422.19     10255880.66      3777494.54     10256487.02
      3777522.19     10257080.71
#Sta/Elev= 30
  4367.3  330.43  4559.1   323.6  4767.9   317.8    4831  315.48  4871.3  315.57
  4877.8  314.17  4891.4  313.92    4972     316    4974 314.276  4977.5  311.26
  4982.5  311.26  4989.8     307  4994.3     307    5002  309.45  5012.1  310.93
  5022.1  310.36  5032.1   307.7  5042.1  307.63  5062.1  314.27  5082.1  316.84
  5151.9  317.13  5262.3  319.64  5392.5  324.15  5422.5  322.74  5455.6  323.94
  5482.6  325.47  5512.6  325.74  5522.6  327.65  5542.6  327.59  5572.3  331.43
#Mann= 5 ,-1 , 0
  4367.3     .17       0  4767.9     .15       0    4974     .09       0
  5062.1     .15       0  5455.6     .17       0
Bank Sta=4974,5062.1
XS Rating Curve= 0 ,0
Exp/Cntr=0.3,0.1

Type RM Length L Ch R = 1 ,9343    ,421,421,421
BEGIN DESCRIPTION:
TRIBUTARY 6 16.0
END DESCRIPTION:
XS GIS Cut Line= 3
      3776976.71     10256048.25      3777045.69      10256521.5
      3777326.18     10257097.15
#Sta/Elev= 30
  4355.3  327.41  4459.2   326.7  4489.5  324.91  4550.2  318.97  4619.1  315.67
  4670.8  315.45  4732.1  313.05  4792.7   314.7  4855.4  311.16  4866.4  311.28
  4872.4  312.75    4923  313.65  4977.7  312.27  4985.1  310.73  4990.6  306.52
  4997.7  305.68  5002.2  305.68  5007.6  307.56  5013.2  310.87  5022.2  312.51
  5052.7  314.71  5104.7  314.17  5111.2  312.59  5133.4  315.81  5170.9  315.92
  5200.2  317.86    5216   317.4  5255.5  319.17  5356.8  324.37  5473.9  332.56
#Mann= 5 ,-1 , 0
  4355.3     .17       0  4619.1     .15       0  4977.7     .09       0
  5022.2     .15       0  5104.7     .17       0
Bank Sta=4977.7,5022.2
XS Rating Curve= 0 ,0
Exp/Cntr=0.3,0.1

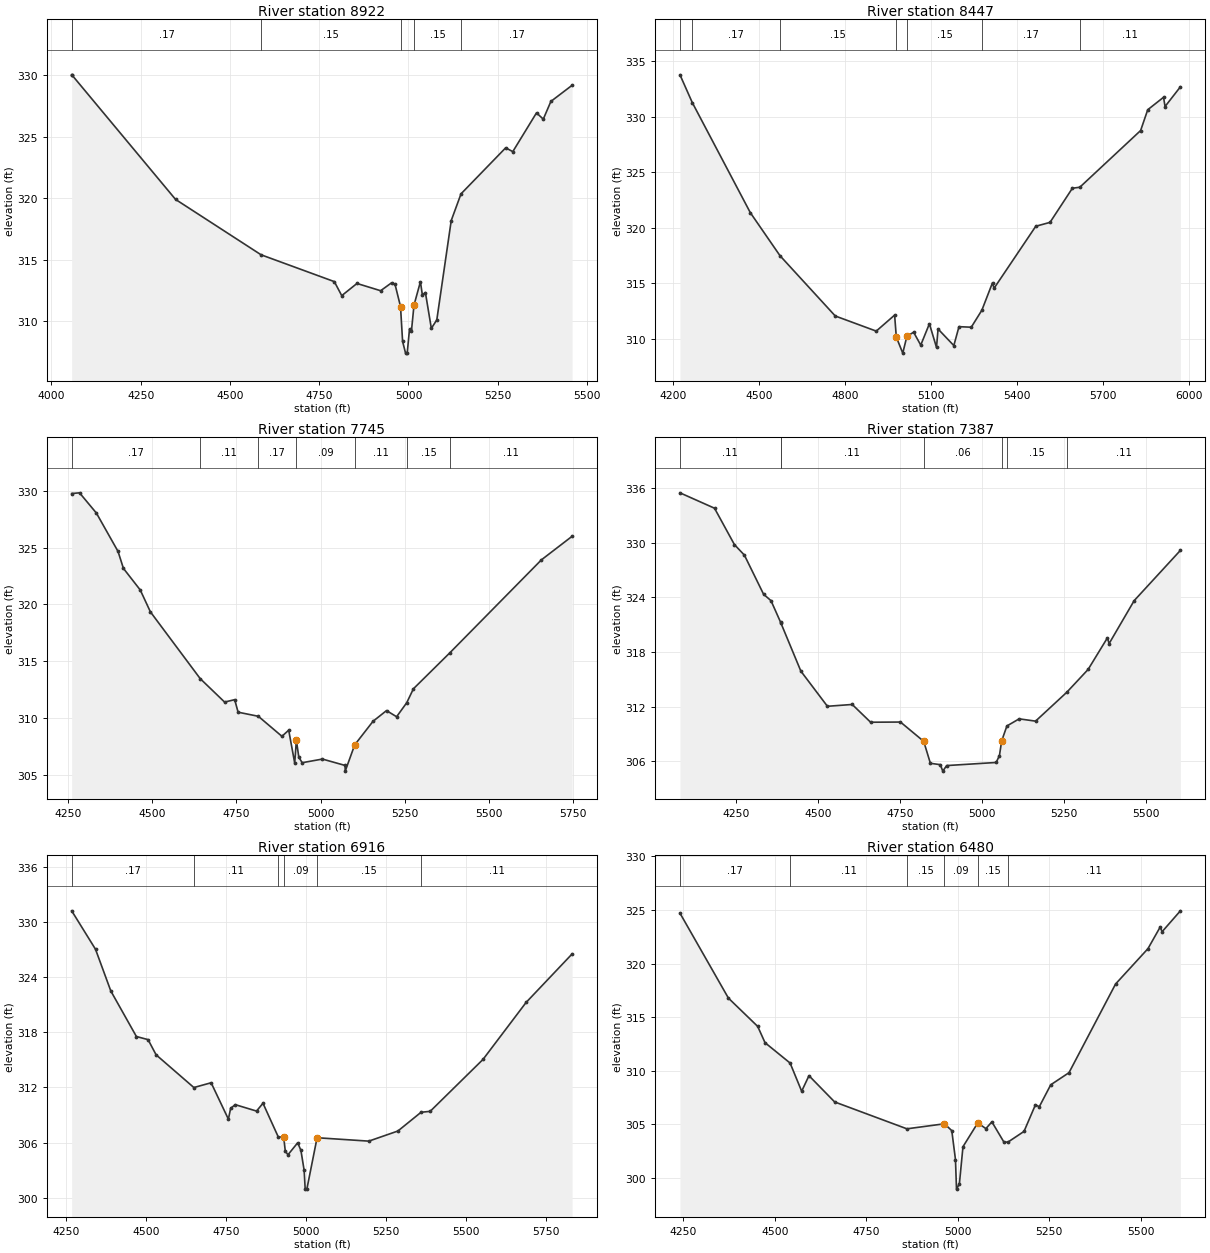
Type RM Length L Ch R = 1 ,8922    ,475,475,475
BEGIN DESCRIPTION:
TRIBUTARY 6 15.0
END DESCRIPTION:
XS GIS Cut Line= 3
      3776704.26     10255943.37      3776812.77     10256681.24
      3777038.21     10257296.86
#Sta/Elev= 30
  4056.9  330.03  4058.4  329.99  4347.7  319.91  4587.2  315.41  4792.4  313.23
  4813.2  312.09  4855.8  313.08  4922.1  312.49  4952.6  313.13  4962.3  313.02
  4977.8   311.2  4983.6  308.37  4991.9  307.42  4996.5  307.42    5003  309.37
  5008.3  309.19  5015.5  311.31  5033.5  313.22  5038.9  312.16  5047.5  312.34
  5064.1  309.43  5079.4  310.12  5119.8  318.19  5147.2  320.36  5272.3   324.1
  5292.2  323.79  5358.6  326.94  5377.6  326.43  5398.9  327.87  5458.3  329.18
#Mann= 6 ,-1 , 0
  4056.9     .11       0  4058.4     .17       0  4587.2     .15       0
  4977.8     .09       0  5015.5     .15       0  5147.2     .17       0
Bank Sta=4977.8,5015.5
XS Rating Curve= 0 ,0
Exp/Cntr=0.3,0.1

Type RM Length L Ch R = 1 ,8447    ,702,702,702
BEGIN DESCRIPTION:
TRIBUTARY 6 14.0
END DESCRIPTION:
XS GIS Cut Line= 3
      3776322.31     10255986.78      3776430.82     10256642.17
      3776812.76     10257653.44
#Sta/Elev= 30
  4224.2  333.75    4267  331.26  4469.6  321.35  4573.1  317.48  4765.8  312.06
  4908.7   310.7  4972.8  312.14  4978.7  310.16  5001.2  308.72  5015.6  310.23
  5039.1   310.6  5063.9  309.44  5094.1  311.36  5118.9  309.23  5124.3  310.89
  5179.3   309.4  5197.3   311.1  5240.1  311.05  5277.1  312.58  5314.2  315.05
  5319.5  314.55  5465.1  320.13  5514.8  320.48  5592.8  323.55  5618.7  323.64
  5830.8  328.74  5855.6  330.61  5910.7  331.73    5916   330.9  5969.5  332.67
#Mann= 7 ,-1 , 0
  4224.2     .11       0    4267     .17       0  4573.1     .15       0
  4978.7     .09       0  5015.6     .15       0  5277.1     .17       0
  5618.7     .11       0
Bank Sta=4978.7,5015.6
XS Rating Curve= 0 ,0
Exp/Cntr=0.3,0.1

Type RM Length L Ch R = 1 ,7745    ,358,358,358
BEGIN DESCRIPTION:
TRIBUTARY 6 13.0
END DESCRIPTION:
XS GIS Cut Line= 3
      3775975.09     10256177.76      3776027.18     10257093.56
      3776027.18     10257662.18
#Sta/Elev= 30
  4260.7  329.75    4284  329.81  4334.1  328.03  4398.3  324.66  4414.3  323.17
  4464.3  321.27  4494.4  319.35  4642.3  313.48  4714.7  311.42  4744.7  311.63
  4754.8  310.53  4814.9  310.17    4885  308.41  4905.1  308.95  4922.9  306.06
  4927.9  308.05  4935.1  306.58  4945.1  306.09  5005.2  306.41  5072.5  305.85
  5072.9  305.35  5101.1  307.66  5155.5  309.73  5195.5  310.67  5225.5  310.13
  5255.5  311.36  5275.5  312.59  5384.3  315.77  5655.5  323.92  5746.6  325.99
#Mann= 7 ,-1 , 0
  4260.7     .17       0  4642.3     .11       0  4814.9     .17       0
  4927.9     .09       0  5101.1     .11       0  5255.5     .15       0
  5384.3     .11       0
Bank Sta=4927.9,5101.1
XS Rating Curve= 0 ,0
Exp/Cntr=0.3,0.1

Type RM Length L Ch R = 1 ,7387    ,471,471,471
BEGIN DESCRIPTION:
TRIBUTARY 6 12.0
END DESCRIPTION:
XS GIS Cut Line= 3
      3775801.48     10256117.04      3775684.29     10256889.57
      3775653.91     10257631.79
#Sta/Elev= 30
  4080.1  335.47  4185.3  333.78    4246  329.78  4276.3  328.63  4334.8  324.33
  4357.3  323.63  4386.3  321.28  4387.5  321.17  4448.3  315.89  4529.2  312.03
  4604.7  312.23  4660.7  310.28  4751.7   310.3  4822.5  308.18  4842.8  305.77
    4873  305.62  4880.6  304.91  4892.4  305.52  5043.1  305.86  5053.1  306.61
    5060 308.238  5075.9  309.87  5113.2  310.65  5163.2   310.4  5258.3  313.57
  5323.3  316.08  5382.1  319.55  5387.1  318.91  5463.5  323.63  5604.3  329.15
#Mann= 7 ,-1 , 0
  4080.1     .11       0  4386.3     .17       0  4387.5     .11       0
  4822.5     .06       0    5060     .11       0  5075.9     .15       0
  5258.3     .11       0
Bank Sta=4822.5,5060
XS Rating Curve= 0 ,0
Exp/Cntr=0.3,0.1

Type RM Length L Ch R = 1 ,6916    ,436,436,436
BEGIN DESCRIPTION:
TRIBUTARY 6 11.0
END DESCRIPTION:
XS GIS Cut Line= 3
      3775050.62     10256221.17      3775250.27      10256763.7
      3775393.49     10257740.25
#Sta/Elev= 30
  4266.3   331.2  4340.8  327.02  4388.7  322.48  4468.7  317.53  4505.2  317.19
  4530.3  315.54  4648.4  311.98  4702.4   312.5  4756.4  308.54  4763.4  309.71
  4777.7  310.12  4844.4  309.42  4864.6  310.27  4912.5   306.6  4929.4  306.58
  4934.4  305.05  4942.8  304.67  4973.1  305.97  4983.2  305.15  4993.3  302.99
  4996.6  300.93  5001.8  300.93  5033.8  306.52  5195.5  306.15  5286.5  307.25
    5359  309.29  5387.5  309.39  5552.8  315.04  5687.4  321.23  5831.4  326.51
#Mann= 6 ,-1 , 0
  4266.3     .17       0  4648.4     .11       0  4912.5     .15       0
  4929.4     .09       0  5033.8     .15       0    5359     .11       0
Bank Sta=4929.4,5033.8
XS Rating Curve= 0 ,0
Exp/Cntr=0.3,0.1

Type RM Length L Ch R = 1 ,6480    ,499,499,499
BEGIN DESCRIPTION:
TRIBUTARY 6 10.0
END DESCRIPTION:
XS GIS Cut Line= 3
      3774972.49     10256368.77      3774946.26     10257127.11
      3775117.84     10257711.03
#Sta/Elev= 30
  4241.2   324.7  4373.6  316.77  4453.6  314.13  4473.6  312.61  4542.1  310.71
  4573.7  308.08  4593.7  309.53  4663.8  307.08  4861.3  304.57  4963.9  305.04
  4983.9   304.4    4994   301.7  4996.8  298.94  5004.7  299.44  5014.5   302.9
  5054.9  305.12  5077.1  304.59  5093.5  305.22  5126.9   303.3  5138.3  303.35
  5181.3  304.33  5212.6  306.82    5223  306.63  5254.3  308.68  5304.2  309.81
  5431.5  318.09    5520  321.39  5553.4  323.41  5558.6  322.97  5608.6  324.92
#Mann= 6 ,-1 , 0
  4241.2     .17       0  4542.1     .11       0  4861.3     .15       0
  4963.9     .09       0  5054.9     .15       0  5138.3     .11       0
Bank Sta=4963.9,5054.9
XS Rating Curve= 0 ,0
Exp/Cntr=0.3,0.1

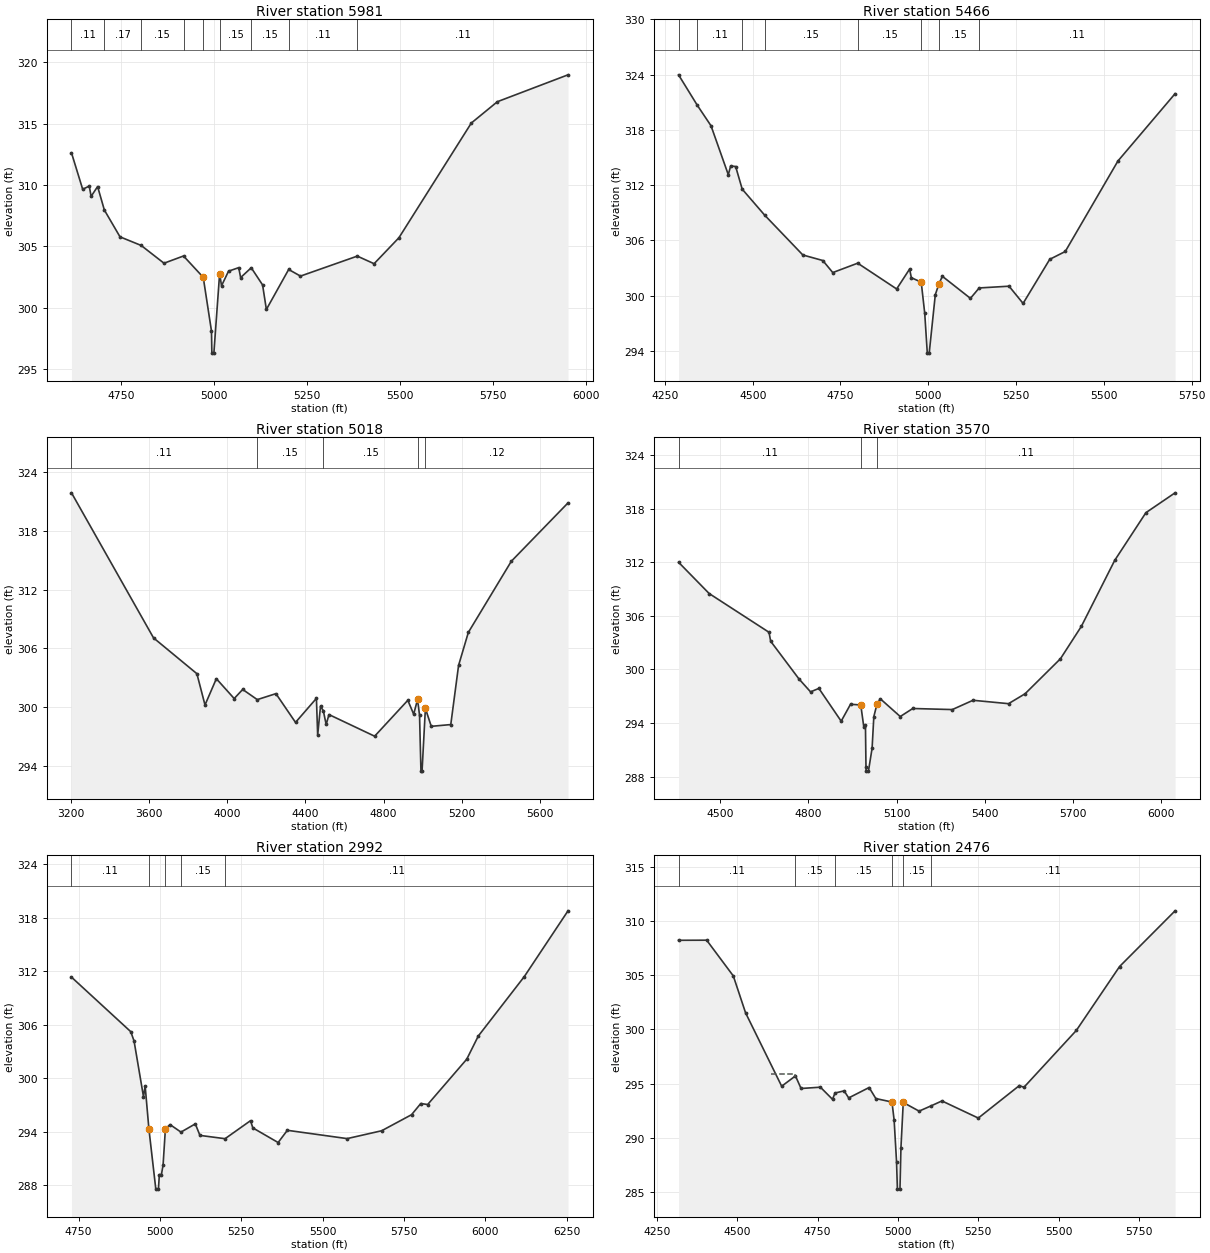
Type RM Length L Ch R = 1 ,5981    ,515,515,515
BEGIN DESCRIPTION:
TRIBUTARY 6 9.0
END DESCRIPTION:
XS GIS Cut Line= 3
      3774467.85      10256661.1        3774506.      10257043.3
      3774321.74      10257977.5
#Sta/Elev= 30
  4615.9  312.62    4646  309.65  4663.7  309.91  4668.7  309.07  4686.2  309.87
  4704.3  307.96  4746.5  305.77  4803.4  305.07  4864.9  303.62  4917.4  304.21
  4970.5  302.47  4992.7  298.08  4993.7  296.29  4999.1  296.29  5014.6  302.78
  5019.7  301.78  5038.5  302.97    5066  303.26  5071.1  302.45  5099.7  303.25
  5130.2  301.85  5140.4  299.85  5200.4  303.11  5232.2  302.57  5385.1   304.2
  5430.3  303.58  5497.2   305.7    5692  315.05  5762.2  316.79  5952.2  318.98
#Mann= 9 ,-1 , 0
  4615.9     .11       0  4704.3     .17       0  4803.4     .15       0
  4917.4     .15       0  4970.5     .09       0  5014.6     .15       0
  5099.7     .15       0  5200.4     .11       0  5385.1     .11       0
Bank Sta=4970.5,5014.6
XS Rating Curve= 0 ,0
Exp/Cntr=0.3,0.1

Type RM Length L Ch R = 1 ,5466    ,448,448,448
BEGIN DESCRIPTION:
TRIBUTARY 6 8.0
END DESCRIPTION:
XS GIS Cut Line= 3
      3774467.88     10256511.04      3774100.09     10256919.95
       3774121.8      10257783.7
#Sta/Elev= 30
  4288.8  323.98  4342.4  320.66  4381.2  318.45  4430.5  313.13  4437.2  314.08
  4451.4  314.02  4470.1  311.56    4534  308.74  4642.8  304.41  4699.6  303.81
    4728   302.5    4799  303.52  4909.9  300.72  4946.8  302.88  4951.8  301.94
  4979.9  301.46  4989.9  298.07  4997.2  293.75  5002.6  293.75    5020   300.1
    5030  301.23    5040   302.1    5120   299.7    5145  300.83    5230  301.02
    5270  299.15  5345.9  303.94  5390.1  304.79  5540.1  314.62  5702.8  321.93
#Mann= 8 ,-1 , 0
  4288.8     .17       0  4342.4     .11       0  4470.1     .17       0
    4534     .15       0    4799     .15       0  4979.9     .09       0
    5030     .15       0    5145     .11       0
#XS Ineff= 1 ,-1
    4695  4946.8  302.88
Permanent Ineff=
       F
Bank Sta=4979.9,5030
XS Rating Curve= 0 ,0
Exp/Cntr=0.3,0.1

Type RM Length L Ch R = 1 ,5018    ,1448,1448,1448
BEGIN DESCRIPTION:
TRIBUTARY 6 7.0
END DESCRIPTION:
XS GIS Cut Line= 3
      3772517.88     10256011.09      3773722.49     10256937.31
      3773744.19     10257961.65
#Sta/Elev= 30
  3201.1  321.89  3621.5  307.06  3843.6   303.4  3885.2   300.2  3943.3  302.89
  4034.7  300.86  4078.3  301.79    4153  300.75  4248.6  301.36    4349  298.42
  4456.1  300.88  4462.5  297.12    4477  300.07  4491.5  299.61    4506  298.21
  4520.5  299.22  4754.4  297.01  4924.4  300.68  4954.4  299.26  4974.4  300.77
  4984.5  299.15  4991.7  293.44  4997.3  293.44  5014.5  299.85  5044.5  298.02
  5144.5   298.2  5184.5  304.25  5234.5  307.62  5454.6  314.89  5745.2  320.86
#Mann= 5 ,-1 , 0
  3201.1     .11       0    4153     .15       0  4491.5     .15       0
  4974.4     .07       0  5014.5     .12       0
#XS Ineff= 1 ,-1
    3810  3943.3  302.89
Permanent Ineff=
       F
Bank Sta=4974.4,5014.5
XS Rating Curve= 0 ,0
Exp/Cntr=0.3,0.1

Type RM Length L Ch R = 1 ,3570    ,578,578,578
BEGIN DESCRIPTION:
TRIBUTARY 6 6.0
END DESCRIPTION:
XS GIS Cut Line= 3
      3772537.57     10256512.79      3772850.09     10257162.14
      3773567.88      10257811.1
#Sta/Elev= 30
  4358.8     312  4462.8   308.5  4666.4  304.16    4672  303.16    4768  298.95
  4807.7  297.49  4835.9  297.88  4911.8  294.21  4943.5   296.1  4978.4  296.03
  4988.7  293.57  4994.3  293.79  4996.1  289.12  4996.6  288.62  5004.5  288.62
  5016.9  291.18  5022.8  294.72  5033.9  296.17  5045.1  296.71  5112.6  294.73
  5155.2  295.63  5289.7  295.51    5360  296.55  5480.8  296.17  5537.1  297.28
  5657.4   301.2  5728.4  304.82  5841.9  312.21    5948  317.55  6047.1  319.77
#Mann= 3 , 0 , 0
  4358.8     .11       0  4978.4     .07       0  5033.9     .11       0
Bank Sta=4978.4,5033.9
XS Rating Curve= 0 ,0
Exp/Cntr=0.3,0.1

Type RM Length L Ch R = 1 ,2992    ,516,516,516
BEGIN DESCRIPTION:
TRIBUTARY 6 5.0
END DESCRIPTION:
XS GIS Cut Line= 3
      3772367.85     10256961.08      3772325.55     10257229.77
      3773217.89     10258111.11
#Sta/Elev= 30
    4728  311.32  4910.2  305.21  4920.3  304.17  4949.3  297.93  4954.4  299.12
    4966 294.294  4987.2  287.57  4995.2  287.57  4998.1   289.2  5004.5   289.2
  5009.6  290.32  5016.7  294.34  5030.9   294.8  5064.5  293.96  5108.6  294.88
  5122.8  293.59  5200.1  293.22  5278.3  295.24  5285.4  294.43  5363.2  292.79
  5391.5  294.16  5575.3  293.23  5681.4  294.11  5773.3  295.91  5801.6  297.16
  5822.8  297.05    5943  302.13  5978.4  304.72  6119.8  311.38  6254.2  318.75
#Mann= 5 ,-1 , 0
    4728     .11       0    4966     .06       0  5016.7     .11       0
  5064.5     .15       0  5200.1     .11       0
Bank Sta=4966,5016.7
XS Rating Curve= 0 ,0
Exp/Cntr=0.3,0.1

Type RM Length L Ch R = 1 ,2476    ,316,316,316
BEGIN DESCRIPTION:
TRIBUTARY 6 4.0
END DESCRIPTION:
XS GIS Cut Line= 3
      3772270.23     10256971.21      3772230.69     10257451.38
      3773025.68     10258157.34
#Sta/Elev= 30
  4317.5  308.23    4405  308.24  4487.9  304.94  4526.1  301.53  4638.4  294.76
  4681.3  295.71  4698.7  294.55  4758.9  294.67  4796.6  293.55  4804.3  294.13
  4832.7  294.33  4846.9  293.68  4910.5  294.64  4931.4  293.62  4981.6   293.3
  4988.3  291.64  4995.8  287.81  4998.5  285.26  5006.5  285.26  5009.5  289.07
  5016.7  293.26    5066  292.46  5104.3  292.96  5137.1   293.4  5250.2  291.82
    5378  294.82  5392.2  294.66  5555.3  299.91  5689.9  305.81  5862.5  310.95
#Mann= 6 ,-1 , 0
  4317.5     .11       0  4681.3     .15       0  4804.3     .15       0
  4981.6     .09       0  5016.7     .15       0  5104.3     .11       0
#XS Ineff= 1 ,-1
    4605  4678.6  295.86
Permanent Ineff=
       F
Bank Sta=4981.6,5016.7
XS Rating Curve= 0 ,0
Exp/Cntr=0.3,0.1

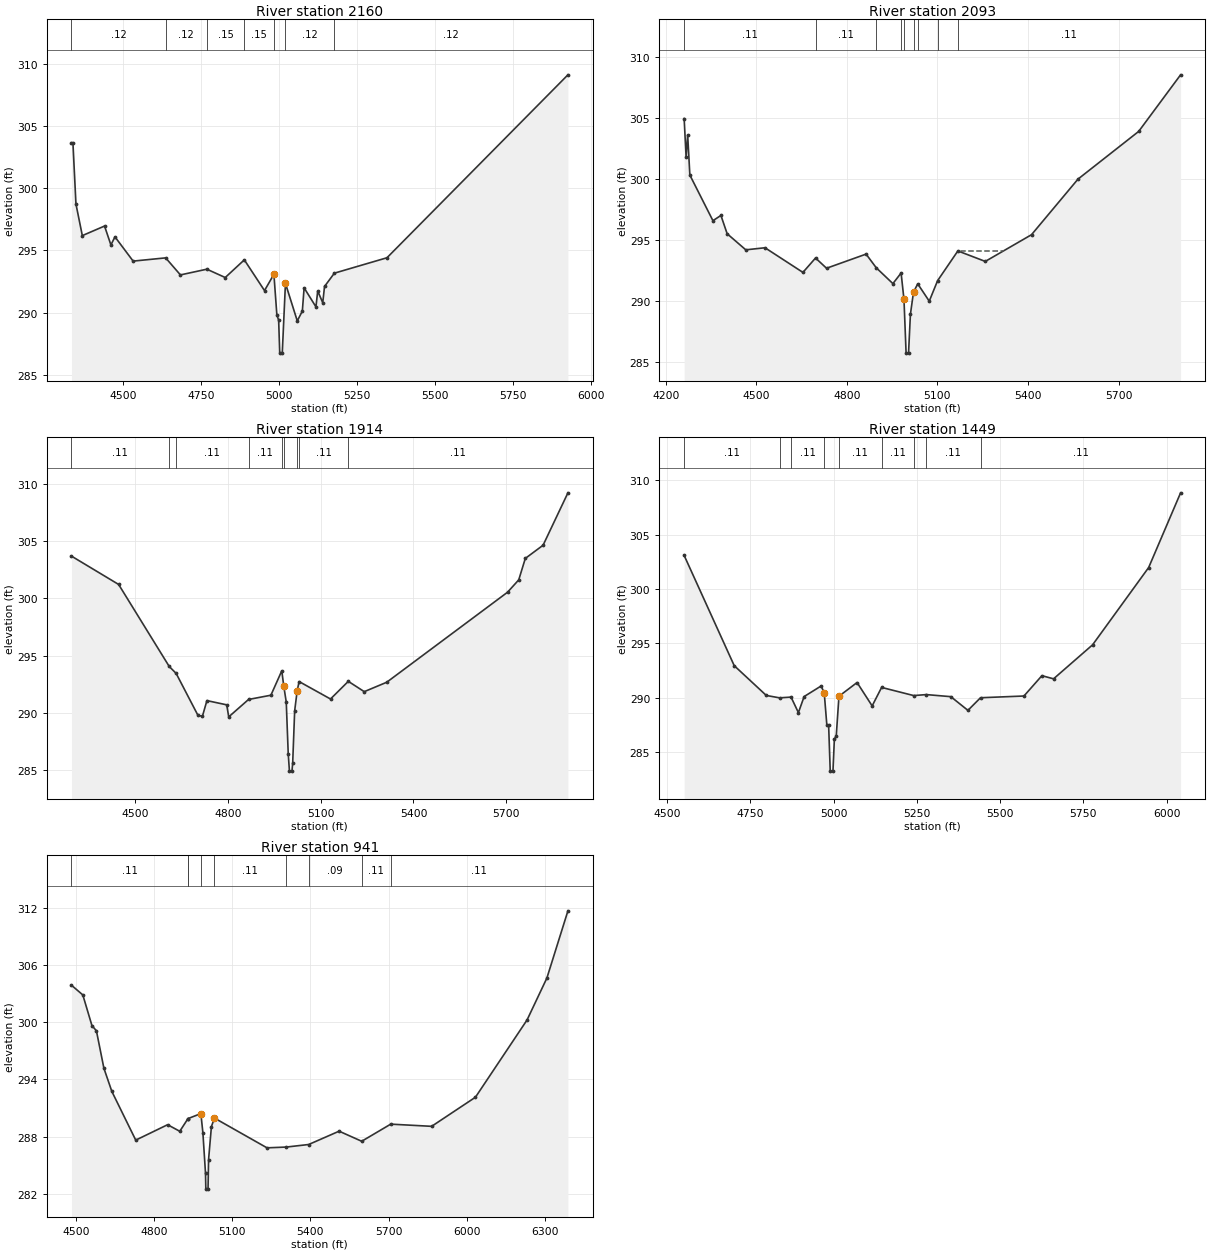
Type RM Length L Ch R = 1 ,2160    ,67,67,67
BEGIN DESCRIPTION:
Mapping XS e7e72c3b
END DESCRIPTION:
XS GIS Cut Line= 4
      3772117.45     10257116.99      3772232.04     10257724.64
      3772395.23     10258023.25      3772714.68      10258568.4
#Sta/Elev= 30
  4334.3  303.66  4338.9  303.66  4348.6  298.73    4369  296.19  4440.2  296.96
  4460.6  295.44  4473.6  296.09  4531.8  294.14    4636   294.4  4683.3  293.03
    4768  293.49  4826.9  292.82    4888  294.24  4952.7  291.77  4982.8  293.08
  4992.3  289.81    4998  289.39  5001.5  286.74  5009.6  286.74  5019.8  292.35
  5057.7  289.33  5073.9  290.12  5079.6  291.99  5117.5  290.46  5123.2  291.74
  5139.3  290.79    5145   292.1  5176.5  293.17  5345.1  294.41  5924.8  309.12
#Mann= 7 ,-1 , 0
  4334.3     .12       0    4636     .12       0    4768     .15       0
    4888     .15       0  4982.8     .07       0  5019.8     .12       0
  5176.5     .12       0
#XS Ineff= 1 ,-1
    4480    4888  294.24
Permanent Ineff=
       F
Bank Sta=4982.8,5019.8
XS Rating Curve= 0 ,0
Exp/Cntr=0.3,0.1

Type RM Length L Ch R = 1 ,2093    ,179,179,179
BEGIN DESCRIPTION:
Mapping XS fedba6c8
END DESCRIPTION:
XS GIS Cut Line= 3
      3772030.64     10257092.65       3772211.2     10257839.22
      3772627.86     10258610.03
#Sta/Elev= 30
  4261.2  304.96  4267.7  301.81  4272.8  303.63  4280.1  300.33  4356.5  296.59
    4383  297.02  4403.6  295.52  4465.3   294.2    4529  294.37  4654.6  292.35
  4696.4  293.53  4732.8  292.69  4863.8  293.85  4897.4  292.73  4952.6  291.43
  4979.8   292.3  4989.3  290.13  4996.3  285.73  5004.4  285.73  5010.6  288.91
  5020.9  290.74  5034.9  291.41    5073  289.99  5100.6  291.67  5167.8  294.11
  5258.6  293.25  5411.7  295.44  5565.7     300  5766.7  303.91  5905.5  308.55
#Mann= 9 ,-1 , 0
  4261.2     .11       0  4696.4     .11       0  4897.4     .11       0
  4979.8     .11       0  4989.3     .06       0  5020.9     .11       0
  5034.9     .11       0  5100.6     .11       0  5167.8     .11       0
#XS Ineff= 2 ,-1
    4440  4863.8  293.85  5176.7    5320  294.11
Permanent Ineff=
       F       F
Bank Sta=4989.3,5020.9
XS Rating Curve= 0 ,0
Exp/Cntr=0.3,0.1

Type RM Length L Ch R = 1 ,1914    ,465,465,465
BEGIN DESCRIPTION:
TRIBUTARY 6 3.0
END DESCRIPTION:
XS GIS Cut Line= 3
      3771512.88     10257481.92      3772117.02     10257961.07
      3772567.56     10258661.62
#Sta/Elev= 30
  4295.1  303.69  4447.4  301.22  4610.8  294.07  4633.3  293.46  4703.8   289.8
  4718.2  289.73  4732.7  291.09  4796.7  290.72  4803.1  289.67  4867.2  291.19
  4939.4  291.56  4974.6  293.69    4981  292.35    4989  290.97  4995.4  286.45
  4999.3  284.94  5007.5  284.94  5009.8  285.65  5016.2   290.2  5024.3  291.95
  5030.6  292.75    5132  291.23  5189.5  292.77    5241  291.87  5313.6  292.69
  5703.9  300.54  5740.2  301.62  5761.4  303.49  5818.8  304.64  5899.1  309.21
#Mann= 9 ,-1 , 0
  4295.1     .11       0  4610.8     .11       0  4633.3     .11       0
  4867.2     .11       0  4974.6     .11       0    4981     .06       0
  5024.3     .11       0  5030.6     .11       0  5189.5     .11       0
#XS Ineff= 1 ,-1
    4500  4974.6  293.69
Permanent Ineff=
       T
Bank Sta=4981,5024.3
XS Rating Curve= 0 ,0
Exp/Cntr=0.3,0.1

Type RM Length L Ch R = 1 ,1449    ,508,508,508
BEGIN DESCRIPTION:
TRIBUTARY 6 2.0
END DESCRIPTION:
XS GIS Cut Line= 3
      3771517.87      10257711.1      3771817.54     10258341.28
      3772511.79     10258725.35
#Sta/Elev= 30
  4550.8  303.08  4701.2  292.94  4797.6   290.2  4837.5  289.98  4871.9  290.05
    4894  288.62  4911.2   290.1  4962.1  291.07  4971.5  290.46  4979.3  287.52
  4984.8  287.45  4989.6  283.24  4997.8  283.24    5002  286.19  5007.6  286.45
  5015.8  290.13  5070.2  291.39  5115.5  289.24  5143.9  290.94  5240.3  290.19
  5278.3  290.28  5351.8  290.09  5403.2  288.83    5441  289.99  5571.5  290.15
  5625.4  292.02  5660.4  291.73  5777.7  294.86  5946.1  301.97    6042  308.84
#Mann= 9 ,-1 , 0
  4550.8     .11       0  4837.5     .11       0  4871.9     .11       0
  4971.5     .06       0  5015.8     .11       0  5143.9     .11       0
  5240.3     .11       0  5278.3     .11       0    5441     .11       0
Bank Sta=4971.5,5015.8
XS Rating Curve= 0 ,0
Exp/Cntr=0.3,0.1

Type RM Length L Ch R = 1 ,941     ,0,0,0
BEGIN DESCRIPTION:
TRIBUTARY 6 1.0
END DESCRIPTION:
XS GIS Cut Line= 3
      3771104.01     10257789.22      3771406.08     10258476.69
      3772524.41     10258765.38
#Sta/Elev= 30
  4482.8   303.9  4526.3  302.88  4561.3  299.66  4578.5  299.11  4607.3  295.17
  4637.7  292.74  4729.5  287.62  4851.8  289.24  4898.5  288.55  4929.6  289.86
  4929.9  289.88  4979.5  290.41  4987.3  288.39  4997.3  284.14  4998.6  282.47
    5007  282.47  5009.1  285.58    5020  289.04  5031.6  289.94  5233.4  286.81
    5307  286.89  5393.4  287.16  5510.3  288.56    5597   287.5  5708.4   289.3
  5865.5  289.07  6033.7  292.13  6231.8  300.25    6308  304.66  6388.7  311.72
#Mann= 9 ,-1 , 0
  4482.8     .11       0  4929.6     .15       0  4929.9     .11       0
  4979.5     .06       0  5031.6     .11       0    5307     .09       0
  5393.4     .09       0    5597     .11       0  5708.4     .11       0
Bank Sta=4979.5,5031.6
XS Rating Curve= 0 ,0
Exp/Cntr=0.3,0.1

Chan Stop Cuts=-1
Use User Specified Reach Order=0
Composite Channel Slope=5