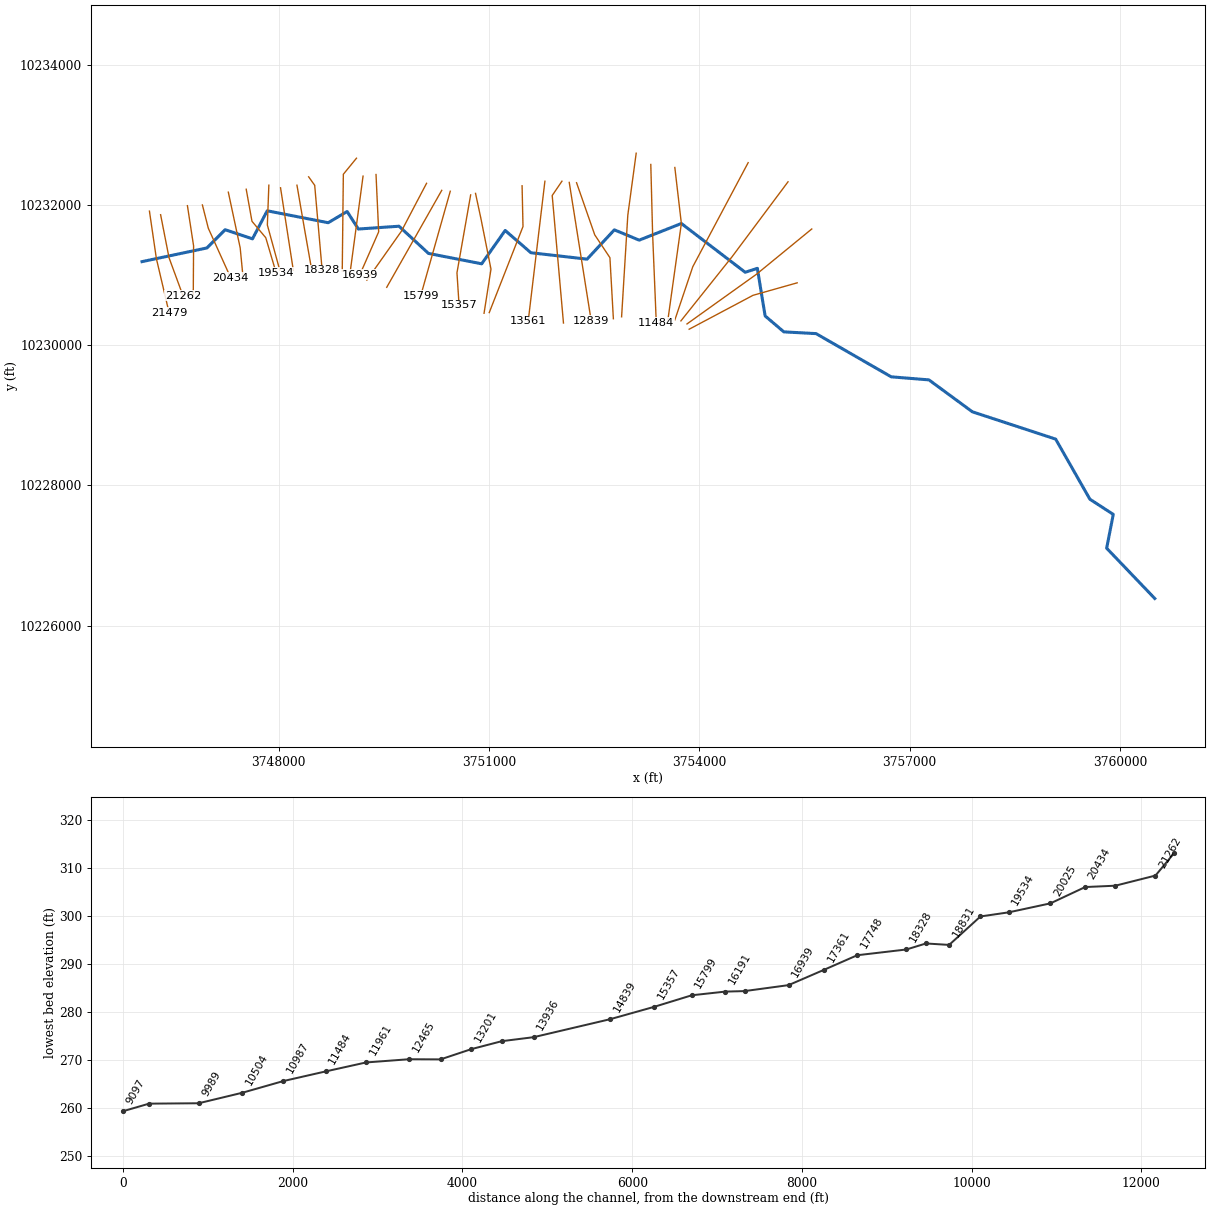
--- WELCH BRANCH.prj (project) ---

Proj Title=WELCH BRANCH Base Level Engineering
Current Plan=p01
Default Exp/Contr=0.3,0.1
English Units
Geom File=g01
Flow File=f01
Plan File=p01
Y Axis Title=Elevation
X Axis Title(PF)=Main Channel Distance
X Axis Title(XS)=Station
BEGIN DESCRIPTION:
WELCH BRANCH
END DESCRIPTION:
DSS Export Rating Curves= 0
DSS Export Rating Curve Sorted= 0
DSS Export Volume Flow Curves= 0
DXF OffsetX= 0
DXF OffsetY= 0
DXF ScaleX= 1
DXF ScaleY= 10

--- WELCH BRANCH.p01 (plan) ---

Plan Title=Multiple Run
Program Version=4.10
Short Identifier=Multiple
Geom File=g01
Flow File=f01
Subcritical Flow
K Sum by GR= 0
Std Step Tol= 0.01
Critical Tol= 0.01
Num of Std Step Trials= 20
Max Error Tol= 0.3
Flow Tol Ratio= 0.001
Split Flow NTrial= 30
Split Flow Tol= 0.02
Split Flow Ratio= 0.02
Log Output Level= 0
Friction Slope Method= 1
Unsteady Friction Slope Method= 2
Unsteady Bridges Friction Slope Method= 1
Parabolic Critical Depth
Global Vel Dist= 1 , 1 , 1
Global Log Level= 0
CheckData=True
Encroach Param=-1 ,0,0, 0
BEGIN DESCRIPTION:
Multiple Run
END DESCRIPTION:
Computation Interval=1HOUR
Output Interval=1HOUR
Run HTab= 0
Run UNet= 0
Run PostProcess= 0
Run WQNet= 0
UNET Theta= 1
UNET Theta Warmup= 1
UNET ZTol= 0.02
UNET ZSATol= 0.05
UNET MxIter= 20
UNET MaxInSteps= 0
UNET DtIC= 0
UNET DtMin= 0
UNET MaxCRTS= 20
UNET WFStab= 2
UNET SFStab= 1
UNET WFX= 1
UNET SFX= 1
UNET DSS MLevel= 4
UNET DZMax Abort= 100
UNET Convert EG Bridges= 0
UNET Use Existing IB Tables=-1
UNET Froude Reduction=False
UNET Froude Limit= 1
UNET Froude Power= 10
UNET Time Slicing=0,0, 5
UNET Junction Losses=0
Instantaneous Interval=1HOUR
Write IC File= 0
Write IC File at Sim End=0
Echo Input=False
Echo Parameters=False
Echo Output=False
Write Detailed= 0
WQ AD Non Conservative
WQ ULTIMATE=-1
WQ Max Comp Step=1HOUR
WQ Output Interval=15MIN
WQ Output Selected Increments= 0
WQ Output face flow=0
WQ Output face velocity=0
WQ Output face area=0
WQ Output face dispersion=0
WQ Output cell volume=0
WQ Output cell surface area=0
WQ Output cell continuity=0
WQ Output cumulative cell continuity=0
WQ Output face conc=0
WQ Output face dconc_dx=0
WQ Output face courant=0
WQ Output face peclet=0
WQ Output face adv mass=0
WQ Output face disp mass=0
WQ Output cell mass=0
WQ Output cell source sink temp=0
WQ Output cell source sink nsm=0
WQ Output MaxMinRange=-1
WQ Daily Max Min Mean=-1
WQ Daily Range=0
WQ Daily Time=0
WQ Create Restart=0
WQ Fixed Restart=0
WQ System Summary=0
WQ Use Fixed Temperature=0
Sorting and Armoring Iterations= 10
XS Update Threshold= 0.02
Hydraulics Update Threshold= 0.02
Energy Slope Method= 1
Volume Change Method= 0
XS Weighting Method= 0
Number of US Weighted Cross Sections= 1
Number of DS Weighted Cross Sections= 1
Upstream XS Weight=0.25
Main XS Weight=0.5
Downstream XS Weight=0.25
Number of DS XS's Weighted with US Boundary= 1
Upstream Boundary Weight= 1
Weight of XSs Associated with US Boundary= 0
Number of US XS's Weighted with DS Boundary= 1
Downstream Boundary Weight= 0.5
Weight of XSs Associated with DS Boundary= 0.5
Sediment Output Level= 4
Mass or Volume Output= 0
Output Increment Type= 1
Profile and TS Output Increment= 10
XS Output Flag= 0
XS Output Increment= 10
Disregard all LS=0
Disregard all Conn=0
Disregard all Breaches=0
Disregard all Pumps=0

--- WELCH BRANCH.f01 (steady flow) ---

Flow Title=Multiple
Program Version=4.10
Number of Profiles= 7
Profile Names=10-year,25-year,50-year,1pct_min,100-year,1pct_plu,500-year
River Rch & RM=WELCH BRANCH,Reach-1         ,21479
     943    1299    1777     797    2408    7272    4573
River Rch & RM=WELCH BRANCH,Reach-1         ,11484
    1131    1569    2153     970    2928    8842    5602
River Rch & RM=WELCH BRANCH,Reach-1         ,2984
    1166    1618    2221    1000    3021    9123    5783
Boundary for River Rch & Prof#=WELCH BRANCH,Reach-1         , 1
Up Type= 0
Dn Type= 3
Dn Slope=0.0045
Boundary for River Rch & Prof#=WELCH BRANCH,Reach-1         , 2
Up Type= 0
Dn Type= 3
Dn Slope=0.0045
Boundary for River Rch & Prof#=WELCH BRANCH,Reach-1         , 3
Up Type= 0
Dn Type= 3
Dn Slope=0.0045
Boundary for River Rch & Prof#=WELCH BRANCH,Reach-1         , 4
Up Type= 0
Dn Type= 3
Dn Slope=0.0045
Boundary for River Rch & Prof#=WELCH BRANCH,Reach-1         , 5
Up Type= 0
Dn Type= 3
Dn Slope=0.0045
Boundary for River Rch & Prof#=WELCH BRANCH,Reach-1         , 6
Up Type= 0
Dn Type= 3
Dn Slope=0.0045
Boundary for River Rch & Prof#=WELCH BRANCH,Reach-1         , 7
Up Type= 0
Dn Type= 3
Dn Slope=0.0045
DSS Import GetInterval= 0
DSS Import GetPeak= 0
DSS Import FillOption= 0

--- WELCH BRANCH.g01 (geometry) ---

Geom Title=Existing Conditions
Program Version=4.10

River Reach=WELCH BRANCH    ,Reach-1
Reach XY= 30
      3746053.23     10231191.84      3746978.23     10231386.84
      3747238.23     10231646.84      3747628.23     10231516.84
      3747838.23     10231916.84      3748708.23     10231746.84
      3748978.23     10231906.84      3749138.23     10231656.84
      3749718.23     10231696.84      3750138.77      10231308.9
      3750897.76     10231160.87      3751232.52     10231636.09
      3751599.72     10231318.49      3752400.23     10231227.14
      3752789.94     10231645.01      3753144.19     10231498.15
      3753745.64     10231735.65       3754656.5     10231039.86
      3754829.66      10231095.9      3754940.21     10230417.71
      3755206.73     10230190.02      3755667.42     10230164.89
      3756739.09     10229548.58      3757276.65     10229505.25
      3757896.66     10229049.77      3759084.43     10228660.39
      3759572.82     10227802.87      3759906.23     10227586.71
      3759811.78     10227104.45      3760498.23     10226386.84

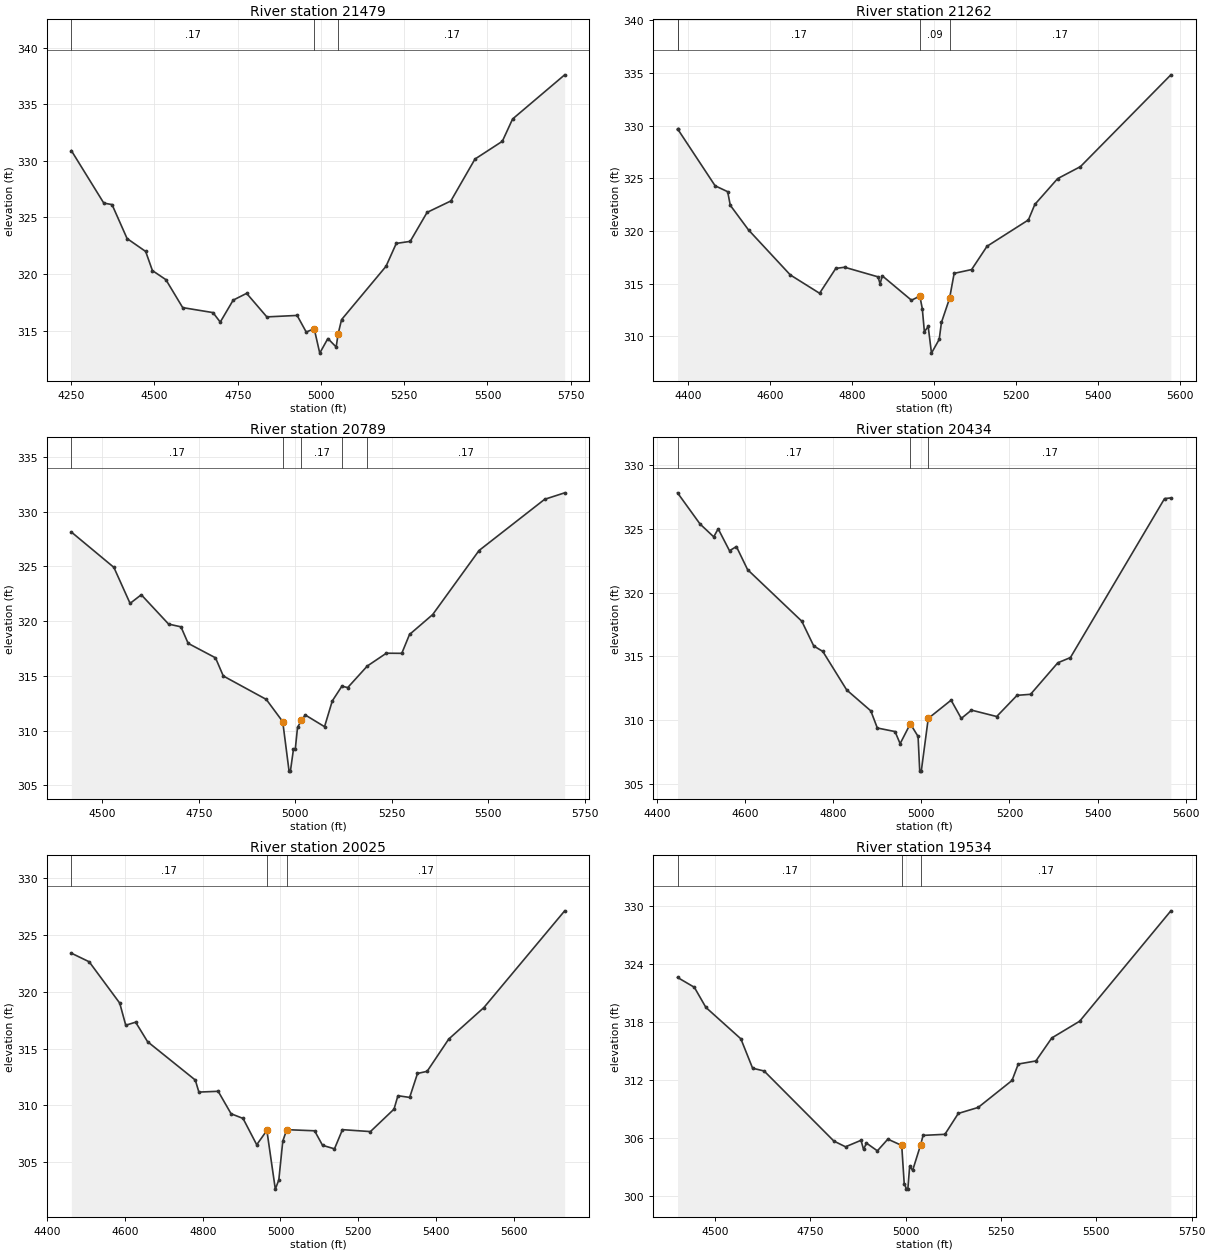
Type RM Length L Ch R = 1 ,21479   ,217,217,217
BEGIN DESCRIPTION:
WELCH BRANCH 42.0
END DESCRIPTION:
XS GIS Cut Line= 3
      3746158.67     10231911.97      3746257.63     10231234.87
      3746439.93     10230458.79
#Sta/Elev= 30
  4250.3   330.9  4347.8  326.26  4372.5  326.13  4417.7  323.13  4473.5  321.99
  4493.8   320.3  4534.2   319.5  4584.7  317.03  4675.7  316.59  4697.5  315.75
  4736.3  317.69  4776.7  318.29  4837.4  316.21  4928.3  316.34  4955.7  314.87
  4979.6  315.17  4996.3  313.01  5020.7   314.3  5045.6  313.55  5051.5  314.71
  5061.8  315.97  5195.3  320.68  5226.1   322.7  5267.9  322.88  5318.6  325.44
    5390  326.45  5462.4  330.15  5544.6  331.72  5575.4  333.69  5731.8  337.59
#Mann= 3 , 0 , 0
  4250.3     .17       0  4979.6     .09       0  5051.5     .17       0
#XS Ineff= 1 ,-1
    4540  4776.7  318.29
Permanent Ineff=
       F
Bank Sta=4979.6,5051.5
XS Rating Curve= 0 ,0
Exp/Cntr=0.3,0.1

Type RM Length L Ch R = 1 ,21262   ,473,473,473
BEGIN DESCRIPTION:
WELCH BRANCH 41.0
END DESCRIPTION:
XS GIS Cut Line= 3
      3746317.85     10231861.06      3746438.23     10231246.84
      3746637.38     10230704.87
#Sta/Elev= 30
  4374.1  329.63  4375.1  329.63  4465.8  324.28  4496.4  323.72  4502.8  322.43
  4547.3  320.09  4649.2  315.82  4720.6  314.08  4760.1  316.44  4781.7  316.55
  4863.1  315.64  4868.2  314.96  4873.4  315.74  4944.7  313.42  4965.1  313.81
  4971.1  312.63  4976.2  310.43  4985.5  310.93  4993.5   308.4  5012.4  309.71
  5017.8  311.31  5037.6  313.59  5048.8  315.97  5091.4  316.33    5129  318.54
  5229.9  321.04  5245.6  322.51  5301.2  324.96  5356.9   326.1  5577.4  334.81
#Mann= 4 ,-1 , 0
  4374.1     .11       0  4375.1     .17       0  4965.1     .09       0
  5037.6     .17       0
Bank Sta=4965.1,5037.6
XS Rating Curve= 0 ,0
Exp/Cntr=0.3,0.1

Type RM Length L Ch R = 1 ,20789   ,355,355,355
BEGIN DESCRIPTION:
WELCH BRANCH 40.0
END DESCRIPTION:
XS GIS Cut Line= 3
      3746700.34     10231990.05      3746788.23     10231416.84
      3746783.67     10230719.26
#Sta/Elev= 30
  4420.1  328.13  4530.3   324.9  4572.2  321.61  4601.2   322.4    4672  319.72
    4704  319.47  4722.6  317.96  4793.4  316.64  4813.6  314.98  4924.9  312.84
  4967.5  310.81  4983.9  306.29  4987.4  306.29  4995.3  308.29    5000  308.29
  5005.8  310.28  5015.8  310.92  5025.8  311.42  5075.8  310.35  5095.8   312.7
  5120.7  314.05  5135.8  313.92  5186.5  315.89  5235.8  317.06  5275.8  317.05
  5295.8  318.77  5355.8  320.59  5475.8  326.44  5645.8  331.12  5697.6  331.71
#Mann= 5 ,-1 , 0
  4420.1     .17       0  4967.5     .09       0  5015.8     .17       0
  5120.7     .11       0  5186.5     .17       0
Bank Sta=4967.5,5015.8
XS Rating Curve= 0 ,0
Exp/Cntr=0.3,0.1

Type RM Length L Ch R = 1 ,20434   ,409,409,409
BEGIN DESCRIPTION:
WELCH BRANCH 39.0
END DESCRIPTION:
XS GIS Cut Line= 3
      3746913.88     10232000.48      3746998.19     10231668.12
      3747317.84      10230961.1
#Sta/Elev= 30
  4447.2  327.82  4498.2  325.38  4529.3  324.37  4539.4     325  4565.1  323.28
  4580.7  323.61  4606.1   321.8    4729  317.76  4756.1  315.82  4776.7  315.39
  4830.9  312.37  4885.6  310.73  4900.3  309.39  4940.5  309.11    4952  308.16
  4975.1  309.72  4992.7  308.73  4996.5  306.01    5000  306.01  5015.8  310.14
  5067.6  311.57  5090.7  310.14  5113.8  310.79    5171  310.29  5217.2  311.95
  5247.8  312.03  5309.6   314.5  5338.2  314.91  5551.7  327.37    5566  327.42
#Mann= 3 , 0 , 0
  4447.2     .17       0  4975.1     .09       0  5015.8     .17       0
Bank Sta=4975.1,5015.8
XS Rating Curve= 0 ,0
Exp/Cntr=0.3,0.1

Type RM Length L Ch R = 1 ,20025   ,491,491,491
BEGIN DESCRIPTION:
WELCH BRANCH 38.0
END DESCRIPTION:
XS GIS Cut Line= 3
      3747283.68     10232182.75      3747453.04     10231387.57
      3747497.05     10230934.42
#Sta/Elev= 30
  4462.3  323.41  4508.2  322.65  4586.7  319.01  4602.2  317.06  4627.6  317.33
  4658.3  315.61    4781  312.23  4790.2  311.17  4839.8  311.24    4873  309.26
  4903.7  308.85  4938.9  306.53    4965  307.79  4986.7  302.62  4995.7  303.43
  5005.9  306.85  5016.1  307.86  5087.7  307.76  5108.1  306.48  5138.8  306.17
  5159.3  307.86  5231.2  307.69  5291.9  309.67  5301.9  310.85  5332.1   310.7
  5352.2  312.81    5377     313  5432.5  315.84    5523  318.62  5730.6  327.14
#Mann= 3 , 0 , 0
  4462.3     .17       0    4965     .09       0  5016.1     .17       0
Bank Sta=4965,5016.1
XS Rating Curve= 0 ,0
Exp/Cntr=0.3,0.1

Type RM Length L Ch R = 1 ,19534   ,334,334,334
BEGIN DESCRIPTION:
WELCH BRANCH 37.0
END DESCRIPTION:
XS GIS Cut Line= 4
      3747538.87     10232224.49      3747621.08     10231767.26
      3747817.94     10231532.81      3747965.97     10231031.72
#Sta/Elev= 30
  4402.3  322.65  4446.4  321.63  4476.6  319.55  4568.3   316.3  4599.1  313.26
  4629.3  312.97  4812.2  305.72  4842.7  305.13  4883.3   305.8  4889.9  304.86
  4897.6  305.51  4926.2  304.71  4953.6  305.92    4990  305.27  4996.5  301.33
  5002.5  300.75    5006  300.75  5010.8  303.11  5018.6  302.69  5039.4  305.31
    5046  306.31  5103.2  306.42  5138.3  308.58  5190.4   309.2  5279.1  311.99
  5295.5  313.69  5341.7  314.01  5383.4  316.39  5456.4  318.12  5695.5  329.54
#Mann= 3 , 0 , 0
  4402.3     .17       0    4990     .09       0  5039.4     .17       0
Bank Sta=4990,5039.4
XS Rating Curve= 0 ,0
Exp/Cntr=0.3,0.1

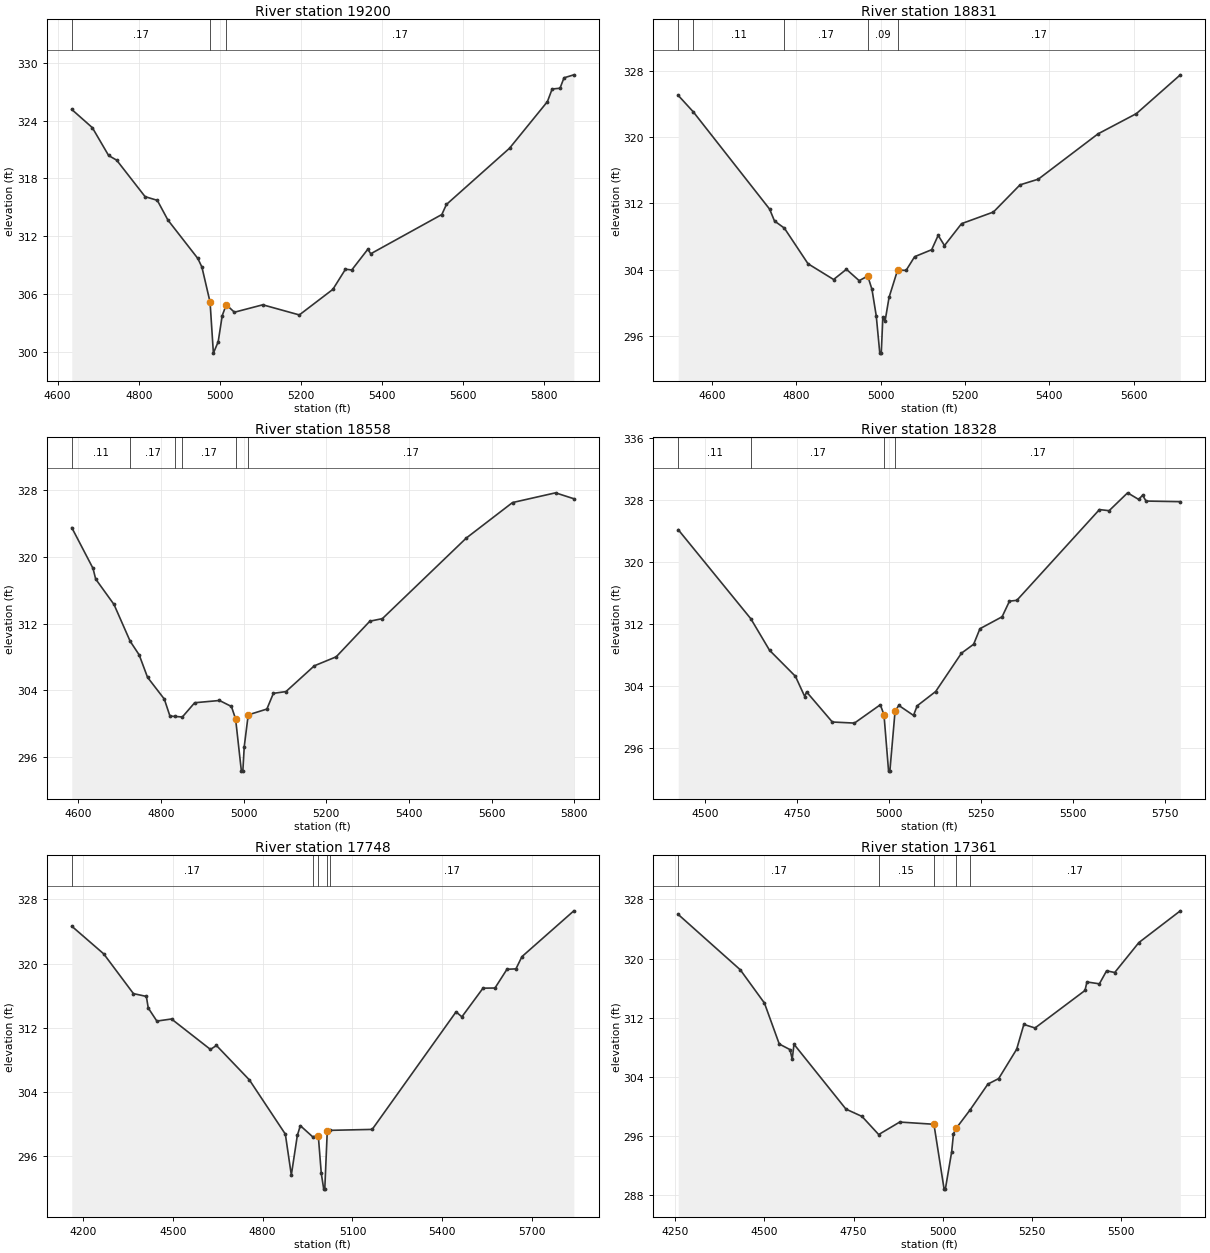
Type RM Length L Ch R = 1 ,19200   ,369,369,369
BEGIN DESCRIPTION:
Mapping XS 25aef246
END DESCRIPTION:
XS GIS Cut Line= 3
       3747861.8     10232281.79      3747840.45     10231714.05
      3748018.06     10231068.16
#Sta/Elev= 30
  4634.8  325.15  4685.6  323.26  4725.6  320.38  4745.6  319.89  4815.6  316.11
  4845.7  315.73  4871.8  313.69  4945.7   309.7  4955.7  308.81  4975.8  305.18
    4984  299.89  4995.8  301.06  5005.8  303.78  5015.8  304.91  5035.8  304.13
  5105.8   304.9  5195.9  303.85  5278.6   306.5  5309.7  308.59  5325.2  308.51
  5364.8  310.66    5372  310.19  5547.3  314.26  5558.6   315.3  5714.2  321.13
  5807.6  325.96  5819.3  327.27  5838.7  327.35  5848.5  328.43  5872.8  328.74
#Mann= 3 , 0 , 0
  4634.8     .17       0  4975.8     .09       0  5015.8     .17       0
Bank Sta=4975.8,5015.8
XS Rating Curve= 0 ,0
Exp/Cntr=0.3,0.1

Type RM Length L Ch R = 1 ,18831   ,273,273,273
BEGIN DESCRIPTION:
WELCH BRANCH 36.0
END DESCRIPTION:
XS GIS Cut Line= 2
      3748028.46     10232245.33      3748210.76     10231068.17
#Sta/Elev= 30
  4519.6  325.02  4555.3  323.04  4736.4  311.32    4748  309.89  4771.4  309.03
  4827.5  304.74  4888.2  302.84  4918.6  304.07  4948.9   302.7  4969.2  303.26
  4979.3  301.64  4989.4  298.46  4997.8  293.97  5001.3  293.97  5005.1  298.33
  5010.2  297.79  5019.8  300.69    5040  303.97  5060.2  303.94  5080.5  305.59
  5120.9  306.43  5136.3  308.16  5151.3  306.93  5191.8  309.57  5267.4  310.97
  5330.4  314.24  5373.9  314.93  5515.6  320.39  5606.7  322.83  5710.8   327.5
#Mann= 5 ,-1 , 0
  4519.6     .17       0  4555.3     .11       0  4771.4     .17       0
  4969.2     .09       0    5040     .17       0
Bank Sta=4969.2,5040
XS Rating Curve= 0 ,0
Exp/Cntr=0.3,0.1

Type RM Length L Ch R = 1 ,18558   ,230,230,230
BEGIN DESCRIPTION:
WELCH BRANCH 35.0
END DESCRIPTION:
XS GIS Cut Line= 3
      3748262.84     10232281.76      3748372.21     10231646.33
      3748470.98     10231084.92
#Sta/Elev= 30
  4584.2  323.54  4635.6  318.64    4642  317.36  4686.4   314.3  4725.4  309.89
  4747.3  308.24  4767.5  305.55  4808.1  302.93  4821.7  300.89  4834.5  300.84
  4851.8  300.78  4881.6  302.49  4941.6  302.76  4970.5  302.04  4980.6  300.54
  4994.6  294.27  4998.1  294.27  5001.5  297.21  5011.1  301.03  5056.3  301.73
    5072  303.62  5102.4  303.83  5171.1  306.93    5224  308.01  5305.4  312.29
  5335.8   312.6  5538.9  322.29  5650.6  326.55  5754.7  327.72    5799  327.01
#Mann= 6 ,-1 , 0
  4584.2     .11       0  4725.4     .17       0  4834.5     .11       0
  4851.8     .17       0  4980.6     .09       0  5011.1     .17       0
Bank Sta=4980.6,5011.1
XS Rating Curve= 0 ,0
Exp/Cntr=0.3,0.1

Type RM Length L Ch R = 1 ,18328   ,580,580,580
BEGIN DESCRIPTION:
WELCH BRANCH 34.0
END DESCRIPTION:
XS GIS Cut Line= 3
      3748429.49     10232401.56      3748515.73     10232280.39
      3748622.21     10231068.18
#Sta/Elev= 30
  4426.1  324.13  4623.6  312.65  4674.5  308.59  4744.8  305.24  4770.2  302.63
  4775.2  303.23  4845.2  299.35  4905.4  299.21  4975.7  301.57  4985.7  300.29
  4998.2  293.02  5001.7  293.02  5015.8  300.71  5025.9  301.49    5066   300.2
  5076.1  301.44  5126.3  303.28  5196.5  308.22  5229.6  309.37  5246.7  311.37
    5307  312.91    5327  314.92  5347.1  315.03  5571.7  326.72  5598.1  326.58
  5648.3  328.88  5678.4  328.03  5689.1  328.57  5698.5  327.82  5791.7  327.74
#Mann= 4 ,-1 , 0
  4426.1     .11       0  4623.6     .17       0  4985.7     .09       0
  5015.8     .17       0
Bank Sta=4985.7,5015.8
XS Rating Curve= 0 ,0
Exp/Cntr=0.3,0.1

Type RM Length L Ch R = 1 ,17748   ,387,387,387
BEGIN DESCRIPTION:
Mapping XS 28c224fc
END DESCRIPTION:
XS GIS Cut Line= 3
      3749111.81     10232667.17       3748924.3     10232437.99
      3748908.67      10231057.8
#Sta/Elev= 30
  4162.7  324.66  4269.5   321.2  4368.6  316.24  4411.7  315.89  4418.1  314.44
  4446.8  312.81  4495.7  313.07  4625.7  309.27  4645.8  309.76  4755.8  305.46
  4875.8  298.69  4895.8  293.58  4915.8  298.52  4925.8  299.75  4967.2  298.35
  4985.8   298.5  4995.8  293.79    5004  291.82  5007.5  291.82  5015.8  299.08
  5023.4  299.16  5165.8  299.28  5445.8  313.96  5465.3  313.34  5535.8  316.92
  5575.8  316.94  5615.8  319.28  5645.8  319.33  5665.8  320.86  5839.1  326.58
#Mann= 5 ,-1 , 0
  4162.7     .17       0  4967.2     .15       0  4985.8     .09       0
  5015.8     .15       0  5023.4     .17       0
Bank Sta=4985.8,5015.8
XS Rating Curve= 0 ,0
Exp/Cntr=0.3,0.1

Type RM Length L Ch R = 1 ,17361   ,422,422,422
BEGIN DESCRIPTION:
WELCH BRANCH 33.0
END DESCRIPTION:
XS GIS Cut Line= 2
      3749205.54     10232411.94      3749018.04     10231016.08
#Sta/Elev= 30
  4258.3  325.96  4432.3  318.48  4500.1  313.98  4541.7  308.44    4572  307.68
    4578  306.37    4583  308.41  4728.8  299.64  4773.8  298.65  4820.6   296.2
  4879.6  297.89  4975.6  297.59  5004.1  288.82  5007.6  288.82  5025.3  293.86
  5030.4   296.3  5037.6  297.02  5076.5   299.5  5126.9  303.02  5157.2  303.77
  5207.6  307.73  5227.8  311.09  5259.1  310.61  5399.3  315.68  5404.8  316.83
  5439.7  316.58  5459.9  318.34  5482.7  318.11  5550.5  322.16  5666.7  326.45
#Mann= 5 ,-1 , 0
  4258.3     .17       0  4820.6     .15       0  4975.6     .09       0
  5037.6     .15       0  5076.5     .17       0
Bank Sta=4975.6,5037.6
XS Rating Curve= 0 ,0
Exp/Cntr=0.3,0.1

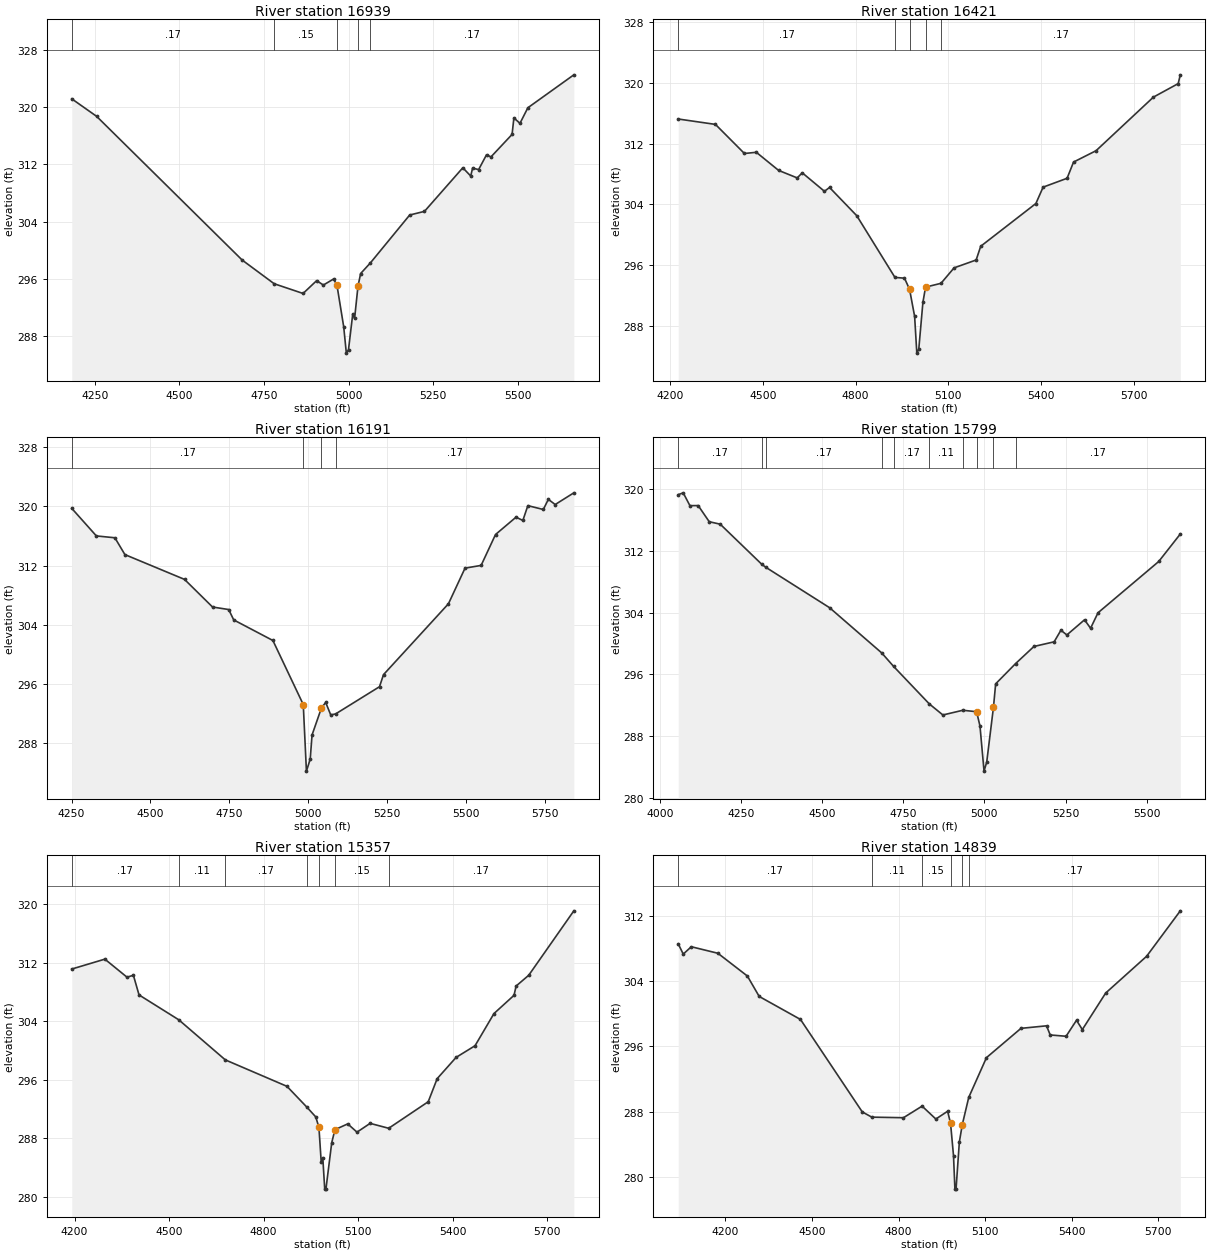
Type RM Length L Ch R = 1 ,16939   ,518,518,518
BEGIN DESCRIPTION:
WELCH BRANCH 32.0
END DESCRIPTION:
XS GIS Cut Line= 3
      3749390.44     10232434.47      3749428.23     10231616.84
      3749160.39     10231006.53
#Sta/Elev= 30
  4181.5  321.19    4255  318.74  4685.4  298.63  4780.2  295.31  4865.6  293.95
  4905.7  295.74  4925.7  295.13  4955.7  295.97  4965.7  295.15  4985.8  289.29
  4993.6   285.6    5000   286.1  5012.6  291.09    5018  290.45  5028.1  294.98
  5035.9  296.74  5064.8  298.23    5181  304.93  5224.7  305.44  5338.1  311.54
  5361.5  310.39    5367  311.49  5384.9  311.29  5408.2  313.36  5421.3  313.06
  5483.8  316.21  5489.2  318.52  5507.1  317.76  5530.5  319.94  5666.5  324.55
#Mann= 5 ,-1 , 0
  4181.5     .17       0  4780.2     .15       0  4965.7     .09       0
  5028.1     .15       0  5064.8     .17       0
Bank Sta=4965.7,5028.1
XS Rating Curve= 0 ,0
Exp/Cntr=0.3,0.1

Type RM Length L Ch R = 1 ,16421   ,230,230,230
BEGIN DESCRIPTION:
WELCH BRANCH 31.0
END DESCRIPTION:
XS GIS Cut Line= 3
      3750110.92     10232308.63      3749751.15     10231623.32
      3749260.23     10230928.44
#Sta/Elev= 30
    4226  315.25  4346.4  314.54  4440.2   310.7  4478.7  310.86  4550.8  308.47
    4611  307.48  4627.4  308.15  4699.2  305.71  4715.6  306.22  4803.8  302.49
  4927.3  294.35  4958.2  294.25  4974.6  292.78    4991  289.21  4998.1  284.36
  5004.4  284.86  5017.8  291.06  5026.4  293.07  5076.3  293.57  5118.7  295.61
  5190.1  296.65  5204.9  298.46  5383.4   304.1  5406.8  306.26  5484.4  307.43
  5505.3  309.57  5578.2  311.07  5763.8  318.14  5843.9  319.92  5850.8  321.08
#Mann= 5 ,-1 , 0
    4226     .17       0  4927.3     .15       0  4974.6     .09       0
  5026.4     .15       0  5076.3     .17       0
Bank Sta=4974.6,5026.4
XS Rating Curve= 0 ,0
Exp/Cntr=0.3,0.1

Type RM Length L Ch R = 1 ,16191   ,392,392,392
BEGIN DESCRIPTION:
WELCH BRANCH 30.0
END DESCRIPTION:
XS GIS Cut Line= 2
      3750327.96     10232208.86      3749543.11     10230825.61
#Sta/Elev= 30
  4250.7  319.73  4328.6  316.01  4387.3  315.76    4419  313.49  4607.9  310.14
  4696.6  306.41  4747.8  306.07  4763.7  304.67  4887.8  301.89    4984  293.24
    4994  284.25    5006  285.86  5011.8  289.13  5041.5  292.77    5055  293.53
  5070.9  291.85  5086.3  291.97  5225.5  295.65  5238.2  297.28  5443.9  306.85
  5496.4  311.66  5547.4  312.03    5593   316.2  5657.9  318.54  5679.6   318.1
  5695.4   320.1  5744.4  319.58  5760.3  320.95    5782  320.25  5841.1  321.83
#Mann= 4 ,-1 , 0
  4250.7     .17       0    4984     .09       0  5041.5     .15       0
  5086.3     .17       0
Bank Sta=4984,5041.5
XS Rating Curve= 0 ,0
Exp/Cntr=0.3,0.1

Type RM Length L Ch R = 1 ,15799   ,442,442,442
BEGIN DESCRIPTION:
Mapping XS 74cd580b
END DESCRIPTION:
XS GIS Cut Line= 2
      3750449.46     10232195.76      3750028.45     10230707.04
#Sta/Elev= 30
  4056.5  319.28  4071.8  319.52  4092.5  317.86    4118  317.87    4152  315.78
  4185.9  315.46  4314.1  310.26  4326.7  309.87  4522.8  304.65  4683.6  298.79
  4720.3  297.04  4830.2  292.19    4872  290.76  4933.5  291.37  4975.9  291.18
  4986.3  289.33  4998.8  283.49  5007.1  284.67  5027.8  291.74  5034.6  294.79
  5096.2  297.42  5152.6  299.63  5214.8  300.23  5235.7  301.73    5254  301.12
  5308.4  303.08  5327.1  301.99    5350  303.99  5537.1  310.63  5603.6  314.19
#Mann= 10 ,-1 , 0
  4056.5     .17       0  4314.1     .11       0  4326.7     .17       0
  4683.6     .11       0  4720.3     .17       0  4830.2     .11       0
  4933.5     .15       0  4975.9     .09       0  5027.8     .15       0
  5096.2     .17       0
Bank Sta=4975.9,5027.8
XS Rating Curve= 0 ,0
Exp/Cntr=0.3,0.1

Type RM Length L Ch R = 1 ,15357   ,518,518,518
BEGIN DESCRIPTION:
WELCH BRANCH 29.0
END DESCRIPTION:
XS GIS Cut Line= 3
      3750740.27     10232143.73      3750544.96     10231032.61
      3750575.34     10230568.16
#Sta/Elev= 30
  4191.1  311.11  4296.1  312.46  4366.4     310  4386.7  310.26  4404.6  307.58
  4530.6  304.19  4678.4  298.72  4874.2  295.11  4938.2  292.23  4965.5  290.94
  4975.6  289.51  4982.8   284.8  4987.8  285.39    4994  281.09  4997.8  281.09
  5016.2  287.42  5026.4   289.2    5067  289.99  5096.4  288.86  5138.1  290.06
    5197  289.39  5322.5  293.01  5350.9  296.16    5411  299.06  5471.1  300.65
  5531.2  305.04  5594.9  307.53  5601.4  308.79  5641.5  310.26  5784.7  319.05
#Mann= 7 ,-1 , 0
  4191.1     .17       0  4530.6     .11       0  4678.4     .17       0
  4938.2     .15       0  4975.6     .09       0  5026.4     .15       0
    5197     .17       0
Bank Sta=4975.6,5026.4
XS Rating Curve= 0 ,0
Exp/Cntr=0.3,0.1

Type RM Length L Ch R = 1 ,14839   ,903,903,903
BEGIN DESCRIPTION:
WELCH BRANCH 28.0
END DESCRIPTION:
XS GIS Cut Line= 4
      3750809.72     10232165.39      3750887.84     10231800.84
      3751030.21     10231085.07       3750931.3     10230455.71
#Sta/Elev= 30
  4036.5  308.57  4053.9  307.32  4081.8  308.22  4173.9  307.42  4276.1  304.63
    4317  302.13  4460.1  299.31  4674.2  287.98  4707.2  287.34  4816.9  287.27
  4881.5  288.69  4929.1  287.11  4969.9  288.06  4980.1  286.58  4990.3  282.63
  4995.2  278.52  4999.1  278.52  5010.6  284.31  5020.8  286.43  5043.1  289.76
  5104.5  294.63  5224.1  298.22  5312.7  298.53  5325.4  297.41  5380.4  297.25
  5416.5  299.21  5436.7  298.07  5517.7  302.55  5659.4  307.05  5776.2  312.62
#Mann= 6 ,-1 , 0
  4036.5     .17       0  4707.2     .11       0  4881.5     .15       0
  4980.1     .09       0  5020.8     .15       0  5043.1     .17       0
Bank Sta=4980.1,5020.8
XS Rating Curve= 0 ,0
Exp/Cntr=0.3,0.1

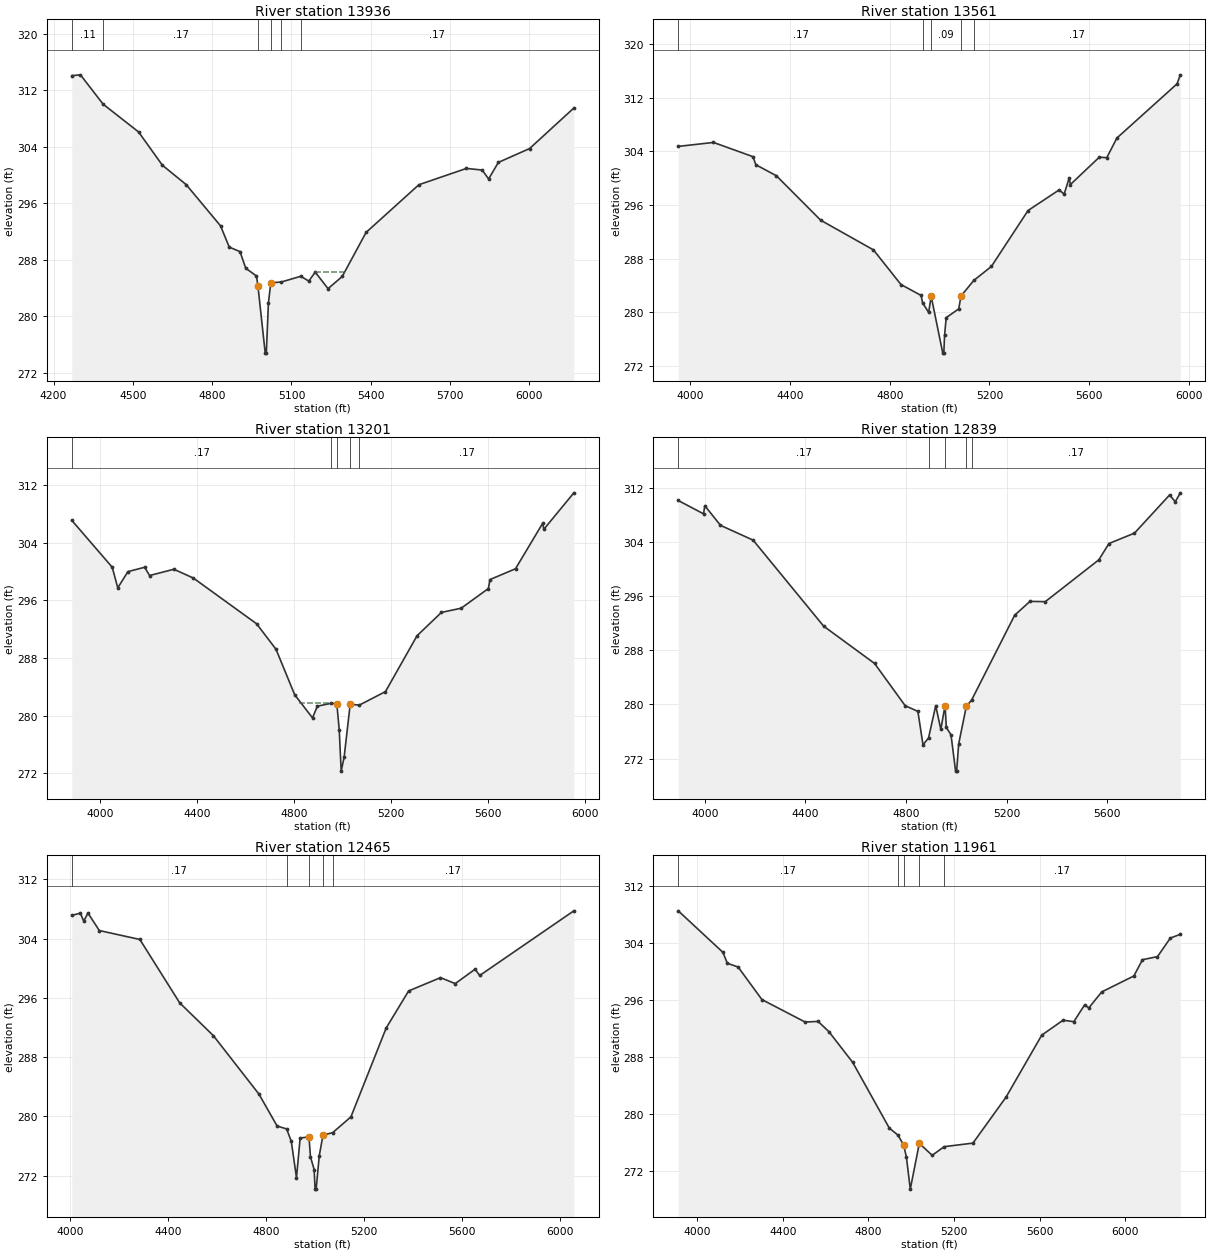
Type RM Length L Ch R = 1 ,13936   ,375,375,375
BEGIN DESCRIPTION:
WELCH BRANCH 27.0
END DESCRIPTION:
XS GIS Cut Line= 3
      3751473.78     10232273.88      3751486.83     10231692.37
      3751005.43     10230465.06
#Sta/Elev= 30
  4268.7  314.05  4301.5  314.17  4387.5  310.01  4521.6  306.08  4611.6  301.37
  4701.6  298.63  4831.7  292.79  4864.6  289.78  4905.5  289.14  4926.9  286.79
  4967.7  285.69    4973  284.34  5000.8  274.77  5004.9  274.77  5012.9  281.88
  5021.9  284.74  5060.9  284.83  5135.3  285.65  5165.6  284.97    5190  286.24
  5238.5   283.9  5292.2  285.62  5382.5  291.86  5582.2  298.61  5762.2  300.92
  5821.8  300.69  5846.2  299.43    5883  301.77  6001.1  303.73  6168.7  309.47
#Mann= 6 ,-1 , 0
  4268.7     .11       0  4387.5     .17       0    4973     .09       0
  5021.9     .17       0  5060.9     .15       0  5135.3     .17       0
#XS Ineff= 1 ,-1
    5190    5300  286.24
Permanent Ineff=
       F
Bank Sta=4973,5021.9
XS Rating Curve= 0 ,0
Exp/Cntr=0.3,0.1

Type RM Length L Ch R = 1 ,13561   ,360,360,360
BEGIN DESCRIPTION:
WELCH BRANCH 26.0
END DESCRIPTION:
XS GIS Cut Line= 2
      3751799.29     10232338.99      3751560.58     10230338.18
#Sta/Elev= 30
  3951.1  304.73  4092.5  305.32  4251.1   303.2  4262.5     302    4345  300.36
    4523  293.73  4734.5  289.32  4844.9  284.16  4925.9  282.53  4931.6  281.44
  4956.1     280  4966.2  282.41  5012.8  273.94    5017  273.94    5020   276.6
  5026.6  279.23  5076.9  280.53  5085.8 282.442  5137.4  284.77  5207.9  286.85
    5355  295.18  5479.8  298.25  5499.9  297.62    5520  300.02    5525  299.05
  5640.9  303.12  5671.1  303.05  5711.4  305.97  5953.1  314.05  5966.1  315.39
#Mann= 5 ,-1 , 0
  3951.1     .17       0  4931.6     .15       0  4966.2     .09       0
  5085.8     .15       0  5137.4     .17       0
Bank Sta=4966.2,5085.8
XS Rating Curve= 0 ,0
Exp/Cntr=0.3,0.1

Type RM Length L Ch R = 1 ,13201   ,362,362,362
BEGIN DESCRIPTION:
Mapping XS 73fe2ece
END DESCRIPTION:
XS GIS Cut Line= 3
      3752042.38     10232339.07      3751903.46     10232135.04
      3752064.05     10230316.45
#Sta/Elev= 30
  3881.7  307.13  4048.7  300.61  4071.6  297.75  4113.5     300  4182.7  300.61
  4202.8  299.46  4303.2  300.33  4383.5  299.11  4644.5  292.76  4724.8  289.21
  4801.9  282.89  4875.4  279.68  4895.5   281.3  4953.3  281.71  4975.8  281.63
  4985.8     278  4993.8  272.28  5005.9   274.2    5031  281.58  5068.4  281.45
  5176.6  283.33  5307.1   291.1  5407.5  294.33  5489.3  294.92  5601.3  297.65
  5608.2   298.9  5713.4   300.4  5825.5  306.71  5830.5  305.89  5954.2  310.95
#Mann= 5 ,-1 , 0
  3881.7     .17       0  4953.3     .15       0  4975.8     .09       0
    5031     .15       0  5068.4     .17       0
#XS Ineff= 1 ,-1
    4820  4955.7  281.75
Permanent Ineff=
       F
Bank Sta=4975.8,5031
XS Rating Curve= 0 ,0
Exp/Cntr=0.3,0.1

Type RM Length L Ch R = 1 ,12839   ,374,374,374
BEGIN DESCRIPTION:
WELCH BRANCH 25.0
END DESCRIPTION:
XS GIS Cut Line= 2
      3752146.53     10232321.63      3752459.02     10230351.15
#Sta/Elev= 30
  3894.7  310.09  3995.2  308.12  4000.3  309.32  4062.6  306.42  4192.2  304.24
  4472.4  291.55  4674.9  286.04  4796.4  279.81    4847  278.97  4867.3  274.03
  4889.3  275.04  4917.9  279.81  4938.1  276.32    4955  279.83    4960  276.59
  4978.6  275.52  4996.8  270.15    5001  270.15    5009  274.14  5039.4   279.7
    5061  280.68  5231.8  293.17  5292.5   295.2  5353.3  295.16  5565.9  301.33
  5606.4  303.74  5707.6  305.27  5847.4  310.91  5869.6  309.89  5889.8  311.22
#Mann= 5 ,-1 , 0
  3894.7     .17       0  4889.3     .15       0    4955     .09       0
  5039.4     .15       0    5061     .17       0
Bank Sta=4955,5039.4
XS Rating Curve= 0 ,0
Exp/Cntr=0.3,0.1

Type RM Length L Ch R = 1 ,12465   ,504,504,504
BEGIN DESCRIPTION:
WELCH BRANCH 24.0
END DESCRIPTION:
XS GIS Cut Line= 4
      3752250.69     10232317.32      3752510.27     10231573.42
      3752726.66     10231248.34      3752775.86     10230377.24
#Sta/Elev= 30
  4007.6  307.15  4042.6  307.44  4056.6  306.37  4073.7  307.46  4120.1   305.1
  4285.8  303.89  4448.5  295.33  4585.9  290.91  4772.2  283.01  4846.4   278.7
  4885.4  278.31  4904.4  276.62  4925.5  271.73  4940.5  277.08  4976.6  277.23
  4982.6  274.55  4997.6  272.83  5001.5  270.18  5005.8  270.18  5018.6  274.69
  5033.7  277.47  5073.6  277.81  5147.9  279.94  5292.1  291.95  5383.6  296.94
  5513.8  298.74  5573.9  297.93  5654.8  299.87  5674.1  299.03  6058.5  307.76
#Mann= 5 ,-1 , 0
  4007.6     .17       0  4885.4     .15       0  4976.6     .09       0
  5033.7     .15       0  5073.6     .17       0
Bank Sta=4976.6,5033.7
XS Rating Curve= 0 ,0
Exp/Cntr=0.3,0.1

Type RM Length L Ch R = 1 ,11961   ,477,477,477
BEGIN DESCRIPTION:
WELCH BRANCH 23.0
END DESCRIPTION:
XS GIS Cut Line= 3
      3753101.37     10232738.29      3752981.75      10231854.4
      3752893.13     10230404.66
#Sta/Elev= 30
  3912.2  308.52  4120.6  302.71  4141.5  301.17  4191.9  300.64    4303  296.08
  4504.8  292.93  4565.3  293.02  4615.8  291.58  4726.8  287.28  4897.7  278.07
  4937.7  277.09  4964.6  275.72  4977.8  273.96  4995.7  269.51  5037.9  275.92
    5098  274.25    5154  275.46  5288.4  275.96  5442.7   282.4  5609.8   291.1
  5709.2  293.19  5759.3  292.98  5809.4  295.32  5829.4  294.92  5889.5  297.15
  6039.8  299.39  6079.9  301.67    6150   302.1  6210.1   304.7  6256.6  305.23
#Mann= 5 ,-1 , 0
  3912.2     .17       0  4937.7     .15       0  4964.6     .09       0
  5037.9     .15       0    5154     .17       0
Bank Sta=4964.6,5037.9
XS Rating Curve= 0 ,0
Exp/Cntr=0.3,0.1

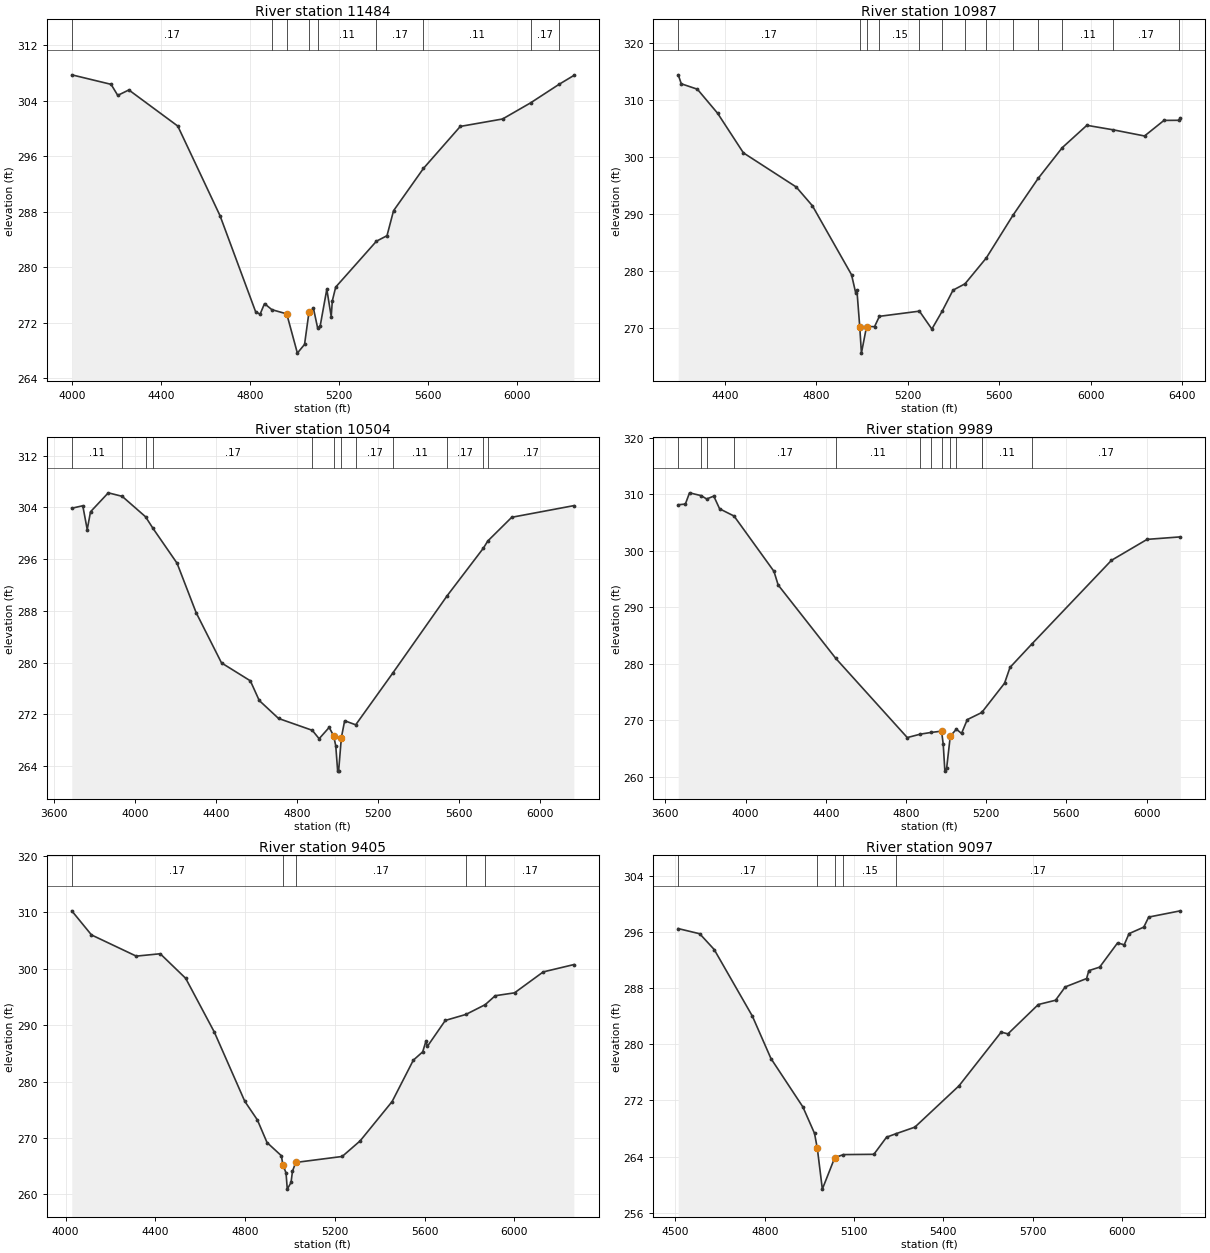
Type RM Length L Ch R = 1 ,11484   ,497,497,497
BEGIN DESCRIPTION:
WELCH BRANCH 22.0
END DESCRIPTION:
XS GIS Cut Line= 3
      3753309.71     10232577.78       3753335.8     10231576.72
      3753387.84     10230320.79
#Sta/Elev= 30
  3998.6  307.72  4175.4  306.35  4205.4  304.76  4255.4  305.54  4475.5  300.34
  4665.5  287.43  4825.6   273.6  4845.6  273.24  4865.6  274.77  4898.6   273.9
  4965.6  273.29  5013.4  267.64  5045.7   268.9  5065.7  273.57  5085.7  274.09
  5104.3   271.3  5115.7   271.5  5145.8  276.84  5165.6  272.91  5170.6  275.17
  5185.8  277.15  5369.1  283.76  5416.5  284.55    5446  288.15  5580.7  294.25
  5746.3  300.29  5936.4  301.36  6062.3  303.68  6190.4  306.35    6257  307.63
#Mann= 9 ,-1 , 0
  3998.6     .17       0  4898.6     .15       0  4965.6     .09       0
  5065.7     .15       0  5104.3     .11       0  5369.1     .17       0
  5580.7     .11       0  6062.3     .17       0  6190.4     .11       0
#XS Ineff= 1 ,-1
  5145.8    5190  276.84
Permanent Ineff=
       F
Bank Sta=4965.6,5065.7
XS Rating Curve= 0 ,0
Exp/Cntr=0.3,0.1

Type RM Length L Ch R = 1 ,10987   ,483,483,483
BEGIN DESCRIPTION:
WELCH BRANCH 21.0
END DESCRIPTION:
XS GIS Cut Line= 3
      3753652.59     10232534.35      3753745.64     10231735.65
      3753552.84     10230356.06
#Sta/Elev= 30
  4195.9  314.43  4209.3  312.86  4279.6  311.91  4368.1   307.7  4481.1  300.75
  4712.1  294.77  4783.1  291.47  4954.3  279.38  4972.6  276.18  4977.7  276.72
  4990.4 270.152  4997.5  265.64    5020  270.29  5055.1  270.29  5076.1  272.09
  5251.3     273  5305.8  269.86  5351.1  273.01  5398.4  276.68  5450.8  277.79
  5543.9  282.32  5660.4  289.79  5770.9  296.27  5876.6  301.67  5984.1  305.58
  6099.1  304.79  6236.5  303.71  6321.5  306.44  6388.8  306.46    6393  306.78
#Mann= 13 ,-1 , 0
  4195.9     .17       0  4990.4     .09       0    5020     .17       0
  5076.1     .15       0  5251.3     .11       0  5351.1     .17       0
  5450.8     .11       0  5543.9     .17       0  5660.4     .11       0
  5770.9     .17       0  5876.6     .11       0  6099.1     .17       0
  6388.8     .11       0
Bank Sta=4990.4,5020
XS Rating Curve= 0 ,0
Exp/Cntr=0.3,0.1

Type RM Length L Ch R = 1 ,10504   ,515,515,515
BEGIN DESCRIPTION:
WELCH BRANCH 20.0
END DESCRIPTION:
XS GIS Cut Line= 3
      3754698.61     10232603.81      3753908.67     10231119.42
      3753652.71     10230360.21
#Sta/Elev= 30
  3685.8  303.85  3740.3  304.23  3762.2  300.55  3778.5   303.3  3866.4  306.23
    3935  305.69  4050.6  302.53  4087.8  300.72  4206.6  295.34  4300.6  287.72
  4426.3  279.94  4568.8  277.17  4612.8  274.13  4708.4  271.35    4875  269.52
    4909  268.22  4958.6  269.97  4980.6  268.68  4991.2  267.12  5000.6  263.21
  5005.3  263.21  5018.9  268.39  5035.2     271  5089.8  270.37  5274.5  278.43
    5542  290.32  5721.2  297.68  5742.8  298.78  5861.5  302.45  6168.5  304.25
#Mann= 12 ,-1 , 0
  3685.8     .11       0    3935     .17       0  4050.6     .11       0
  4087.8     .17       0    4875     .15       0  4980.6     .09       0
  5018.9     .15       0  5089.8     .17       0  5274.5     .11       0
    5542     .17       0  5721.2     .11       0  5742.8     .17       0
Bank Sta=4980.6,5018.9
XS Rating Curve= 0 ,0
Exp/Cntr=0.3,0.1

Type RM Length L Ch R = 1 ,9989    ,584,584,584
BEGIN DESCRIPTION:
WELCH BRANCH 19.0
END DESCRIPTION:
XS GIS Cut Line= 3
      3755267.18     10232330.35      3754467.71     10231260.08
      3753739.39     10230346.84
#Sta/Elev= 30
  3664.1  308.18  3699.6   308.3  3720.4  310.29  3778.7  309.79  3805.9   309.2
  3841.3  309.71  3870.5  307.46  3942.5  306.18  4141.5  296.39  4162.5  293.97
  4450.3  280.96  4806.4  266.96  4871.9  267.57  4923.7  267.86  4977.4   268.1
  4985.7  265.78  4993.9  261.02  5002.6  261.52  5020.9  267.22  5051.4  268.45
  5076.9  267.69  5105.7  270.14  5178.7  271.41  5180.2  271.51  5291.5  276.58
  5318.7  279.38  5429.6   283.6  5824.7  298.34  6002.5  302.05  6168.1  302.49
#Mann= 13 ,-1 , 0
  3664.1     .11       0  3778.7     .17       0  3805.9     .11       0
  3942.5     .17       0  4450.3     .11       0  4871.9     .17       0
  4923.7     .15       0  4977.4     .09       0  5020.9     .15       0
  5051.4     .17       0  5178.7     .15       0  5180.2     .11       0
  5429.6     .17       0
Bank Sta=4977.4,5020.9
XS Rating Curve= 0 ,0
Exp/Cntr=0.3,0.1

Type RM Length L Ch R = 1 ,9405    ,308,308,308
BEGIN DESCRIPTION:
WELCH BRANCH 18.0
END DESCRIPTION:
XS GIS Cut Line= 3
      3755605.72     10231657.61      3754815.79     10231010.91
      3753826.24     10230303.47
#Sta/Elev= 30
  4027.6  310.28  4115.4  306.01  4314.9  302.25  4421.8  302.67  4535.3  298.31
    4663  288.77  4798.7   276.5  4854.7  273.21  4897.7   269.2  4961.6  266.86
  4968.3  265.25  4982.4  263.81  4987.9  260.94  5004.7  262.12  5011.1  264.11
  5025.5  265.67  5232.6  266.73  5312.5  269.49    5455  276.46  5549.6   283.8
  5591.4  285.28  5606.1   287.2  5612.3  286.25  5692.2  290.85  5783.9  291.91
  5869.8  293.64  5914.6  295.23  6000.6  295.74  6128.4  299.45  6264.9  300.75
#Mann= 5 ,-1 , 0
  4027.6     .17       0  4968.3     .09       0  5025.5     .17       0
  5783.9     .11       0  5869.8     .17       0
Bank Sta=4968.3,5025.5
XS Rating Curve= 0 ,0
Exp/Cntr=0.3,0.1

Type RM Length L Ch R = 1 ,9097    ,484,484,484
BEGIN DESCRIPTION:
WELCH BRANCH 17.0
END DESCRIPTION:
XS GIS Cut Line= 3
      3755397.36     10230889.37      3754768.05     10230711.43
      3753856.63     10230227.53
#Sta/Elev= 30
  4509.5  296.48  4581.7  295.74  4630.2   293.5  4758.4  284.01  4820.8  277.97
  4927.9  271.08  4967.1  267.31  4976.6  265.15  4993.4  259.36    5035  263.84
  5064.1  264.28  5166.4  264.32    5209  266.76  5239.1  267.23    5304  268.19
  5452.3  274.08  5593.9  281.73  5616.6  281.48  5718.5  285.66  5776.4  286.27
    5809  288.17  5880.6  289.36  5888.3  290.49  5924.6  290.99  5984.9  294.45
  6006.9  294.16  6023.2  295.76  6072.8  296.69  6089.2  298.12  6195.4  299.01
#Mann= 5 ,-1 , 0
  4509.5     .17       0  4976.6     .09       0    5035     .17       0
  5064.1     .15       0  5239.1     .17       0
Bank Sta=4976.6,5035
XS Rating Curve= 0 ,0
Exp/Cntr=0.3,0.1