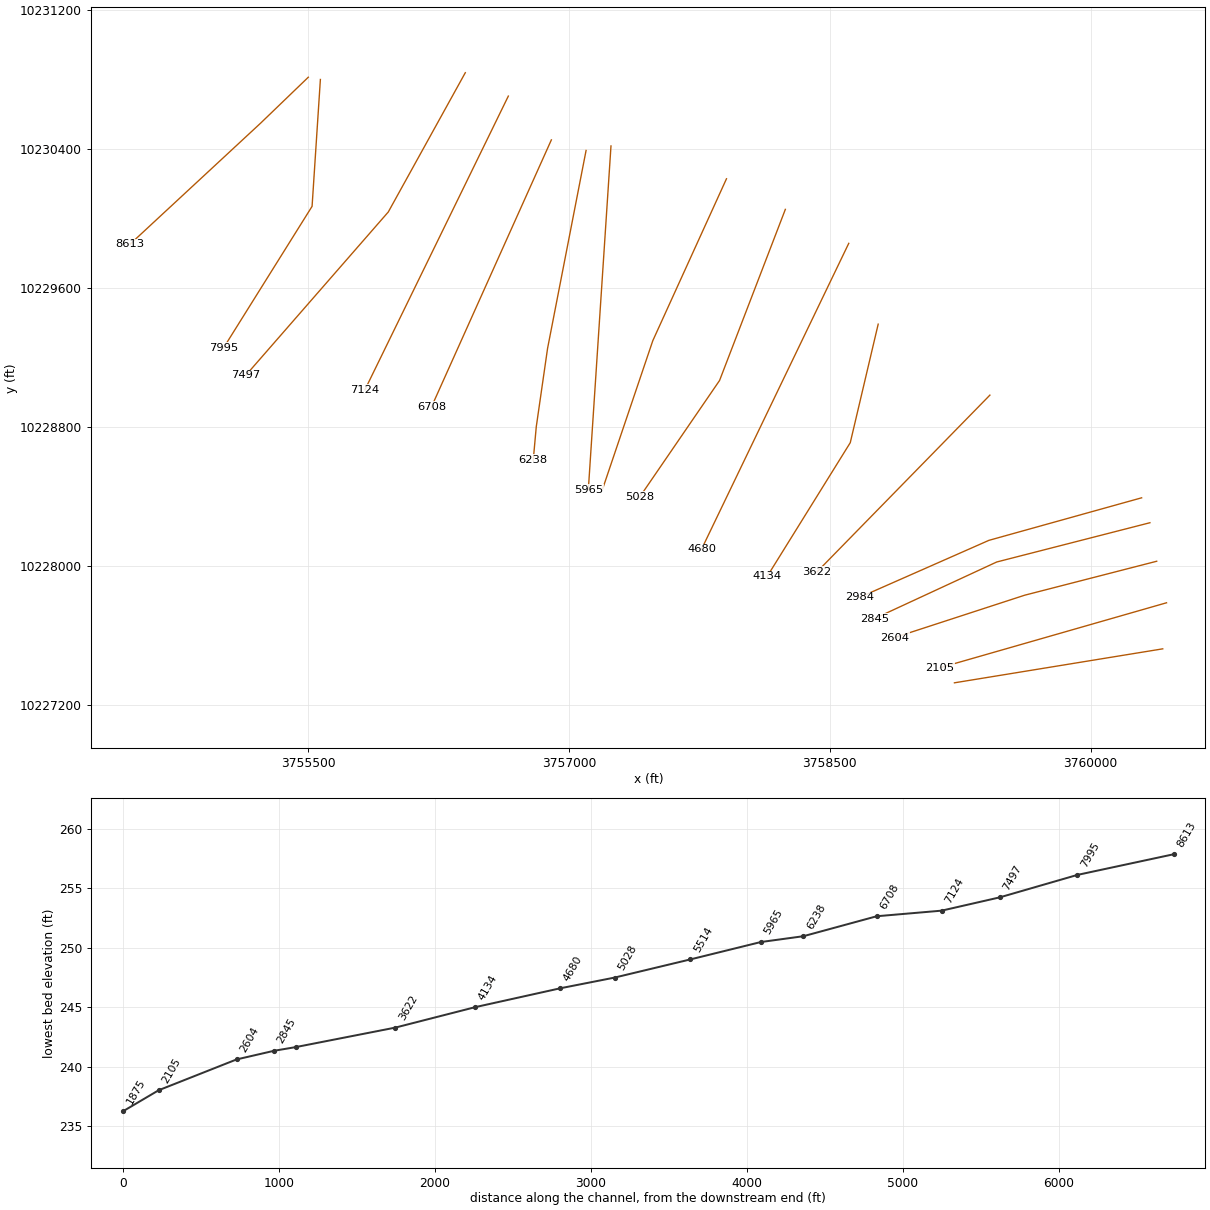
HEC-RAS study WELCH BRANCH.prj: WELCH BRANCH Base Level Engineering

--- WELCH BRANCH.g01 (geometry) --- (continued)

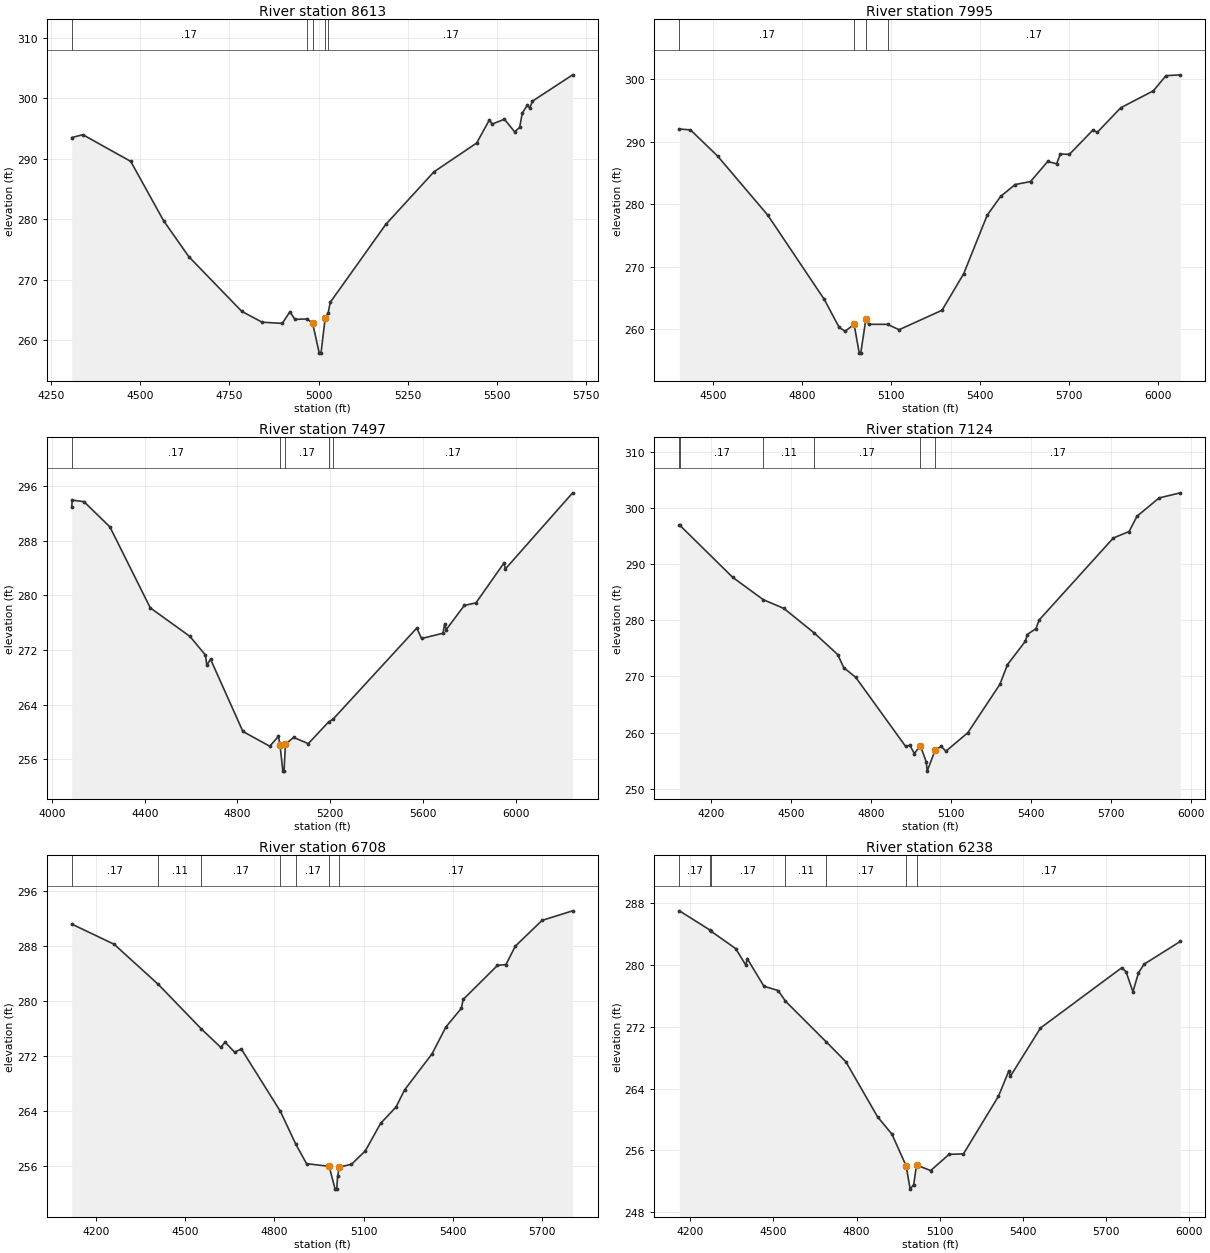
Type RM Length L Ch R = 1 ,8613    ,618,618,618
BEGIN DESCRIPTION:
WELCH BRANCH 16.0
END DESCRIPTION:
XS GIS Cut Line= 3
      3755501.55     10230811.25      3755226.94     10230546.91
      3754477.28     10229852.09
#Sta/Elev= 30
  4308.2  293.52  4339.3     294  4473.6  289.58  4565.5  279.78  4636.2  273.83
  4784.6  264.78  4841.3  262.99    4898  262.79  4919.5  264.71  4933.5  263.45
  4966.8  263.53    4983  262.86  5001.6  257.87  5006.5  257.87  5018.2  263.63
  5026.7  264.53  5032.4  266.27  5188.3  279.18  5322.6  287.84  5442.8  292.63
  5478.5  296.48  5485.4  295.75  5520.5  296.55  5548.9  294.48    5563   295.2
  5570.4  297.59  5584.6  298.87  5591.4  298.41  5598.7  299.54  5711.5   303.9
#Mann= 5 ,-1 , 0
  4308.2     .17       0  4966.8     .15       0    4983     .09       0
  5018.2     .15       0  5026.7     .17       0
Bank Sta=4983,5018.2
XS Rating Curve= 0 ,0
Exp/Cntr=0.3,0.1

Type RM Length L Ch R = 1 ,7995    ,498,498,498
BEGIN DESCRIPTION:
WELCH BRANCH 15.0
END DESCRIPTION:
XS GIS Cut Line= 3
        3755571.     10230798.24      3755523.25     10230069.07
      3755015.46     10229257.47
#Sta/Elev= 30
  4387.6  292.03  4424.9  291.89  4516.2   287.7  4685.4  278.23  4875.8  264.73
  4925.9  260.25    4946  259.64  4976.2  260.74  4993.6  256.13  4998.6  256.13
  5016.1  261.65  5026.1  260.75  5088.8  260.74  5127.8  259.88  5272.6     263
  5345.7  268.87  5424.7  278.22  5469.9  281.23    5519  283.14  5570.8  283.61
  5628.6  286.83  5658.6  286.46  5671.1  288.02  5701.7  287.97  5780.7  291.85
    5796  291.52    5875  295.44  5984.7  298.15  6027.1  300.57  6075.7  300.71
#Mann= 4 ,-1 , 0
  4387.6     .17       0  4976.2     .09       0  5016.1     .15       0
  5088.8     .17       0
Bank Sta=4976.2,5016.1
XS Rating Curve= 0 ,0
Exp/Cntr=0.3,0.1

Type RM Length L Ch R = 1 ,7497    ,373,373,373
BEGIN DESCRIPTION:
WELCH BRANCH 14.0
END DESCRIPTION:
XS GIS Cut Line= 3
      3756404.31     10230837.26      3755961.41     10230036.59
      3755142.08     10229097.73
#Sta/Elev= 30
    4085  292.93  4087.2  293.94  4137.8  293.72  4249.8  290.02  4423.9  278.16
  4594.9  273.98  4662.1  271.24  4667.8  269.76  4683.9  270.64  4823.5  260.05
  4939.2  257.89    4977  259.33  4983.5  258.07    4996  254.24  5001.1  254.24
  5006.9  258.16    5042  259.18  5105.6  258.27  5193.9  261.47  5211.9  261.83
  5573.6   275.2  5594.4  273.67  5686.5  274.44  5694.1  275.82  5700.8  274.97
  5778.6  278.51  5828.9  278.89  5949.5  284.71  5956.1  283.87  6246.1  295.01
#Mann= 5 ,-1 , 0
    4085     .17       0  4983.5     .09       0  5006.9     .17       0
  5193.9     .15       0  5211.9     .17       0
Bank Sta=4983.5,5006.9
XS Rating Curve= 0 ,0
Exp/Cntr=0.3,0.1

Type RM Length L Ch R = 1 ,7124    ,416,416,416
BEGIN DESCRIPTION:
WELCH BRANCH 13.0
END DESCRIPTION:
XS GIS Cut Line= 2
      3756651.74     10230702.78      3755827.48     10229015.22
#Sta/Elev= 30
  4080.7  296.92    4083  296.92  4280.3  287.68  4395.3  283.68  4472.1  282.14
  4585.6  277.77  4674.3   273.9  4696.8  271.57  4741.9  269.83  4928.4  257.55
  4944.6  257.71  4961.5  256.26    4984  257.66  5006.3  254.75  5009.5  253.12
  5040.2  256.95  5062.7  257.52  5079.7  256.67  5162.1  259.98  5282.4  268.61
  5310.5  272.11    5378   276.3  5384.7  277.47  5417.5  278.54  5429.2  280.06
  5707.5  294.69  5766.5  295.84  5796.5  298.58  5879.1  301.83  5958.8  302.74
#Mann= 6 ,-1 , 0
  4080.7     .11       0    4083     .17       0  4395.3     .11       0
  4585.6     .17       0    4984     .09       0  5040.2     .17       0
Bank Sta=4984,5040.2
XS Rating Curve= 0 ,0
Exp/Cntr=0.3,0.1

Type RM Length L Ch R = 1 ,6708    ,470,470,470
BEGIN DESCRIPTION:
WELCH BRANCH 12.0
END DESCRIPTION:
XS GIS Cut Line= 2
      3756899.14     10230451.05      3756209.37     10228915.34
#Sta/Elev= 30
  4118.5  291.16  4261.2  288.22  4409.6  282.39  4553.5  275.95  4619.6  273.24
  4633.7  274.01    4666  272.55  4688.5  273.01  4819.4  263.98  4871.8  259.16
  4907.8  256.35  4983.6  255.96  5003.8  252.65    5009  252.65  5012.2  254.55
  5017.7  255.86  5058.5  256.25  5104.9  258.19  5156.7  262.21  5208.5  264.58
  5237.1  267.06  5329.8  272.33  5376.1  276.21  5427.9  278.92    5434   280.2
  5549.3  285.15  5577.9  285.28  5609.4  287.95  5699.2  291.69    5802  293.08
#Mann= 7 ,-1 , 0
  4118.5     .17       0  4409.6     .11       0  4553.5     .17       0
  4819.4     .11       0  4871.8     .17       0  4983.6     .09       0
  5017.7     .17       0
Bank Sta=4983.6,5017.7
XS Rating Curve= 0 ,0
Exp/Cntr=0.3,0.1

Type RM Length L Ch R = 1 ,6238    ,273,273,273
BEGIN DESCRIPTION:
Mapping XS aceec017
END DESCRIPTION:
XS GIS Cut Line= 4
      3757098.78     10230390.29      3756877.42      10229253.1
      3756812.32     10228801.71      3756794.95     10228610.69
#Sta/Elev= 30
  4161.2  287.05  4271.6  284.55    4274  284.44  4364.2  282.15  4400.7  280.01
  4405.8  280.85    4466  277.27    4517  276.72  4543.6  275.34  4689.6   270.1
  4761.5  267.48  4875.6  260.35  4927.3  258.11  4978.9  253.97  4993.1  250.97
    5006  251.56  5016.2  254.09  5067.1  253.38  5133.8  255.48  5185.4  255.54
  5311.6  263.01  5349.4  266.33  5354.4  265.59  5463.2  271.86  5756.2  279.67
  5771.7  279.16  5796.5  276.55  5816.6  279.02  5836.7  280.13  5967.6  283.09
#Mann= 7 ,-1 , 0
  4161.2     .17       0  4271.6     .11       0    4274     .17       0
  4543.6     .11       0  4689.6     .17       0  4978.9     .09       0
  5016.2     .17       0
Bank Sta=4978.9,5016.2
XS Rating Curve= 0 ,0
Exp/Cntr=0.3,0.1

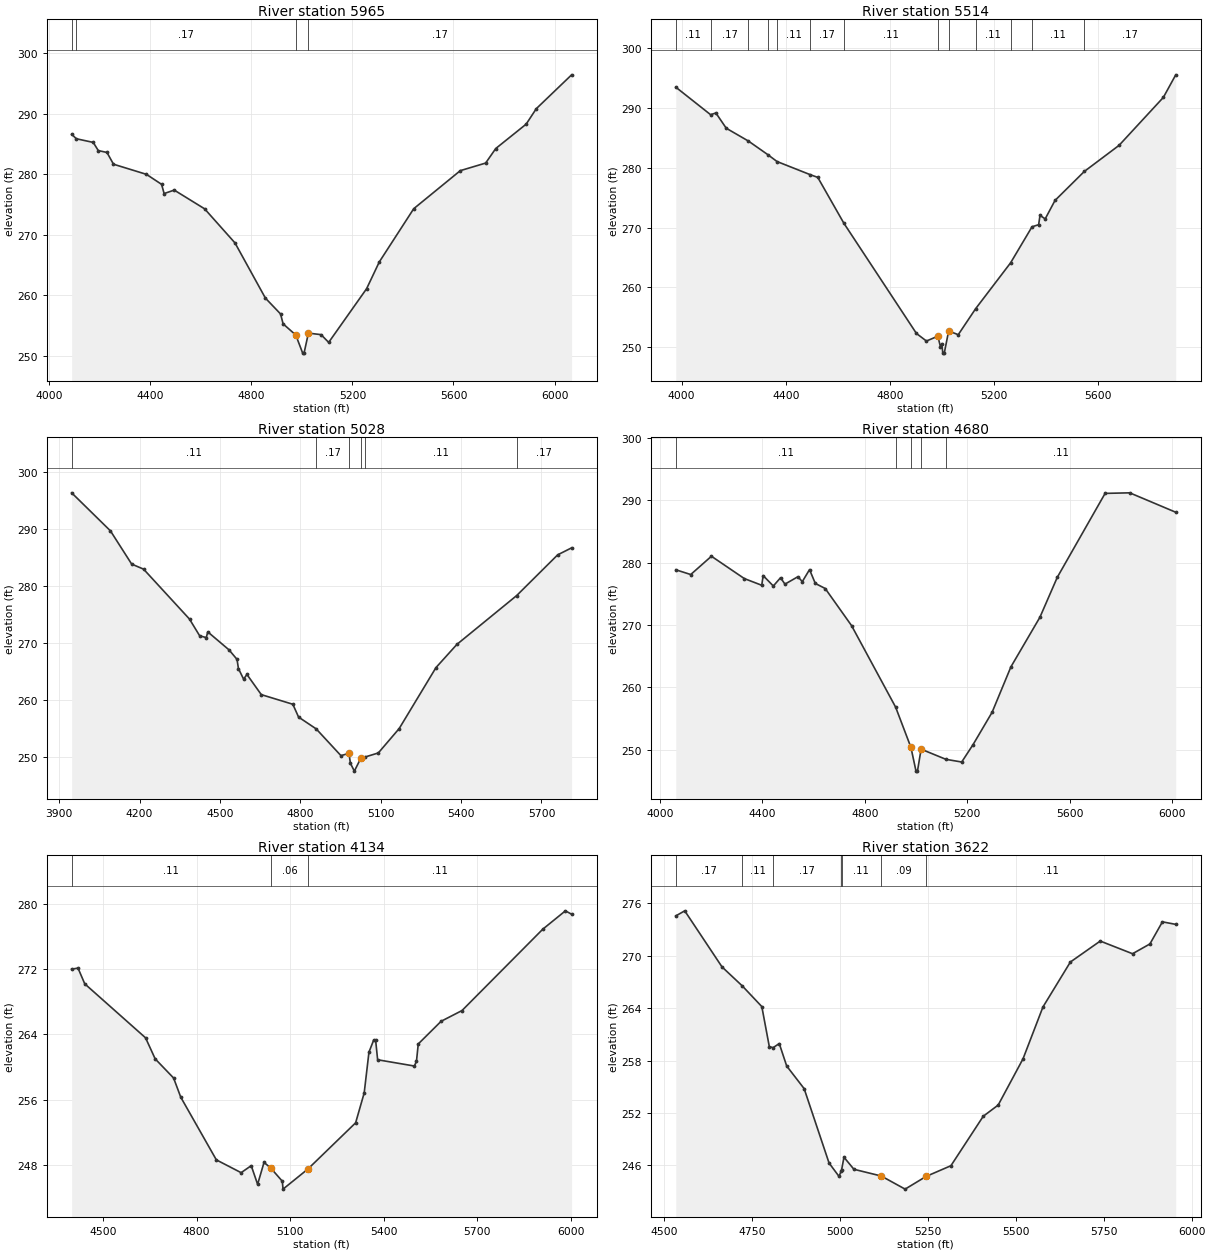
Type RM Length L Ch R = 1 ,5965    ,451,451,451
BEGIN DESCRIPTION:
WELCH BRANCH 11.0
END DESCRIPTION:
XS GIS Cut Line= 2
        3757242.     10230416.27       3757111.8     10228441.46
#Sta/Elev= 30
  4088.6  286.59  4107.3  285.85    4174  285.25    4194   283.9  4228.4  283.59
  4254.2  281.65  4384.6  279.98  4444.6  278.33  4454.6  276.81  4494.7  277.38
  4614.9  274.29  4735.2  268.66  4855.5  259.56  4915.6  256.94  4925.6  255.31
  4975.7  253.47  5003.1  250.48  5008.5  250.48  5025.8  253.78  5075.9  253.53
    5106  252.25  5256.3  261.12  5306.4  265.53  5442.7  274.31  5627.1  280.59
  5727.3  281.84  5767.4  284.24  5887.7  288.26  5927.8  290.81  6067.7   296.4
#Mann= 4 ,-1 , 0
  4088.6     .11       0  4107.3     .17       0  4975.7     .09       0
  5025.8     .17       0
Bank Sta=4975.7,5025.8
XS Rating Curve= 0 ,0
Exp/Cntr=0.3,0.1

Type RM Length L Ch R = 1 ,5514    ,486,486,486
BEGIN DESCRIPTION:
WELCH BRANCH 10.0
END DESCRIPTION:
XS GIS Cut Line= 3
      3757906.07     10230227.52      3757482.44      10229296.9
      3757194.31     10228445.96
#Sta/Elev= 30
  3977.5  293.44  4111.3  288.84  4131.5  289.13  4171.4  286.58  4256.5  284.44
    4331  282.17  4366.4  281.02  4493.7  278.83    4523  278.37  4623.2  270.72
  4902.2   252.3  4940.5  251.04  4984.4  251.85  4994.5  250.06  4999.5  250.61
  5003.4  249.02    5009  249.02  5025.9  252.72  5062.7   252.1  5129.7  256.45
    5264  264.11  5346.2  270.12  5371.6  270.47  5376.9  272.03  5396.8  271.44
  5434.5  274.52  5547.3  279.37  5680.6  283.72  5850.8  291.73  5898.4   295.5
#Mann= 13 ,-1 , 0
  3977.5     .11       0  4111.3     .17       0  4256.5     .11       0
    4331     .17       0  4366.4     .11       0  4493.7     .17       0
  4623.2     .11       0  4984.4     .07       0  5025.9     .17       0
  5129.7     .11       0    5264     .17       0  5346.2     .11       0
  5547.3     .17       0
Bank Sta=4984.4,5025.9
XS Rating Curve= 0 ,0
Exp/Cntr=0.3,0.1

Type RM Length L Ch R = 1 ,5028    ,348,348,348
BEGIN DESCRIPTION:
WELCH BRANCH 9.0
END DESCRIPTION:
XS GIS Cut Line= 3
      3758244.59     10230051.67      3757866.43     10229068.28
      3757406.94     10228398.06
#Sta/Elev= 30
  3946.4  296.31  4091.1  289.64  4170.4  283.81  4214.9  282.92  4386.3  274.16
  4424.3  271.22    4449  270.92  4454.4  271.92  4533.6  268.77  4563.6   267.1
    4569  265.47  4588.3  263.62  4600.6  264.45  4654.2  260.91    4772  259.22
  4793.4  256.97  4859.2   254.9  4951.5  250.21  4981.5   250.6  4986.9  248.87
  5001.6  247.49  5025.5  249.73  5040.4  249.95  5091.1  250.68    5169  254.96
  5306.4  265.66  5384.6  269.73  5607.6  278.29  5760.5  285.43  5812.6  286.66
#Mann= 6 ,-1 , 0
  3946.4     .11       0  4859.2     .17       0  4981.5     .09       0
  5025.5     .17       0  5040.4     .11       0  5607.6     .17       0
Bank Sta=4981.5,5025.5
XS Rating Curve= 0 ,0
Exp/Cntr=0.3,0.1

Type RM Length L Ch R = 1 ,4680    ,546,546,546
BEGIN DESCRIPTION:
WELCH BRANCH 8.0
END DESCRIPTION:
XS GIS Cut Line= 2
       3758609.2     10229856.42      3757762.83     10228098.57
#Sta/Elev= 30
  4062.5  278.85  4120.8  278.09  4201.6  281.02    4330  277.44  4397.9  276.37
  4403.4  277.92  4443.1  276.25  4471.3  277.58  4488.4  276.55  4539.1  277.74
  4556.2  276.95  4584.4  278.88    4607  276.66  4645.6  275.85  4748.3  269.91
  4920.4  256.84  4980.1  250.39  4999.9  246.59  5005.6  246.59  5019.8  250.11
  5116.6  248.48  5178.2  248.05  5222.7  250.85  5296.9  256.02  5370.3   263.3
  5483.4  271.24  5551.3  277.65  5737.8  291.09  5833.9  291.18  6013.5  288.07
#Mann= 5 ,-1 , 0
  4062.5     .11       0  4920.4     .17       0  4980.1     .09       0
  5019.8     .17       0  5116.6     .11       0
Bank Sta=4980.1,5019.8
XS Rating Curve= 0 ,0
Exp/Cntr=0.3,0.1

Type RM Length L Ch R = 1 ,4134    ,512,512,512
BEGIN DESCRIPTION:
WELCH BRANCH 7.0
END DESCRIPTION:
XS GIS Cut Line= 3
      3758778.46     10229391.97      3758617.87     10228710.56
      3758140.43     10227942.31
#Sta/Elev= 30
  4398.8     272  4419.2  272.13  4440.8   270.2    4636  263.57  4666.8  260.99
  4725.9  258.64    4749  256.28  4863.2  248.59  4942.7  247.02  4975.1  247.88
  4995.6  245.59  5016.2  248.28  5037.7  247.59  5074.9  245.97  5077.2     245
  5157.1  247.47  5310.2  253.14  5337.7  256.81    5353  261.82  5368.4  263.32
  5374.3  263.31  5380.8  260.88  5498.6  260.11  5505.4  260.67  5511.2  262.82
  5584.5   265.6  5651.6  266.92  5910.7   276.9  5983.5  279.16  6003.4  278.74
#Mann= 3 , 0 , 0
  4398.8     .11       0  5037.7     .06       0  5157.1     .11       0
Bank Sta=5037.7,5157.1
XS Rating Curve= 0 ,0
Exp/Cntr=0.3,0.1

Type RM Length L Ch R = 1 ,3622    ,638,638,638
BEGIN DESCRIPTION:
WELCH BRANCH 6.0
END DESCRIPTION:
XS GIS Cut Line= 2
       3759420.8     10228983.98      3758426.91     10227968.39
#Sta/Elev= 30
  4533.8  274.55  4559.2  275.13  4665.2  268.71  4723.2  266.52  4778.3  264.17
  4799.6  259.59  4810.4  259.47  4827.9  259.94    4849  257.37  4898.6  254.78
  4969.4  246.27  4997.6  244.74  5003.7  245.31  5004.8  245.43  5011.8  246.93
  5040.1  245.55  5117.8  244.78  5185.6  243.28  5245.1  244.73  5315.8  245.96
  5407.7  251.62  5450.1   252.9  5520.8   258.2  5577.4  264.13  5655.3  269.27
  5740.2  271.67    5832  270.22  5881.4  271.34  5916.9  273.87  5954.8  273.58
#Mann= 7 ,-1 , 0
  4533.8     .17       0  4723.2     .11       0  4810.4     .17       0
  5003.7     .15       0  5004.8     .11       0  5117.8     .09       0
  5245.1     .11       0
Bank Sta=5117.8,5245.1
XS Rating Curve= 0 ,0
Exp/Cntr=0.3,0.1

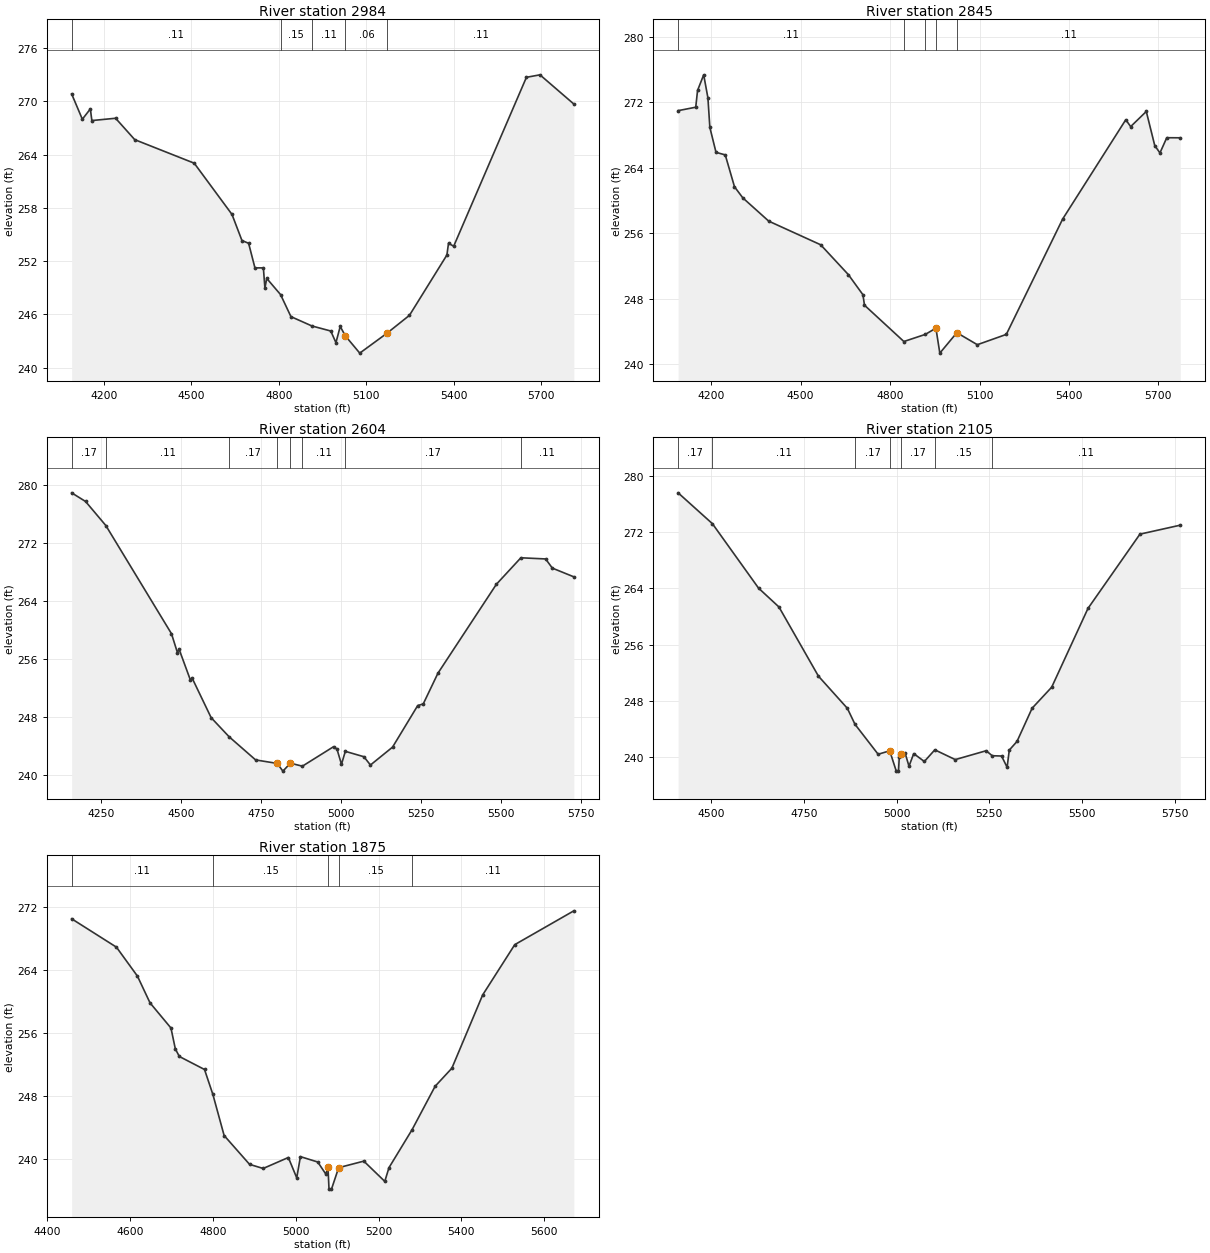
Type RM Length L Ch R = 1 ,2984    ,139,139,139
BEGIN DESCRIPTION:
WELCH BRANCH 5.0
END DESCRIPTION:
XS GIS Cut Line= 3
      3760293.21     10228393.72      3759415.29     10228149.31
      3758671.44     10227821.46
#Sta/Elev= 30
  4088.7  270.83  4125.4  267.98  4152.9  269.14  4158.1  267.83  4239.6  268.09
  4305.3  265.68  4509.5  263.03  4639.2  257.26  4673.4  254.32  4696.3  254.01
    4718  251.24    4747  251.24  4752.2  248.97  4758.6  250.05    4806  248.23
  4841.6  245.75  4913.5   244.7  4978.3  244.13  4996.1  242.82  5010.8  244.64
  5028.7  243.57  5077.9  241.64  5172.1   243.9  5248.6   245.9  5377.1  252.69
  5382.6  254.01  5400.4  253.68  5650.1   272.7  5696.6  272.98  5812.9  269.69
#Mann= 5 ,-1 , 0
  4088.7     .11       0    4806     .15       0  4913.5     .11       0
  5028.7     .06       0  5172.1     .11       0
Bank Sta=5028.7,5172.1
XS Rating Curve= 0 ,0
Exp/Cntr=0.3,0.1

Type RM Length L Ch R = 1 ,2845    ,241,241,241
BEGIN DESCRIPTION:
Mapping XS c5f2d04c
END DESCRIPTION:
XS GIS Cut Line= 3
      3760341.01     10228250.51      3759459.89      10228024.8
      3758756.76     10227699.28
#Sta/Elev= 30
    4089  270.98  4148.1   271.4  4154.2  273.45  4174.8  275.36  4188.9  272.55
  4195.5  268.92  4216.1  265.88  4247.1  265.57  4278.1  261.67  4306.1  260.31
  4392.9  257.47  4567.1  254.58    4660  250.93  4708.9  248.47  4714.1  247.19
  4846.2  242.75  4918.1  243.62  4953.7  244.38  4966.8  241.33  5023.9  243.83
  5092.6  242.36  5189.8  243.62  5378.7  257.72  5590.5  269.87  5606.9  269.03
  5659.3  270.88  5687.7  266.71  5705.1  265.81    5728  267.67  5773.4  267.66
#Mann= 5 ,-1 , 0
    4089     .11       0  4846.2     .17       0  4918.1     .11       0
  4953.7     .06       0  5023.9     .11       0
Bank Sta=4953.7,5023.9
XS Rating Curve= 0 ,0
Exp/Cntr=0.3,0.1

Type RM Length L Ch R = 1 ,2604    ,499,499,499
BEGIN DESCRIPTION:
WELCH BRANCH 4.0
END DESCRIPTION:
XS GIS Cut Line= 3
        3760380.     10228029.13      3759620.48     10227833.83
      3758873.98     10227590.78
#Sta/Elev= 30
  4158.5  278.86    4202  277.67  4265.4  274.36  4470.5  259.49    4489   256.9
  4494.2  257.36  4529.7  253.11  4534.9   253.4  4594.4  247.95  4650.4  245.33
  4733.4  242.14  4800.9  241.66  4818.6   240.6  4842.2  241.69  4879.5  241.28
    4977  243.96  4987.6  243.63  5001.7  241.54  5013.7  243.32  5071.7  242.58
  5092.2  241.44  5161.3   243.9    5240  249.62  5257.1  249.83  5303.1  254.06
  5485.8  266.29  5562.3  269.93  5639.6  269.77  5660.6  268.51  5727.8  267.31
#Mann= 8 ,-1 , 0
  4158.5     .17       0  4265.4     .11       0  4650.4     .17       0
  4800.9     .06       0  4842.2     .17       0  4879.5     .11       0
  5013.7     .17       0  5562.3     .11       0
Bank Sta=4800.9,4842.2
XS Rating Curve= 0 ,0
Exp/Cntr=0.3,0.1

Type RM Length L Ch R = 1 ,2105    ,230,230,230
BEGIN DESCRIPTION:
WELCH BRANCH 3.0
END DESCRIPTION:
XS GIS Cut Line= 2
      3760436.45     10227790.42      3759134.39     10227417.17
#Sta/Elev= 30
  4410.6   277.6  4503.1  273.21  4627.6  264.04  4682.6  261.36  4789.1  251.52
    4867  246.95  4887.8  244.66  4950.1  240.41  4981.3   240.9    4999  238.01
    5005  238.01  5007.2  240.09  5012.5  240.41  5022.9  240.57  5033.3  238.71
  5046.1   240.5  5074.7  239.38    5103  241.04  5158.1  239.65  5241.4  240.91
  5257.8   240.2    5283  240.16    5298  238.55  5303.8     241  5324.6  242.23
  5365.4  246.96  5418.2  249.95    5516  261.15  5656.2  271.72  5765.1     273
#Mann= 7 ,-1 , 0
  4410.6     .17       0  4503.1     .11       0  4887.8     .17       0
  4981.3     .09       0  5012.5     .17       0    5103     .15       0
  5257.8     .11       0
Bank Sta=4981.3,5012.5
XS Rating Curve= 0 ,0
Exp/Cntr=0.3,0.1

Type RM Length L Ch R = 1 ,1875    ,495,495,495
BEGIN DESCRIPTION:
Mapping XS 108670bb
END DESCRIPTION:
XS GIS Cut Line= 2
      3760414.75     10227525.67      3759216.87     10227330.36
#Sta/Elev= 30
  4458.4  270.51  4566.7  266.91  4617.4  263.24  4647.8  259.85  4698.4  256.66
    4709  254.01  4718.7  253.05  4779.5   251.4  4799.7  248.24  4826.9  243.03
  4888.4  239.37  4921.3  238.85  4982.1  240.24  5002.4  237.66  5011.3  240.35
  5053.1  239.67  5072.8  238.13  5077.9     239  5080.4  236.23  5086.4  236.23
  5103.7  238.95  5164.5  239.78  5215.2  237.21  5225.3  238.95  5281.3  243.78
  5336.8  249.27  5377.3  251.56  5451.7  260.85  5529.3  267.23  5672.1  271.52
#Mann= 5 ,-1 , 0
  4458.4     .11       0  4799.7     .15       0  5077.9     .09       0
  5103.7     .15       0  5281.3     .11       0
Bank Sta=5077.9,5103.7
XS Rating Curve= 0 ,0
Exp/Cntr=0.3,0.1