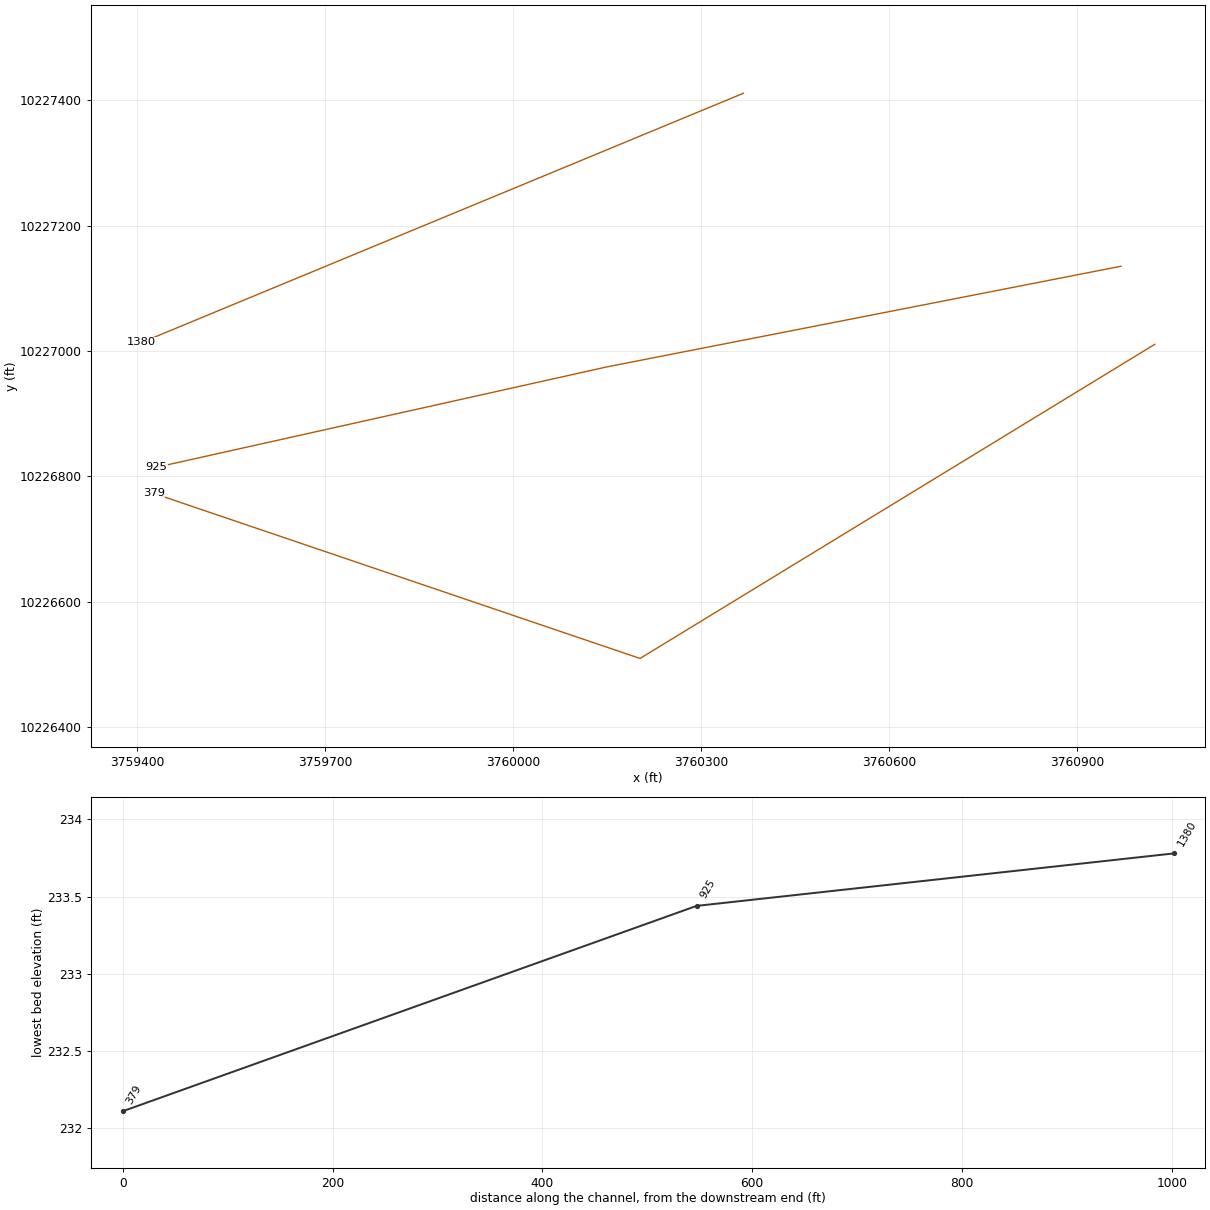
HEC-RAS study WELCH BRANCH.prj: WELCH BRANCH Base Level Engineering

--- WELCH BRANCH.g01 (geometry) --- (continued)

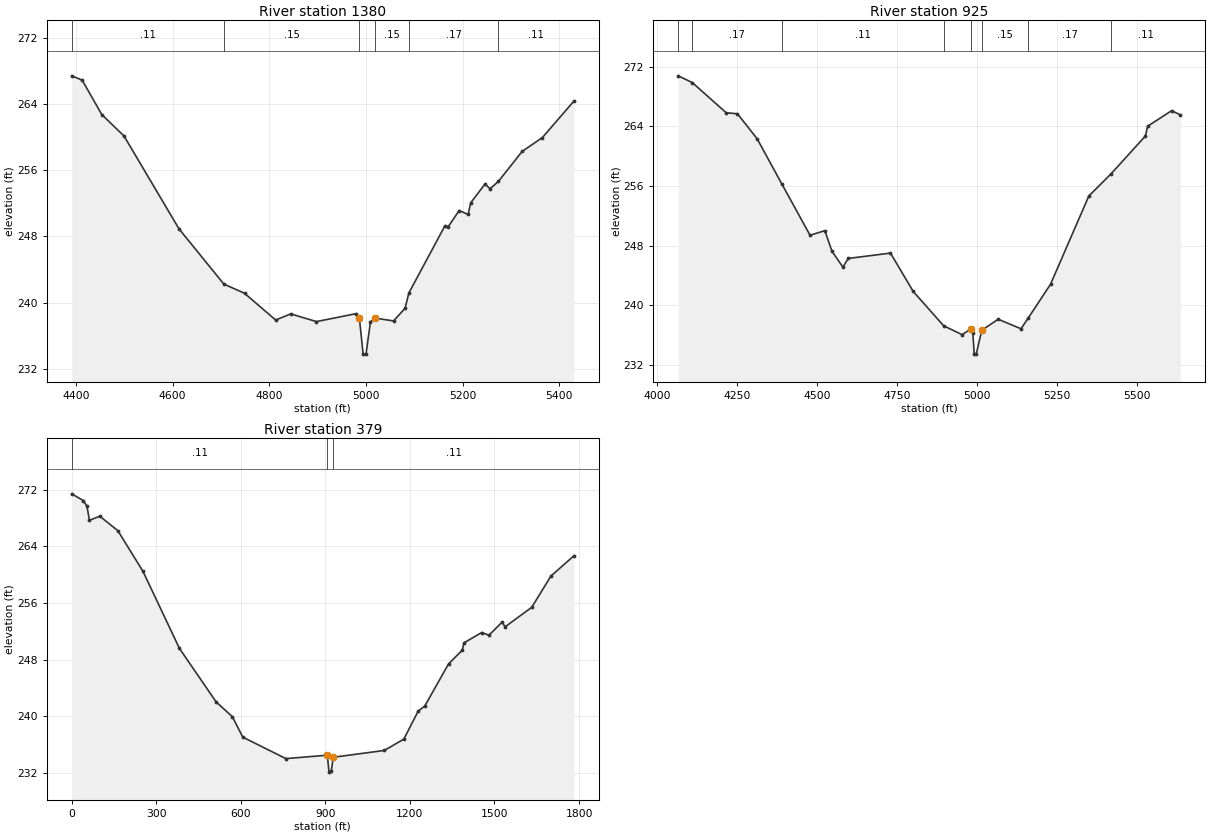
Type RM Length L Ch R = 1 ,1380    ,455,455,455
BEGIN DESCRIPTION:
WELCH BRANCH 2.0
END DESCRIPTION:
XS GIS Cut Line= 2
      3760367.87     10227411.08      3759407.83     10227013.52
#Sta/Elev= 30
  4391.1  267.39  4412.8  266.87  4453.6   262.7  4499.4  260.13  4613.1  248.92
    4706  242.24  4748.8  241.13  4813.2   237.9  4844.4  238.64  4897.6  237.71
  4980.1  238.67  4986.4  238.17  4994.2  233.78  5000.2  233.78  5009.4  237.68
  5018.9  238.13  5057.2  237.79  5081.1  239.33  5088.8  241.16  5163.6  249.29
  5170.4  249.18  5192.9  251.12  5211.4  250.65  5216.8  252.05  5246.2  254.31
    5257  253.76    5274  254.63  5323.2  258.26  5365.2  259.94  5430.2  264.33
#Mann= 6 ,-1 , 0
  4391.1     .11       0    4706     .15       0  4986.4     .09       0
  5018.9     .15       0  5088.8     .17       0    5274     .11       0
Bank Sta=4986.4,5018.9
XS Rating Curve= 0 ,0
Exp/Cntr=0.3,0.1

Type RM Length L Ch R = 1 ,925     ,547,547,547
BEGIN DESCRIPTION:
WELCH BRANCH 1.0
END DESCRIPTION:
XS GIS Cut Line= 3
      3760970.32     10227135.05      3760149.99     10226974.45
      3759431.14     10226814.23
#Sta/Elev= 30
  4064.6  270.76  4108.9  269.86  4215.1  265.81  4250.5  265.67  4311.7  262.34
    4390  256.21  4477.7  249.38  4524.1     250    4546  247.26  4580.7   245.1
    4597  246.27  4729.5  246.99  4800.8  241.84  4896.3  237.23  4953.9  236.05
  4982.3  236.85  4987.4  236.24  4991.9  233.44    4998  233.44  5015.4  236.64
  5066.6  238.12  5138.3  236.84  5161.6  238.33  5230.6   242.8  5350.5  254.64
  5419.6  257.59  5527.7  262.69  5534.7     264  5609.6  266.08    5637  265.53
#Mann= 8 ,-1 , 0
  4064.6     .11       0  4108.9     .17       0    4390     .11       0
  4896.3     .15       0  4982.3     .08       0  5015.4     .15       0
  5161.6     .17       0  5419.6     .11       0
Bank Sta=4982.3,5015.4
XS Rating Curve= 0 ,0
Exp/Cntr=0.3,0.1

Type RM Length L Ch R = 1 ,379     ,0,0,0
XS GIS Cut Line= 3
      3761024.21     10227010.44      3760202.84     10226509.18
      3759426.98     10226772.59
#Sta/Elev= 30
       0  271.41    41.8  270.45    54.3  269.65    63.1  267.67    99.8  268.25
   163.8  266.21   252.8  260.48   382.3  249.59   512.3  242.04   570.4  239.93
   607.1  237.05   760.1  234.02   907.1   234.5     913  232.11   921.2  232.33
   928.4  234.21  1109.1  235.17  1178.7  236.78  1229.4  240.73  1252.6  241.43
  1337.1  247.39  1386.4  249.36  1391.6  250.36  1454.4  251.82  1480.5  251.45
  1527.2  253.29  1537.8  252.63  1632.2  255.38  1700.3   259.8  1781.6  262.65
#Mann= 3 , 0 , 0
       0     .11       0   907.1     .06       0   928.4     .11       0
Bank Sta=907.1,928.4
XS Rating Curve= 0 ,0
Exp/Cntr=0.3,0.1

Chan Stop Cuts=-1
Use User Specified Reach Order=0
Composite Channel Slope=5