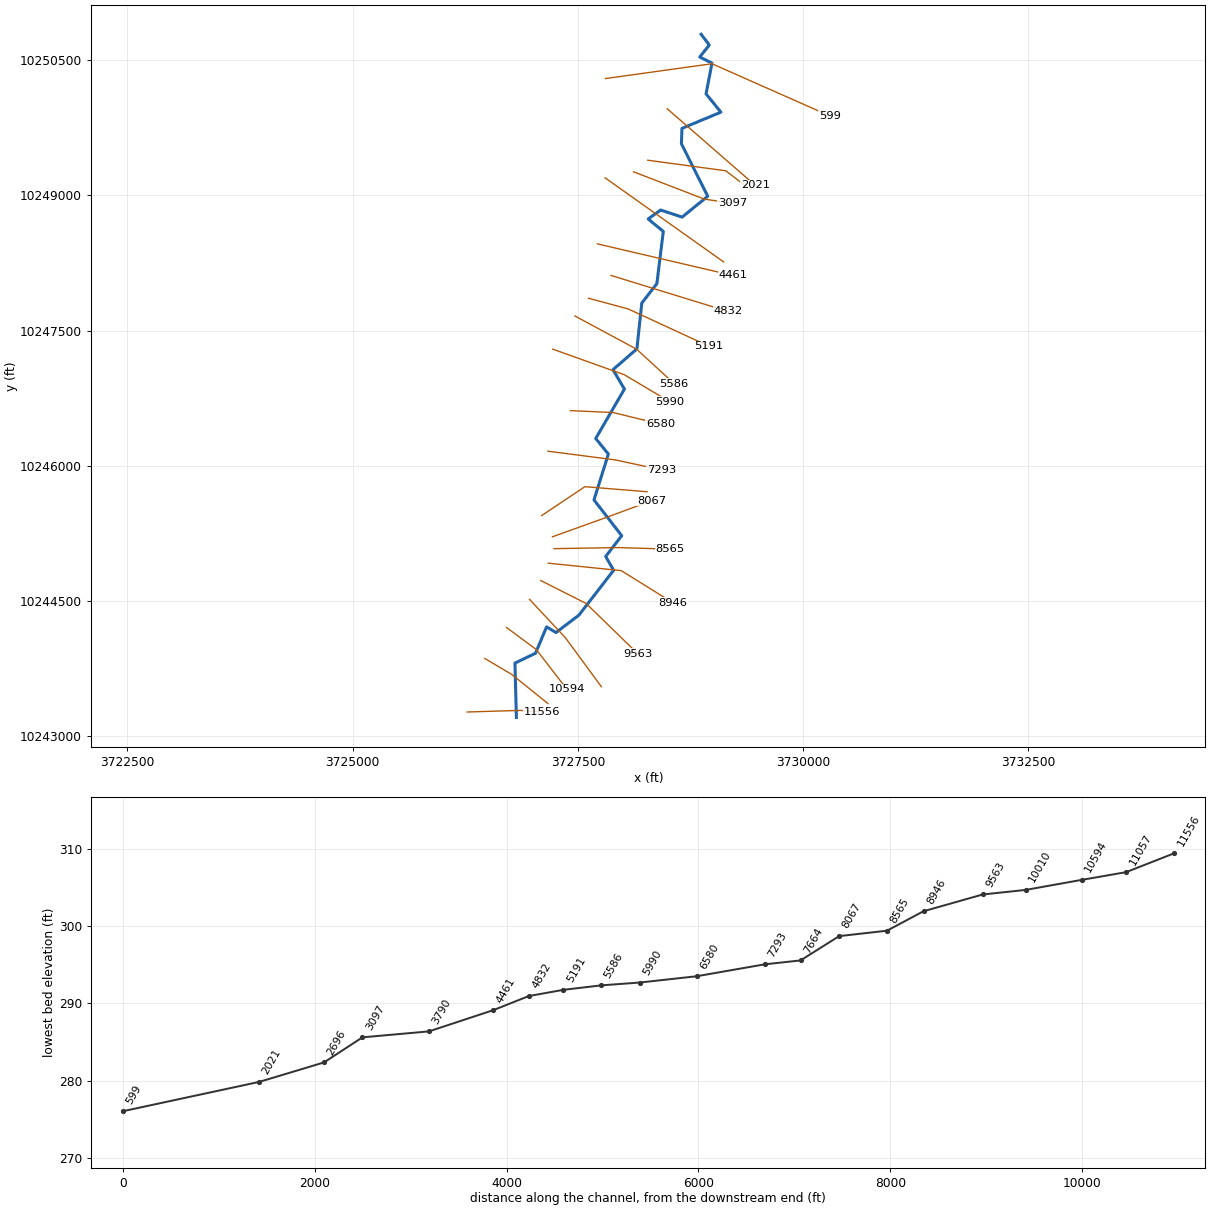
--- WEST CEDAR CREEK.prj (project) ---

Proj Title=WEST CEDAR CREEK Base Level Engineering
Current Plan=p01
Default Exp/Contr=0.3,0.1
English Units
Geom File=g01
Flow File=f01
Plan File=p01
Y Axis Title=Elevation
X Axis Title(PF)=Main Channel Distance
X Axis Title(XS)=Station
BEGIN DESCRIPTION:
WEST CEDAR CREEK
END DESCRIPTION:
DSS Export Rating Curves= 0
DSS Export Rating Curve Sorted= 0
DSS Export Volume Flow Curves= 0
DXF OffsetX= 0
DXF OffsetY= 0
DXF ScaleX= 1
DXF ScaleY= 10

--- WEST CEDAR CREEK.p01 (plan) ---

Plan Title=Multiple Run
Program Version=4.10
Short Identifier=Multiple
Geom File=g01
Flow File=f01
Subcritical Flow
K Sum by GR= 0
Std Step Tol= 0.01
Critical Tol= 0.01
Num of Std Step Trials= 20
Max Error Tol= 0.3
Flow Tol Ratio= 0.001
Split Flow NTrial= 30
Split Flow Tol= 0.02
Split Flow Ratio= 0.02
Log Output Level= 0
Friction Slope Method= 1
Unsteady Friction Slope Method= 2
Unsteady Bridges Friction Slope Method= 1
Parabolic Critical Depth
Global Vel Dist= 1 , 1 , 1
Global Log Level= 0
CheckData=True
Encroach Param=-1 ,0,0, 0
BEGIN DESCRIPTION:
Multiple Run
END DESCRIPTION:
Computation Interval=1HOUR
Output Interval=1HOUR
Run HTab= 0
Run UNet= 0
Run PostProcess= 0
Run WQNet= 0
UNET Theta= 1
UNET Theta Warmup= 1
UNET ZTol= 0.02
UNET ZSATol= 0.05
UNET MxIter= 20
UNET MaxInSteps= 0
UNET DtIC= 0
UNET DtMin= 0
UNET MaxCRTS= 20
UNET WFStab= 2
UNET SFStab= 1
UNET WFX= 1
UNET SFX= 1
UNET DSS MLevel= 4
UNET DZMax Abort= 100
UNET Convert EG Bridges= 0
UNET Use Existing IB Tables=-1
UNET Froude Reduction=False
UNET Froude Limit= 1
UNET Froude Power= 10
UNET Time Slicing=0,0, 5
UNET Junction Losses=0
Instantaneous Interval=1HOUR
Write IC File= 0
Write IC File at Sim End=0
Echo Input=False
Echo Parameters=False
Echo Output=False
Write Detailed= 0
WQ AD Non Conservative
WQ ULTIMATE=-1
WQ Max Comp Step=1HOUR
WQ Output Interval=15MIN
WQ Output Selected Increments= 0
WQ Output face flow=0
WQ Output face velocity=0
WQ Output face area=0
WQ Output face dispersion=0
WQ Output cell volume=0
WQ Output cell surface area=0
WQ Output cell continuity=0
WQ Output cumulative cell continuity=0
WQ Output face conc=0
WQ Output face dconc_dx=0
WQ Output face courant=0
WQ Output face peclet=0
WQ Output face adv mass=0
WQ Output face disp mass=0
WQ Output cell mass=0
WQ Output cell source sink temp=0
WQ Output cell source sink nsm=0
WQ Output MaxMinRange=-1
WQ Daily Max Min Mean=-1
WQ Daily Range=0
WQ Daily Time=0
WQ Create Restart=0
WQ Fixed Restart=0
WQ System Summary=0
WQ Use Fixed Temperature=0
Sorting and Armoring Iterations= 10
XS Update Threshold= 0.02
Hydraulics Update Threshold= 0.02
Energy Slope Method= 1
Volume Change Method= 0
XS Weighting Method= 0
Number of US Weighted Cross Sections= 1
Number of DS Weighted Cross Sections= 1
Upstream XS Weight=0.25
Main XS Weight=0.5
Downstream XS Weight=0.25
Number of DS XS's Weighted with US Boundary= 1
Upstream Boundary Weight= 1
Weight of XSs Associated with US Boundary= 0
Number of US XS's Weighted with DS Boundary= 1
Downstream Boundary Weight= 0.5
Weight of XSs Associated with DS Boundary= 0.5
Sediment Output Level= 4
Mass or Volume Output= 0
Output Increment Type= 1
Profile and TS Output Increment= 10
XS Output Flag= 0
XS Output Increment= 10
Disregard all LS=0
Disregard all Conn=0
Disregard all Breaches=0
Disregard all Pumps=0

--- WEST CEDAR CREEK.f01 (steady flow) ---

Flow Title=Multiple
Program Version=4.10
Number of Profiles= 7
Profile Names=10-year,25-year,50-year,1pct_min,100-year,1pct_plu,500-year
River Rch & RM=WEST CEDAR CREEK,Reach-1         ,11556
     552     746    1006     447    1351    4080    2515
River Rch & RM=WEST CEDAR CREEK,Reach-1         ,11057
     672     914    1239     552    1668    5037    3125
River Rch & RM=WEST CEDAR CREEK,Reach-1         ,5990
     794    1085    1477     660    1992    6016    3750
Boundary for River Rch & Prof#=WEST CEDAR CREEK,Reach-1         , 1
Up Type= 0
Dn Type= 3
Dn Slope=0.003
Boundary for River Rch & Prof#=WEST CEDAR CREEK,Reach-1         , 2
Up Type= 0
Dn Type= 3
Dn Slope=0.003
Boundary for River Rch & Prof#=WEST CEDAR CREEK,Reach-1         , 3
Up Type= 0
Dn Type= 3
Dn Slope=0.003
Boundary for River Rch & Prof#=WEST CEDAR CREEK,Reach-1         , 4
Up Type= 0
Dn Type= 3
Dn Slope=0.003
Boundary for River Rch & Prof#=WEST CEDAR CREEK,Reach-1         , 5
Up Type= 0
Dn Type= 3
Dn Slope=0.003
Boundary for River Rch & Prof#=WEST CEDAR CREEK,Reach-1         , 6
Up Type= 0
Dn Type= 3
Dn Slope=0.003
Boundary for River Rch & Prof#=WEST CEDAR CREEK,Reach-1         , 7
Up Type= 0
Dn Type= 3
Dn Slope=0.003
DSS Import GetInterval= 0
DSS Import GetPeak= 0
DSS Import FillOption= 0

--- WEST CEDAR CREEK.g01 (geometry) ---

Geom Title=Existing Conditions
Program Version=4.10

River Reach=WEST CEDAR CREEK,Reach-1
Reach XY= 30
      3726818.23     10243206.84      3726802.41     10243809.98
      3727030.28     10243918.62       3727153.5     10244211.81
      3727257.46      10244148.8      3727511.65     10244341.54
      3727897.52     10244840.12      3727809.02     10244992.67
      3727986.89      10245223.5      3727679.33     10245620.23
      3727838.74     10246129.28      3727698.59     10246301.77
       3728017.2     10246850.18      3727889.78     10247065.31
      3728155.53     10247296.04      3728209.66     10247804.37
      3728377.13     10248020.25      3728448.09     10248599.69
      3728280.66     10248737.58      3728418.67     10248836.91
      3728656.72      10248758.1      3728941.27     10248989.31
       3728649.4     10249571.69      3728655.21     10249742.63
      3729087.79     10249922.82      3728922.72     10250125.32
      3728988.33     10250466.97      3728852.73     10250534.62
      3728958.72     10250667.77      3728868.23     10250786.84

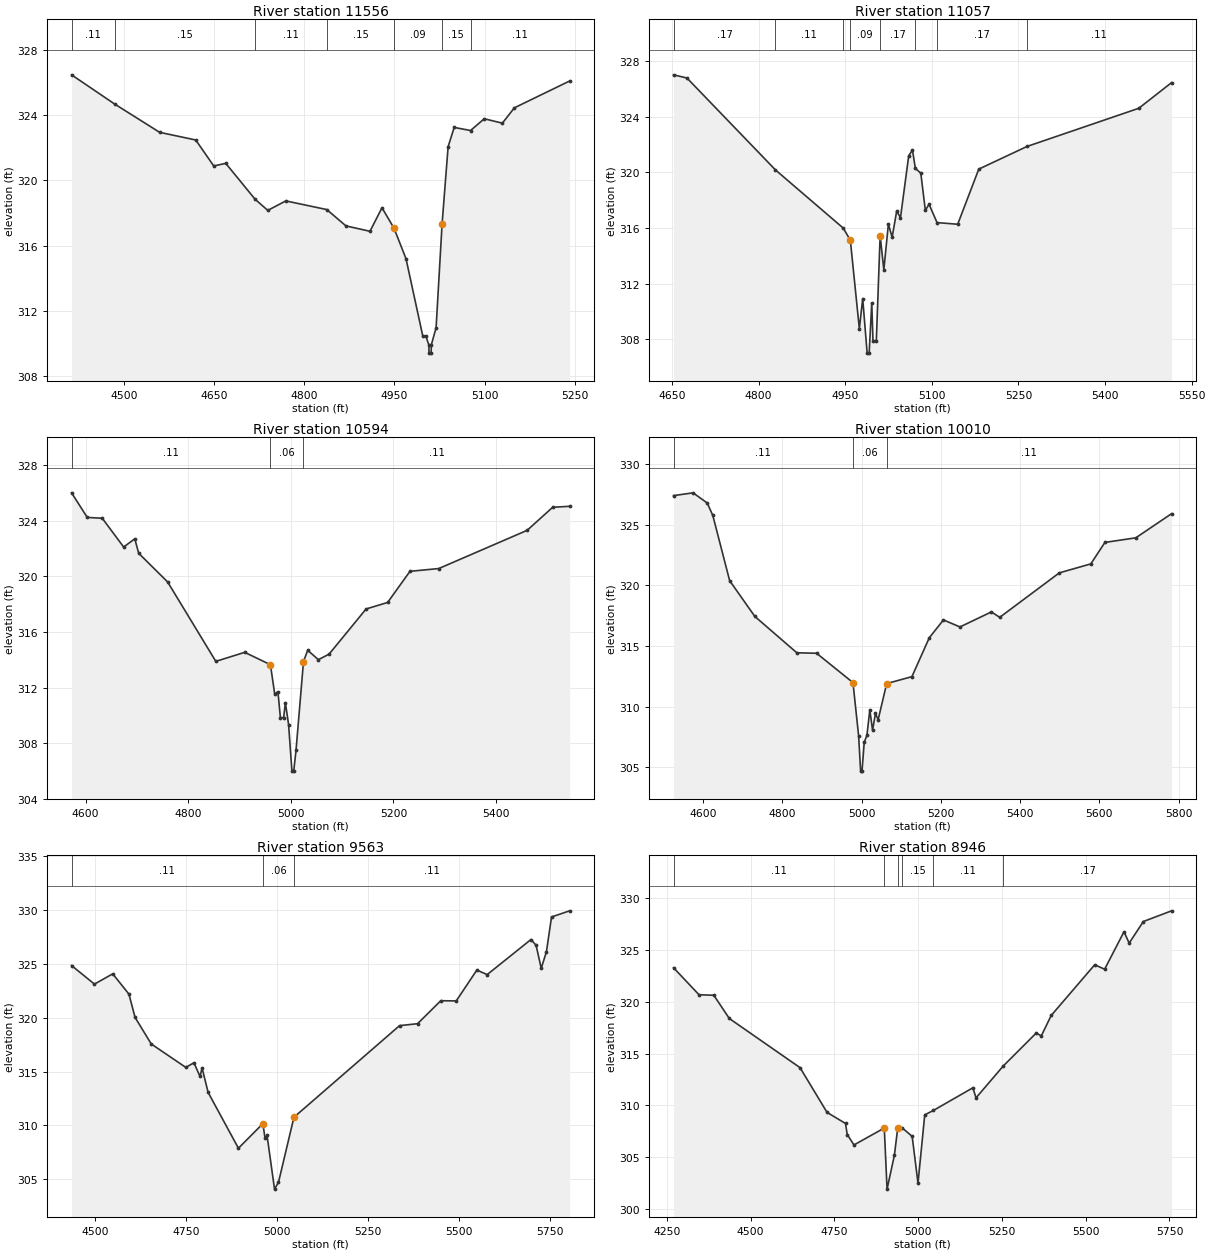
Type RM Length L Ch R = 1 ,11556   ,499,499,499
BEGIN DESCRIPTION:
WEST CEDAR CREEK 21.0
END DESCRIPTION:
XS GIS Cut Line= 3
      3726271.27     10243267.12      3726858.51      10243284.8
      3727099.46     10243267.12
#Sta/Elev= 30
  4412.5  326.46  4484.3  324.67  4559.1  322.94  4619.2  322.47  4649.2  320.88
  4669.2  321.04  4718.1  318.84  4739.2  318.16  4769.2  318.74  4837.4  318.21
  4869.3  317.21  4909.3  316.88  4929.3  318.32  4949.3  317.07  4969.3   315.2
  4997.2  310.47  5002.2  310.47  5007.4  309.92  5007.6  309.42  5011.1  309.42
  5011.4  309.92  5019.4  310.98  5029.4  317.35  5039.4  322.06  5049.5  323.24
  5076.7  323.05  5099.6  323.77  5129.7   323.5  5149.7  324.44  5241.6  326.08
#Mann= 7 ,-1 , 0
  4412.5     .11       0  4484.3     .15       0  4718.1     .11       0
  4837.4     .15       0  4949.3     .09       0  5029.4     .15       0
  5076.7     .11       0
Bank Sta=4949.3,5029.4
XS Rating Curve= 0 ,0
Exp/Cntr=0.3,0.1

Type RM Length L Ch R = 1 ,11057   ,463,463,463
BEGIN DESCRIPTION:
WEST CEDAR CREEK 20.0
END DESCRIPTION:
XS GIS Cut Line= 3
      3726467.89     10243861.05      3726766.61     10243684.28
      3727167.83     10243361.09
#Sta/Elev= 30
  4652.9  327.03  4676.1   326.8  4829.4  320.18  4946.8  315.99    4959  315.12
  4974.6  308.75  4980.4  310.92  4988.1  306.99  4991.6  306.99  4996.1  310.61
  4998.2  307.88    5004  307.88  5010.6  315.45    5017  312.99  5024.9  316.28
  5031.4  315.33  5039.3  317.23  5045.8  316.74  5060.1  321.21  5066.6  321.61
  5071.6  320.29    5081  319.95  5088.9  317.27  5095.3  317.71  5109.1  316.39
  5144.9  316.27  5181.4  320.24  5264.8  321.87  5458.4  324.62  5515.2  326.47
#Mann= 8 ,-1 , 0
  4652.9     .17       0  4829.4     .11       0  4946.8     .17       0
    4959     .09       0  5010.6     .17       0  5071.6     .15       0
  5109.1     .17       0  5264.8     .11       0
#XS Ineff= 1 ,-1
  5066.6    5300  321.61
Permanent Ineff=
       F
Bank Sta=4959,5010.6
XS Rating Curve= 0 ,0
Exp/Cntr=0.3,0.1

Type RM Length L Ch R = 1 ,10594   ,584,584,584
BEGIN DESCRIPTION:
WEST CEDAR CREEK 19.0
END DESCRIPTION:
XS GIS Cut Line= 3
      3726708.79     10244204.65      3727038.81     10243960.43
       3727380.7     10243517.11
#Sta/Elev= 30
  4572.7  326.02  4603.3  324.25  4632.5  324.19  4674.2  322.12  4695.9  322.71
  4703.5  321.67  4759.8  319.61  4853.8  313.89  4910.1  314.54  4960.2  313.65
  4968.6  311.52  4974.8  311.71  4979.6  309.84    4986  309.84  4989.3  310.92
  4995.6  309.34  5002.1  305.99  5005.6  305.99  5010.1  307.49  5024.6  313.87
  5032.8  314.69  5053.6  314.01  5074.5  314.41  5146.6  317.66  5188.6  318.13
  5232.1  320.37  5288.2  320.57  5460.4  323.32  5510.2  324.98  5543.1  325.05
#Mann= 3 , 0 , 0
  4572.7     .11       0  4960.2     .06       0  5024.6     .11       0
Bank Sta=4960.2,5024.6
XS Rating Curve= 0 ,0
Exp/Cntr=0.3,0.1

Type RM Length L Ch R = 1 ,10010   ,447,447,447
BEGIN DESCRIPTION:
WEST CEDAR CREEK 18.0
END DESCRIPTION:
XS GIS Cut Line= 3
      3726964.03     10244517.12      3727363.47     10244089.16
      3727760.89     10243548.39
#Sta/Elev= 30
  4525.7  327.41    4575  327.64  4610.6   326.8  4624.7  325.78  4667.2   320.4
  4730.7  317.45  4836.7  314.45  4886.6  314.41  4978.4  311.99  4992.6  307.61
  4997.7  304.69  5001.2  304.69  5006.8  307.08  5013.6  307.64  5020.9  309.74
  5027.8  308.06  5035.1  309.45  5041.9  308.93  5063.4  311.91  5127.1  312.48
  5170.8  315.68  5206.6  317.16  5248.3  316.58  5327.7  317.82  5348.6  317.37
    5499  321.04  5578.5  321.78    5614  323.55    5692  323.93  5782.2  325.92
#Mann= 3 , 0 , 0
  4525.7     .11       0  4978.4     .06       0  5063.4     .11       0
Bank Sta=4978.4,5063.4
XS Rating Curve= 0 ,0
Exp/Cntr=0.3,0.1

Type RM Length L Ch R = 1 ,9563    ,617,617,617
BEGIN DESCRIPTION:
WEST CEDAR CREEK 17.0
END DESCRIPTION:
XS GIS Cut Line= 3
      3727089.01     10244725.46      3727592.83     10244471.06
      3728167.82      10243911.1
#Sta/Elev= 30
  4435.6  324.82  4498.4   323.1  4548.6  324.05  4593.1  322.17  4609.8  320.02
  4654.4  317.55  4749.2  315.38  4771.5  315.81  4788.2  314.54  4793.8  315.33
  4810.5  313.06  4893.6  307.89  4960.8  310.17  4966.6  308.82  4972.2  309.08
  4992.7   304.1  5003.6  304.73    5046  310.76  5335.9  319.25  5385.3  319.43
  5449.1  321.56  5491.5  321.54  5548.1   324.4  5576.4  323.98  5696.6  327.23
  5710.7   326.7  5724.8  324.56    5739  326.09  5753.1  329.32  5802.6  329.89
#Mann= 3 , 0 , 0
  4435.6     .11       0  4960.8     .06       0    5046     .11       0
Bank Sta=4960.8,5046
XS Rating Curve= 0 ,0
Exp/Cntr=0.3,0.1

Type RM Length L Ch R = 1 ,8946    ,381,381,381
BEGIN DESCRIPTION:
WEST CEDAR CREEK 16.0
END DESCRIPTION:
XS GIS Cut Line= 3
      3727172.36     10244918.16      3727982.27     10244835.46
      3728552.59     10244480.65
#Sta/Elev= 30
  4270.4  323.27  4346.3  320.67  4390.5  320.62  4436.8  318.38  4647.8  313.64
  4728.3  309.33  4783.4  308.26  4788.6  307.19  4808.7  306.19  4899.1  307.82
  4907.4  301.93  4929.3   305.2  4939.4  307.87  4951.1  307.87  4982.3  307.02
  4999.7   302.5  5019.8  309.09  5045.9  309.52  5163.4   311.7  5172.8  310.73
  5254.3  313.81  5352.2  316.97  5367.6  316.71  5397.3  318.68  5526.9  323.56
  5556.5  323.13  5614.3  326.74  5629.7  325.65  5672.1  327.73  5756.2  328.76
#Mann= 6 ,-1 , 0
  4270.4     .11       0  4899.1     .09       0  4939.4     .11       0
  4951.1     .15       0  5045.9     .11       0  5254.3     .17       0
Bank Sta=4899.1,4939.4
XS Rating Curve= 0 ,0
Exp/Cntr=0.3,0.1

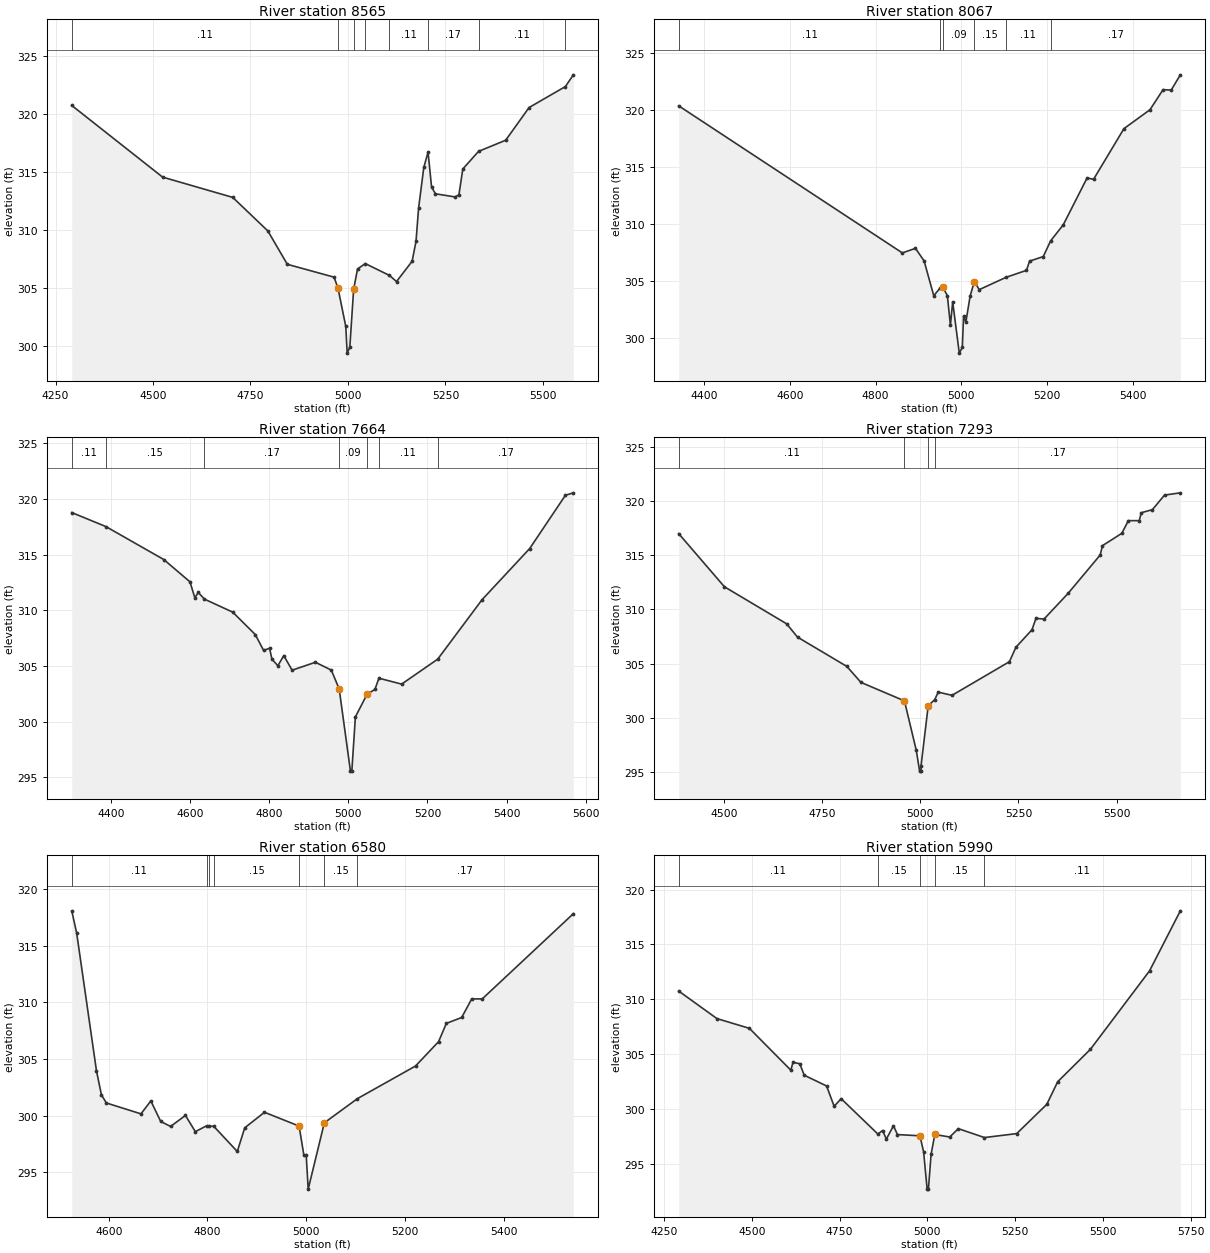
Type RM Length L Ch R = 1 ,8565    ,498,498,498
BEGIN DESCRIPTION:
WEST CEDAR CREEK 15.0
END DESCRIPTION:
XS GIS Cut Line= 3
       3727234.9     10245079.62       3727943.3     10245091.46
      3728521.35     10245074.41
#Sta/Elev= 30
  4291.5  320.77  4524.5  314.59  4704.5  312.84  4794.5  309.95  4844.5  307.07
  4964.5  305.96  4974.5  305.01  4994.5  301.71    4998  299.41  5004.8  299.91
  5014.6   304.9  5024.6  306.67  5044.6  307.13  5106.6  306.11  5124.6  305.58
  5164.6  307.33  5174.6  309.04  5181.3  311.93  5194.6  315.42  5205.5  316.74
  5214.6  313.72  5224.6  313.15  5274.7  312.88  5284.7  313.06  5294.7  315.29
  5335.1  316.81  5404.7  317.77  5464.7  320.59  5557.9   322.4  5578.3  323.41
#Mann= 8 ,-1 , 0
  4291.5     .11       0  4974.5     .06       0  5014.6     .11       0
  5044.6     .15       0  5106.6     .11       0  5205.5     .17       0
  5335.1     .11       0  5557.9     .17       0
Bank Sta=4974.5,5014.6
XS Rating Curve= 0 ,0
Exp/Cntr=0.3,0.1

Type RM Length L Ch R = 1 ,8067    ,403,403,403
BEGIN DESCRIPTION:
WEST CEDAR CREEK 14.0
END DESCRIPTION:
XS GIS Cut Line= 3
      3727217.85     10245211.07      3727838.41     10245434.04
      3728317.87     10245611.08
#Sta/Elev= 30
  4340.6   320.4  4862.4   307.5  4893.1   307.9  4913.2   306.8  4935.7  303.75
  4951.2  304.44  4956.9  304.52  4967.5  303.74  4974.6  301.16  4979.9  303.21
  4995.3  298.71  5002.4  299.21  5005.3  301.96  5010.6  301.43  5020.7  303.73
  5030.4  304.98    5042  304.28  5104.5  305.36  5152.1  305.97  5159.3  306.78
  5191.3  307.18  5208.3  308.55    5238  309.97  5293.6  314.08  5308.5  313.95
  5379.5   318.4  5440.3  320.06  5470.8  321.82  5489.8  321.78  5511.1  323.12
#Mann= 6 ,-1 , 0
  4340.6     .11       0  4951.2     .15       0  4956.9     .09       0
  5030.4     .15       0  5104.5     .11       0  5208.3     .17       0
Bank Sta=4956.9,5030.4
XS Rating Curve= 0 ,0
Exp/Cntr=0.3,0.1

Type RM Length L Ch R = 1 ,7664    ,371,371,371
BEGIN DESCRIPTION:
WEST CEDAR CREEK 13.0
END DESCRIPTION:
XS GIS Cut Line= 3
      3727099.16     10245446.79      3727578.35     10245767.12
      3728267.88     10245711.07
#Sta/Elev= 30
  4300.8  318.77  4387.2  317.51  4533.6  314.55  4599.7  312.55    4612  311.12
  4620.7   311.6  4636.2     311  4707.8  309.83  4764.8  307.82  4785.9  306.39
  4800.9  306.59  4806.9  305.61  4821.9  305.02  4836.9  305.93  4857.9  304.62
  4916.8  305.33    4957  304.63    4977  302.93  5005.4  295.56  5008.9  295.56
  5017.9  300.43  5047.3  302.45  5067.3   302.9  5077.4   303.9  5134.8  303.37
    5226  305.61  5338.2  310.95  5458.6  315.54  5548.9  320.32    5569  320.54
#Mann= 7 ,-1 , 0
  4300.8     .11       0  4387.2     .15       0  4636.2     .17       0
    4977     .09       0  5047.3     .17       0  5077.4     .11       0
    5226     .17       0
Bank Sta=4977,5047.3
XS Rating Curve= 0 ,0
Exp/Cntr=0.3,0.1

Type RM Length L Ch R = 1 ,7293    ,713,713,713
BEGIN DESCRIPTION:
WEST CEDAR CREEK 12.0
END DESCRIPTION:
XS GIS Cut Line= 3
      3727167.84     10246161.07      3727916.89       10246064.
      3728427.29     10245954.63
#Sta/Elev= 30
  4384.9     317  4501.3  312.09  4659.7  308.67  4687.4  307.44  4813.2  304.73
  4848.8  303.26  4959.7  301.55  4989.9  296.97  4998.3  295.06  5001.8  295.06
    5002  295.56  5020.2   301.1  5036.7  301.66  5045.8  302.36  5080.7  302.06
    5227  305.17  5243.5   306.5  5284.4  308.12  5294.6  309.17  5315.1  309.11
  5376.4  311.48  5458.2  315.03  5463.9  315.89  5513.3  317.03  5529.8   318.2
  5557.6   318.2  5562.7  318.93  5591.2  319.22  5621.9  320.56  5662.2  320.77
#Mann= 4 ,-1 , 0
  4384.9     .11       0  4959.7     .07       0  5020.2     .11       0
  5036.7     .17       0
Bank Sta=4959.7,5020.2
XS Rating Curve= 0 ,0
Exp/Cntr=0.3,0.1

Type RM Length L Ch R = 1 ,6580    ,590,590,590
BEGIN DESCRIPTION:
WEST CEDAR CREEK 11.0
END DESCRIPTION:
XS GIS Cut Line= 3
      3727417.82     10246611.07      3727892.25     10246589.82
      3728417.81     10246461.08
#Sta/Elev= 30
  4525.1  318.06  4535.1  316.09  4575.2  303.94  4585.2  301.83  4595.2  301.11
  4665.3  300.15  4685.3  301.29  4705.3  299.48  4725.3  299.04  4755.4  300.01
  4775.4  298.58  4798.4   299.1  4802.9  299.09    4813  299.04  4860.4  296.83
  4875.5  298.92  4915.5  300.29  4985.6  299.07  4995.3  296.49    5000  296.49
    5004  293.51  5036.7  299.36  5103.6  301.49  5221.4  304.37  5268.1  306.52
  5283.8  308.13  5314.9  308.65  5335.2  310.29  5356.5  310.29  5541.1  317.81
#Mann= 7 ,-1 , 0
  4525.1     .11       0  4798.4     .15       0  4802.9     .11       0
    4813     .15       0  4985.6     .09       0  5036.7     .15       0
  5103.6     .17       0
#XS Ineff= 1 ,-1
    4590  4685.3  301.29
Permanent Ineff=
       F
Bank Sta=4985.6,5036.7
XS Rating Curve= 0 ,0
Exp/Cntr=0.3,0.1

Type RM Length L Ch R = 1 ,5990    ,404,404,404
BEGIN DESCRIPTION:
WEST CEDAR CREEK 10.0
END DESCRIPTION:
XS GIS Cut Line= 3
      3727221.63     10247293.15      3728015.85     10247009.31
      3728517.83     10246711.09
#Sta/Elev= 30
  4292.3  310.75  4401.1  308.24  4493.5  307.35  4611.3  303.54  4617.5  304.25
  4636.8  304.13  4649.4  303.08  4713.1   302.1  4734.5  300.25  4754.6  300.94
    4859  297.72  4872.4  298.04  4883.1  297.26  4903.3  298.47  4914.8  297.67
  4978.6  297.56  4989.2  296.09  4999.1   292.7  5002.8   292.7  5010.4  295.87
    5021  297.68  5063.5  297.45    5088  298.21  5162.3   297.4    5254  297.76
  5339.7  300.43  5370.7  302.49  5463.7  305.44    5632  312.59  5719.6  318.06
#Mann= 5 ,-1 , 0
  4292.3     .11       0    4859     .15       0  4978.6     .09       0
    5021     .15       0  5162.3     .11       0
Bank Sta=4978.6,5021
XS Rating Curve= 0 ,0
Exp/Cntr=0.3,0.1

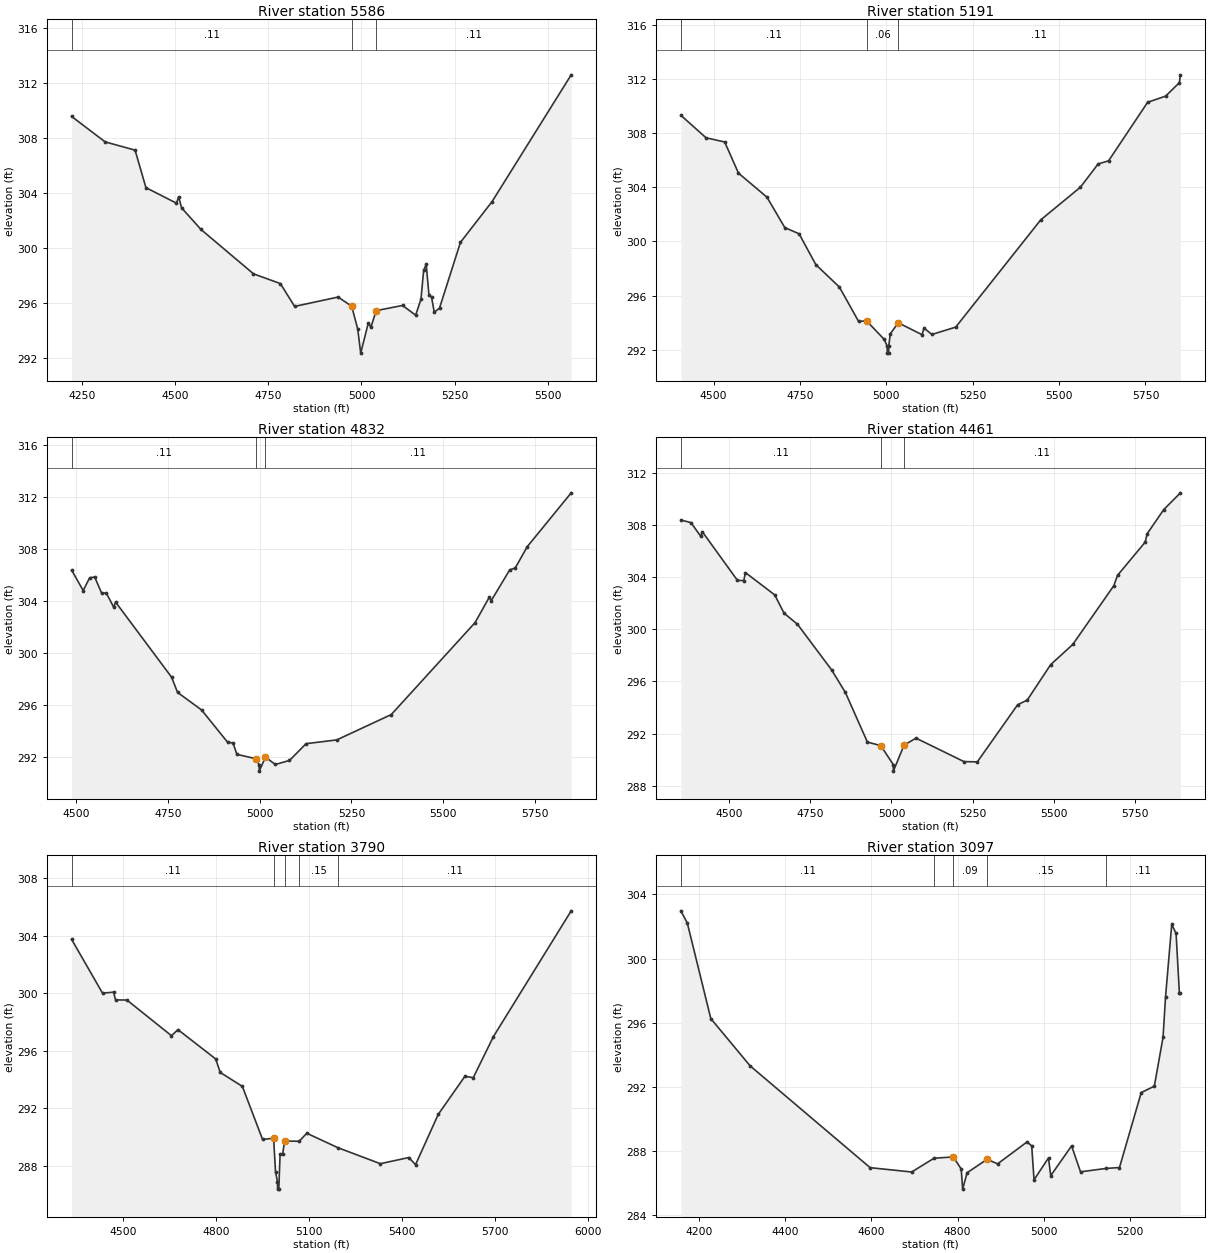
Type RM Length L Ch R = 1 ,5586    ,395,395,395
BEGIN DESCRIPTION:
WEST CEDAR CREEK 9.0
END DESCRIPTION:
XS GIS Cut Line= 3
      3727467.88     10247661.06      3728153.06      10247292.1
      3728567.82      10246911.1
#Sta/Elev= 30
  4221.8  309.55  4311.8   307.7  4392.1   307.1  4421.3  304.37  4503.3  303.24
    4509   303.7  4517.1   302.9    4569  301.33  4710.1   298.1  4782.3  297.39
  4820.5  295.73  4937.3  296.41  4973.8  295.74    4990  294.08    4998  292.33
  5018.5  294.54  5025.3  294.21  5039.5  295.42  5110.4   295.8  5145.5  295.09
  5159.7  296.24  5167.1  298.37  5173.9  298.78  5181.3  296.54  5188.1  296.43
  5195.5   295.3  5209.6  295.61  5265.8  300.39  5350.8  303.36  5563.2  312.58
#Mann= 3 , 0 , 0
  4221.8     .11       0  4973.8     .06       0  5039.5     .11       0
#XS Ineff= 1 ,-1
  5173.9    5250  298.78
Permanent Ineff=
       F
Bank Sta=4973.8,5039.5
XS Rating Curve= 0 ,0
Exp/Cntr=0.3,0.1

Type RM Length L Ch R = 1 ,5191    ,359,359,359
BEGIN DESCRIPTION:
WEST CEDAR CREEK 8.0
END DESCRIPTION:
XS GIS Cut Line= 3
      3727617.44     10247858.26      3728057.65      10247739.6
      3728956.74     10247325.25
#Sta/Elev= 30
  4405.4  309.31  4478.3  307.65  4532.2  307.34  4572.1  305.04  4654.4  303.27
  4706.2  301.02  4747.6  300.56  4796.1  298.28  4864.2  296.63  4919.8  294.09
  4942.8  294.13  4994.2  292.76  5002.5  292.25  5002.8  291.75  5006.6  291.75
  5006.9  292.25  5011.6  293.18  5034.6  293.99  5103.5  293.11    5109   293.6
  5131.9  293.13  5200.8  293.67  5446.9  301.59  5561.7     304  5613.1  305.72
  5643.3  305.95  5756.3  310.27  5808.5  310.73  5848.2  311.72  5851.3   312.3
#Mann= 3 , 0 , 0
  4405.4     .11       0  4942.8     .06       0  5034.6     .11       0
Bank Sta=4942.8,5034.6
XS Rating Curve= 0 ,0
Exp/Cntr=0.3,0.1

Type RM Length L Ch R = 1 ,4832    ,371,371,371
BEGIN DESCRIPTION:
WEST CEDAR CREEK 7.0
END DESCRIPTION:
XS GIS Cut Line= 2
      3727867.82     10248111.08      3729167.87     10247711.07
#Sta/Elev= 30
  4488.1   306.4  4519.5  304.83  4537.2  305.81  4550.9  305.87  4569.9  304.62
  4582.3  304.65  4602.6  303.55  4607.8  303.94  4760.2  298.17  4776.5     297
  4841.9  295.65  4912.5  293.18  4927.6  293.11    4938  292.24  4990.3   291.9
  4998.6  291.45  4998.9  290.95  5015.8  292.03  5042.7  291.46  5081.2  291.77
  5126.4  293.06  5210.1  293.35  5358.5   295.3  5586.7  302.37  5625.3  304.32
  5630.5  304.05  5680.9  306.42  5695.9  306.56  5728.6   308.2  5848.3  312.34
#Mann= 3 , 0 , 0
  4488.1     .11       0  4990.3     .06       0  5015.8     .11       0
Bank Sta=4990.3,5015.8
XS Rating Curve= 0 ,0
Exp/Cntr=0.3,0.1

Type RM Length L Ch R = 1 ,4461    ,671,671,671
BEGIN DESCRIPTION:
WEST CEDAR CREEK 6.0
END DESCRIPTION:
XS GIS Cut Line= 2
       3727717.9     10248461.06      3729217.81     10248111.08
#Sta/Elev= 30
  4350.8  308.38  4381.6  308.19    4412  307.14  4417.1  307.48  4525.3  303.75
  4544.8  303.74  4549.9  304.35  4640.1  302.64  4669.1  301.23  4710.2  300.39
  4815.4  296.89  4857.9  295.16  4925.8  291.35  4966.9  291.08  5005.7  289.62
    5006  289.12  5038.7  291.11  5075.8  291.65  5223.6  289.85  5264.7  289.83
    5389  294.21  5418.7  294.57  5490.6  297.28  5559.1  298.84  5685.7  303.35
    5697  304.14  5782.1  306.68  5788.4  307.33  5839.7  309.19    5891  310.47
#Mann= 3 , 0 , 0
  4350.8     .11       0  4966.9     .06       0  5038.7     .11       0
Bank Sta=4966.9,5038.7
XS Rating Curve= 0 ,0
Exp/Cntr=0.3,0.1

Type RM Length L Ch R = 1 ,3790    ,693,693,693
BEGIN DESCRIPTION:
WEST CEDAR CREEK 5.0
END DESCRIPTION:
XS GIS Cut Line= 2
      3727802.27     10249194.23      3729117.83     10248261.09
#Sta/Elev= 30
    4333  303.75  4432.7  300.01  4468.3  300.08  4474.7  299.54  4511.5  299.53
  4655.3  297.05  4676.3  297.47    4798  295.43  4812.8  294.49  4884.2  293.52
  4949.4  289.83  4985.1  289.91  4991.2  287.59  4997.6  286.87  4997.9  286.37
  5001.8  286.37    5006   288.8  5014.1  288.79  5020.7  289.72  5067.6   289.7
  5092.1  290.26    5192  289.26  5329.6  288.14  5421.8  288.57  5443.3  288.07
  5516.6  291.57  5602.6  294.22  5629.7  294.13  5694.9  296.99  5945.9  305.74
#Mann= 5 ,-1 , 0
    4333     .11       0  4985.1     .06       0  5020.7     .11       0
  5067.6     .15       0    5192     .11       0
Bank Sta=4985.1,5020.7
XS Rating Curve= 0 ,0
Exp/Cntr=0.3,0.1

Type RM Length L Ch R = 1 ,3097    ,401,401,401
BEGIN DESCRIPTION:
WEST CEDAR CREEK 4.0
END DESCRIPTION:
XS GIS Cut Line= 3
      3728117.89     10249261.06       3728903.9     10248958.02
      3729217.81     10248911.08
#Sta/Elev= 30
  4157.6  302.98  4172.5  302.22  4227.1  296.25  4318.3   293.3    4597  286.94
  4693.4  286.67  4745.4  287.53  4789.9  287.61  4808.4  286.86  4811.8   285.6
    4822  286.62  4868.3  287.46    4893  287.18  4961.4  288.55  4972.1   288.3
  4977.5  286.18  5011.1  287.55  5016.2  286.44  5064.7   288.3  5085.4  286.68
    5144  286.89  5175.9  286.95  5226.4  291.63  5256.8  292.03    5277  295.08
  5282.8  297.61  5297.2  302.13  5307.3  301.57  5314.9  297.86  5317.4  297.86
#Mann= 5 ,-1 , 0
  4157.6     .11       0  4745.4     .15       0  4789.9     .09       0
  4868.3     .15       0    5144     .11       0
#XS Ineff= 1 ,-1
  4961.4    5200  288.55
Permanent Ineff=
       F
Bank Sta=4789.9,4868.3
XS Rating Curve= 0 ,0
Exp/Cntr=0.3,0.1

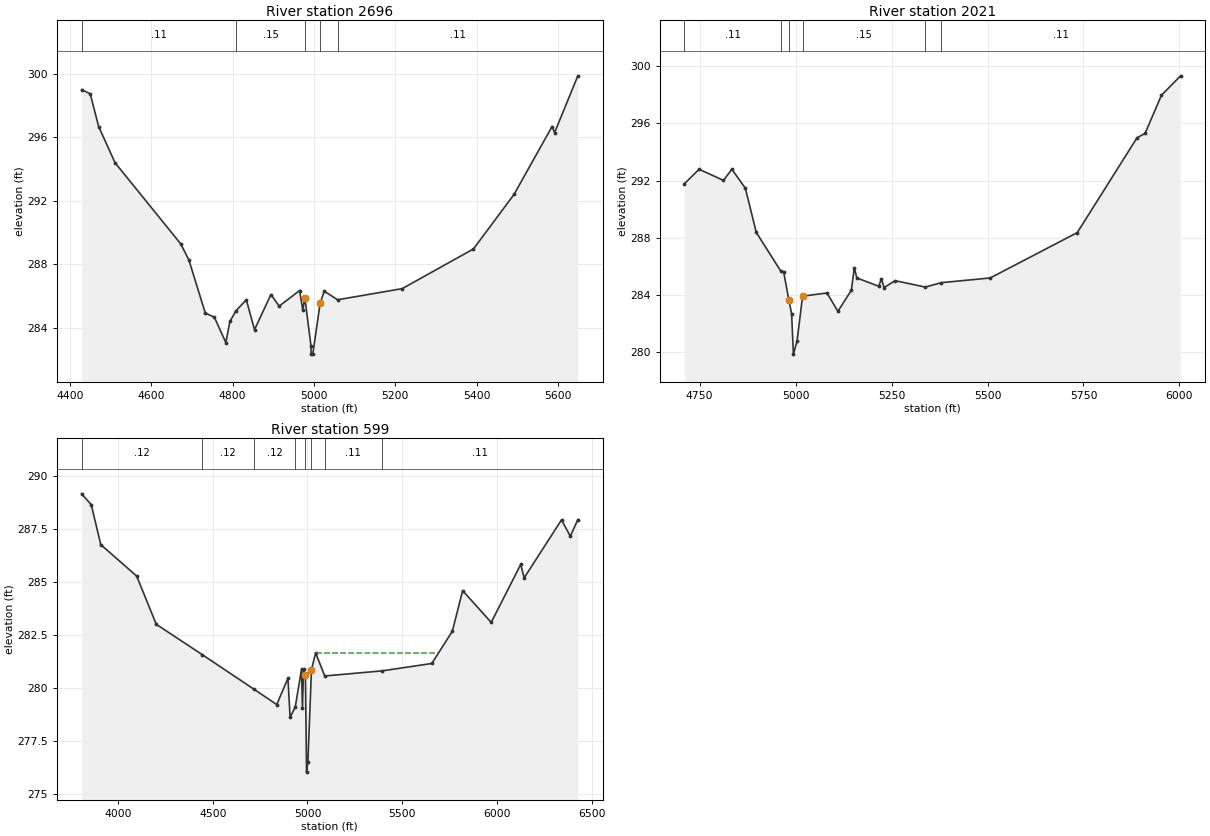
Type RM Length L Ch R = 1 ,2696    ,675,675,675
BEGIN DESCRIPTION:
WEST CEDAR CREEK 3.0
END DESCRIPTION:
XS GIS Cut Line= 3
      3728276.28     10249389.52      3729140.85     10249272.33
      3729417.82      10249061.1
#Sta/Elev= 30
  4428.4  298.99  4449.6  298.73  4470.3  296.67  4510.7  294.39  4672.2  289.29
  4692.4  288.27  4732.7  284.93  4754.9  284.68  4783.2  283.08  4793.3  284.41
  4808.6  285.09  4833.6  285.77  4853.8  283.89  4894.2   286.1  4914.4  285.37
  4964.8  286.35  4972.5  285.12  4977.6   285.9  4992.8  282.85  4993.1  282.35
  4997.1  282.35  5015.3  285.56  5025.4  286.31  5058.2  285.77  5217.1  286.47
  5392.5  288.97  5492.3   292.4  5585.8  296.67  5592.1  296.29  5649.2  299.86
#Mann= 5 ,-1 , 0
  4428.4     .11       0  4808.6     .15       0  4977.6     .09       0
  5015.3     .15       0  5058.2     .11       0
Bank Sta=4977.6,5015.3
XS Rating Curve= 0 ,0
Exp/Cntr=0.3,0.1

Type RM Length L Ch R = 1 ,2021    ,1422,1422,1422
BEGIN DESCRIPTION:
WEST CEDAR CREEK 2.0
END DESCRIPTION:
XS GIS Cut Line= 2
      3728492.38     10249959.86      3729467.88     10249111.04
#Sta/Elev= 30
  4710.1  291.77  4748.4  292.79    4812  292.01  4833.9  292.79    4869  291.46
  4897.5  288.36  4961.1  285.66  4968.7  285.61  4982.5  283.61  4989.6  282.65
  4994.2  279.83  5003.8  280.75  5018.1  283.89  5081.7  284.12  5110.2  282.83
  5145.3  284.31  5152.9  285.89  5159.5  285.17  5216.5  284.59  5223.2  285.09
  5230.8   284.5  5259.3  284.98  5338.1  284.53  5379.8  284.84  5507.1  285.17
    5734  288.35  5889.7     295  5910.6   295.3  5953.3  297.98  6003.2  299.34
#Mann= 6 ,-1 , 0
  4710.1     .11       0  4961.1     .15       0  4982.5     .09       0
  5018.1     .15       0  5338.1     .11       0  5379.8     .11       0
Bank Sta=4982.5,5018.1
XS Rating Curve= 0 ,0
Exp/Cntr=0.3,0.1

Type RM Length L Ch R = 1 ,599     ,0,0,0
BEGIN DESCRIPTION:
WEST CEDAR CREEK 1.0
END DESCRIPTION:
XS GIS Cut Line= 3
      3727807.49     10250295.76      3728988.56     10250459.78
      3730293.71     10249882.06
#Sta/Elev= 30
  3807.6  289.17  3858.4  288.66  3908.9  286.77  4098.2  285.29  4201.7  283.01
    4444  281.58  4716.6  279.95  4837.8  279.22  4896.8  280.46  4908.4  278.61
  4935.8  279.12  4968.5  280.88  4973.5  279.04  4979.1  280.88  4989.2  280.62
  4995.1  276.03  5002.3  276.53  5021.1  280.86    5043  281.66  5091.3  280.57
  5392.9  280.81  5656.2  281.16  5764.7  282.68  5819.2   284.6  5969.9   283.1
    6126  285.84  6143.8   285.2  6341.1  287.94  6387.6  287.17  6427.3  287.95
#Mann= 8 ,-1 , 0
  3807.6     .12       0    4444     .12       0  4716.6     .12       0
  4935.8     .15       0  4989.2     .08       0  5021.1     .15       0
  5091.3     .11       0  5392.9     .11       0
#XS Ineff= 2 ,-1
    4560  4979.1  280.88    5043    5690  281.66
Permanent Ineff=
       T       T
Bank Sta=4989.2,5021.1
XS Rating Curve= 0 ,0
Exp/Cntr=0.3,0.1

Chan Stop Cuts=-1
Use User Specified Reach Order=0
Composite Channel Slope=5