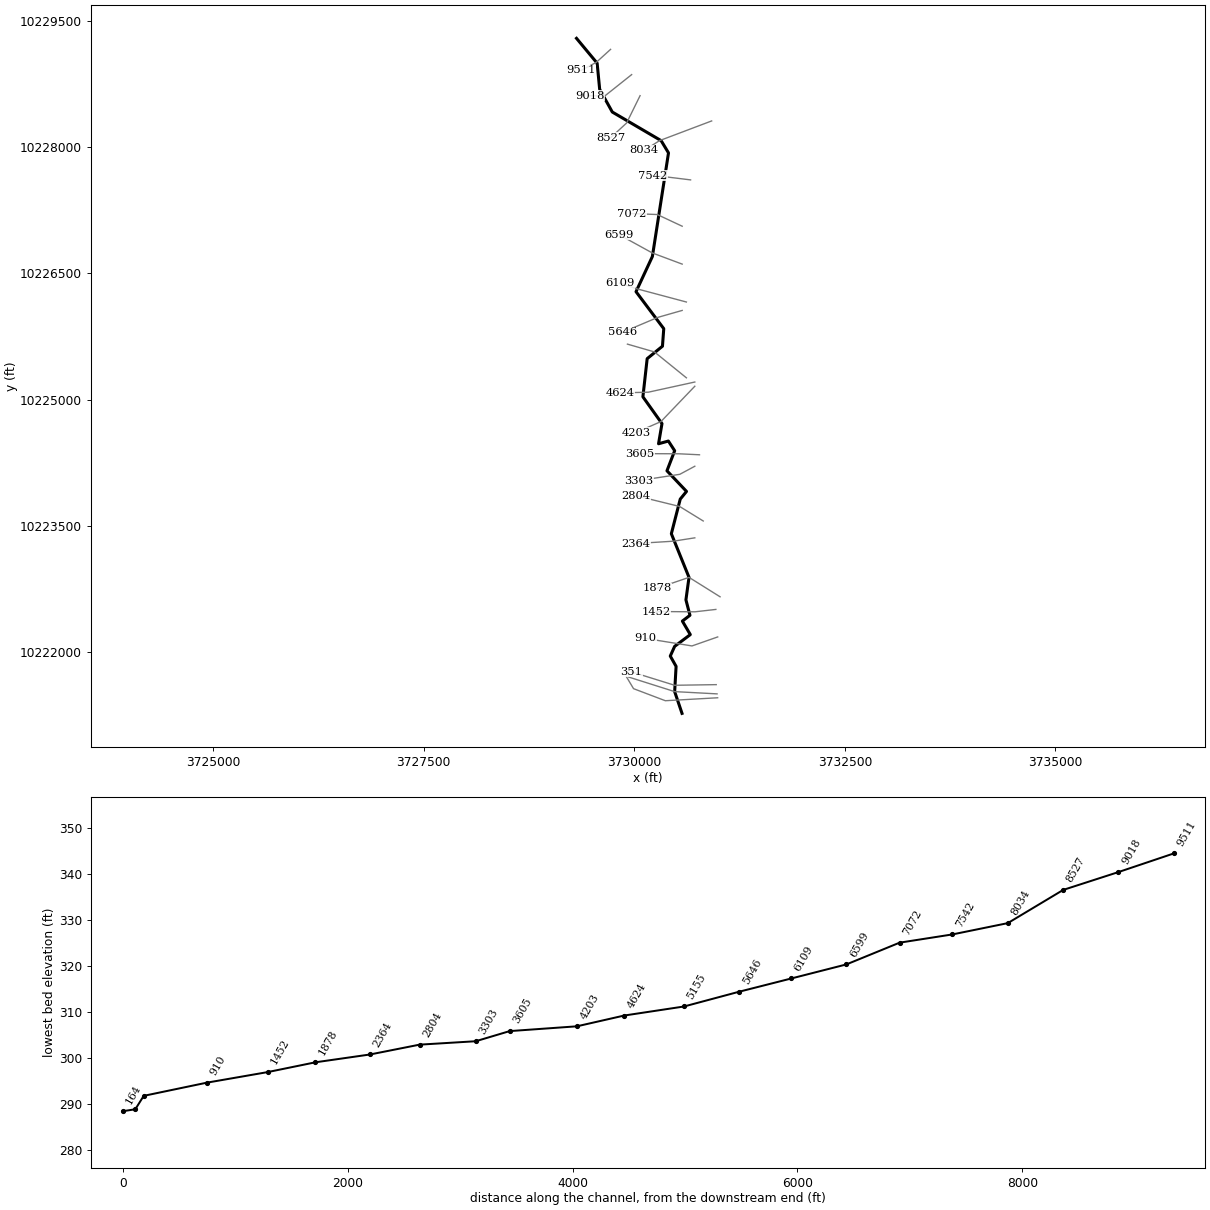
--- WEST GUM BRANCH.prj (project) ---

Proj Title=WEST GUM BRANCH Base Level Engineering
Current Plan=p01
Default Exp/Contr=0.3,0.1
English Units
Geom File=g01
Flow File=f01
Plan File=p01
Y Axis Title=Elevation
X Axis Title(PF)=Main Channel Distance
X Axis Title(XS)=Station
BEGIN DESCRIPTION:
WEST GUM BRANCH
END DESCRIPTION:
DSS Export Rating Curves= 0
DSS Export Rating Curve Sorted= 0
DSS Export Volume Flow Curves= 0
DXF OffsetX= 0
DXF OffsetY= 0
DXF ScaleX= 1
DXF ScaleY= 10

--- WEST GUM BRANCH.p01 (plan) ---

Plan Title=Multiple Run
Program Version=4.10
Short Identifier=Multiple
Geom File=g01
Flow File=f01
Subcritical Flow
K Sum by GR= 0
Std Step Tol= 0.01
Critical Tol= 0.01
Num of Std Step Trials= 20
Max Error Tol= 0.3
Flow Tol Ratio= 0.001
Split Flow NTrial= 30
Split Flow Tol= 0.02
Split Flow Ratio= 0.02
Log Output Level= 0
Friction Slope Method= 1
Unsteady Friction Slope Method= 2
Unsteady Bridges Friction Slope Method= 1
Parabolic Critical Depth
Global Vel Dist= 1 , 1 , 1
Global Log Level= 0
CheckData=True
Encroach Param=-1 ,0,0, 0
BEGIN DESCRIPTION:
Multiple Run
END DESCRIPTION:
Computation Interval=1HOUR
Output Interval=1HOUR
Run HTab= 0
Run UNet= 0
Run PostProcess= 0
Run WQNet= 0
UNET Theta= 1
UNET Theta Warmup= 1
UNET ZTol= 0.02
UNET ZSATol= 0.05
UNET MxIter= 20
UNET MaxInSteps= 0
UNET DtIC= 0
UNET DtMin= 0
UNET MaxCRTS= 20
UNET WFStab= 2
UNET SFStab= 1
UNET WFX= 1
UNET SFX= 1
UNET DSS MLevel= 4
UNET DZMax Abort= 100
UNET Convert EG Bridges= 0
UNET Use Existing IB Tables=-1
UNET Froude Reduction=False
UNET Froude Limit= 1
UNET Froude Power= 10
UNET Time Slicing=0,0, 5
UNET Junction Losses=0
Instantaneous Interval=1HOUR
Write IC File= 0
Write IC File at Sim End=0
Echo Input=False
Echo Parameters=False
Echo Output=False
Write Detailed= 0
WQ AD Non Conservative
WQ ULTIMATE=-1
WQ Max Comp Step=1HOUR
WQ Output Interval=15MIN
WQ Output Selected Increments= 0
WQ Output face flow=0
WQ Output face velocity=0
WQ Output face area=0
WQ Output face dispersion=0
WQ Output cell volume=0
WQ Output cell surface area=0
WQ Output cell continuity=0
WQ Output cumulative cell continuity=0
WQ Output face conc=0
WQ Output face dconc_dx=0
WQ Output face courant=0
WQ Output face peclet=0
WQ Output face adv mass=0
WQ Output face disp mass=0
WQ Output cell mass=0
WQ Output cell source sink temp=0
WQ Output cell source sink nsm=0
WQ Output MaxMinRange=-1
WQ Daily Max Min Mean=-1
WQ Daily Range=0
WQ Daily Time=0
WQ Create Restart=0
WQ Fixed Restart=0
WQ System Summary=0
WQ Use Fixed Temperature=0
Sorting and Armoring Iterations= 10
XS Update Threshold= 0.02
Hydraulics Update Threshold= 0.02
Energy Slope Method= 1
Volume Change Method= 0
XS Weighting Method= 0
Number of US Weighted Cross Sections= 1
Number of DS Weighted Cross Sections= 1
Upstream XS Weight=0.25
Main XS Weight=0.5
Downstream XS Weight=0.25
Number of DS XS's Weighted with US Boundary= 1
Upstream Boundary Weight= 1
Weight of XSs Associated with US Boundary= 0
Number of US XS's Weighted with DS Boundary= 1
Downstream Boundary Weight= 0.5
Weight of XSs Associated with DS Boundary= 0.5
Sediment Output Level= 4
Mass or Volume Output= 0
Output Increment Type= 1
Profile and TS Output Increment= 10
XS Output Flag= 0
XS Output Increment= 10
Disregard all LS=0
Disregard all Conn=0
Disregard all Breaches=0
Disregard all Pumps=0

--- WEST GUM BRANCH.f01 (steady flow) ---

Flow Title=Multiple
Program Version=4.10
Number of Profiles= 7
Profile Names=10-year,25-year,50-year,1pct_min,100-year,1pct_plu,500-year
River Rch & RM=WEST GUM BRANCH,Reach-1         ,9511
    1067    1492    2062     935    2824    8528    5485
Boundary for River Rch & Prof#=WEST GUM BRANCH,Reach-1         , 1
Up Type= 0
Dn Type= 3
Dn Slope=0.02
Boundary for River Rch & Prof#=WEST GUM BRANCH,Reach-1         , 2
Up Type= 0
Dn Type= 3
Dn Slope=0.02
Boundary for River Rch & Prof#=WEST GUM BRANCH,Reach-1         , 3
Up Type= 0
Dn Type= 3
Dn Slope=0.02
Boundary for River Rch & Prof#=WEST GUM BRANCH,Reach-1         , 4
Up Type= 0
Dn Type= 3
Dn Slope=0.02
Boundary for River Rch & Prof#=WEST GUM BRANCH,Reach-1         , 5
Up Type= 0
Dn Type= 3
Dn Slope=0.02
Boundary for River Rch & Prof#=WEST GUM BRANCH,Reach-1         , 6
Up Type= 0
Dn Type= 3
Dn Slope=0.02
Boundary for River Rch & Prof#=WEST GUM BRANCH,Reach-1         , 7
Up Type= 0
Dn Type= 3
Dn Slope=0.02
DSS Import GetInterval= 0
DSS Import GetPeak= 0
DSS Import FillOption= 0

--- WEST GUM BRANCH.g01 (geometry) ---

Geom Title=Existing Conditions
Program Version=4.10

River Reach=WEST GUM BRANCH ,Reach-1
Reach XY= 30
      3729313.23     10229291.84      3729558.23     10228996.84
      3729588.23     10228686.84      3729738.23     10228416.84
      3730318.23     10228076.84       3730405.5     10227931.66
       3730214.1     10226701.62      3730019.88     10226283.63
      3730349.21     10225844.53      3730333.72     10225636.24
      3730152.17     10225488.47      3730101.51      10225035.3
       3730328.1     10224717.23      3730287.28     10224477.98
      3730404.09     10224510.35      3730478.68     10224394.95
       3730387.2      10224157.1      3730619.42     10223912.22
      3730544.83     10223820.74      3730439.28     10223409.79
      3730648.98     10222891.88      3730612.38     10222624.48
      3730660.23     10222441.52      3730570.16     10222372.56
      3730664.46     10222212.12      3730478.68     10222072.79
      3730426.61     10221957.39      3730495.57     10221834.94
      3730478.68     10221535.18       3730565.9     10221276.82

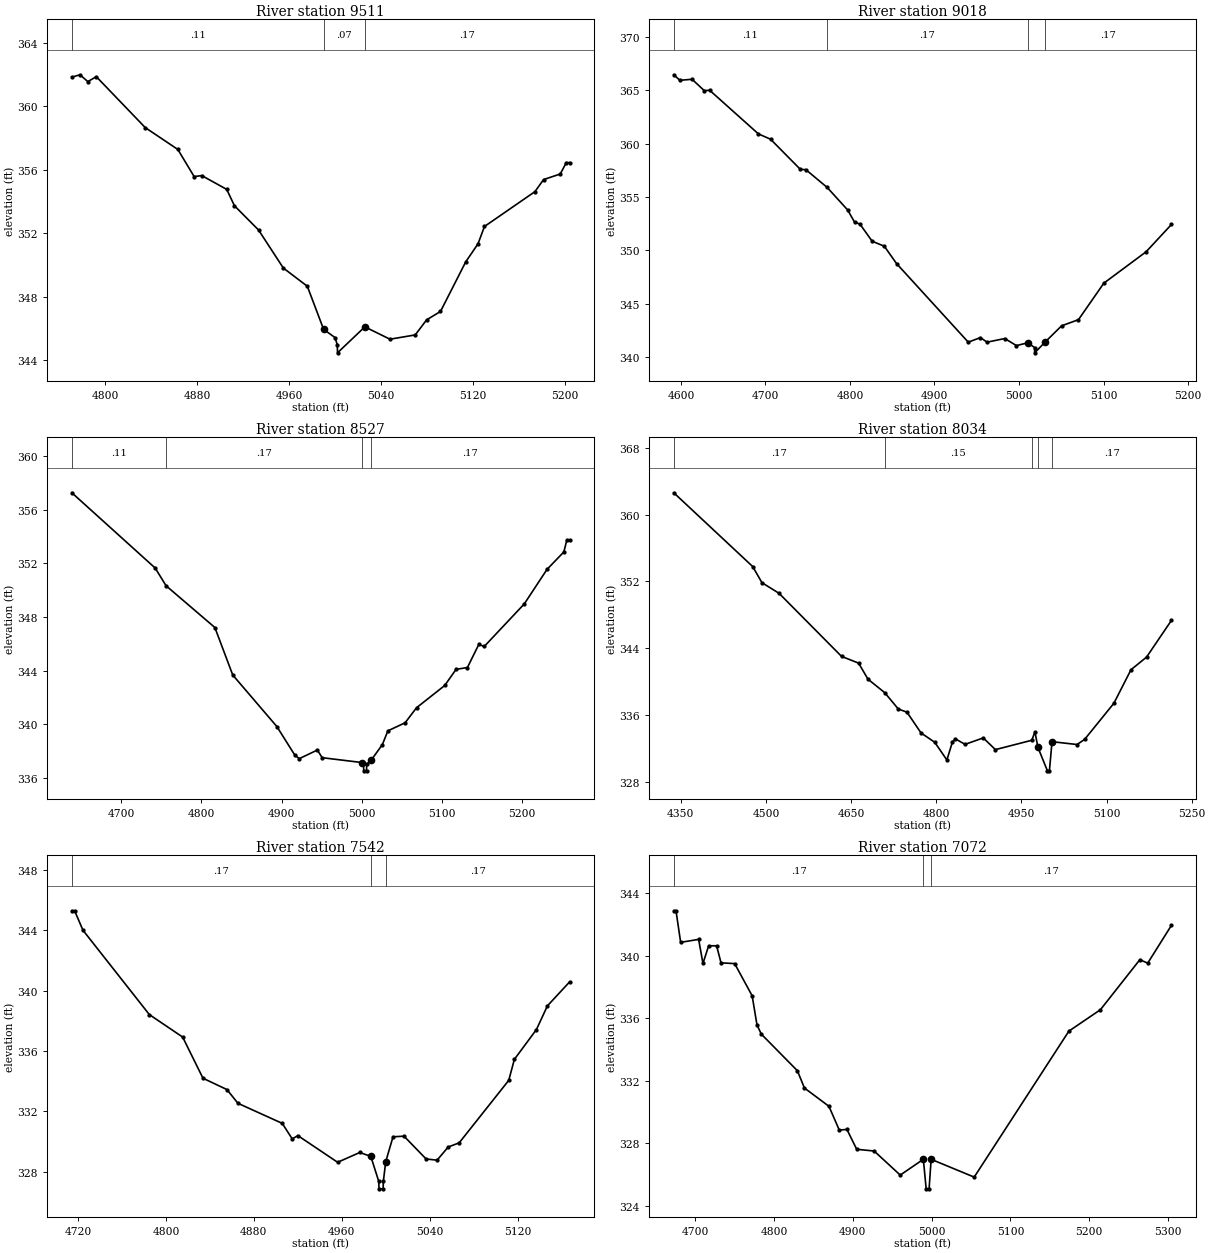
Type RM Length L Ch R = 1 ,9511    ,493,493,493
BEGIN DESCRIPTION:
WEST GUM BRANCH 20.0
END DESCRIPTION:
XS GIS Cut Line= 3
      3729717.89      10229161.1      3729548.23     10229006.84
      3729367.88     10228911.08
#Sta/Elev= 30
  4770.7  361.84  4777.8  361.99  4784.6  361.56    4792  361.87  4834.6  358.66
    4863  357.28  4877.2  355.57  4883.9  355.63  4905.6  354.76  4912.3  353.73
  4933.3   352.2  4954.9   349.8  4975.8  348.65    4990  345.93    5000  345.41
  5001.9  344.95  5002.1  344.45  5025.9  346.09  5047.8  345.31  5069.8  345.58
  5079.7  346.53  5091.8  347.06  5113.8  350.19  5124.5  351.33  5130.1  352.42
  5174.1  354.62  5181.6  355.38  5196.1  355.73  5201.4  356.45  5204.2  356.45
#Mann= 3 ,-1 , 0
  4770.7     .11       0    4990     .07       0  5025.9     .17       0
Bank Sta=4990,5025.9
XS Rating Curve= 0 ,0
Exp/Cntr=0.3,0.1

Type RM Length L Ch R = 1 ,9018    ,491,491,491
BEGIN DESCRIPTION:
WEST GUM BRANCH 19.0
END DESCRIPTION:
XS GIS Cut Line= 3
      3729967.85     10228861.07      3729648.23     10228606.84
      3729467.88     10228611.07
#Sta/Elev= 30
  4591.6  366.46  4598.8  365.94  4613.2  366.04  4627.7  364.97    4634  365.01
  4691.7  360.92  4706.1  360.42  4741.4  357.59  4747.8  357.57  4773.1   355.9
  4797.4  353.78  4805.5  352.64  4811.8  352.47  4826.3  350.86  4840.7  350.39
  4855.1  348.77    4940   341.4  4954.4  341.83  4962.2   341.4  4983.2  341.74
    4997  341.08  5010.4  341.34  5018.4   340.9  5018.6   340.4  5030.4  341.37
  5050.4  342.93  5070.4  343.51  5100.4  346.93  5150.4  349.87  5180.4  352.43
#Mann= 4 ,-1 , 0
  4591.6     .11       0  4773.1     .17       0  5010.4     .09       0
  5030.4     .17       0
Bank Sta=5010.4,5030.4
XS Rating Curve= 0 ,0
Exp/Cntr=0.3,0.1

Type RM Length L Ch R = 1 ,8527    ,493,493,493
BEGIN DESCRIPTION:
WEST GUM BRANCH 18.0
END DESCRIPTION:
XS GIS Cut Line= 3
      3730067.86     10228611.08      3729908.23     10228286.84
      3729717.86     10228111.08
#Sta/Elev= 30
  4638.6  357.25  4742.5  351.64  4756.1  350.32  4816.9  347.21  4839.2  343.67
  4894.2  339.83  4916.7  337.69  4922.2  337.44  4944.7  338.08  4950.7  337.51
    5000  337.15  5002.2  337.03  5002.5  336.53    5006  336.53  5006.2  337.03
  5011.6  337.31  5025.8  338.49  5032.6  339.51  5054.1  340.11  5068.3  341.23
  5103.5  342.89  5117.6  344.09  5131.8  344.23    5146  345.95  5152.8   345.8
  5202.7  348.97    5231  351.54    5252  352.84  5255.7  353.72  5259.1  353.72
#Mann= 4 ,-1 , 0
  4638.6     .11       0  4756.1     .17       0    5000     .09       0
  5011.6     .17       0
Bank Sta=5000,5011.6
XS Rating Curve= 0 ,0
Exp/Cntr=0.3,0.1

Type RM Length L Ch R = 1 ,8034    ,492,492,492
BEGIN DESCRIPTION:
WEST GUM BRANCH 17.0
END DESCRIPTION:
XS GIS Cut Line= 3
      3730917.84     10228311.07      3730298.23     10228076.84
      3730117.88     10227961.09
#Sta/Elev= 30
  4337.6   362.6  4476.6  353.77  4492.9  351.84    4523  350.57  4633.1  343.02
  4663.2  342.21  4679.7  340.29  4709.3  338.67  4733.1  336.72  4748.4  336.34
  4773.2  333.85  4797.3  332.74  4818.7  330.62  4828.3  332.74  4833.6  333.15
  4850.7  332.49  4882.8  333.26  4904.2  331.86  4968.3  332.98  4973.8  333.99
  4979.1  332.12  4995.8  329.32  4999.3  329.32  5003.9  332.81    5048  332.47
  5061.4  333.09  5112.9  337.41    5143  341.42  5170.4  342.93  5214.3  347.33
#Mann= 5 ,-1 , 0
  4337.6     .17       0  4709.3     .15       0  4968.3     .17       0
  4979.1     .09       0  5003.9     .17       0
Bank Sta=4979.1,5003.9
XS Rating Curve= 0 ,0
Exp/Cntr=0.3,0.1

Type RM Length L Ch R = 1 ,7542    ,470,470,470
BEGIN DESCRIPTION:
WEST GUM BRANCH 16.0
END DESCRIPTION:
XS GIS Cut Line= 3
      3730667.85     10227611.07      3730384.39     10227645.96
      3730217.87     10227661.07
#Sta/Elev= 30
  4714.4   345.3  4716.9   345.3  4724.5  344.01  4784.9  338.42  4815.2  336.93
  4833.7   334.2  4855.5  333.45  4865.5  332.54  4905.8  331.21  4914.9  330.18
    4920   330.4  4956.2  328.63  4976.4  329.28  4986.4  329.02  4993.6  327.37
  4993.9  326.87  4997.6  326.87  4997.8  327.37    5000  328.68  5006.6  330.32
  5016.6  330.36  5036.7  328.85  5046.7  328.77  5056.8  329.64  5066.8  329.92
  5111.9  334.06    5117  335.45  5137.1  337.43  5147.1     339  5167.2  340.58
#Mann= 3 , 0 , 0
  4714.4     .17       0  4986.4     .09       0    5000     .17       0
Bank Sta=4986.4,5000
XS Rating Curve= 0 ,0
Exp/Cntr=0.3,0.1

Type RM Length L Ch R = 1 ,7072    ,473,473,473
BEGIN DESCRIPTION:
WEST GUM BRANCH 15.0
END DESCRIPTION:
XS GIS Cut Line= 3
      3730567.89     10227061.05       3730271.8     10227199.83
      3729967.81     10227211.07
#Sta/Elev= 30
    4673  342.87  4675.8  342.87  4681.7  340.85  4704.5  341.04    4710   339.5
  4717.2  340.63  4727.3  340.63  4732.9  339.54  4750.2  339.49  4772.4  337.43
  4778.5  335.57    4784  334.98  4829.7  332.64  4838.7  331.53  4869.8  330.36
  4882.9  328.84  4892.6  328.88    4905  327.61  4927.1   327.5  4960.2  325.96
  4989.5  326.97  4993.1  325.08  4996.8  325.08  4999.4  326.97    5054  325.83
  5174.1  335.17  5214.1  336.54  5264.1  339.74  5274.1  339.52  5304.2  341.94
#Mann= 3 , 0 , 0
    4673     .17       0  4989.5     .09       0  4999.4     .17       0
Bank Sta=4989.5,4999.4
XS Rating Curve= 0 ,0
Exp/Cntr=0.3,0.1

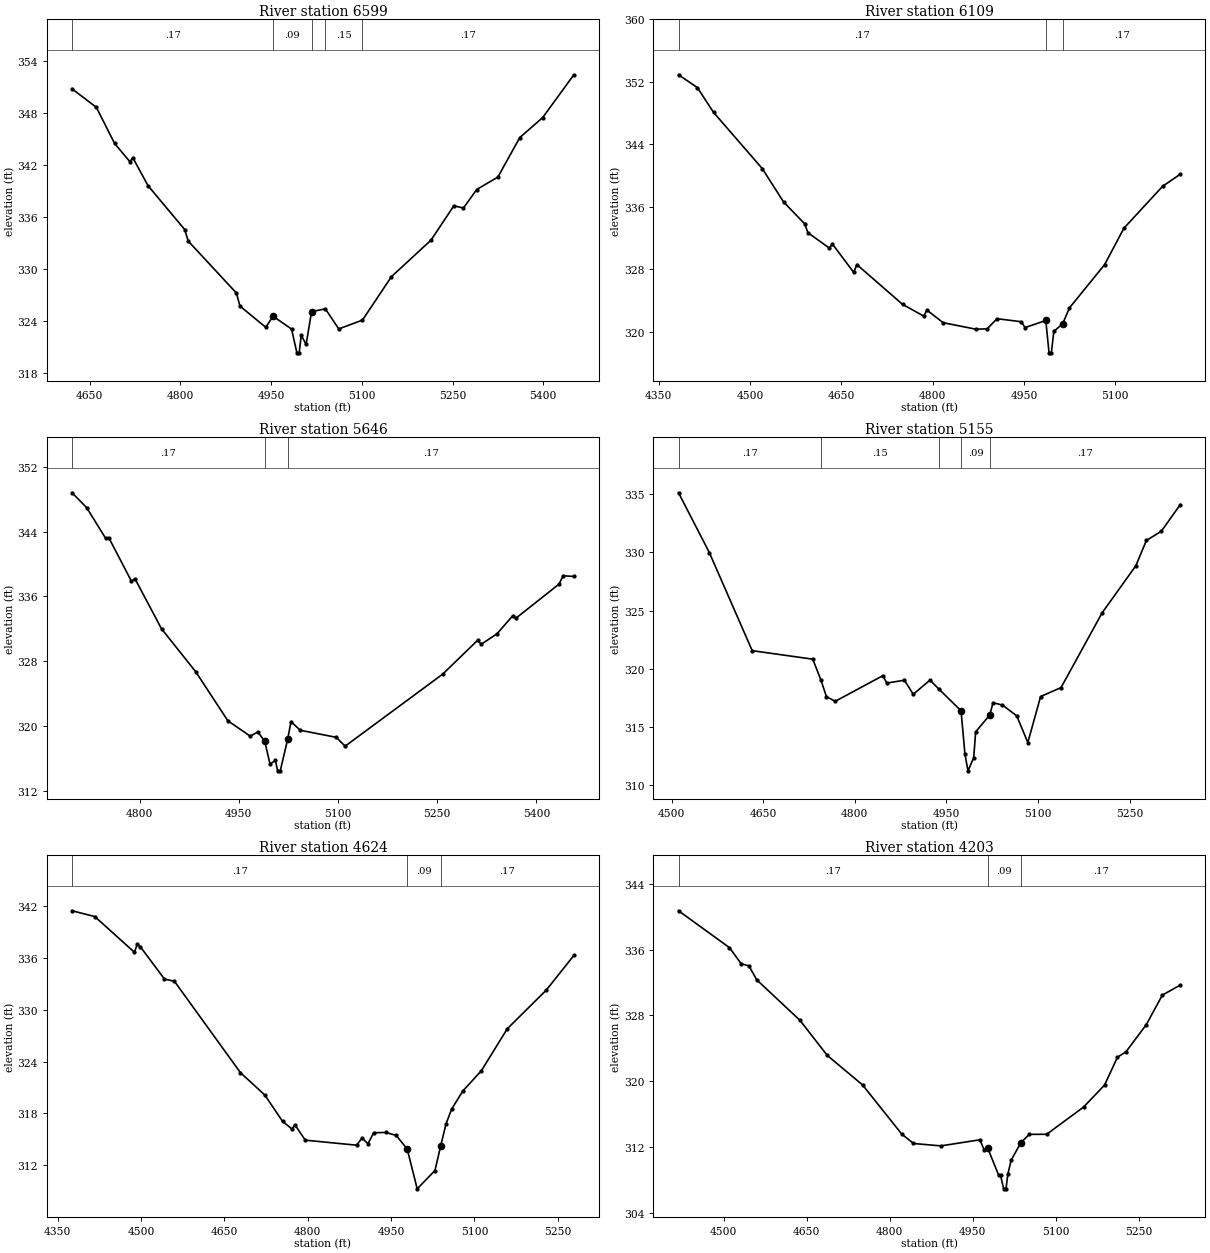
Type RM Length L Ch R = 1 ,6599    ,490,490,490
BEGIN DESCRIPTION:
WEST GUM BRANCH 14.0
END DESCRIPTION:
XS GIS Cut Line= 3
      3730567.88     10226611.06      3730212.69     10226743.84
      3729817.81     10226961.09
#Sta/Elev= 30
  4620.8  350.82  4660.9   348.7  4691.2  344.52  4716.2  342.44  4721.5  342.85
  4746.5  339.64  4807.1  334.59    4813  333.25  4892.6  327.26  4898.4  325.76
  4941.1  323.31  4953.2  324.58  4983.8  323.11  4992.6  320.36  4996.4  320.36
  4999.9  322.39  5007.9  321.33  5016.9  325.12  5039.8  325.43  5061.9  323.12
  5101.1  324.14    5149  329.15  5214.4  333.36  5252.2  337.33    5268  337.07
  5290.1  339.21  5325.1  340.65  5361.2   345.2    5399   347.5  5450.7  352.45
#Mann= 5 ,-1 , 0
  4620.8     .17       0  4953.2     .09       0  5016.9     .17       0
  5039.8     .15       0  5101.1     .17       0
Bank Sta=4953.2,5016.9
XS Rating Curve= 0 ,0
Exp/Cntr=0.3,0.1

Type RM Length L Ch R = 1 ,6109    ,463,463,463
BEGIN DESCRIPTION:
WEST GUM BRANCH 13.0
END DESCRIPTION:
XS GIS Cut Line= 3
      3730617.83     10226161.08      3730021.29     10226320.22
       3729824.7     10226385.05
#Sta/Elev= 30
  4382.6   352.9  4413.6  351.26  4440.1  348.09  4520.3  340.88  4555.2  336.62
  4589.6  333.84  4595.3  332.68  4630.3  330.72  4635.4  331.24  4670.4   327.6
  4675.5  328.61  4750.6  323.52  4785.5  322.01  4790.7  322.78  4817.3  321.17
  4870.8  320.34  4889.7  320.38  4905.8  321.68  4945.9  321.29  4951.8  320.54
    4986  321.45  4991.3  317.31  4995.1  317.31  4999.2  320.06  5013.8  321.04
  5024.7  323.05  5082.6   328.6  5114.3  333.26  5177.8  338.62    5207  340.18
#Mann= 3 , 0 , 0
  4382.6     .17       0    4986     .09       0  5013.8     .17       0
Bank Sta=4986,5013.8
XS Rating Curve= 0 ,0
Exp/Cntr=0.3,0.1

Type RM Length L Ch R = 1 ,5646    ,491,491,491
BEGIN DESCRIPTION:
WEST GUM BRANCH 12.0
END DESCRIPTION:
XS GIS Cut Line= 3
      3730567.85     10226061.07      3730277.43     10225978.23
       3729857.1     10225800.14
#Sta/Elev= 30
    4698  348.79  4720.1  346.95  4748.7  343.17  4753.9  343.18  4787.8  337.86
    4793  338.18  4833.2  331.99  4885.2  326.65  4933.5  320.62  4967.3  318.73
  4978.8  319.24  4989.2   318.1  4997.2  315.28  5005.3  315.72  5008.7  314.44
  5012.7  314.44    5024  318.38  5028.9  320.52    5043  319.45  5097.3  318.58
  5110.8  317.49  5258.3  326.39  5311.1  330.57  5316.5  330.08  5340.2  331.36
  5363.9  333.58  5369.3  333.32    5434   337.5  5440.3  338.54  5456.5  338.45
#Mann= 3 , 0 , 0
    4698     .17       0  4989.2     .09       0    5024     .17       0
Bank Sta=4989.2,5024
XS Rating Curve= 0 ,0
Exp/Cntr=0.3,0.1

Type RM Length L Ch R = 1 ,5155    ,531,531,531
BEGIN DESCRIPTION:
WEST GUM BRANCH 11.0
END DESCRIPTION:
XS GIS Cut Line= 3
      3730617.87     10225261.05      3730238.02     10225568.69
      3729917.88     10225661.06
#Sta/Elev= 30
  4511.2  335.11  4561.6  329.98  4631.9  321.55  4731.1  320.82  4744.6  319.01
  4753.4  317.61  4767.8   317.2  4845.8   319.4  4852.5  318.77  4881.3  319.01
  4895.7   317.8    4923  319.02  4938.3  318.22    4974  316.39  4980.4  312.65
  4985.4  311.23  4994.8  312.37  4997.9  314.58    5021  316.02  5026.4  317.08
  5041.8  316.88  5065.3  315.95  5083.4  313.66  5104.3  317.61  5137.8  318.38
  5205.1   324.8  5260.4  328.85  5277.6  331.02    5302   331.8  5333.2   334.1
#Mann= 5 ,-1 , 0
  4511.2     .17       0  4744.6     .15       0  4938.3     .17       0
    4974     .09       0    5021     .17       0
Bank Sta=4974,5021
XS Rating Curve= 0 ,0
Exp/Cntr=0.3,0.1

Type RM Length L Ch R = 1 ,4624    ,421,421,421
BEGIN DESCRIPTION:
WEST GUM BRANCH 10.0
END DESCRIPTION:
XS GIS Cut Line= 3
      3730717.81     10225211.06      3730166.57     10225090.45
      3729828.06     10225081.77
#Sta/Elev= 30
  4375.9  341.44  4416.8  340.77  4488.1  336.64  4493.2  337.57  4498.7  337.28
  4542.2  333.54  4560.1  333.28  4678.9  322.71  4722.8  320.12  4754.6  317.08
  4771.7  316.19  4776.9  316.67  4795.6   314.9  4887.7  314.32  4897.9  315.14
  4908.2  314.49  4918.7  315.76  4940.2  315.79  4958.9  315.46  4978.9  313.89
  4996.9  309.27  5028.9  311.39  5038.9  314.17  5048.9  316.81  5058.9  318.49
  5078.9  320.58  5112.4  322.94    5159  327.79    5229  332.25  5278.8  336.27
#Mann= 3 , 0 , 0
  4375.9     .17       0  4978.9     .09       0  5038.9     .17       0
Bank Sta=4978.9,5038.9
XS Rating Curve= 0 ,0
Exp/Cntr=0.3,0.1

Type RM Length L Ch R = 1 ,4203    ,598,598,598
BEGIN DESCRIPTION:
WEST GUM BRANCH 9.0
END DESCRIPTION:
XS GIS Cut Line= 3
      3730717.84     10225161.06      3730315.43     10224741.16
      3730017.82     10224611.06
#Sta/Elev= 30
  4418.4  340.72  4510.4  336.24  4531.5  334.29  4545.6  334.02  4559.8  332.32
  4637.7  327.41  4687.1  323.14  4750.8  319.56  4821.4   313.6  4842.8  312.44
  4892.2  312.15  4962.9  312.89  4970.2  311.68  4977.1  311.85  4996.6  308.59
    5000  308.59  5005.7  306.93  5009.9  306.93  5013.2   308.7  5019.2   310.4
  5036.6  312.53  5051.9  313.55  5083.4  313.56  5150.1  316.87  5187.9  319.54
  5211.3  322.93  5226.5  323.57  5263.5   326.9  5292.4  330.48  5324.8  331.69
#Mann= 3 ,-1 , 0
  4418.4     .17       0  4977.1     .09       0  5036.6     .17       0
Bank Sta=4977.1,5036.6
XS Rating Curve= 0 ,0
Exp/Cntr=0.3,0.1

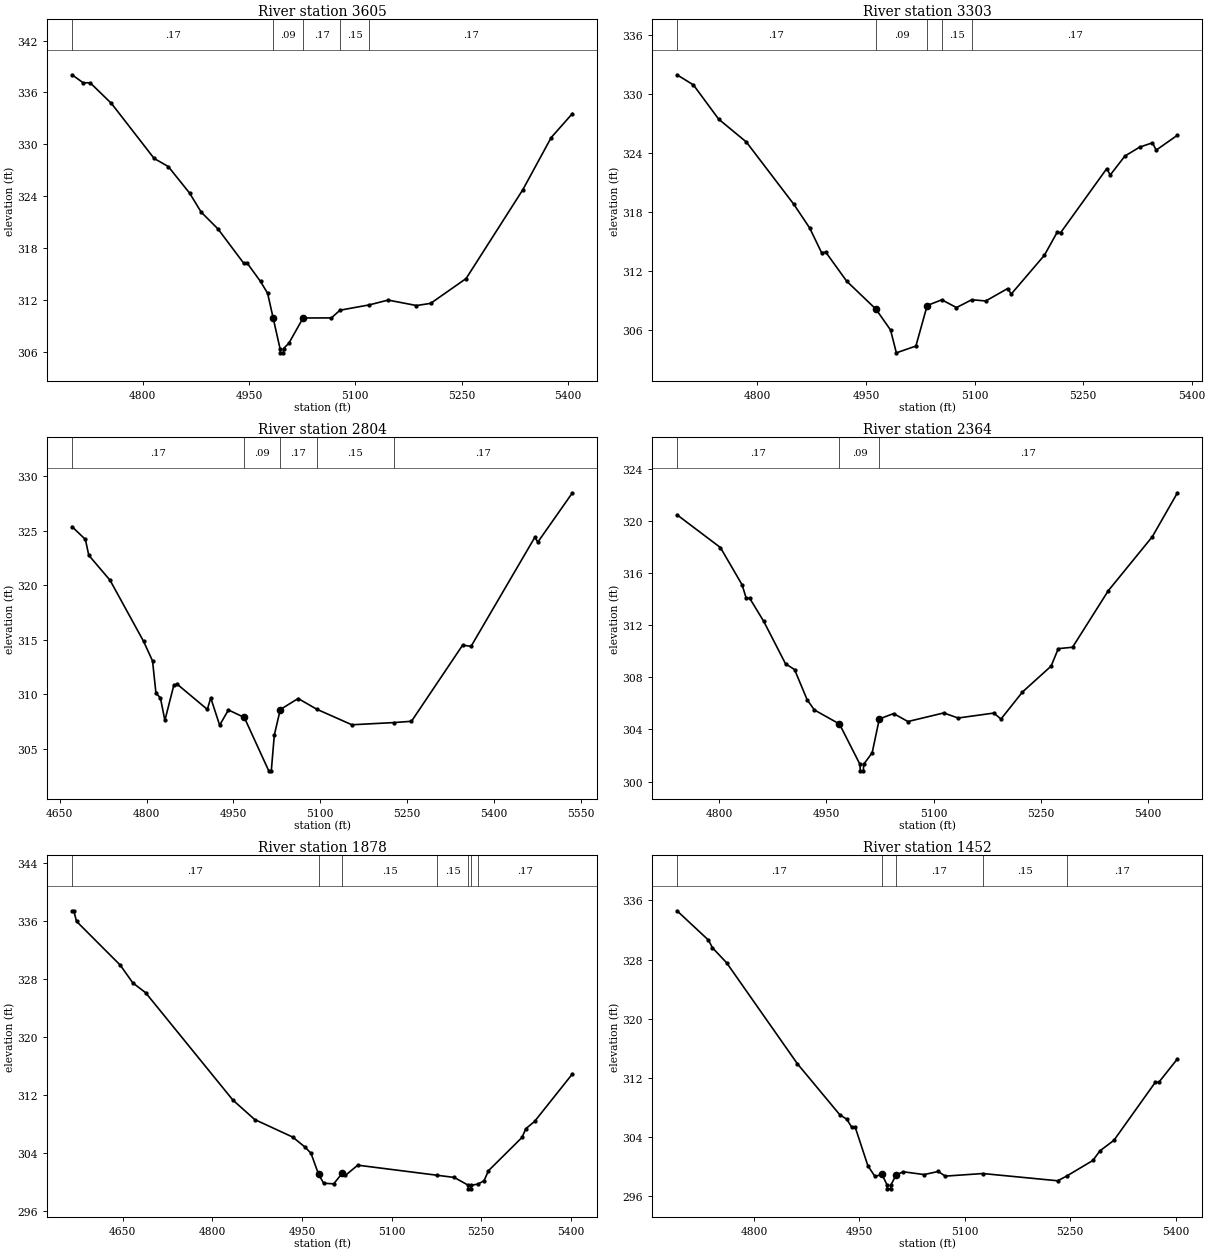
Type RM Length L Ch R = 1 ,3605    ,302,302,302
BEGIN DESCRIPTION:
WEST GUM BRANCH 8.0
END DESCRIPTION:
XS GIS Cut Line= 3
      3730773.49     10224347.25      3730529.99     10224358.97
      3730067.88     10224361.07
#Sta/Elev= 30
  4700.3  338.04    4716  337.12    4726  337.11    4756  334.72  4816.1  328.37
  4836.1  327.43  4866.1  324.37  4882.5  322.16  4906.2  320.22  4942.6  316.24
  4947.6  316.24  4966.2  314.14  4976.2  312.78    4984 309.932  4993.7  306.39
  4994.1  305.89  4998.4  305.89  4998.7  306.39  5006.2     307  5026.2  309.92
  5066.2  309.93  5078.3  310.82  5119.4  311.43  5146.2  311.99  5186.2  311.36
  5206.2  311.61  5256.2  314.48  5336.2  324.75  5376.2  330.78  5406.2  333.56
#Mann= 5 ,-1 , 0
  4700.3     .17       0    4984     .09       0  5026.2     .17       0
  5078.3     .15       0  5119.4     .17       0
Bank Sta=4984,5026.2
XS Rating Curve= 0 ,0
Exp/Cntr=0.3,0.1

Type RM Length L Ch R = 1 ,3303    ,499,499,499
BEGIN DESCRIPTION:
WEST GUM BRANCH 7.0
END DESCRIPTION:
XS GIS Cut Line= 3
      3730717.84     10224211.07      3730539.75      10224115.4
      3730056.06     10224041.26
#Sta/Elev= 30
  4688.8  331.95  4711.5  330.92  4746.4  327.44  4784.6  325.12  4850.3  318.78
  4872.2  316.37  4888.5  313.88  4894.4  313.92  4923.2  310.98  4963.7  308.13
  4983.9  306.01  4991.9  303.69  5018.9  304.38  5034.5   308.5  5054.7  309.08
    5075  308.29  5096.2  309.09  5115.4  308.96  5145.6  310.22  5150.7  309.67
  5196.4   313.6    5214  315.93  5219.1  315.92  5282.5   322.4  5287.5  321.77
  5307.7  323.69  5327.9  324.59  5345.8  325.04  5350.9  324.29  5380.3  325.81
#Mann= 5 ,-1 , 0
  4688.8     .17       0  4963.7     .09       0  5034.5     .17       0
  5054.7     .15       0  5096.2     .17       0
Bank Sta=4963.7,5034.5
XS Rating Curve= 0 ,0
Exp/Cntr=0.3,0.1

Type RM Length L Ch R = 1 ,2804    ,440,440,440
BEGIN DESCRIPTION:
WEST GUM BRANCH 6.0
END DESCRIPTION:
XS GIS Cut Line= 3
      3730817.87     10223561.06      3730537.79     10223733.48
      3730017.82     10223861.08
#Sta/Elev= 30
  4671.1  325.37  4694.2   324.2  4700.1  322.74  4736.8  320.45  4794.8  314.83
  4810.2  313.04  4816.1  310.08  4823.8  309.65  4831.5  307.58  4846.9   310.8
  4852.7  310.91  4904.8  308.59  4910.7  309.65  4926.1  307.14  4941.2  308.54
  4968.7  307.85  5010.9  302.95  5015.3  302.95  5020.5  306.23  5030.8  308.58
  5061.7  309.59  5093.7  308.61  5154.4  307.18  5226.6  307.38  5257.4   307.5
  5345.7  314.49  5360.3  314.38  5470.4  324.39  5475.6  323.95  5535.4  328.48
#Mann= 5 ,-1 , 0
  4671.1     .17       0  4968.7     .09       0  5030.8     .17       0
  5093.7     .15       0  5226.6     .17       0
#XS Ineff= 1 ,-1
    4805  4852.7  310.91
Permanent Ineff=
       F
Bank Sta=4968.7,5030.8
XS Rating Curve= 0 ,0
Exp/Cntr=0.3,0.1

Type RM Length L Ch R = 1 ,2364    ,486,486,486
BEGIN DESCRIPTION:
WEST GUM BRANCH 5.0
END DESCRIPTION:
XS GIS Cut Line= 3
       3730717.9     10223361.08       3730461.8     10223321.12
      3730021.35     10223293.67
#Sta/Elev= 30
  4740.8   320.5  4801.6  317.98  4831.9  315.12  4837.6   314.1  4842.6  314.08
  4862.3   312.3  4892.7  309.05  4905.4   308.6    4923  306.28  4933.1   305.5
  4968.2  304.42  4996.9  301.32  4997.3  300.82  5001.7  300.82  5002.1  301.32
    5014  302.21    5024  304.81    5044  305.22  5064.1  304.61  5114.2  305.27
  5134.2  304.88  5184.3  305.26  5194.3   304.8  5224.4  306.88  5264.5  308.87
  5274.5  310.21  5294.5  310.32  5344.6  314.67  5406.2  318.82  5441.3  322.19
#Mann= 3 , 0 , 0
  4740.8     .17       0  4968.2     .09       0    5024     .17       0
Bank Sta=4968.2,5024
XS Rating Curve= 0 ,0
Exp/Cntr=0.3,0.1

Type RM Length L Ch R = 1 ,1878    ,426,426,426
BEGIN DESCRIPTION:
WEST GUM BRANCH 4.0
END DESCRIPTION:
XS GIS Cut Line= 3
      3731017.82     10222661.09      3730648.98     10222891.88
       3730267.9     10222761.09
#Sta/Elev= 30
  4564.9  337.43  4567.8  337.43  4572.5  335.97  4645.6  329.95  4666.8  327.49
  4688.1  326.15  4834.3  311.35  4870.8  308.67  4934.5  306.25  4955.7  304.83
  4965.1  304.02  4977.7  301.14  4986.3  299.89  5003.2  299.81  5017.5  301.29
  5022.8  300.98  5043.4  302.38  5175.6     301    5205  300.69  5228.4  299.62
  5228.8  299.12  5233.2  299.12  5233.6  299.62  5244.8  299.77  5254.9  300.25
  5262.3  301.62  5318.4   306.2  5324.8   307.4  5339.5  308.41  5402.9  314.96
#Mann= 7 ,-1 , 0
  4564.9     .17       0  4977.7     .09       0  5017.5     .15       0
  5175.6     .15       0  5228.4     .12       0  5233.6     .15       0
  5244.8     .17       0
Bank Sta=4977.7,5017.5
XS Rating Curve= 0 ,0
Exp/Cntr=0.3,0.1

Type RM Length L Ch R = 1 ,1452    ,542,542,542
BEGIN DESCRIPTION:
WEST GUM BRANCH 3.0
END DESCRIPTION:
XS GIS Cut Line= 3
      3730967.88     10222511.07       3730719.4     10222482.81
       3730257.6     10222486.28
#Sta/Elev= 30
  4690.5   334.6  4735.3  330.63  4740.9   329.6    4761  327.58  4861.6  313.93
    4922  307.02  4932.1   306.4  4938.8  305.36  4943.9  305.36  4962.1   300.1
  4972.1  298.67  4982.1  298.94  4989.5  297.49  4989.9  296.99  4994.3  296.99
  4994.7  297.49  5002.1  298.85  5012.1   299.3  5042.1  298.92  5062.1  299.34
  5072.1  298.71  5125.6  299.06  5232.1  298.08  5244.9  298.72  5282.1  300.83
  5292.1  302.12  5312.1  303.56  5370.9   311.4  5375.9   311.4  5402.4  314.57
#Mann= 5 ,-1 , 0
  4690.5     .17       0  4982.1     .09       0  5002.1     .17       0
  5125.6     .15       0  5244.9     .17       0
Bank Sta=4982.1,5002.1
XS Rating Curve= 0 ,0
Exp/Cntr=0.3,0.1

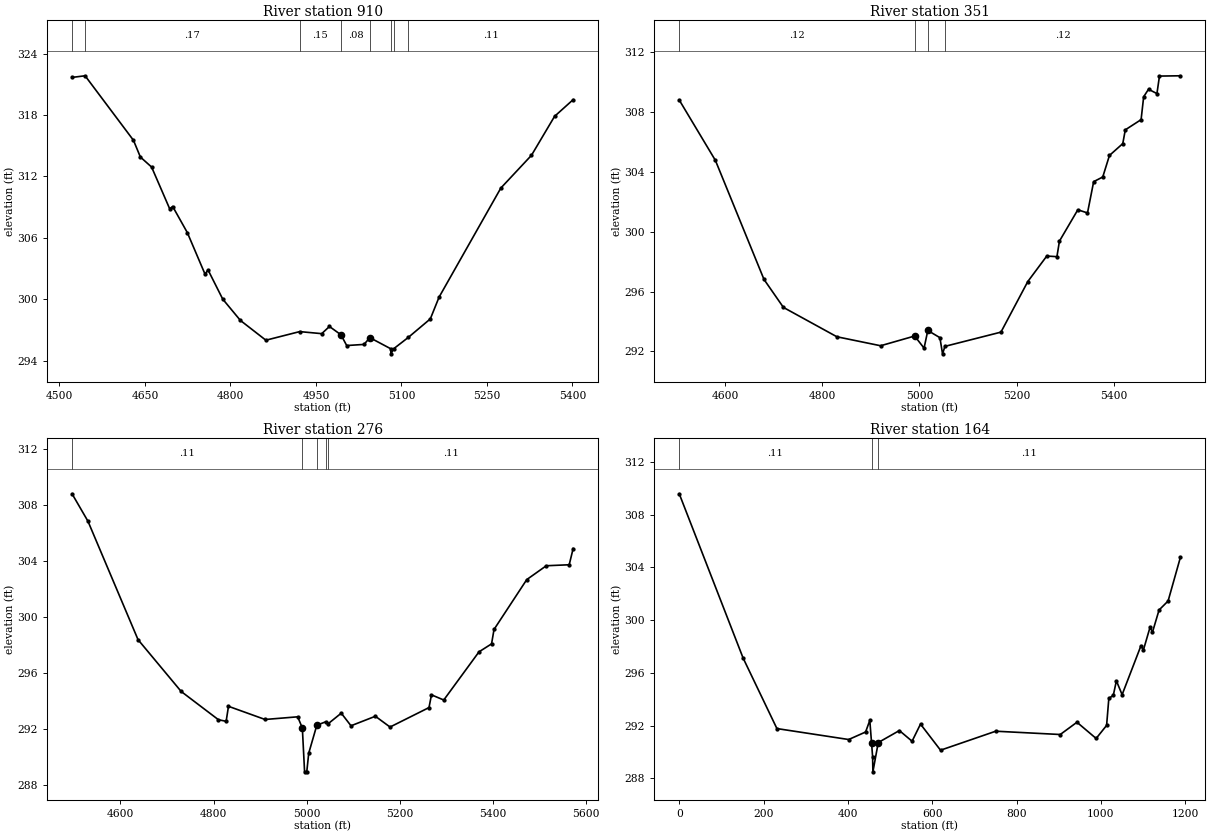
Type RM Length L Ch R = 1 ,910     ,559,559,559
BEGIN DESCRIPTION:
WEST GUM BRANCH 2.0
END DESCRIPTION:
XS GIS Cut Line= 3
       3730989.6     10222184.42      3730684.44     10222077.54
      3730135.66     10222165.96
#Sta/Elev= 30
    4522  321.67  4544.9  321.83  4629.8  315.53  4641.9   313.9  4661.6  312.92
  4693.3  308.85  4698.6  309.07  4724.3  306.52  4755.3  302.47  4760.6  302.88
  4786.4  300.03  4817.4  297.95  4862.1  296.02  4921.4  296.86  4960.1  296.66
  4973.6  297.36  4993.8  296.55  5003.9   295.5  5034.3  295.61  5044.5  296.27
    5081  295.19  5081.5  294.69  5086.4  295.19  5111.9  296.29  5150.6   298.1
    5166  300.23  5274.3  310.87  5328.1  314.07  5368.6  317.87  5401.2   319.5
#Mann= 8 ,-1 , 0
    4522     .11       0  4544.9     .17       0  4921.4     .15       0
  4993.8     .08       0  5044.5     .12       0    5081     .12       0
  5086.4     .15       0  5111.9     .11       0
Bank Sta=4993.8,5044.5
XS Rating Curve= 0 ,0
Exp/Cntr=0.3,0.1

Type RM Length L Ch R = 1 ,351     ,75,75,75
BEGIN DESCRIPTION:
Mapping XS 7559c494
END DESCRIPTION:
XS GIS Cut Line= 3
      3730972.24     10221618.01      3730478.52     10221610.41
      3729965.31     10221769.91
#Sta/Elev= 30
  4505.6  308.79    4580  304.76    4680  296.81    4720  294.94    4830  292.98
    4920  292.38    4990  293.03  5009.4  292.22  5017.1   293.4    5042  292.92
  5047.4  291.84  5052.4  292.34  5167.6  293.29  5222.9  296.67  5261.9  298.37
  5282.8  298.33    5288  299.37  5325.8  301.46  5345.7  301.25  5358.4  303.34
  5377.1  303.65  5390.9  305.09  5418.3  305.88  5423.5   306.8    5456  307.48
  5461.3  309.01  5471.3  309.51  5488.6  309.22  5493.8  310.39  5536.8  310.41
#Mann= 4 ,-1 , 0
  4505.6     .12       0    4990     .08       0  5017.1     .12       0
  5052.4     .12       0
Bank Sta=4990,5017.1
XS Rating Curve= 0 ,0
Exp/Cntr=0.3,0.1

Type RM Length L Ch R = 1 ,276     ,112,112,112
BEGIN DESCRIPTION:
WEST GUM BRANCH 1.0
END DESCRIPTION:
XS GIS Cut Line= 3
      3730981.97     10221508.42      3730478.68     10221535.18
       3729932.8     10221708.05
#Sta/Elev= 30
    4496  308.79  4530.2  306.83  4637.8  298.37  4730.5  294.67  4810.6  292.65
  4827.1  292.54  4832.1  293.61  4910.7  292.67  4980.8  292.86  4990.8  292.06
  4995.6  288.93  5000.3  288.93  5004.5  290.26  5021.9  292.26  5040.7   292.5
  5046.4  292.37  5074.4  293.12  5095.3  292.22  5147.7   292.9  5179.2  292.13
  5262.9  293.52  5268.2  294.43  5294.6  294.06  5370.3   297.5  5397.3  298.07
  5402.6   299.1  5472.9  302.66  5514.9  303.65  5564.1  303.72  5572.6  304.88
#Mann= 5 ,-1 , 0
    4496     .11       0  4990.8     .06       0  5021.9     .11       0
  5040.7     .15       0  5046.4     .11       0
Bank Sta=4990.8,5021.9
XS Rating Curve= 0 ,0
Exp/Cntr=0.3,0.1

Type RM Length L Ch R = 1 ,164     ,0,0,0
XS GIS Cut Line= 4
      3730989.04     10221462.15      3730367.95       10221427.
      3729990.35     10221570.23      3729907.01     10221709.55
#Sta/Elev= 30
       0  309.58   151.4  297.13   231.6  291.78   401.8  290.95   441.9  291.52
   451.9   292.4     456 290.699   458.5 289.661   459.2   288.5   471.9  290.72
     522  291.63   552.1  290.82   572.1  292.12   619.6  290.14   750.5  291.58
   903.5  291.33   943.1  292.26   988.6  291.03  1013.4  292.02  1018.7  294.07
  1029.3   294.3  1036.6   295.4  1050.2  294.35    1095  298.07  1100.8  297.75
  1116.4  299.46  1122.2  299.09  1137.8  300.77  1159.2  301.45  1188.3  304.75
#Mann= 3 , 0 , 0
       0     .11       0     456     .06       0   471.9     .11       0
Bank Sta=456,471.9
XS Rating Curve= 0 ,0
Exp/Cntr=0.3,0.1

Chan Stop Cuts=-1
Use User Specified Reach Order=0
Composite Channel Slope=5