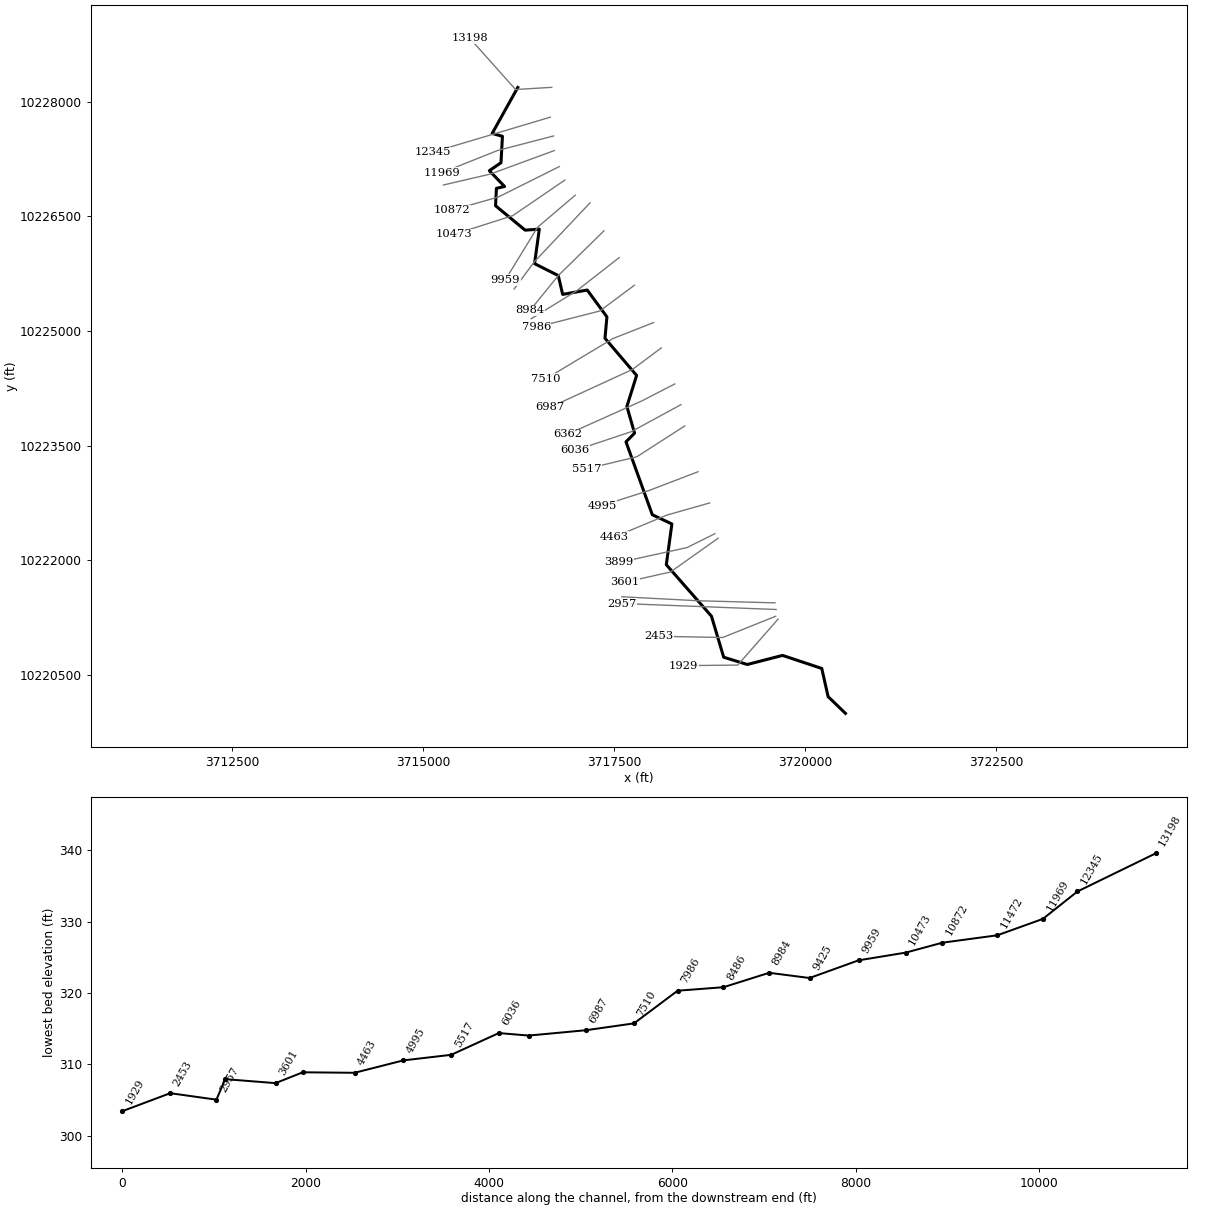
--- WEST ROCKY BRANCH.prj (project) ---

Proj Title=WEST ROCKY BRANCH Base Level Engineering
Current Plan=p01
Default Exp/Contr=0.3,0.1
English Units
Geom File=g01
Flow File=f01
Flow File=f02
Plan File=p01
Y Axis Title=Elevation
X Axis Title(PF)=Main Channel Distance
X Axis Title(XS)=Station
BEGIN DESCRIPTION:
WEST ROCKY BRANCH
END DESCRIPTION:
DSS Export Rating Curves= 0
DSS Export Rating Curve Sorted= 0
DSS Export Volume Flow Curves= 0
DXF OffsetX= 0
DXF OffsetY= 0
DXF ScaleX= 1
DXF ScaleY= 10

--- WEST ROCKY BRANCH.p01 (plan) ---

Plan Title=Multiple Run
Program Version=4.10
Short Identifier=Multiple
Geom File=g01
Flow File=f01
Subcritical Flow
K Sum by GR= 0
Std Step Tol= 0.01
Critical Tol= 0.01
Num of Std Step Trials= 20
Max Error Tol= 0.3
Flow Tol Ratio= 0.001
Split Flow NTrial= 30
Split Flow Tol= 0.02
Split Flow Ratio= 0.02
Log Output Level= 0
Friction Slope Method= 1
Unsteady Friction Slope Method= 2
Unsteady Bridges Friction Slope Method= 1
Parabolic Critical Depth
Global Vel Dist= 1 , 1 , 1
Global Log Level= 0
CheckData=True
Encroach Param=-1 ,0,0, 0
BEGIN DESCRIPTION:
Multiple Run
END DESCRIPTION:
Computation Interval=1HOUR
Output Interval=1HOUR
Run HTab= 0
Run UNet= 0
Run PostProcess= 0
Run WQNet= 0
UNET Theta= 1
UNET Theta Warmup= 1
UNET ZTol= 0.02
UNET ZSATol= 0.05
UNET MxIter= 20
UNET MaxInSteps= 0
UNET DtIC= 0
UNET DtMin= 0
UNET MaxCRTS= 20
UNET WFStab= 2
UNET SFStab= 1
UNET WFX= 1
UNET SFX= 1
UNET DSS MLevel= 4
UNET DZMax Abort= 100
UNET Convert EG Bridges= 0
UNET Use Existing IB Tables=-1
UNET Froude Reduction=False
UNET Froude Limit= 1
UNET Froude Power= 10
UNET Time Slicing=0,0, 5
UNET Junction Losses=0
Instantaneous Interval=1HOUR
Write IC File= 0
Write IC File at Sim End=0
Echo Input=False
Echo Parameters=False
Echo Output=False
Write Detailed= 0
WQ AD Non Conservative
WQ ULTIMATE=-1
WQ Max Comp Step=1HOUR
WQ Output Interval=15MIN
WQ Output Selected Increments= 0
WQ Output face flow=0
WQ Output face velocity=0
WQ Output face area=0
WQ Output face dispersion=0
WQ Output cell volume=0
WQ Output cell surface area=0
WQ Output cell continuity=0
WQ Output cumulative cell continuity=0
WQ Output face conc=0
WQ Output face dconc_dx=0
WQ Output face courant=0
WQ Output face peclet=0
WQ Output face adv mass=0
WQ Output face disp mass=0
WQ Output cell mass=0
WQ Output cell source sink temp=0
WQ Output cell source sink nsm=0
WQ Output MaxMinRange=-1
WQ Daily Max Min Mean=-1
WQ Daily Range=0
WQ Daily Time=0
WQ Create Restart=0
WQ Fixed Restart=0
WQ System Summary=0
WQ Use Fixed Temperature=0
Sorting and Armoring Iterations= 10
XS Update Threshold= 0.02
Hydraulics Update Threshold= 0.02
Energy Slope Method= 1
Volume Change Method= 0
XS Weighting Method= 0
Number of US Weighted Cross Sections= 1
Number of DS Weighted Cross Sections= 1
Upstream XS Weight=0.25
Main XS Weight=0.5
Downstream XS Weight=0.25
Number of DS XS's Weighted with US Boundary= 1
Upstream Boundary Weight= 1
Weight of XSs Associated with US Boundary= 0
Number of US XS's Weighted with DS Boundary= 1
Downstream Boundary Weight= 0.5
Weight of XSs Associated with DS Boundary= 0.5
Sediment Output Level= 4
Mass or Volume Output= 0
Output Increment Type= 1
Profile and TS Output Increment= 10
XS Output Flag= 0
XS Output Increment= 10
Disregard all LS=0
Disregard all Conn=0
Disregard all Breaches=0
Disregard all Pumps=0

--- WEST ROCKY BRANCH.f01 (steady flow) ---

Flow Title=Multiple
Program Version=4.10
Number of Profiles= 7
Profile Names=10-year,25-year,50-year,1pct_min,100-year,1pct_plu,500-year
River Rch & RM=WEST ROCKY BRANC,Reach-1         ,13198
     747    1018    1380     615    1856    5605    3476
River Rch & RM=WEST ROCKY BRANC,Reach-1         ,10872
    1042    1442    1978     890    2687    8115    5132
River Rch & RM=WEST ROCKY BRANC,Reach-1         ,2453
    1013    1396    1908     855    2582    7798    4897
Boundary for River Rch & Prof#=WEST ROCKY BRANC,Reach-1         , 1
Up Type= 0
Dn Type= 3
Dn Slope=0.005
Boundary for River Rch & Prof#=WEST ROCKY BRANC,Reach-1         , 2
Up Type= 0
Dn Type= 3
Dn Slope=0.005
Boundary for River Rch & Prof#=WEST ROCKY BRANC,Reach-1         , 3
Up Type= 0
Dn Type= 3
Dn Slope=0.005
Boundary for River Rch & Prof#=WEST ROCKY BRANC,Reach-1         , 4
Up Type= 0
Dn Type= 3
Dn Slope=0.005
Boundary for River Rch & Prof#=WEST ROCKY BRANC,Reach-1         , 5
Up Type= 0
Dn Type= 3
Dn Slope=0.005
Boundary for River Rch & Prof#=WEST ROCKY BRANC,Reach-1         , 6
Up Type= 0
Dn Type= 3
Dn Slope=0.005
Boundary for River Rch & Prof#=WEST ROCKY BRANC,Reach-1         , 7
Up Type= 0
Dn Type= 3
Dn Slope=0.005
DSS Import GetInterval= 0
DSS Import GetPeak= 0
DSS Import FillOption= 0

--- WEST ROCKY BRANCH.f02 (steady flow) ---

Flow Title=Orig_BLE_Flow
Program Version=4.10
Number of Profiles= 7
Profile Names=10-year,25-year,50-year,1pct_min,100-year,1pct_plu,500-year
River Rch & RM=WEST ROCKY BRANC,Reach-1         ,13198
     747     998    1200     473    1428    4313    2021
River Rch & RM=WEST ROCKY BRANC,Reach-1         ,10872
    1042    1414    1720     684    2067    6241    2984
River Rch & RM=WEST ROCKY BRANC,Reach-1         ,2453
    1013    1369    1659     658    1986    5999    2847
Boundary for River Rch & Prof#=WEST ROCKY BRANC,Reach-1         , 1
Up Type= 0
Dn Type= 3
Dn Slope=0.005
Boundary for River Rch & Prof#=WEST ROCKY BRANC,Reach-1         , 2
Up Type= 0
Dn Type= 3
Dn Slope=0.005
Boundary for River Rch & Prof#=WEST ROCKY BRANC,Reach-1         , 3
Up Type= 0
Dn Type= 3
Dn Slope=0.005
Boundary for River Rch & Prof#=WEST ROCKY BRANC,Reach-1         , 4
Up Type= 0
Dn Type= 3
Dn Slope=0.005
Boundary for River Rch & Prof#=WEST ROCKY BRANC,Reach-1         , 5
Up Type= 0
Dn Type= 3
Dn Slope=0.005
Boundary for River Rch & Prof#=WEST ROCKY BRANC,Reach-1         , 6
Up Type= 0
Dn Type= 3
Dn Slope=0.005
Boundary for River Rch & Prof#=WEST ROCKY BRANC,Reach-1         , 7
Up Type= 0
Dn Type= 3
Dn Slope=0.005
DSS Import GetInterval= 0
DSS Import GetPeak= 0
DSS Import FillOption= 0

--- WEST ROCKY BRANCH.g01 (geometry) ---

Geom Title=Existing Conditions
Program Version=4.10

River Reach=WEST ROCKY BRANC,Reach-1
Reach XY= 30
      3716240.09     10228187.05      3715905.07     10227585.57
      3716039.61     10227547.81      3716020.63     10227202.54
      3715868.29      10227097.7      3716067.71     10226891.59
      3715960.56     10226867.23      3715949.55     10226639.19
      3716336.49     10226319.92       3716521.9     10226333.12
      3716459.88     10225881.62      3716770.31     10225725.56
      3716827.38     10225479.39      3717149.33     10225536.18
       3717406.6     10225185.23      3717381.32     10224905.24
      3717795.16     10224419.03      3717668.02     10224012.95
      3717768.18     10223663.71      3717656.15     10223549.84
       3718000.8     10222595.95      3718256.71     10222475.35
      3718183.85     10221942.12      3718774.45     10221269.09
      3718934.87     10220731.51      3719243.26     10220636.48
      3719704.83     10220755.33      3720218.26     10220584.48
      3720301.05     10220216.12      3720528.17     10219996.84

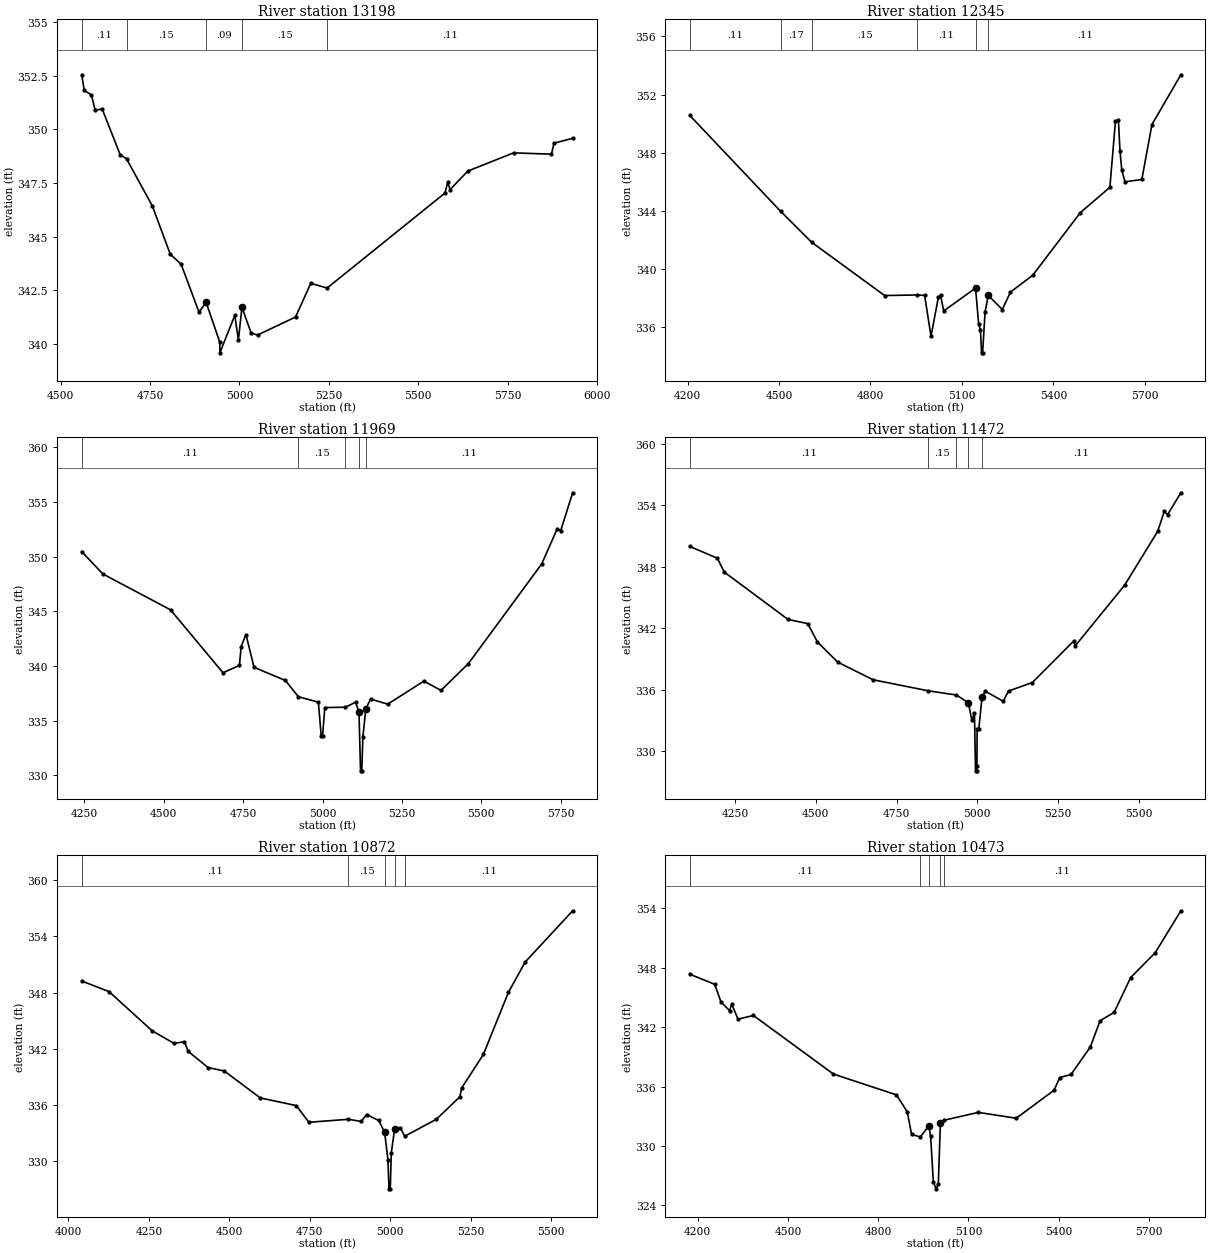
Type RM Length L Ch R = 1 ,13198   ,853,853,853
BEGIN DESCRIPTION:
WEST ROCKY BRANCH 23.0
END DESCRIPTION:
XS GIS Cut Line= 3
      3716685.27      10228188.9      3716211.74     10228160.09
      3715613.11     10228829.98
#Sta/Elev= 30
    4559  352.54  4566.4  351.81  4586.5   351.6  4596.5   350.9  4616.5  350.94
  4666.6  348.82  4684.6  348.62  4756.8  346.42  4806.9  344.17  4836.9  343.72
    4887  341.48  4907.1  341.93  4945.1  340.08  4945.4  339.58  4987.2  341.33
  4997.2  340.18  5007.2   341.7  5032.9   340.5  5050.8  340.41    5157  341.25
  5199.6  342.82  5245.3   342.6  5574.9  347.03  5582.4  347.53  5589.2  347.19
  5638.5  348.05  5766.4   348.9  5872.5  348.84  5879.6  349.35  5931.8  349.58
#Mann= 5 ,-1 , 0
    4559     .11       0  4684.6     .15       0  4907.1     .09       0
  5007.2     .15       0  5245.3     .11       0
Bank Sta=4907.1,5007.2
XS Rating Curve= 0 ,0
Exp/Cntr=0.3,0.1

Type RM Length L Ch R = 1 ,12345   ,376,376,376
BEGIN DESCRIPTION:
WEST ROCKY BRANCH 22.0
END DESCRIPTION:
XS GIS Cut Line= 3
        3716666.     10227798.42      3715990.82     10227597.11
      3715122.11     10227338.99
#Sta/Elev= 30
  4207.4  350.56  4505.2  343.97  4607.1  341.84  4846.4  338.18  4953.2  338.22
  4977.6  338.19  4998.5  335.38  5022.8  338.07  5029.8   338.2  5040.2  337.12
  5144.6  338.69    5155  336.19  5160.8  335.82  5164.3  334.24  5167.8  334.24
  5175.9  337.04  5186.3  338.19  5232.4  337.22  5259.3  338.42    5332  339.57
  5488.8  343.89  5585.3  345.62  5603.6  350.16  5613.3  350.22  5618.5  348.12
  5624.4   346.8  5634.9     346  5690.1  346.16  5723.3  349.94  5818.2  353.36
#Mann= 6 ,-1 , 0
  4207.4     .11       0  4505.2     .17       0  4607.1     .15       0
  4953.2     .11       0  5144.6     .06       0  5186.3     .11       0
Bank Sta=5144.6,5186.3
XS Rating Curve= 0 ,0
Exp/Cntr=0.3,0.1

Type RM Length L Ch R = 1 ,11969   ,497,497,497
BEGIN DESCRIPTION:
WEST ROCKY BRANCH 21.0
END DESCRIPTION:
XS GIS Cut Line= 3
      3716708.82     10227552.58      3715974.44     10227361.64
      3715242.68     10227069.81
#Sta/Elev= 30
  4241.2  350.46  4308.1  348.41  4521.2  345.13  4686.5  339.37  4738.2  340.05
  4743.6  341.77  4758.8  342.87  4784.2  339.87  4882.8  338.67  4923.9  337.18
  4986.9  336.68  4995.7  333.59    5000  333.59  5007.1  336.19    5072  336.22
    5104  336.68  5114.8  335.75  5119.6   330.4  5123.5   330.4    5127   333.5
  5136.3  336.08  5151.2  336.97  5205.1   336.5  5319.3  338.61  5373.1  337.76
  5459.3  340.21  5690.3  349.33  5738.9  352.53  5749.9  352.36  5787.8  355.84
#Mann= 5 ,-1 , 0
  4241.2     .11       0  4923.9     .15       0    5072     .11       0
  5114.8     .09       0  5136.3     .11       0
Bank Sta=5114.8,5136.3
XS Rating Curve= 0 ,0
Exp/Cntr=0.3,0.1

Type RM Length L Ch R = 1 ,11472   ,600,600,600
BEGIN DESCRIPTION:
WEST ROCKY BRANCH 20.0
END DESCRIPTION:
XS GIS Cut Line= 3
      3716717.83     10227361.06      3715882.26     10227054.01
      3715267.87     10226911.08
#Sta/Elev= 30
  4109.8     350    4195  348.85  4216.4   347.5  4413.8  342.88  4474.8  342.47
  4505.2  340.67  4567.9  338.71  4677.4  336.99  4848.6  335.91  4935.7   335.5
  4972.7  334.74  4983.4  333.03  4991.4  333.76  4994.7   328.1  4998.7   328.1
    4999   328.6  4999.7  332.15  5004.8  332.15  5014.8  335.28  5025.1  335.87
  5080.4  334.89  5096.9  335.89  5170.7  336.72  5298.5  340.76  5303.6   340.3
  5456.3  346.21  5558.9  351.47  5579.5  353.42  5589.7  353.11  5630.8  355.24
#Mann= 5 ,-1 , 0
  4109.8     .11       0  4848.6     .15       0  4935.7     .11       0
  4972.7     .06       0  5014.8     .11       0
Bank Sta=4972.7,5014.8
XS Rating Curve= 0 ,0
Exp/Cntr=0.3,0.1

Type RM Length L Ch R = 1 ,10872   ,399,399,399
BEGIN DESCRIPTION:
WEST ROCKY BRANCH 19.0
END DESCRIPTION:
XS GIS Cut Line= 3
      3716783.59      10227151.7      3715987.26     10226754.42
      3715376.14     10226579.82
#Sta/Elev= 30
  4041.1  349.23  4126.1   348.1  4260.4  343.91  4327.5  342.59  4360.4  342.73
  4372.2  341.72  4433.8     340  4484.1  339.63    4596  336.76  4707.9  335.94
    4747  334.16  4869.8  334.48  4909.3  334.25  4926.1  334.98  4964.1  334.35
  4982.4  333.09  4992.7  330.15  4995.9  327.06  4999.9  327.06  5003.2  330.92
  5013.6  333.47  5031.7  333.53  5044.8  332.67  5143.5  334.49  5216.3  336.89
  5221.6  337.81  5289.1  341.39  5367.2  348.03  5419.2  351.26  5566.6  356.72
#Mann= 5 ,-1 , 0
  4041.1     .11       0  4869.8     .15       0  4982.4     .09       0
  5013.6     .15       0  5044.8     .11       0
Bank Sta=4982.4,5013.6
XS Rating Curve= 0 ,0
Exp/Cntr=0.3,0.1

Type RM Length L Ch R = 1 ,10473   ,514,514,514
BEGIN DESCRIPTION:
WEST ROCKY BRANCH 18.0
END DESCRIPTION:
XS GIS Cut Line= 3
       3716856.7     10226975.36      3716174.43     10226509.94
       3715406.5      10226264.5
#Sta/Elev= 30
  4174.1  347.34  4256.5  346.33  4277.5  344.55  4305.9  343.67  4313.4  344.32
  4334.3   342.8  4385.2  343.18  4651.4  337.26  4860.8  335.16  4896.7  333.45
  4911.1  331.17  4940.3  330.91  4968.5  332.03  4974.5  330.98  4983.4  326.36
  4992.9  325.67    5000  326.17  5006.9   332.3  5017.7  332.59  5132.9  333.39
  5258.9   332.8  5384.8  335.63  5403.7  336.91  5441.2  337.22  5505.5  340.01
  5537.7  342.65  5584.3  343.48  5639.4  347.01  5720.8  349.51  5806.2  353.75
#Mann= 5 ,-1 , 0
  4174.1     .11       0  4940.3     .15       0  4968.5     .09       0
  5006.9     .15       0  5017.7     .11       0
Bank Sta=4968.5,5006.9
XS Rating Curve= 0 ,0
Exp/Cntr=0.3,0.1

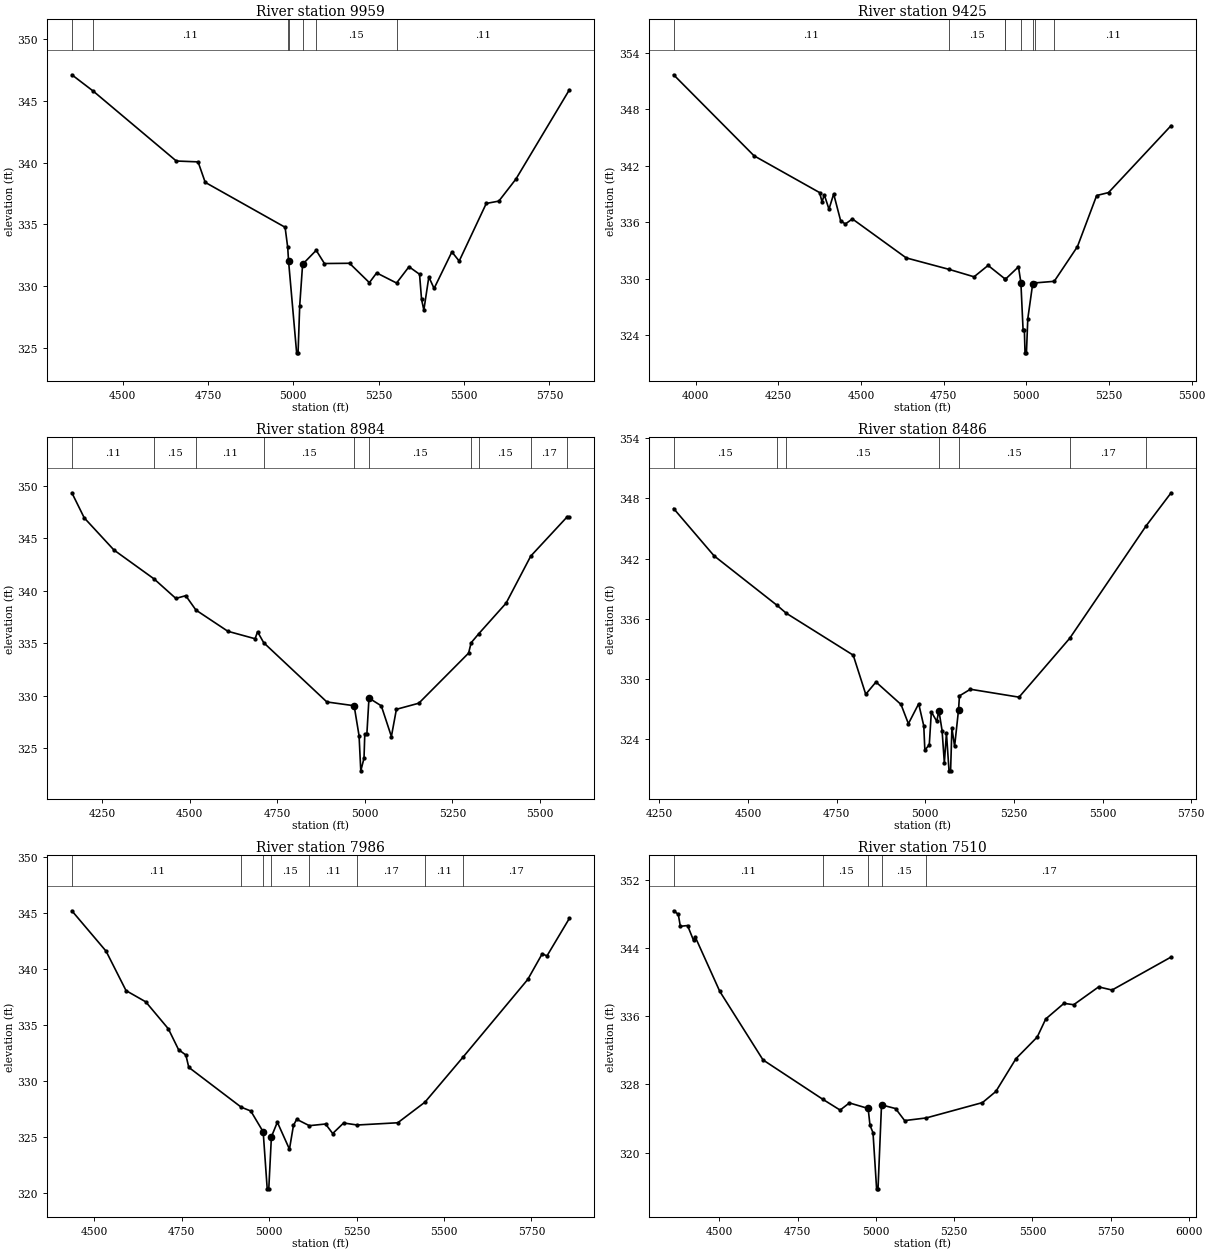
Type RM Length L Ch R = 1 ,9959    ,534,534,534
BEGIN DESCRIPTION:
WEST ROCKY BRANCH 17.0
END DESCRIPTION:
XS GIS Cut Line= 3
      3716992.09      10226777.6      3716498.57     10226357.13
      3716076.35     10225667.69
#Sta/Elev= 30
  4351.5  347.13  4413.9  345.81  4657.4  340.14  4721.1  340.07    4742  338.41
  4975.9  334.77  4983.6  333.13    4986 332.048  5009.7  324.59  5013.9  324.59
  5018.7  328.41  5027.2  331.77    5067   332.9  5091.1  331.83  5164.6  331.85
  5222.7  330.28    5244  331.07  5302.3  330.25  5338.7  331.57  5369.6  330.96
  5375.5  328.92  5382.2  328.06  5396.8  330.74  5412.2  329.81  5464.3  332.77
  5485.7  332.03    5565   336.7  5601.8  336.89  5651.9  338.68  5808.3  345.91
#Mann= 7 ,-1 , 0
  4351.5     .17       0  4413.9     .11       0  4983.6     .11       0
    4986     .06       0  5027.2     .11       0    5067     .15       0
  5302.3     .11       0
Bank Sta=4986,5027.2
XS Rating Curve= 0 ,0
Exp/Cntr=0.3,0.1

Type RM Length L Ch R = 1 ,9425    ,441,441,441
BEGIN DESCRIPTION:
WEST ROCKY BRANCH 16.0
END DESCRIPTION:
XS GIS Cut Line= 3
      3717185.61     10226677.34      3716457.59     10225906.39
      3716192.49     10225550.55
#Sta/Elev= 30
  3933.8  351.66    4177  343.05  4375.2  339.14  4382.5  338.16  4389.4   338.9
  4403.5  337.38  4417.7  338.99  4438.7  336.16  4452.9   335.8  4474.3  336.34
    4637   332.2  4766.6  330.98  4842.1  330.19  4884.6   331.4  4934.5     330
  4936.2  329.91  4976.4  331.25  4983.7  329.58  4990.3  324.56  4994.2  324.56
  4996.2  322.11  5000.5  322.11  5004.6  325.74  5019.2   329.4  5025.7  329.54
  5084.5  329.71  5154.7   333.4  5212.8  338.83  5248.6  339.14  5437.9  346.26
#Mann= 8 ,-1 , 0
  3933.8     .11       0  4766.6     .15       0  4934.5     .11       0
  4936.2     .15       0  4983.7     .09       0  5019.2     .12       0
  5025.7     .15       0  5084.5     .11       0
Bank Sta=4983.7,5019.2
XS Rating Curve= 0 ,0
Exp/Cntr=0.3,0.1

Type RM Length L Ch R = 1 ,8984    ,498,498,498
BEGIN DESCRIPTION:
WEST ROCKY BRANCH 15.0
END DESCRIPTION:
XS GIS Cut Line= 3
      3717367.86     10226311.08      3716770.31     10225725.56
      3716402.27     10225271.73
#Sta/Elev= 30
  4163.4  349.32  4198.8  346.93  4283.6  343.87  4398.1  341.12  4460.4  339.26
  4488.7  339.52  4517.8  338.15    4609  336.13  4686.7  335.42  4693.8  336.08
  4711.4  335.04  4891.7   329.4  4969.6  329.04  4983.7  326.18  4988.6  322.84
  4997.8  324.04    5000  326.31  5005.9  326.31    5012  329.77  5047.2  329.03
    5076  326.11  5090.3   328.7  5154.3  329.28  5296.5  334.05  5303.8  335.04
  5325.9  335.91  5403.6  338.81    5474  343.29  5578.9  347.06  5584.3     347
#Mann= 10 ,-1 , 0
  4163.4     .11       0  4398.1     .15       0  4517.8     .11       0
  4711.4     .15       0  4969.6     .09       0    5012     .15       0
  5303.8     .11       0  5325.9     .15       0    5474     .17       0
  5578.9     .11       0
Bank Sta=4969.6,5012
XS Rating Curve= 0 ,0
Exp/Cntr=0.3,0.1

Type RM Length L Ch R = 1 ,8486    ,500,500,500
BEGIN DESCRIPTION:
WEST ROCKY BRANCH 14.0
END DESCRIPTION:
XS GIS Cut Line= 3
      3717567.83     10225961.06      3717008.16      10225524.5
      3716417.86     10225161.08
#Sta/Elev= 30
  4290.2  346.99  4404.3  342.27  4582.3  337.32  4607.6  336.55  4796.7  332.36
    4832  328.46  4860.9  329.68  4931.5  327.44  4952.3  325.52  4981.3  327.51
  4995.7   325.3  4998.7  322.89  5011.2  323.42    5017   326.7  5032.4  325.76
  5038.3  326.83  5047.3  324.84  5053.7  321.61  5059.6  324.59  5066.9  320.82
  5071.3  320.82    5075   325.1  5082.6  323.26  5093.7 326.908  5096.3   328.3
  5127.1  328.96  5264.3  328.17  5407.4  334.05  5622.7  345.26  5693.2  348.56
#Mann= 7 ,-1 , 0
  4290.2     .15       0  4582.3     .11       0  4607.6     .15       0
  5038.3     .09       0  5093.7     .15       0  5407.4     .17       0
  5622.7     .11       0
Bank Sta=5038.3,5093.7
XS Rating Curve= 0 ,0
Exp/Cntr=0.3,0.1

Type RM Length L Ch R = 1 ,7986    ,476,476,476
BEGIN DESCRIPTION:
WEST ROCKY BRANCH 13.0
END DESCRIPTION:
XS GIS Cut Line= 3
      3717766.32     10225599.19      3717314.25     10225262.28
      3716482.67     10225049.76
#Sta/Elev= 30
  4436.2  345.16  4534.1  341.55  4591.1  338.03  4647.4  337.03    4712  334.62
  4741.2  332.76  4762.1  332.28  4770.4  331.18  4920.4  327.62  4947.7  327.28
  4983.1  325.42  4994.6  320.33  4999.1  320.33  5006.6  324.98  5023.6  326.28
  5058.2  323.87  5069.6  325.99  5078.9  326.54    5115  325.97  5161.4  326.12
  5181.8  325.27    5213  326.21  5251.9  326.03  5367.8  326.23  5445.5  328.07
  5554.6   332.1  5739.4  339.03  5780.7  341.32  5794.3  341.13  5858.3  344.48
#Mann= 8 ,-1 , 0
  4436.2     .11       0  4920.4     .15       0  4983.1     .09       0
  5006.6     .15       0    5115     .11       0  5251.9     .17       0
  5445.5     .11       0  5554.6     .17       0
Bank Sta=4983.1,5006.6
XS Rating Curve= 0 ,0
Exp/Cntr=0.3,0.1

Type RM Length L Ch R = 1 ,7510    ,523,523,523
BEGIN DESCRIPTION:
WEST ROCKY BRANCH 12.0
END DESCRIPTION:
XS GIS Cut Line= 3
      3718017.82     10225111.06      3717485.07     10224901.27
      3716612.72     10224377.86
#Sta/Elev= 30
  4353.4  348.34  4368.3  347.93  4374.9  346.52    4398  346.61    4417  344.88
  4422.4  345.28    4501  338.89  4639.1  330.86  4830.4  326.24  4885.5  324.98
  4915.2  325.82  4975.1  325.17    4981  323.19  4990.6  322.33  5002.1  315.75
  5006.6  315.75  5017.8  325.59  5062.7  325.16  5091.7  323.75  5160.7  324.06
  5340.5  325.86  5383.2  327.16  5447.5  331.01  5515.4  333.54  5542.6  335.66
  5600.9  337.49    5632  337.33  5711.7  339.42  5754.5  339.05  5943.3  342.92
#Mann= 5 ,-1 , 0
  4353.4     .11       0  4830.4     .15       0  4975.1     .09       0
  5017.8     .15       0  5160.7     .17       0
Bank Sta=4975.1,5017.8
XS Rating Curve= 0 ,0
Exp/Cntr=0.3,0.1

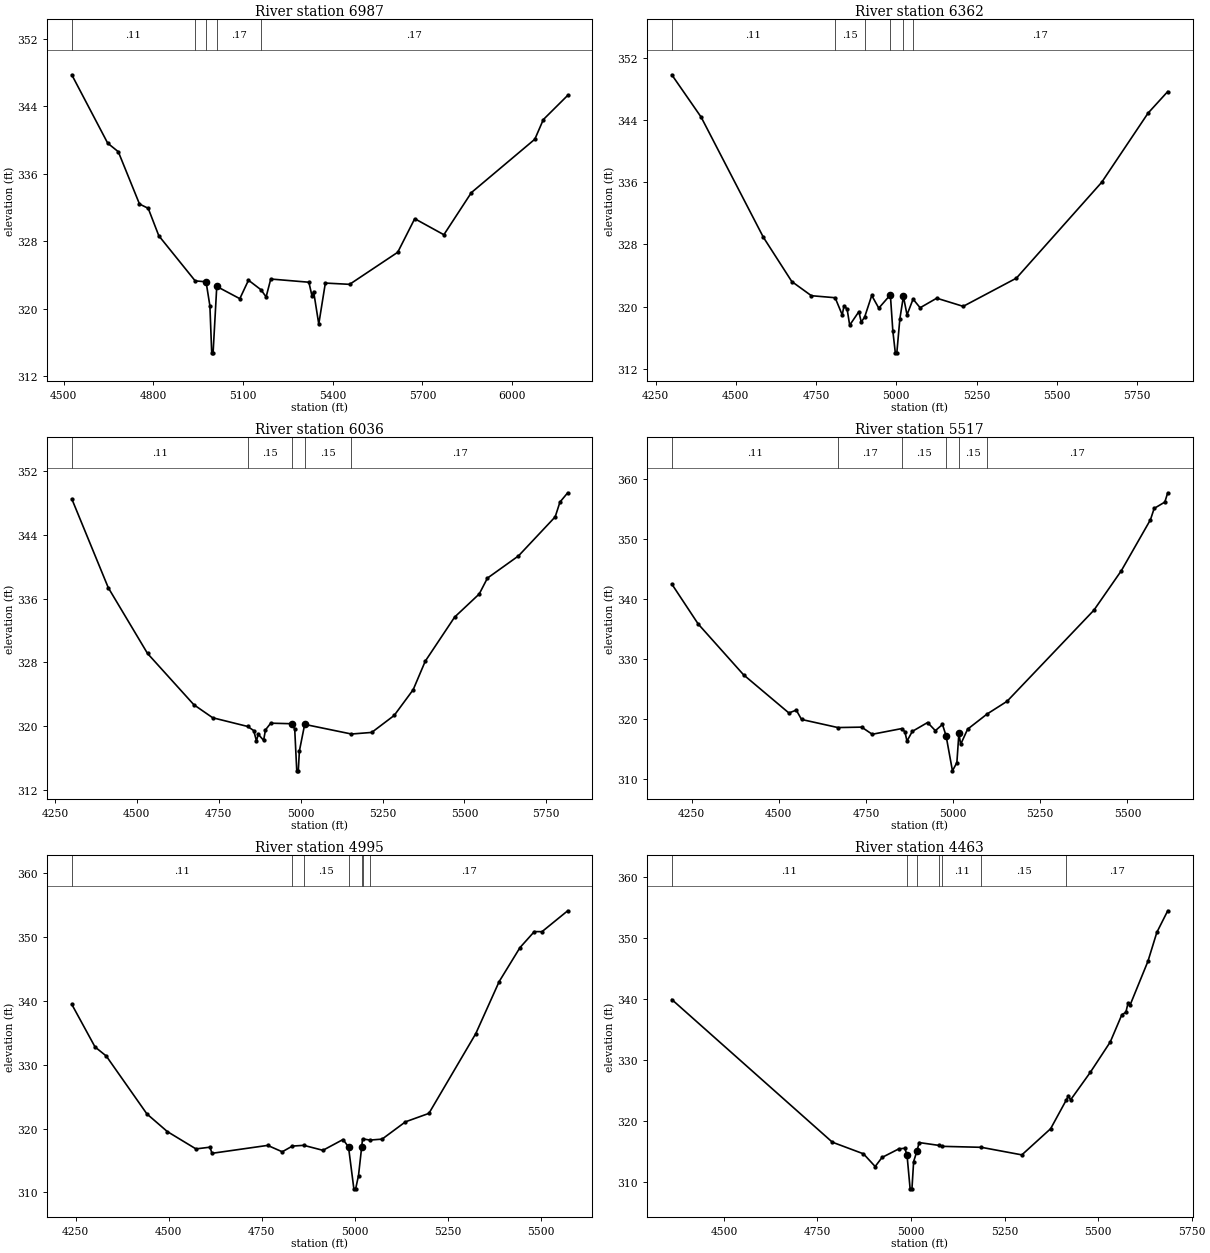
Type RM Length L Ch R = 1 ,6987    ,625,625,625
BEGIN DESCRIPTION:
WEST ROCKY BRANCH 11.0
END DESCRIPTION:
XS GIS Cut Line= 3
      3718117.89     10224778.88      3717738.98      10224496.1
      3716661.16     10224000.97
#Sta/Elev= 30
  4527.2  347.75  4647.4  339.64  4682.8  338.63  4753.7  332.43  4782.9  331.92
  4818.3  328.67    4940  323.32  4976.4  323.21  4989.2  320.37  4995.3  314.79
  4999.9  314.79  5012.2  322.66  5089.3  321.21  5118.3   323.4    5160  322.27
  5177.3  321.42  5192.8  323.54  5320.4  323.16  5330.7  321.53  5336.2  322.06
  5353.4   318.2  5375.4  323.06  5456.6  322.91  5617.5  326.71  5674.4  330.69
  5771.9  328.79  5863.8  333.78  6076.1  340.11  6104.6  342.44  6186.1  345.31
#Mann= 5 ,-1 , 0
  4527.2     .11       0    4940     .17       0  4976.4     .09       0
  5012.2     .17       0    5160     .17       0
Bank Sta=4976.4,5012.2
XS Rating Curve= 0 ,0
Exp/Cntr=0.3,0.1

Type RM Length L Ch R = 1 ,6362    ,326,326,326
BEGIN DESCRIPTION:
WEST ROCKY BRANCH 10.0
END DESCRIPTION:
XS GIS Cut Line= 3
      3718294.97     10224307.53      3717865.27     10224086.17
      3716896.48     10223651.25
#Sta/Elev= 30
  4300.4  349.81  4391.9  344.36  4585.7  328.91  4674.4  323.21  4735.3  321.39
  4809.4  321.13  4831.5  318.92    4837  320.08  4846.7  319.67  4854.7   317.6
  4883.4  319.34  4890.6  318.01  4901.1  318.61  4923.4  321.42  4945.4  319.79
  4981.5   321.5  4989.2  316.85  4996.9  314.04  5001.6  314.04  5011.1  318.42
  5022.1   321.3  5033.4  318.93  5052.2  320.95  5074.2  319.84    5126  321.07
  5208.4  320.02  5374.2  323.65    5640  335.98  5784.5  344.88  5845.7  347.65
#Mann= 6 ,-1 , 0
  4300.4     .11       0  4809.4     .15       0  4901.1     .15       0
  4981.5     .09       0  5022.1     .15       0  5052.2     .17       0
Bank Sta=4981.5,5022.1
XS Rating Curve= 0 ,0
Exp/Cntr=0.3,0.1

Type RM Length L Ch R = 1 ,6036    ,519,519,519
BEGIN DESCRIPTION:
WEST ROCKY BRANCH 9.0
END DESCRIPTION:
XS GIS Cut Line= 3
      3718375.73     10224036.71      3717724.65     10223682.52
      3716991.58     10223438.17
#Sta/Elev= 30
  4301.4  348.52  4412.9  337.36  4532.6  329.12  4674.2  322.68  4731.6  321.05
  4838.2  319.96  4856.8  319.44  4865.1  318.15  4870.8  318.98    4887  318.21
  4892.7  319.53  4908.8  320.37  4974.3   320.3    4982  319.61  4988.2  314.39
  4992.9  314.39  4996.2  316.88  5012.4  320.22  5155.1  319.01  5217.1  319.21
  5285.6  321.34  5343.6  324.57  5380.5  328.15  5470.1  333.68  5545.2  336.58
  5570.2  338.57  5665.1  341.36  5777.1  346.26  5791.6  348.11  5815.3  349.28
#Mann= 5 ,-1 , 0
  4301.4     .11       0  4838.2     .15       0  4974.3     .09       0
  5012.4     .15       0  5155.1     .17       0
Bank Sta=4974.3,5012.4
XS Rating Curve= 0 ,0
Exp/Cntr=0.3,0.1

Type RM Length L Ch R = 1 ,5517    ,522,522,522
BEGIN DESCRIPTION:
WEST ROCKY BRANCH 8.0
END DESCRIPTION:
XS GIS Cut Line= 3
      3718425.14     10223758.02      3717797.57     10223354.39
      3717139.78      10223195.8
#Sta/Elev= 30
  4192.8   342.5  4268.6  335.83  4398.7  327.36  4528.8  320.99  4549.9  321.47
  4565.1  319.91  4669.3  318.56  4737.5  318.63  4767.9  317.44  4852.6  318.39
  4861.6  317.85  4867.6   316.3  4882.8  317.92  4926.7   319.4    4949  318.04
  4969.4  319.08  4979.8  317.16    4998  311.34  5010.7  312.71  5016.5   317.6
  5021.6  315.77  5041.5  318.29  5097.7  320.83  5154.7  322.94  5403.9  338.14
  5482.6  344.73  5566.1  353.23  5576.7  355.11  5607.3  356.17  5615.6  357.72
#Mann= 6 ,-1 , 0
  4192.8     .11       0  4669.3     .17       0  4852.6     .15       0
  4979.8     .09       0  5016.5     .15       0  5097.7     .17       0
Bank Sta=4979.8,5016.5
XS Rating Curve= 0 ,0
Exp/Cntr=0.3,0.1

Type RM Length L Ch R = 1 ,4995    ,532,532,532
BEGIN DESCRIPTION:
WEST ROCKY BRANCH 7.0
END DESCRIPTION:
XS GIS Cut Line= 3
      3718599.68      10223159.1      3717953.82     10222911.69
      3717342.34     10222716.53
#Sta/Elev= 30
  4239.5  339.44  4302.1  332.76  4332.2  331.35  4441.6  322.28  4496.3  319.53
  4573.4  316.81  4611.1  317.08  4616.5  316.12  4766.2  317.36  4805.4  316.36
  4832.6  317.25  4863.3  317.37  4914.8  316.59  4968.9  318.28  4983.6  317.12
    4998  310.56  5002.8  310.56  5010.5  312.64    5019   317.1  5021.4  318.39
  5040.9  318.19  5073.9  318.34  5136.8  321.05  5199.8  322.37  5325.8  334.85
  5388.8  343.01  5444.7  348.32  5483.2  350.82  5503.9  350.81    5573  354.08
#Mann= 7 ,-1 , 0
  4239.5     .11       0  4832.6     .17       0  4863.3     .15       0
  4983.6     .09       0    5019     .12       0  5021.4     .15       0
  5040.9     .17       0
Bank Sta=4983.6,5019
XS Rating Curve= 0 ,0
Exp/Cntr=0.3,0.1

Type RM Length L Ch R = 1 ,4463    ,564,564,564
BEGIN DESCRIPTION:
WEST ROCKY BRANCH 6.0
END DESCRIPTION:
XS GIS Cut Line= 3
       3718750.7     10222750.23      3718190.79     10222591.37
      3717504.67     10222305.49
#Sta/Elev= 30
  4360.7  339.87  4789.8  316.47    4873  314.56  4904.2  312.48  4922.6  313.97
  4967.6  315.38  4983.1  315.47  4989.2  314.45  4997.6  308.82  5002.5  308.82
    5007   313.3    5016 315.037  5021.7  316.41  5073.9  315.95  5082.6  315.79
  5187.9  315.63  5296.2  314.39  5373.1  318.68  5415.5  323.45  5420.8  324.11
  5426.2  323.39  5479.3  327.94  5532.4   332.9  5563.4  337.37  5574.2  337.78
  5580.1  339.32  5585.5  338.97  5633.1  346.13    5657  350.89    5686  354.42
#Mann= 7 ,-1 , 0
  4360.7     .11       0  4989.2     .06       0    5016     .11       0
  5073.9     .15       0  5082.6     .11       0  5187.9     .15       0
  5415.5     .17       0
Bank Sta=4989.2,5016
XS Rating Curve= 0 ,0
Exp/Cntr=0.3,0.1

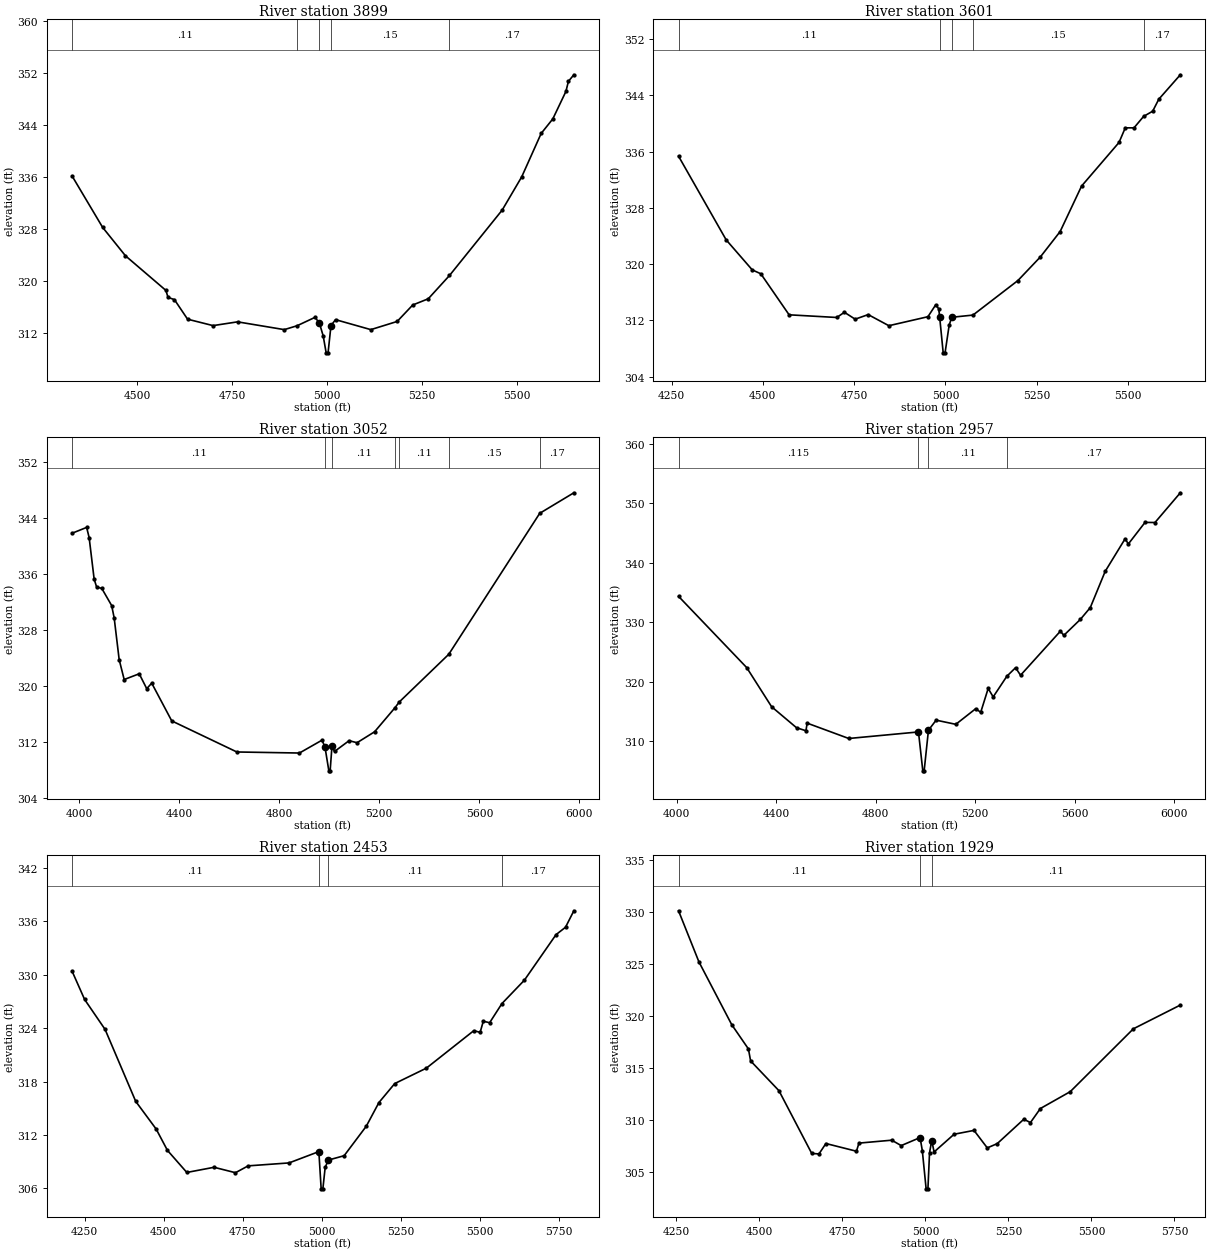
Type RM Length L Ch R = 1 ,3899    ,298,298,298
BEGIN DESCRIPTION:
WEST ROCKY BRANCH 5.0
END DESCRIPTION:
XS GIS Cut Line= 3
      3718819.79     10222348.08      3718455.04     10222166.37
      3717563.84      10221971.3
#Sta/Elev= 30
  4329.5  336.17  4409.9  328.24  4469.9  323.86  4576.3  318.52  4581.9  317.44
  4598.7   317.1  4633.3  314.08  4700.3  313.09  4764.8  313.67  4887.7  312.47
  4921.4  313.07  4968.3  314.36  4979.8  313.53    4990   311.5  4997.8  308.89
  5002.8  308.89  5010.5  313.09  5022.4  314.01  5115.3  312.47  5184.5  313.73
  5225.5  316.27  5266.4  317.23  5322.2  320.82  5460.9  330.92  5512.1  336.03
  5563.3  342.73    5594  344.98  5628.4  349.21    5635  350.77  5649.3  351.78
#Mann= 5 ,-1 , 0
  4329.5     .11       0  4921.4     .15       0  4979.8     .09       0
  5010.5     .15       0  5322.2     .17       0
Bank Sta=4979.8,5010.5
XS Rating Curve= 0 ,0
Exp/Cntr=0.3,0.1

Type RM Length L Ch R = 1 ,3601    ,549,549,549
BEGIN DESCRIPTION:
WEST ROCKY BRANCH 4.0
END DESCRIPTION:
XS GIS Cut Line= 3
      3718862.55     10222289.28      3718238.57     10221847.02
      3717644.01     10221713.41
#Sta/Elev= 30
  4269.1  335.35  4399.6  323.44    4471  319.17  4494.4  318.62  4571.9  312.78
  4702.4   312.4  4723.3  313.14  4752.8  312.16  4788.5  312.81  4845.1  311.23
  4952.1  312.51  4973.5  314.21  4981.7  313.63  4984.3 312.424  4993.9  307.37
    4999  307.37  5010.3  311.32  5017.3  312.43  5075.4  312.74  5198.6  317.66
  5260.1  321.02  5314.2  324.63  5372.9   331.1  5475.4   337.3  5492.5  339.38
  5516.4  339.38  5542.8  341.01  5567.6  341.75  5584.3  343.45  5643.3  346.93
#Mann= 5 ,-1 , 0
  4269.1     .11       0  4984.3     .07       0  5017.3     .11       0
  5075.4     .15       0  5542.8     .17       0
Bank Sta=4984.3,5017.3
XS Rating Curve= 0 ,0
Exp/Cntr=0.3,0.1

Type RM Length L Ch R = 1 ,3052    ,95,95,95
BEGIN DESCRIPTION:
WEST ROCKY BRANCH 3.0
END DESCRIPTION:
XS GIS Cut Line= 3
      3719606.01     10221442.93       3718599.1      10221470.7
      3717602.75     10221522.78
#Sta/Elev= 30
  3972.5  341.81  4030.7  342.64  4040.7   341.2  4060.7  335.27  4070.7  334.13
  4091.1  333.95  4130.7   331.5  4140.7  329.75  4160.7  323.79  4180.7  320.95
  4240.8  321.77  4270.8  319.65  4290.8  320.43  4370.8  315.05  4630.9  310.62
    4881  310.47    4971   312.3  4982.9  311.36  4998.5  307.93  5003.7  307.93
  5011.1  311.51  5021.1  310.69  5079.4  312.23  5111.2  311.94  5181.3   313.5
    5263  316.94  5279.6  317.74  5477.7  324.55  5841.1  344.65  5977.5  347.58
#Mann= 7 ,-1 , 0
  3972.5     .11       0  4982.9     .07       0  5011.1     .11       0
    5263     .17       0  5279.6     .11       0  5477.7     .15       0
  5841.1     .17       0
Bank Sta=4982.9,5011.1
XS Rating Curve= 0 ,0
Exp/Cntr=0.3,0.1

Type RM Length L Ch R = 1 ,2957    ,504,504,504
BEGIN DESCRIPTION:
Mapping XS 297f6058
END DESCRIPTION:
XS GIS Cut Line= 2
      3719621.66     10221356.12      3717606.08     10221434.25
#Sta/Elev= 30
  4007.9  334.39  4281.9  322.41    4382  315.83  4482.1   312.3    4520  311.79
    4525  313.07  4692.2  310.49  4972.4  311.59  4989.8  305.05  4995.2  305.05
  5012.5  311.88  5043.4  313.57  5122.5  312.87  5202.6   315.5  5222.6  314.89
  5252.6   318.9  5272.7  317.48  5327.8  320.96  5362.7  322.39  5382.7  321.12
  5542.9  328.53  5556.8  327.83  5622.9   330.5    5663  332.49    5723  338.59
  5803.1  344.07    5816  343.19  5883.1  346.82  5923.1   346.8    6025   351.8
#Mann= 4 ,-1 , 0
  4007.9    .115       0  4972.4     .06       0  5012.5     .11       0
  5327.8     .17       0
Bank Sta=4972.4,5012.5
XS Rating Curve= 0 ,0
Exp/Cntr=0.3,0.1

Type RM Length L Ch R = 1 ,2453    ,524,524,524
BEGIN DESCRIPTION:
WEST ROCKY BRANCH 2.0
END DESCRIPTION:
XS GIS Cut Line= 3
      3719614.71     10221267.57      3718922.02      10220989.8
      3718081.47      10221005.4
#Sta/Elev= 30
  4209.9   330.4  4249.6  327.22  4314.3  323.86  4411.2  315.78  4475.9  312.67
  4511.5  310.28  4572.8   307.8    4659  308.38  4726.7  307.77  4766.8  308.54
  4896.1  308.87  4990.4  310.14  4997.7  305.96  5003.1  305.96  5010.4  308.37
  5020.4  309.19  5070.4  309.68  5140.4  312.99  5180.4  315.65  5230.4  317.78
  5330.4  319.51  5480.5  323.72  5500.5  323.53  5510.5  324.78  5530.5  324.61
  5569.4  326.76  5640.5  329.39  5740.5   334.5  5770.5  335.33  5796.9  337.18
#Mann= 4 ,-1 , 0
  4209.9     .11       0  4990.4     .06       0  5020.4     .11       0
  5569.4     .17       0
Bank Sta=4990.4,5020.4
XS Rating Curve= 0 ,0
Exp/Cntr=0.3,0.1

Type RM Length L Ch R = 1 ,1929    ,0,0,0
BEGIN DESCRIPTION:
WEST ROCKY BRANCH 1.0
END DESCRIPTION:
XS GIS Cut Line= 3
      3719645.98     10221229.39       3719118.2     10220628.69
      3718406.36     10220621.75
#Sta/Elev= 30
  4256.4  330.12  4317.9  325.21  4416.6  319.19  4466.9  316.86  4473.5  315.71
  4558.9  312.85  4657.6  306.83  4679.4  306.78  4700.3  307.78  4792.3  307.04
  4799.9  307.82  4898.6   308.1  4927.1  307.58    4984  308.35  4990.7   307.1
  5002.2  303.43  5007.6  303.43  5012.5   306.9  5019.1  308.06  5026.2  306.97
  5086.4  308.67  5146.4  309.04  5186.4  307.36  5216.4  307.77  5296.4  310.11
  5316.4  309.79  5346.4  311.14  5436.4  312.76  5626.4  318.79  5767.9  321.07
#Mann= 3 , 0 , 0
  4256.4     .11       0    4984     .06       0  5019.1     .11       0
Bank Sta=4984,5019.1
XS Rating Curve= 0 ,0
Exp/Cntr=0.3,0.1

Chan Stop Cuts=-1
Use User Specified Reach Order=0
Composite Channel Slope=5