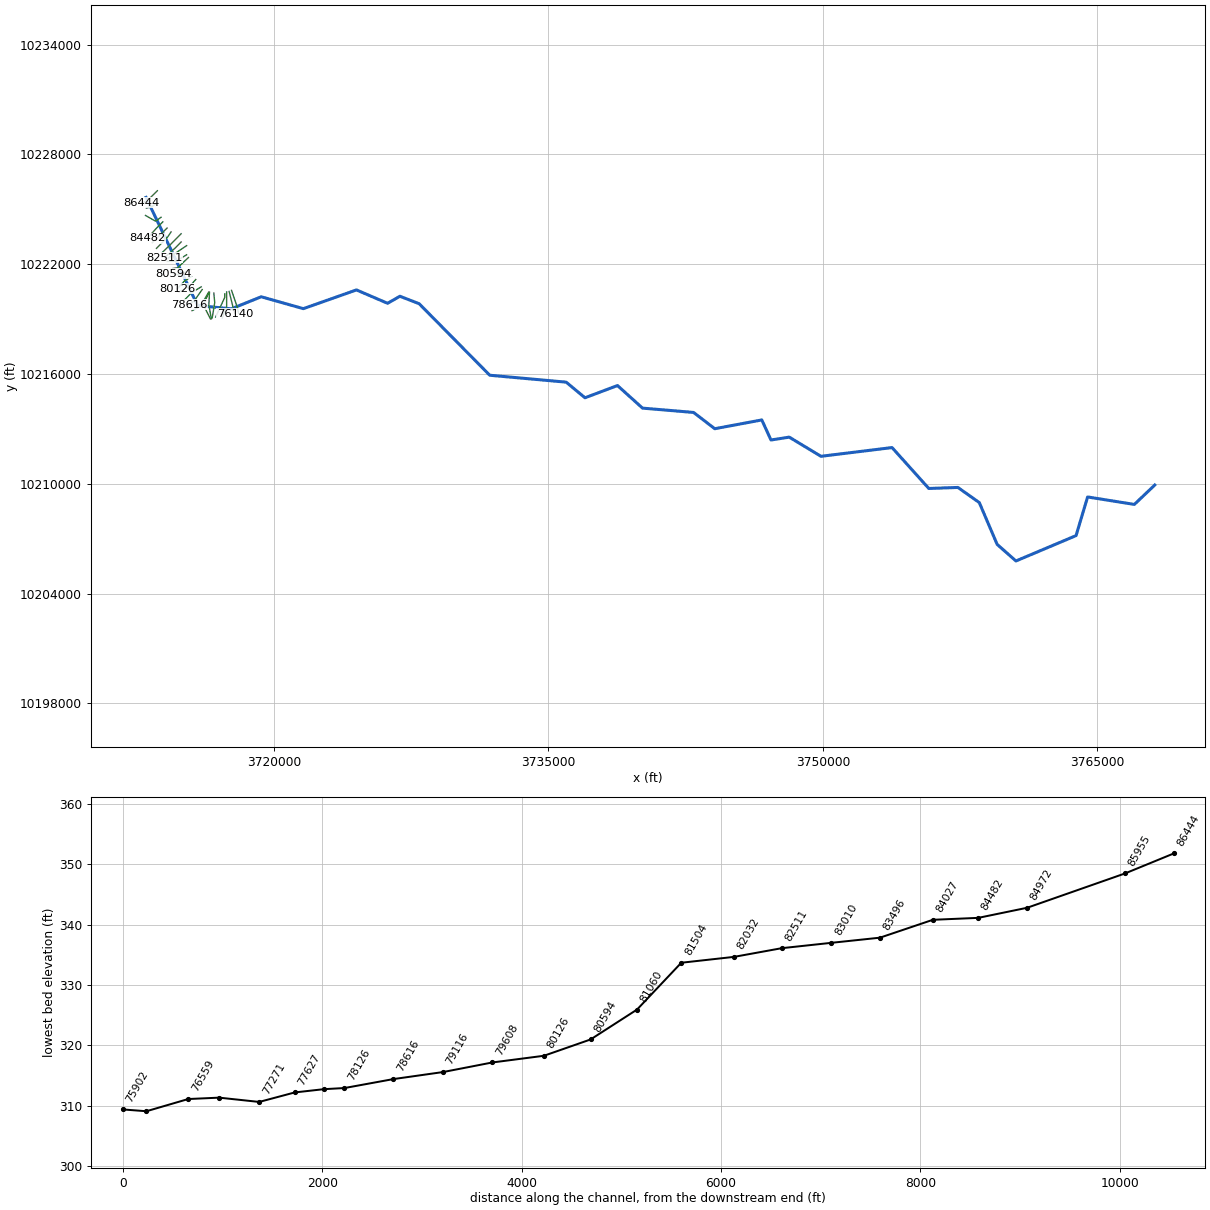
--- WEST SANDY CREEK.prj (project) ---

Proj Title=WEST SANDY CREEK Base Level Engineering
Current Plan=p01
Default Exp/Contr=0.3,0.1
English Units
Geom File=g01
Flow File=f01
Plan File=p01
Y Axis Title=Elevation
X Axis Title(PF)=Main Channel Distance
X Axis Title(XS)=Station
BEGIN DESCRIPTION:
WEST SANDY CREEK
END DESCRIPTION:
DSS Export Rating Curves= 0
DSS Export Rating Curve Sorted= 0
DSS Export Volume Flow Curves= 0
DXF OffsetX= 0
DXF OffsetY= 0
DXF ScaleX= 1
DXF ScaleY= 10

--- WEST SANDY CREEK.p01 (plan) ---

Plan Title=Multiple Run
Program Version=4.10
Short Identifier=Multiple
Geom File=g01
Flow File=f01
Subcritical Flow
K Sum by GR= 0
Std Step Tol= 0.01
Critical Tol= 0.01
Num of Std Step Trials= 20
Max Error Tol= 0.3
Flow Tol Ratio= 0.001
Split Flow NTrial= 30
Split Flow Tol= 0.02
Split Flow Ratio= 0.02
Log Output Level= 0
Friction Slope Method= 1
Unsteady Friction Slope Method= 2
Unsteady Bridges Friction Slope Method= 1
Parabolic Critical Depth
Global Vel Dist= 1 , 1 , 1
Global Log Level= 0
CheckData=True
Encroach Param=-1 ,0,0, 0
BEGIN DESCRIPTION:
Multiple Run
END DESCRIPTION:
Computation Interval=1HOUR
Output Interval=1HOUR
Run HTab= 0
Run UNet= 0
Run PostProcess= 0
Run WQNet= 0
UNET Theta= 1
UNET Theta Warmup= 1
UNET ZTol= 0.02
UNET ZSATol= 0.05
UNET MxIter= 20
UNET MaxInSteps= 0
UNET DtIC= 0
UNET DtMin= 0
UNET MaxCRTS= 20
UNET WFStab= 2
UNET SFStab= 1
UNET WFX= 1
UNET SFX= 1
UNET DSS MLevel= 4
UNET DZMax Abort= 100
UNET Convert EG Bridges= 0
UNET Use Existing IB Tables=-1
UNET Froude Reduction=False
UNET Froude Limit= 1
UNET Froude Power= 10
UNET Time Slicing=0,0, 5
UNET Junction Losses=0
Instantaneous Interval=1HOUR
Write IC File= 0
Write IC File at Sim End=0
Echo Input=False
Echo Parameters=False
Echo Output=False
Write Detailed= 0
WQ AD Non Conservative
WQ ULTIMATE=-1
WQ Max Comp Step=1HOUR
WQ Output Interval=15MIN
WQ Output Selected Increments= 0
WQ Output face flow=0
WQ Output face velocity=0
WQ Output face area=0
WQ Output face dispersion=0
WQ Output cell volume=0
WQ Output cell surface area=0
WQ Output cell continuity=0
WQ Output cumulative cell continuity=0
WQ Output face conc=0
WQ Output face dconc_dx=0
WQ Output face courant=0
WQ Output face peclet=0
WQ Output face adv mass=0
WQ Output face disp mass=0
WQ Output cell mass=0
WQ Output cell source sink temp=0
WQ Output cell source sink nsm=0
WQ Output MaxMinRange=-1
WQ Daily Max Min Mean=-1
WQ Daily Range=0
WQ Daily Time=0
WQ Create Restart=0
WQ Fixed Restart=0
WQ System Summary=0
WQ Use Fixed Temperature=0
Sorting and Armoring Iterations= 10
XS Update Threshold= 0.02
Hydraulics Update Threshold= 0.02
Energy Slope Method= 1
Volume Change Method= 0
XS Weighting Method= 0
Number of US Weighted Cross Sections= 1
Number of DS Weighted Cross Sections= 1
Upstream XS Weight=0.25
Main XS Weight=0.5
Downstream XS Weight=0.25
Number of DS XS's Weighted with US Boundary= 1
Upstream Boundary Weight= 1
Weight of XSs Associated with US Boundary= 0
Number of US XS's Weighted with DS Boundary= 1
Downstream Boundary Weight= 0.5
Weight of XSs Associated with DS Boundary= 0.5
Sediment Output Level= 4
Mass or Volume Output= 0
Output Increment Type= 1
Profile and TS Output Increment= 10
XS Output Flag= 0
XS Output Increment= 10
Disregard all LS=0
Disregard all Conn=0
Disregard all Breaches=0
Disregard all Pumps=0

--- WEST SANDY CREEK.f01 (steady flow) ---

Flow Title=Multiple
Program Version=4.10
Number of Profiles= 7
Profile Names=10-year,25-year,50-year,1pct_min,100-year,1pct_plu,500-year
River Rch & RM=WEST SANDY CREEK,Reach-1         ,86444
     677     921    1250     558    1684    5086    3160
River Rch & RM=WEST SANDY CREEK,Reach-1         ,81060
     670     910    1231     548    1654    4995    3086
River Rch & RM=WEST SANDY CREEK,Reach-1         ,80126
    1027    1426    1958     882    2665    8048    5112
River Rch & RM=WEST SANDY CREEK,Reach-1         ,79608
    1027    1426    1958     882    2665    8048    5112
River Rch & RM=WEST SANDY CREEK,Reach-1         ,77627
    1447    2049    2852    1302    3931   11871    7733
River Rch & RM=WEST SANDY CREEK,Reach-1         ,75485
    1598    2271    3166    1447    4371   13200    8629
River Rch & RM=WEST SANDY CREEK,Reach-1         ,74045
    2205    3148    4402    2015    6085   18376   12042
River Rch & RM=WEST SANDY CREEK,Reach-1         ,72649
    2205    3148    4402    2015    6085   18376   12042
River Rch & RM=WEST SANDY CREEK,Reach-1         ,69195
    2538    3626    5074    2321    7010   21170   13861
River Rch & RM=WEST SANDY CREEK,Reach-1         ,67268
    2538    3626    5074    2321    7010   21170   13861
River Rch & RM=WEST SANDY CREEK,Reach-1         ,62484
    2793    4015    5641    2591    7826   23634   15606
River Rch & RM=WEST SANDY CREEK,Reach-1         ,57659
    2941    4236    5960    2742    8280   25005   16550
River Rch & RM=WEST SANDY CREEK,Reach-1         ,56827
    3171    4559    6408    2942    8886   26835   17699
River Rch & RM=WEST SANDY CREEK,Reach-1         ,55636
    4434    6472    9190    4262   12871   38870   26146
River Rch & RM=WEST SANDY CREEK,Reach-1         ,51414
    4427    6454    9156    4242   12810   38686   25972
River Rch & RM=WEST SANDY CREEK,Reach-1         ,48047
    4734    6911    9815    4551   13745   41509   27914
River Rch & RM=WEST SANDY CREEK,Reach-1         ,45624
    5092    7423   10534    4880   14736   44502   29852
River Rch & RM=WEST SANDY CREEK,Reach-1         ,41577
    5190    7570   10747    4980   15040   45420   30489
River Rch & RM=WEST SANDY CREEK,Reach-1         ,40456
    6080    8900   12665    5881   17761   53637   36149
River Rch & RM=WEST SANDY CREEK,Reach-1         ,33485
    6193    9062   12892    5984   18071   54574   36753
River Rch & RM=WEST SANDY CREEK,Reach-1         ,31600
    6430    9412   13393    6218   18777   56706   38196
River Rch & RM=WEST SANDY CREEK,Reach-1         ,28663
    6070    8827   12504    5778   17449   52695   35165
River Rch & RM=WEST SANDY CREEK,Reach-1         ,24609
    5779    8349   11773    5414   16349   49373   32634
River Rch & RM=WEST SANDY CREEK,Reach-1         ,22510
    5834    8428   11885    5466   16506   49847   32945
River Rch & RM=WEST SANDY CREEK,Reach-1         ,19543
    6207    9013   12756    5888   17780   53695   35748
River Rch & RM=WEST SANDY CREEK,Reach-1         ,16173
    6209    8996   12712    5857   17689   53420   35446
River Rch & RM=WEST SANDY CREEK,Reach-1         ,15412
    6209    8996   12712    5857   17689   53420   35446
River Rch & RM=WEST SANDY CREEK,Reach-1         ,9689
    6706    9753   13818    6384   19280   58225   38836
River Rch & RM=WEST SANDY CREEK,Reach-1         ,6715
    6706    9753   13818    6384   19280   58225   38836
Boundary for River Rch & Prof#=WEST SANDY CREEK,Reach-1         , 1
Up Type= 0
Dn Type= 3
Dn Slope=0.002
Boundary for River Rch & Prof#=WEST SANDY CREEK,Reach-1         , 2
Up Type= 0
Dn Type= 3
Dn Slope=0.002
Boundary for River Rch & Prof#=WEST SANDY CREEK,Reach-1         , 3
Up Type= 0
Dn Type= 3
Dn Slope=0.002
Boundary for River Rch & Prof#=WEST SANDY CREEK,Reach-1         , 4
Up Type= 0
Dn Type= 3
Dn Slope=0.002
Boundary for River Rch & Prof#=WEST SANDY CREEK,Reach-1         , 5
Up Type= 0
Dn Type= 3
Dn Slope=0.002
Boundary for River Rch & Prof#=WEST SANDY CREEK,Reach-1         , 6
Up Type= 0
Dn Type= 3
Dn Slope=0.002
Boundary for River Rch & Prof#=WEST SANDY CREEK,Reach-1         , 7
Up Type= 0
Dn Type= 3
Dn Slope=0.002
DSS Import GetInterval= 0
DSS Import GetPeak= 0
DSS Import FillOption= 0

--- WEST SANDY CREEK.g01 (geometry) ---

Geom Title=Existing Conditions
Program Version=4.10

River Reach=WEST SANDY CREEK,Reach-1
Reach XY= 30
      3712998.11     10225647.26      3715818.12     10219739.16
      3717661.12     10219557.27      3719295.51     10220216.95
      3721599.25     10219566.78      3724501.68      10220591.2
      3726204.77     10219859.97      3726879.86     10220243.63
      3727929.25     10219838.58      3731790.77     10215928.36
      3735970.96     10215549.86      3736998.18     10214696.87
      3738773.98     10215365.94      3740143.97     10214131.04
      3742934.86     10213895.66      3744093.64     10213006.14
      3746664.85     10213485.95      3747166.18     10212390.17
      3748165.78     10212545.66      3749900.28     10211498.54
      3753784.91     10211975.81      3755795.87     10209740.43
       3757386.9     10209796.51      3758557.27     10208967.83
      3759531.52     10206684.44      3760559.73     10205778.57
      3763846.86     10207165.44      3764478.23     10209276.84
      3767033.48     10208868.96      3768149.72     10209928.11

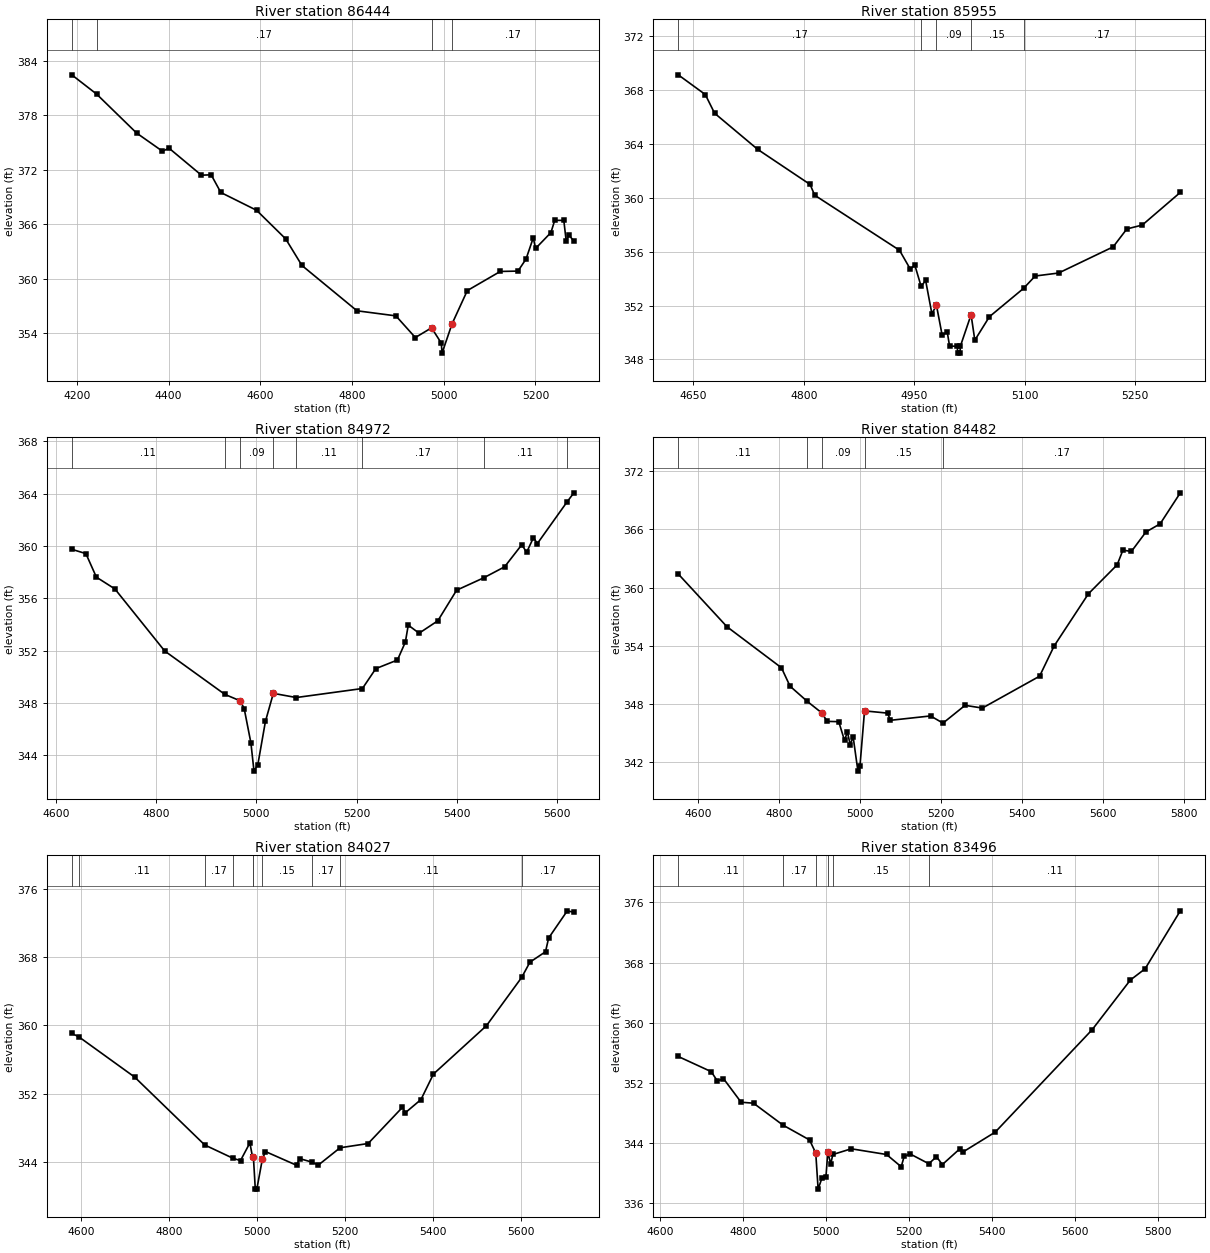
Type RM Length L Ch R = 1 ,86444   ,489,489,489
BEGIN DESCRIPTION:
WEST SANDY CREEK 151.0
END DESCRIPTION:
XS GIS Cut Line= 3
      3713617.84     10226011.06      3713040.17     10225441.25
      3712767.83     10225361.07
#Sta/Elev= 30
  4188.6  382.48  4242.9  380.35    4330  376.06  4386.5  374.05  4400.7  374.39
  4471.4  371.41  4492.7  371.45  4513.8   369.5  4591.7  367.54  4655.3  364.38
  4690.7  361.45  4810.8  356.45  4895.7  355.89  4938.1   353.5  4973.5  354.57
  4994.7  352.89  4996.4  351.78  5018.2  355.01  5051.5  358.68  5123.4  360.79
    5162  360.83  5179.6  362.16  5195.3  364.49  5200.5  363.33  5233.9  365.08
  5242.2  366.43    5262  366.42  5267.2  364.16  5273.5  364.79  5283.9  364.13
#Mann= 4 ,-1 , 0
  4188.6     .11       0  4242.9     .17       0  4973.5     .09       0
  5018.2     .17       0
Bank Sta=4973.5,5018.2
XS Rating Curve= 0 ,0
Exp/Cntr=0.3,0.1

Type RM Length L Ch R = 1 ,85955   ,983,983,983
BEGIN DESCRIPTION:
WEST SANDY CREEK 150.0
END DESCRIPTION:
XS GIS Cut Line= 3
      3713617.86     10225361.08      3713317.88     10225143.47
      3713017.89     10225061.08
#Sta/Elev= 30
  4629.4  369.11  4666.1  367.65  4678.8  366.26  4737.3  363.58  4808.4  360.98
  4814.7  360.18  4929.8   356.1  4944.5   354.7  4950.6     355  4959.2  353.42
  4965.3  353.86  4973.8  351.39    4980  352.02  4987.7  349.81  4994.7  350.02
  4997.8     349  5008.4  348.97  5008.6  348.47  5012.1  348.47  5012.4  348.97
    5027  351.32  5032.1  349.43  5051.9  351.17  5098.2  353.27  5114.1  354.19
  5145.8  354.41  5219.9  356.35  5238.5  357.68  5259.5  357.97  5311.1  360.39
#Mann= 5 ,-1 , 0
  4629.4     .17       0  4959.2     .15       0    4980     .09       0
    5027     .15       0  5098.2     .17       0
Bank Sta=4980,5027
XS Rating Curve= 0 ,0
Exp/Cntr=0.3,0.1

Type RM Length L Ch R = 1 ,84972   ,490,490,490
BEGIN DESCRIPTION:
WEST SANDY CREEK 149.0
END DESCRIPTION:
XS GIS Cut Line= 3
      3713817.83     10224561.05      3713518.23     10224346.84
      3712967.82     10224661.09
#Sta/Elev= 30
  4631.7  359.75  4659.9  359.42  4680.8  357.62  4717.7  356.72  4817.2  351.97
  4937.3  348.65  4968.3  348.15  4975.9  347.55  4989.2  344.95  4995.4  342.78
  5003.1  343.28  5018.2  346.58    5034  348.73  5079.8  348.41  5211.8   349.1
  5238.5  350.62  5281.7  351.28  5297.5  352.65  5303.3  353.95  5324.9  353.33
  5362.3  354.28  5399.8  356.62  5453.5  357.56  5495.6  358.41  5530.1  360.11
  5539.4  359.51  5553.2  360.64    5561  360.19  5619.6  363.34  5633.8  364.07
#Mann= 8 ,-1 , 0
  4631.7     .11       0  4937.3     .15       0  4968.3     .09       0
    5034     .15       0  5079.8     .11       0  5211.8     .17       0
  5453.5     .11       0  5619.6     .17       0
Bank Sta=4968.3,5034
XS Rating Curve= 0 ,0
Exp/Cntr=0.3,0.1

Type RM Length L Ch R = 1 ,84482   ,455,455,455
BEGIN DESCRIPTION:
WEST SANDY CREEK 148.0
END DESCRIPTION:
XS GIS Cut Line= 3
      3713917.84     10224311.06      3713598.23     10223996.84
      3713067.86     10223411.08
#Sta/Elev= 30
  4551.8   361.4    4672  355.97  4806.3  351.75  4827.6  349.85    4870  348.29
  4905.3  347.12  4919.5  346.23  4947.7   346.2  4961.9  344.27    4969  345.15
    4976  343.84  4983.2  344.64    4995  341.11    5000  341.61  5011.3  347.31
  5068.1  347.08  5075.2  346.34  5174.2  346.79  5204.8  346.05  5259.3  347.88
  5301.9   347.6  5443.1  350.88    5479  353.99  5563.5  359.36  5634.4  362.34
  5648.6  363.85  5669.6  363.72  5705.4  365.72  5740.5  366.56  5790.2  369.75
#Mann= 5 ,-1 , 0
  4551.8     .11       0    4870     .15       0  4905.3     .09       0
  5011.3     .15       0  5204.8     .17       0
Bank Sta=4905.3,5011.3
XS Rating Curve= 0 ,0
Exp/Cntr=0.3,0.1

Type RM Length L Ch R = 1 ,84027   ,531,531,531
BEGIN DESCRIPTION:
WEST SANDY CREEK 147.0
END DESCRIPTION:
XS GIS Cut Line= 3
      3714149.59     10223971.53      3713854.29     10223683.17
      3713338.16     10223169.67
#Sta/Elev= 30
  4578.5  359.05  4594.1  358.67  4721.4  353.93  4880.6  345.97  4945.6  344.39
  4961.9  344.14  4983.2  346.21  4989.2  344.57  4991.2  344.57  4995.5  340.79
    4999  340.79  5011.4  344.27  5018.5   345.2  5089.2  343.59  5096.3  344.37
  5124.6  343.95  5138.7  343.61  5188.1  345.64  5251.9  346.14  5329.6  350.37
  5336.7  349.76    5372   351.3  5400.3  354.29  5520.6  359.95  5600.8  365.62
  5619.5  367.41  5654.9  368.63    5662  370.24  5704.4  373.43  5719.3  373.26
#Mann= 10 ,-1 , 0
  4578.5     .17       0  4594.1     .11       0  4880.6     .17       0
  4945.6     .15       0  4989.2     .12       0  4991.2     .09       0
  5011.4     .15       0  5124.6     .17       0  5188.1     .11       0
  5600.8     .17       0
Bank Sta=4991.2,5011.4
XS Rating Curve= 0 ,0
Exp/Cntr=0.3,0.1

Type RM Length L Ch R = 1 ,83496   ,486,486,486
BEGIN DESCRIPTION:
WEST SANDY CREEK 146.0
END DESCRIPTION:
XS GIS Cut Line= 3
      3714367.88     10223761.11      3714168.23     10223466.84
      3713567.84     10222861.06
#Sta/Elev= 30
  4644.4  355.49  4723.8  353.47  4738.7  352.22  4753.2  352.55  4795.7   349.4
  4825.6  349.27  4896.3  346.36  4960.4  344.38  4975.4  342.64  4981.1  337.83
  4990.3   339.3    5000   339.5  5004.4  342.76  5011.4   341.2  5016.6  342.44
  5060.9   343.2  5145.8  342.44  5181.1  340.81  5188.2  342.18  5202.4  342.52
  5247.6  341.21    5266  342.15  5280.1   341.1  5322.5  343.21  5329.6  342.77
  5407.4  345.42  5640.8  359.06  5732.7  365.67  5768.1  367.16  5852.9  374.88
#Mann= 6 ,-1 , 0
  4644.4     .11       0  4896.3     .17       0  4975.4     .09       0
  5004.4     .17       0  5016.6     .15       0  5247.6     .11       0
Bank Sta=4975.4,5004.4
XS Rating Curve= 0 ,0
Exp/Cntr=0.3,0.1

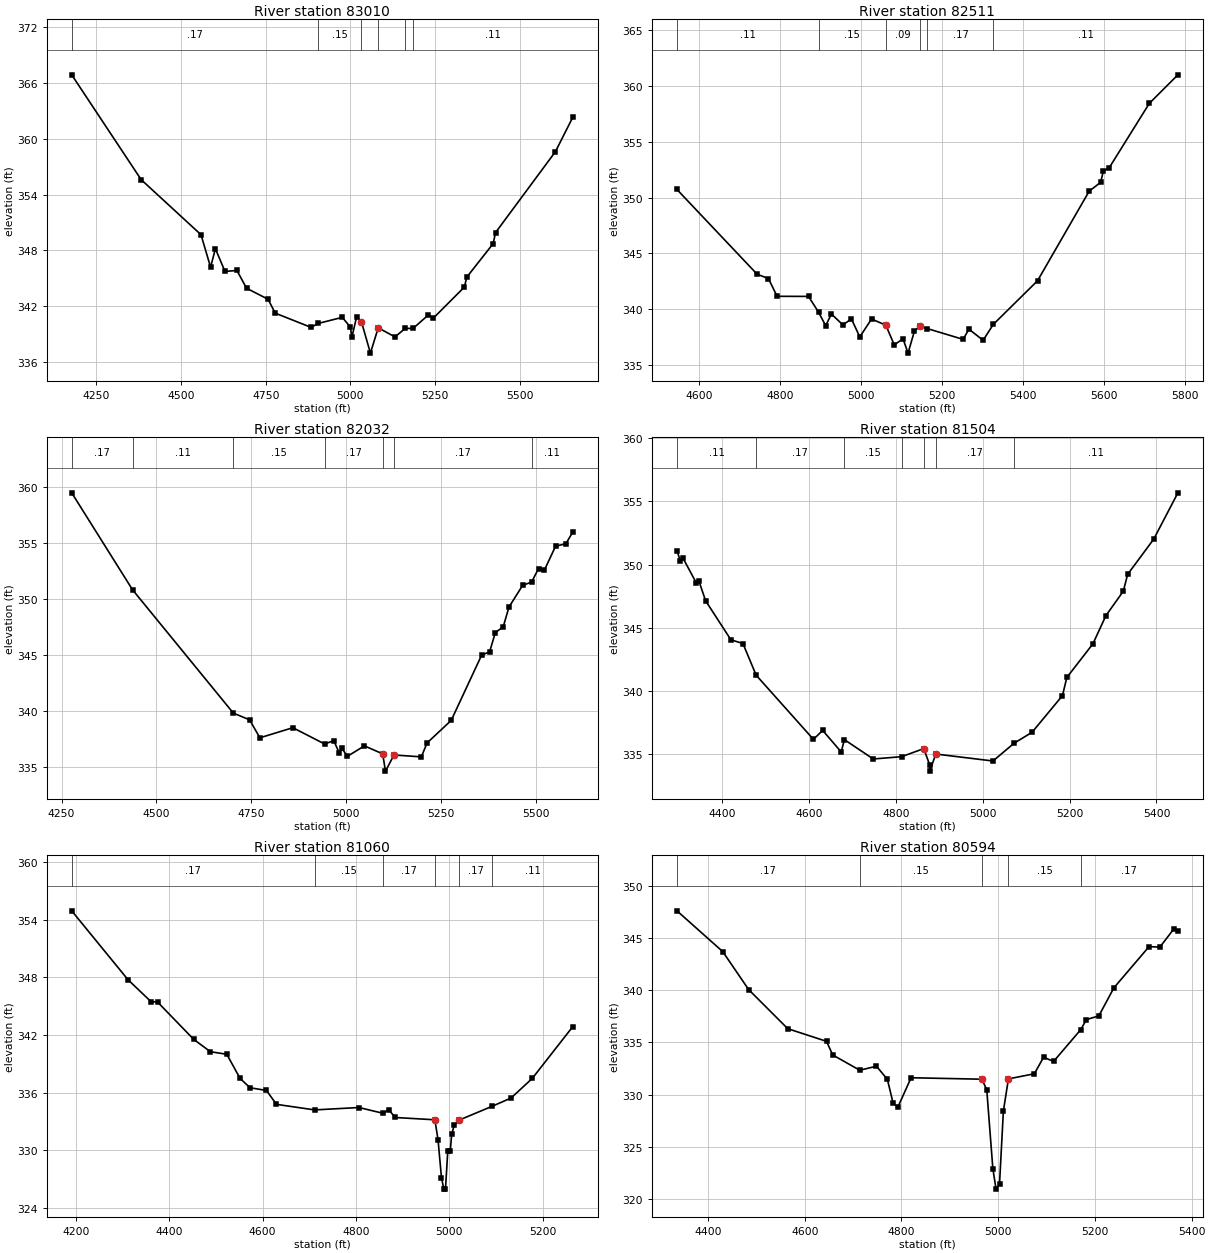
Type RM Length L Ch R = 1 ,83010   ,499,499,499
BEGIN DESCRIPTION:
WEST SANDY CREEK 145.0
END DESCRIPTION:
XS GIS Cut Line= 3
      3714917.87     10223661.09      3714338.23     10223076.84
      3713868.17     10222618.69
#Sta/Elev= 30
    4177  366.85  4382.1   355.6  4558.8  349.69  4587.1   346.2  4601.3  348.19
  4629.6  345.75  4664.9  345.85  4693.2  343.95  4756.8  342.76  4778.1  341.27
  4884.1  339.74  4904.2  340.16  4976.1  340.82    5000  339.77  5004.3  338.67
  5018.5   340.9  5032.6  340.35  5059.1  336.98  5082.2   339.7  5131.6  338.72
  5161.9  339.63  5185.5  339.64  5230.6  341.09  5244.8  340.73  5336.6  344.07
  5343.8  345.14  5421.5  348.73  5428.7  349.92  5605.4   358.6  5656.4  362.27
#Mann= 6 ,-1 , 0
    4177     .17       0  4904.2     .15       0  5032.6     .09       0
  5082.2     .15       0  5161.9     .17       0  5185.5     .11       0
Bank Sta=5032.6,5082.2
XS Rating Curve= 0 ,0
Exp/Cntr=0.3,0.1

Type RM Length L Ch R = 1 ,82511   ,479,479,479
BEGIN DESCRIPTION:
WEST SANDY CREEK 144.0
END DESCRIPTION:
XS GIS Cut Line= 3
      3714917.86     10223211.08      3714598.23     10222886.84
      3714017.87     10222361.08
#Sta/Elev= 30
  4544.7  350.72  4742.7  343.15    4771  342.75  4792.2  341.17    4870  341.16
  4894.9  339.74  4912.4  338.54  4926.5  339.59  4954.8  338.62  4976.1  339.14
  4996.7  337.54  5025.8  339.14    5061  338.59  5081.9  336.83  5103.6  337.37
    5116  336.09  5131.9  338.08  5146.1  338.49    5164  338.28  5252.2  337.32
  5266.4  338.23  5301.6  337.24  5326.8  338.66  5436.1  342.56  5563.8  350.57
  5592.2  351.36  5598.9  352.39  5613.1  352.65  5712.5  358.42  5783.1  360.97
#Mann= 6 ,-1 , 0
  4544.7     .11       0  4894.9     .15       0    5061     .09       0
  5146.1     .15       0    5164     .17       0  5326.8     .11       0
Bank Sta=5061,5146.1
XS Rating Curve= 0 ,0
Exp/Cntr=0.3,0.1

Type RM Length L Ch R = 1 ,82032   ,528,528,528
BEGIN DESCRIPTION:
WEST SANDY CREEK 143.0
END DESCRIPTION:
XS GIS Cut Line= 3
      3715217.81     10223011.04      3714618.23     10222606.84
      3714122.05     10222273.24
#Sta/Elev= 30
  4276.9  359.45  4437.3  350.81  4703.1  339.82    4746  339.22  4773.1  337.62
    4860  338.52  4943.7  337.07    4968  337.36  4982.9  336.23    4989   336.7
  5003.9  335.97  5048.7   336.9  5096.9  336.19  5104.2  334.65  5126.9  336.09
  5198.9  335.92  5213.9  337.16  5277.6  339.17  5357.9  344.99  5378.9  345.28
  5393.9  346.99  5414.9  347.52  5429.9  349.27  5465.9   351.2  5489.6   351.5
  5507.9   352.7  5522.9  352.53  5552.9   354.7  5579.9  354.91  5597.9  355.94
#Mann= 7 ,-1 , 0
  4276.9     .17       0  4437.3     .11       0  4703.1     .15       0
  4943.7     .17       0  5096.9     .09       0  5126.9     .17       0
  5489.6     .11       0
Bank Sta=5096.9,5126.9
XS Rating Curve= 0 ,0
Exp/Cntr=0.3,0.1

Type RM Length L Ch R = 1 ,81504   ,444,444,444
BEGIN DESCRIPTION:
WEST SANDY CREEK 142.0
END DESCRIPTION:
XS GIS Cut Line= 3
      3715217.86     10222511.08      3714638.58     10222160.61
      3714162.17     10222149.05
#Sta/Elev= 30
  4295.7  351.11  4303.5  350.27  4309.3  350.53  4340.3  348.55  4346.2  348.71
  4361.7  347.14  4419.9  344.06  4447.7  343.76  4478.1  341.26    4610  336.19
  4631.3   336.9    4674  335.19  4681.2  336.17  4747.7  334.64  4812.9  334.82
  4864.1  335.46  4877.6  334.18  4877.8  333.68  4891.8  335.03  5023.5  334.48
  5071.8  335.88  5113.5  336.75  5183.5  339.65  5193.5  341.08  5253.6  343.74
  5283.6  345.97  5323.6   347.9  5333.6  349.23  5393.6  352.01  5449.3  355.67
#Mann= 7 ,-1 , 0
  4295.7     .11       0  4478.1     .17       0  4681.2     .15       0
  4812.9     .17       0  4864.1     .09       0  4891.8     .17       0
  5071.8     .11       0
Bank Sta=4864.1,4891.8
XS Rating Curve= 0 ,0
Exp/Cntr=0.3,0.1

Type RM Length L Ch R = 1 ,81060   ,466,466,466
BEGIN DESCRIPTION:
WEST SANDY CREEK 141.0
END DESCRIPTION:
XS GIS Cut Line= 3
      3715317.84     10222361.06      3714728.23     10221806.84
      3714467.82     10221761.07
#Sta/Elev= 30
  4190.8  354.95  4311.2  347.78  4360.5  345.49  4374.7  345.44  4452.4  341.54
    4488  340.26  4523.2  339.99  4551.5  337.48    4573   336.5  4608.1  336.22
  4629.6  334.77  4711.4  334.19  4806.4  334.44  4858.7  333.83  4869.9  334.23
  4884.1   333.4  4969.1  333.16  4975.9  331.06  4983.2  327.13  4988.3  325.93
  4991.8  325.93  4996.8  329.95  5002.2  329.95    5005  331.63  5010.5  332.57
  5020.7  333.12  5092.3  334.58  5132.4  335.43  5177.9  337.48  5264.4  342.86
#Mann= 6 ,-1 , 0
  4190.8     .17       0  4711.4     .15       0  4858.7     .17       0
  4969.1     .09       0  5020.7     .17       0  5092.3     .11       0
Bank Sta=4969.1,5020.7
XS Rating Curve= 0 ,0
Exp/Cntr=0.3,0.1

Type RM Length L Ch R = 1 ,80594   ,468,468,468
BEGIN DESCRIPTION:
WEST SANDY CREEK 140.0
END DESCRIPTION:
XS GIS Cut Line= 3
      3715417.82     10221711.05      3714838.23     10221386.84
      3714480.42     10221487.14
#Sta/Elev= 30
  4335.9  347.59  4430.6  343.69  4484.3  340.05    4565  336.32  4645.2  335.11
  4657.9  333.81  4713.8  332.35  4748.4  332.73  4770.9  331.48  4782.7  329.23
  4792.6  328.82    4820  331.63  4966.2  331.49  4976.4  330.49    4989  322.95
  4995.6  320.98  5002.8  321.48  5010.8  328.45  5021.2  331.52  5074.8  332.01
  5093.9  333.59  5114.6  333.19  5170.9  336.24  5182.3  337.19  5208.1  337.54
  5239.3  340.23    5312  344.17  5334.3  344.12  5363.2  345.86  5371.6  345.65
#Mann= 5 ,-1 , 0
  4335.9     .17       0  4713.8     .15       0  4966.2     .09       0
  5021.2     .15       0  5170.9     .17       0
Bank Sta=4966.2,5021.2
XS Rating Curve= 0 ,0
Exp/Cntr=0.3,0.1

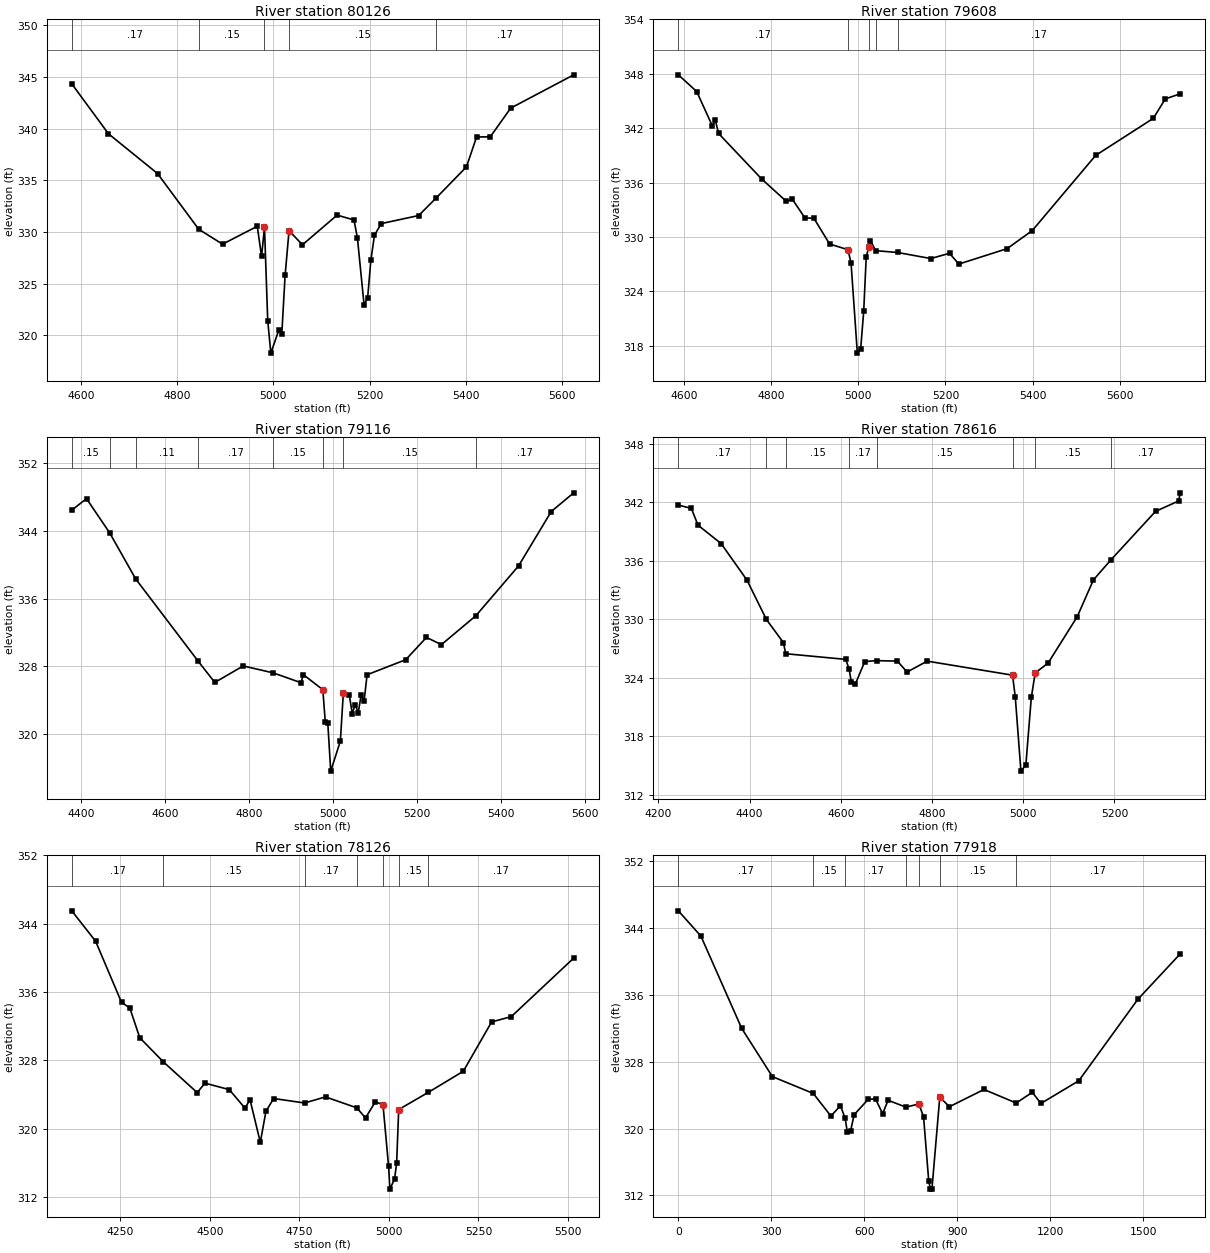
Type RM Length L Ch R = 1 ,80126   ,518,518,518
BEGIN DESCRIPTION:
WEST SANDY CREEK 139.0
END DESCRIPTION:
XS GIS Cut Line= 3
      3715486.05     10221328.55      3715071.54     10221050.76
      3714704.76     10220649.26
#Sta/Elev= 30
  4581.3  344.33  4657.5   339.5  4759.5  335.65  4845.1  330.26  4894.6  328.82
  4966.7  330.55  4975.6  327.63  4981.7  330.45  4988.4  321.42  4994.9  318.28
  5011.7  320.55  5017.7  320.16  5024.5  325.79  5032.7  330.12  5060.6  328.76
  5132.5  331.63  5167.6  331.16  5174.7  329.44  5188.6  322.94    5196  323.64
  5202.7  327.28  5210.2  329.69  5224.3  330.81    5302  331.59    5339  333.32
  5401.3   336.3  5422.3  339.19  5450.7   339.2  5493.2  341.98  5624.1   345.2
#Mann= 5 ,-1 , 0
  4581.3     .17       0  4845.1     .15       0  4981.7     .09       0
  5032.7     .15       0    5339     .17       0
#XS Ineff= 1 ,-1
  5132.5    5330  331.63
Permanent Ineff=
       F
Bank Sta=4981.7,5032.7
XS Rating Curve= 0 ,0
Exp/Cntr=0.3,0.1

Type RM Length L Ch R = 1 ,79608   ,492,492,492
BEGIN DESCRIPTION:
WEST SANDY CREEK 138.0
END DESCRIPTION:
XS GIS Cut Line= 3
      3715717.85     10221161.08      3715441.94     10220853.09
      3714805.05     10220477.29
#Sta/Elev= 30
  4586.5  347.89  4628.7  346.04  4664.6  342.24  4671.4   342.9  4678.8  341.42
  4777.5  336.41  4834.3  333.93  4848.5  334.14    4877  332.11  4897.9  332.05
  4933.8  329.22  4975.9  328.59  4983.1  327.15  4997.6  317.17  5005.3  317.67
  5012.2  321.77    5018  327.79  5023.8  328.86  5027.8   329.6  5039.6  328.48
    5090  328.28  5166.4  327.61  5209.3  328.19  5230.7     327  5341.5   328.7
  5399.5   330.7  5544.9  338.99  5677.6  343.09  5704.9  345.23  5739.5   345.8
#Mann= 5 ,-1 , 0
  4586.5     .17       0  4975.9     .09       0  5023.8     .17       0
  5039.6     .15       0    5090     .17       0
Bank Sta=4975.9,5023.8
XS Rating Curve= 0 ,0
Exp/Cntr=0.3,0.1

Type RM Length L Ch R = 1 ,79116   ,500,500,500
BEGIN DESCRIPTION:
WEST SANDY CREEK 137.0
END DESCRIPTION:
XS GIS Cut Line= 3
      3716017.83     10220761.06      3715486.49     10220436.16
      3715087.24     10220025.99
#Sta/Elev= 30
  4377.2  346.46  4412.3  347.82  4467.4  343.78  4529.2  338.34  4678.5  328.57
  4717.8  326.08  4785.4  328.03  4857.1  327.21  4922.9  326.05  4928.7     327
    4975  325.22  4980.9  321.39  4986.8  321.32  4993.8  315.59  5016.8  319.15
  5023.8  324.81  5037.9  324.63  5045.1   322.4  5052.1  323.47  5059.3   322.5
  5066.2  324.58  5073.4  323.92  5080.4  326.99  5172.4  328.77  5221.8  331.41
  5257.3  330.55  5339.4  333.97    5441  339.86  5518.9   346.3  5572.4  348.51
#Mann= 8 ,-1 , 0
  4377.2     .15       0  4467.4     .17       0  4529.2     .11       0
  4678.5     .17       0  4857.1     .15       0    4975     .09       0
  5023.8     .15       0  5339.4     .17       0
Bank Sta=4975,5023.8
XS Rating Curve= 0 ,0
Exp/Cntr=0.3,0.1

Type RM Length L Ch R = 1 ,78616   ,490,490,490
BEGIN DESCRIPTION:
WEST SANDY CREEK 136.0
END DESCRIPTION:
XS GIS Cut Line= 3
      3716067.87      10220611.1      3715632.21     10219992.89
      3715352.34     10219791.83
#Sta/Elev= 30
  4243.7   341.7  4272.1  341.37  4286.8  339.64  4337.4  337.76    4394  334.02
  4436.8  329.97  4474.1   327.6  4479.1  326.46  4610.7  325.88  4618.2  324.89
    4623  323.56  4631.7  323.34  4652.6  325.66  4679.6  325.75  4724.1   325.7
  4745.3  324.58  4789.4   325.7  4976.6  324.26  4982.7  321.98    4995  314.42
  5005.8  315.04  5017.8  321.98  5026.3  324.49  5054.6   325.5  5118.4  330.25
    5154  334.03  5192.3  336.08  5290.3  341.06  5340.7  342.12  5344.6  342.96
#Mann= 8 ,-1 , 0
  4243.7     .17       0  4436.8     .11       0  4479.1     .15       0
  4618.2     .17       0  4679.6     .15       0  4976.6     .09       0
  5026.3     .15       0  5192.3     .17       0
Bank Sta=4976.6,5026.3
XS Rating Curve= 0 ,0
Exp/Cntr=0.3,0.1

Type RM Length L Ch R = 1 ,78126   ,208,208,208
BEGIN DESCRIPTION:
WEST SANDY CREEK 135.0
END DESCRIPTION:
XS GIS Cut Line= 3
      3716417.83     10220461.04      3715972.06     10219696.16
      3715514.66     10219457.31
#Sta/Elev= 30
  4114.7   345.5  4181.2  341.95  4253.6  334.79  4276.7  334.14  4304.5  330.65
  4370.4  327.83  4464.9  324.23  4486.5  325.34  4554.5  324.58  4598.1  322.42
  4612.4   323.4  4641.1  318.41  4656.8  322.05  4678.3  323.54  4764.7  323.02
  4823.1  323.73  4910.4  322.45  4934.8  321.27    4962  323.14  4983.5  322.84
  4999.2   315.6  5002.8  312.94    5016  314.14  5021.7  316.04  5027.4  322.25
    5110  324.26  5207.8  326.73  5286.8   332.5  5341.7  333.12    5516  339.97
#Mann= 7 ,-1 , 0
  4114.7     .17       0  4370.4     .15       0  4764.7     .17       0
  4910.4     .15       0  4983.5     .09       0  5027.4     .15       0
    5110     .17       0
Bank Sta=4983.5,5027.4
XS Rating Curve= 0 ,0
Exp/Cntr=0.3,0.1

Type RM Length L Ch R = 1 ,77918   ,291,291,291
XS GIS Cut Line= 3
      3716445.19     10220467.16      3716130.09     10219774.45
      3716518.11     10219008.83
#Sta/Elev= 30
       0  346.07    72.6  343.05   204.4  331.99   303.3  326.22     435  324.21
   492.1   321.5     523  322.74   538.2  321.21     545  319.57   555.8  319.75
     567  321.66   612.9  323.52     636  323.54     659  321.79   676.6  323.39
   733.7  322.57     776  322.94     791  321.41   807.7   313.7   813.3  312.75
     818  312.75   843.3  323.76   874.5  322.62   985.9  324.68  1089.9  323.06
  1141.8  324.34  1169.6  323.01  1291.7  325.72  1482.3  335.48  1619.3  340.93
#Mann= 7 ,-1 , 0
       0     .17       0     435     .15       0   538.2     .17       0
   733.7     .15       0     776     .09       0   843.3     .15       0
  1089.9     .17       0
#XS Ineff= 1 ,-1
   985.9    1250  324.68
Permanent Ineff=
       F
Bank Sta=776,843.3
XS Rating Curve= 0 ,0
Exp/Cntr=0.3,0.1

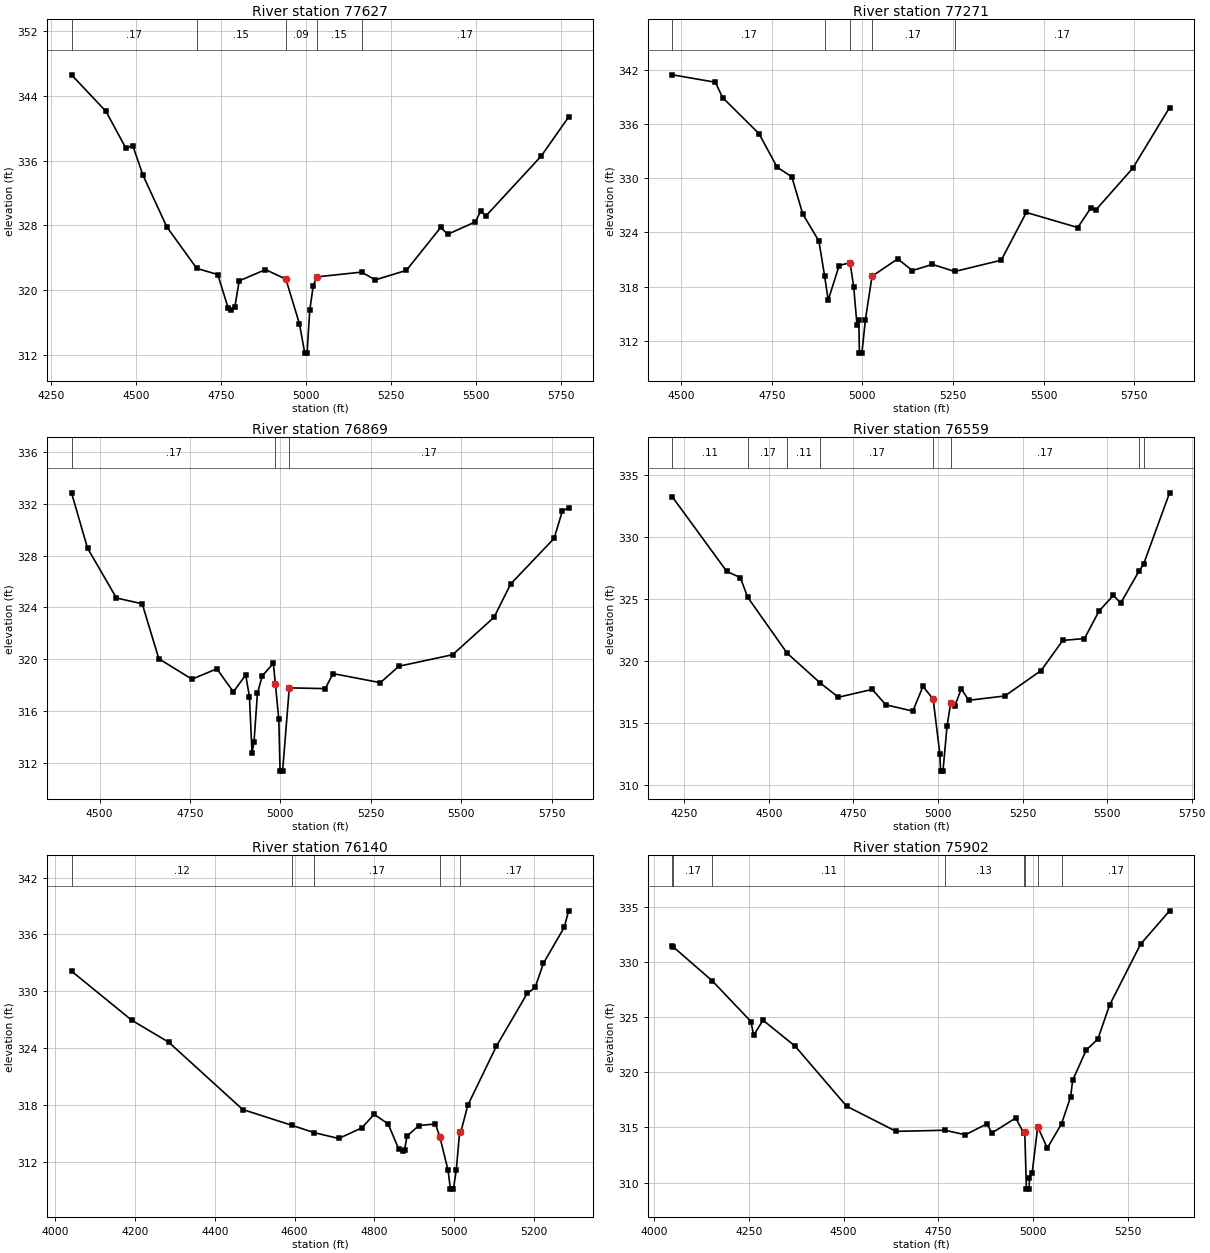
Type RM Length L Ch R = 1 ,77627   ,356,356,356
BEGIN DESCRIPTION:
WEST SANDY CREEK 134.0
END DESCRIPTION:
XS GIS Cut Line= 3
      3716467.85     10220461.04      3716432.74     10219772.14
      3716567.86     10219011.04
#Sta/Elev= 30
  4310.2   346.6  4411.9  342.07  4470.4  337.51  4490.4  337.86  4520.4   334.2
  4590.5  327.82  4678.7  322.68  4740.7  321.92  4770.8  317.82  4780.8  317.48
  4790.8  317.89  4803.6  321.14  4880.9  322.53    4941  321.36    4981  315.82
  4996.6  312.21  5003.4  312.21  5011.2  317.48  5021.4  320.49  5031.6  321.63
  5163.7  322.22  5204.2  321.26  5295.6  322.44  5396.6  327.74  5417.5   326.9
  5498.7  328.43  5514.7  329.79  5529.2  329.14    5692  336.54    5773  341.38
#Mann= 5 ,-1 , 0
  4310.2     .17       0  4678.7     .15       0    4941     .09       0
  5031.6     .15       0  5163.7     .17       0
Bank Sta=4941,5031.6
XS Rating Curve= 0 ,0
Exp/Cntr=0.3,0.1

Type RM Length L Ch R = 1 ,77271   ,402,402,402
BEGIN DESCRIPTION:
WEST SANDY CREEK 133.0
END DESCRIPTION:
XS GIS Cut Line= 3
      3716706.05     10220418.71      3716753.79     10219897.84
      3716617.85     10219061.07
#Sta/Elev= 30
  4476.2  341.46  4594.3  340.64  4614.4  338.94  4714.8  334.94  4764.9  331.22
  4805.2  330.17  4835.3  326.06  4879.9  323.05  4895.6  319.21  4905.6  316.51
  4935.8  320.34  4965.9  320.66  4975.9  317.98  4984.9   313.8    4990  314.26
  4991.7  310.64  4998.5  310.64  5008.2  314.33  5026.4  319.15  5097.3  321.08
  5137.8  319.78  5192.9  320.47  5254.5  319.68  5382.7  320.93  5451.9  326.22
  5593.7  324.55    5629  326.66  5644.4  326.53  5745.7  331.13    5847  337.84
#Mann= 5 ,-1 , 0
  4476.2     .17       0  4895.6     .17       0  4965.9     .09       0
  5026.4     .17       0  5254.5     .17       0
Bank Sta=4965.9,5026.4
XS Rating Curve= 0 ,0
Exp/Cntr=0.3,0.1

Type RM Length L Ch R = 1 ,76869   ,310,310,310
BEGIN DESCRIPTION:
Mapping XS 99fd2e4a
END DESCRIPTION:
XS GIS Cut Line= 3
      3717307.18     10220375.23      3717302.84      10220184.3
      3716805.87     10219110.07
#Sta/Elev= 30
  4422.5  332.84  4466.7  328.57  4546.7  324.72    4618  324.27  4663.9  320.03
  4755.6  318.45  4824.3  319.25  4870.2  317.47  4904.1  318.78  4914.5   317.1
  4921.6  312.76  4927.1  313.57  4936.6  317.36    4950   318.7  4980.6  319.68
  4986.2 318.081  4995.8  315.34  4999.2  311.35  5006.2  311.35  5024.7  317.78
  5123.9  317.72  5145.9  318.88  5276.5  318.18  5327.8  319.45  5476.5  320.34
    5591  323.23  5636.9   325.8    5757  329.32    5780  331.45  5797.1  331.69
#Mann= 3 , 0 , 0
  4422.5     .17       0  4986.2     .09       0  5024.7     .17       0
Bank Sta=4986.2,5024.7
XS Rating Curve= 0 ,0
Exp/Cntr=0.3,0.1

Type RM Length L Ch R = 1 ,76559   ,419,419,419
BEGIN DESCRIPTION:
WEST SANDY CREEK 132.0
END DESCRIPTION:
XS GIS Cut Line= 3
      3717404.84      10220481.6      3717404.84     10219685.17
      3717166.17     10219055.95
#Sta/Elev= 30
  4215.3  333.22  4375.8  327.22  4415.8  326.73  4437.6  325.14  4554.5  320.62
  4652.8  318.21  4705.8  317.08  4805.8  317.71  4845.8  316.47  4925.8  315.96
  4955.8  317.96  4985.8  316.92  5005.8  312.47  5007.7  311.12  5014.8  311.12
  5026.8  314.72  5037.5   316.6  5049.5  316.35    5069  317.76    5091  316.83
  5197.9  317.18  5304.9  319.23  5369.1  321.66  5433.2  321.81    5476  324.02
  5518.8   325.3  5540.2  324.67    5594  327.23  5607.8   327.8  5684.7  333.56
#Mann= 8 ,-1 , 0
  4215.3     .11       0  4437.6     .17       0  4554.5     .11       0
  4652.8     .17       0  4985.8     .09       0  5037.5     .17       0
    5594     .15       0  5607.8     .17       0
Bank Sta=4985.8,5037.5
XS Rating Curve= 0 ,0
Exp/Cntr=0.3,0.1

Type RM Length L Ch R = 1 ,76140   ,238,238,238
BEGIN DESCRIPTION:
WEST SANDY CREEK 131.0
END DESCRIPTION:
XS GIS Cut Line= 3
      3717541.11      10220507.7      3717777.23     10219559.73
      3717853.25     10219300.58
#Sta/Elev= 30
  4040.6  332.13  4191.7  326.94  4284.5  324.62    4470  317.51  4593.6  315.84
    4649  315.07    4711  314.45  4768.8  315.57  4799.7     317  4834.9  315.99
  4861.6  313.32    4871  313.16  4876.2  313.25  4882.2  314.71  4912.3  315.82
  4953.6  315.98  4964.6  314.61  4985.2  311.09  4991.2   309.1  4998.5   309.1
  5005.8   311.1  5014.3  315.17  5017.5  315.17  5034.6  317.95  5106.6  324.21
  5183.8  329.78  5203.7  330.41  5224.6  332.97  5276.7  336.76  5287.6   338.5
#Mann= 5 ,-1 , 0
  4040.6     .12       0  4593.6     .12       0    4649     .17       0
  4964.6     .09       0  5014.3     .17       0
Bank Sta=4964.6,5014.3
XS Rating Curve= 0 ,0
Exp/Cntr=0.3,0.1

Type RM Length L Ch R = 1 ,75902   ,303,303,303
BEGIN DESCRIPTION:
WEST SANDY CREEK 130.0
END DESCRIPTION:
XS GIS Cut Line= 3
      3717673.08     10220566.64      3717978.62     10219674.32
      3718058.48     10219316.71
#Sta/Elev= 30
  4049.2  331.47  4051.5  331.36    4154  328.29  4255.9   324.6  4262.9  323.34
  4287.6  324.72  4372.2  322.37  4507.9  316.92  4638.4  314.64  4767.1  314.74
  4820.8  314.33  4878.1  315.33  4890.1  314.48  4953.5  315.85    4974  314.52
  4977.3   314.6  4981.6   309.4  4988.9   309.4  4989.4  310.45  4996.6  310.82
  5011.4  315.06  5036.7  313.12  5074.3  315.34  5098.2  317.78  5103.4  319.27
  5139.2  322.01  5169.9  323.01  5200.6  326.08  5282.3  331.61  5358.8  334.64
#Mann= 8 ,-1 , 0
  4049.2     .11       0  4051.5     .17       0    4154     .11       0
  4767.1     .13       0    4974     .13       0  4977.3     .09       0
  5011.4     .13       0  5074.3     .17       0
Bank Sta=4977.3,5011.4
XS Rating Curve= 0 ,0
Exp/Cntr=0.3,0.1