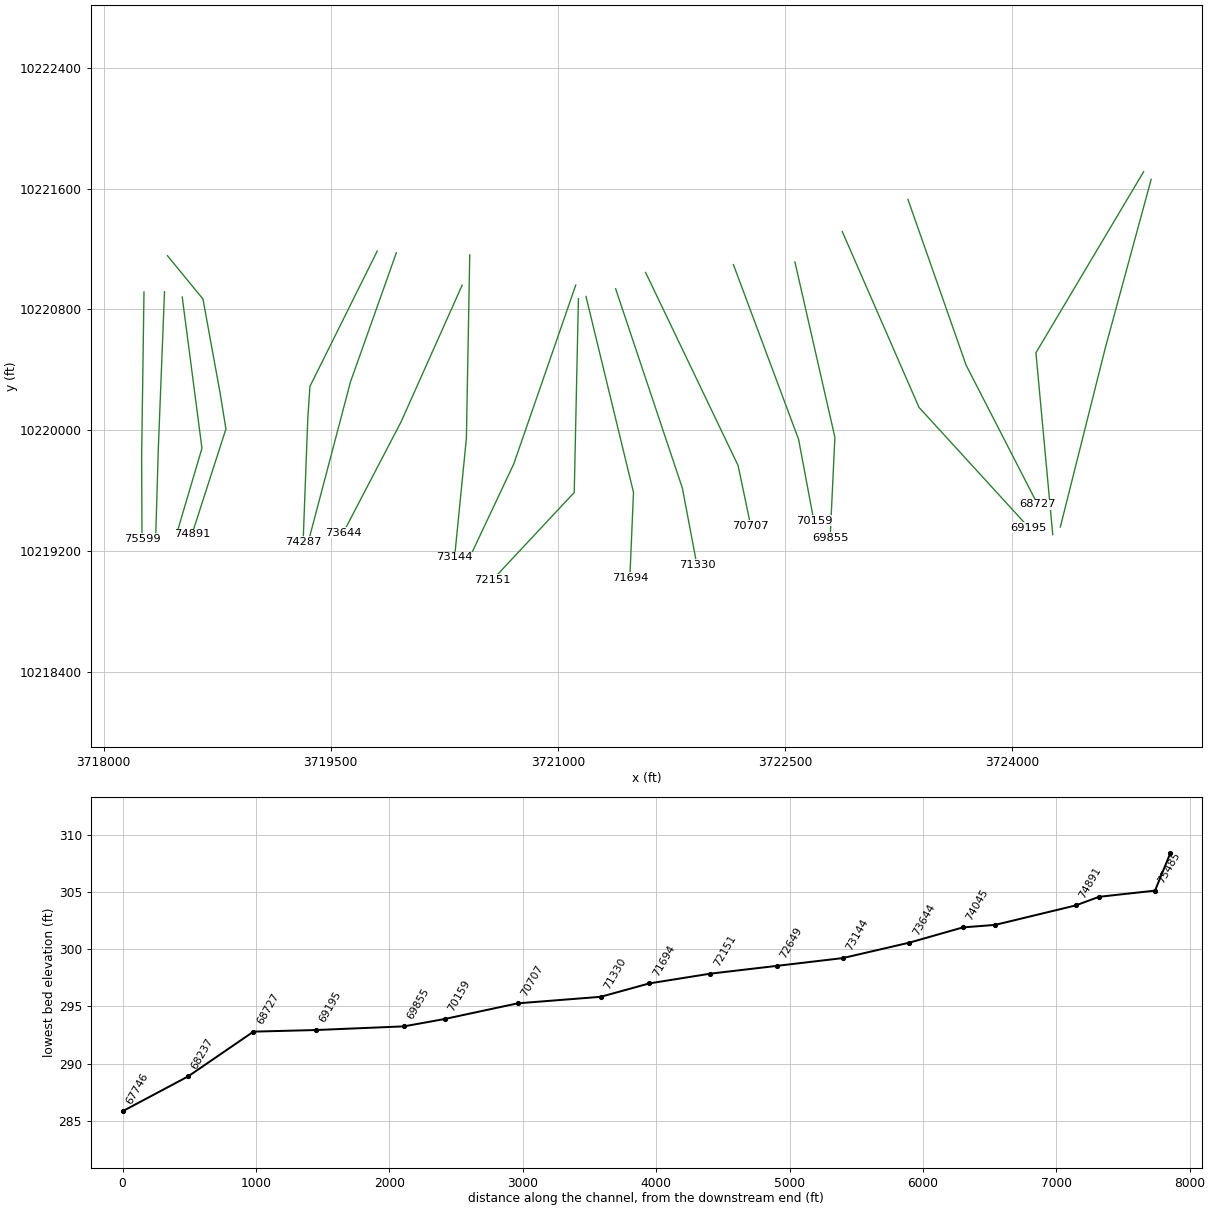
HEC-RAS study WEST SANDY CREEK.prj: WEST SANDY CREEK Base Level Engineering

--- WEST SANDY CREEK.g01 (geometry) --- (continued)

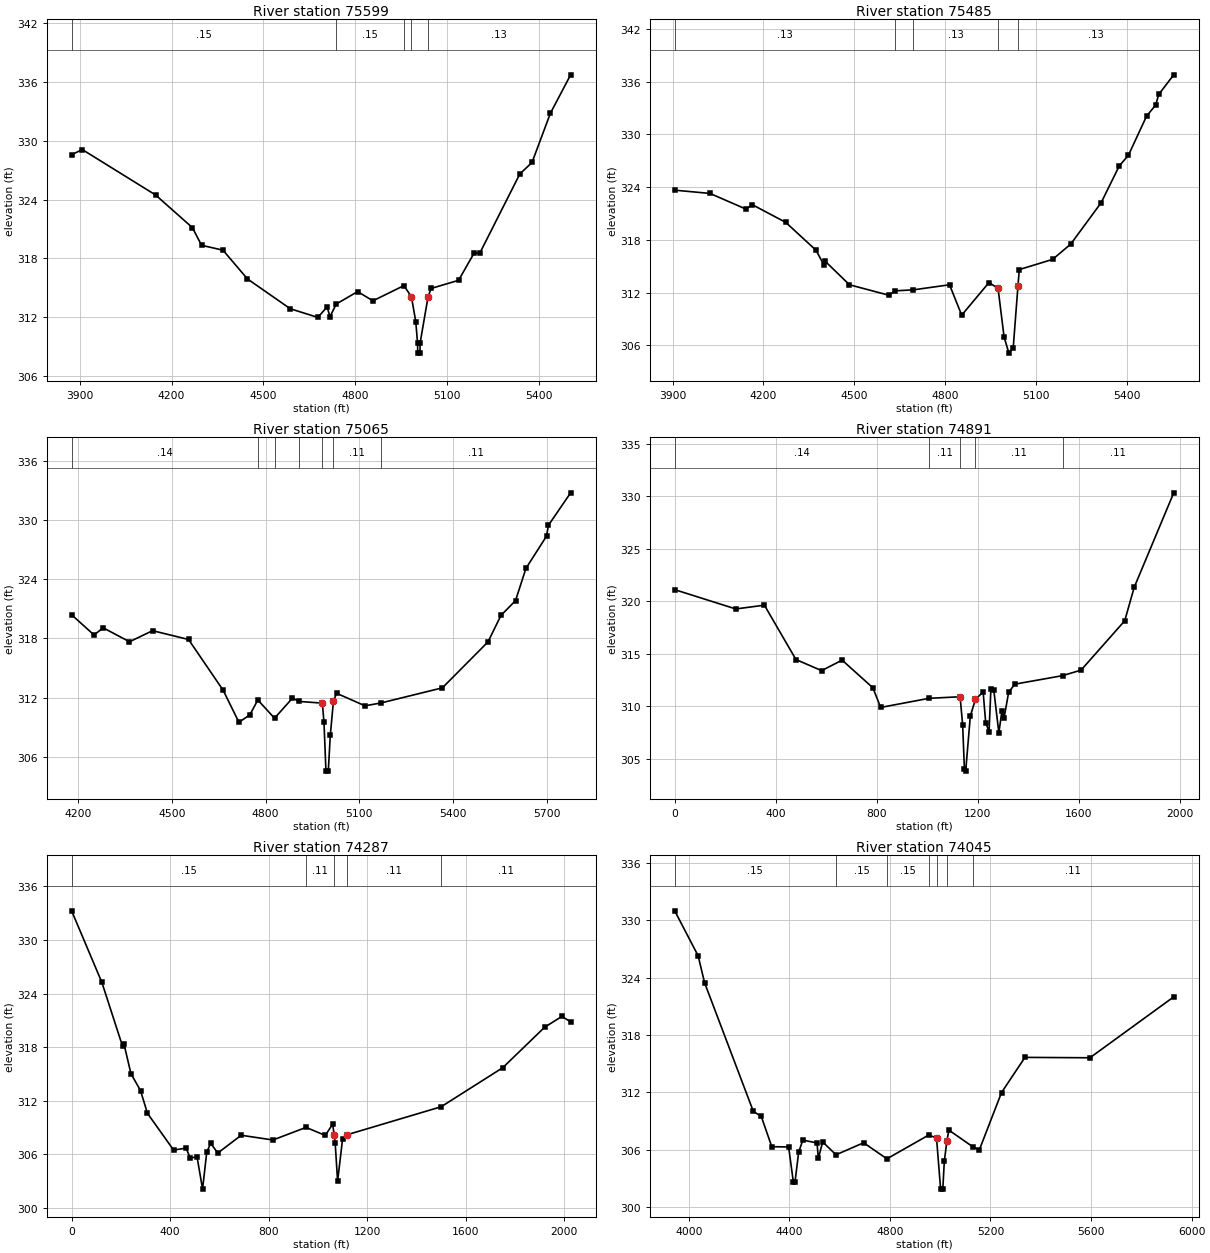
Type RM Length L Ch R = 1 ,75599   ,114,114,114
BEGIN DESCRIPTION:
Mapping XS 147827e9
END DESCRIPTION:
XS GIS Cut Line= 3
      3718266.69     10220915.77      3718251.21     10219829.88
      3718253.42     10219284.88
#Sta/Elev= 30
  3873.4  328.56  3908.1   329.1  4148.1  324.46  4268.1  321.14  4298.1  319.34
  4368.1  318.84  4448.2  315.91  4588.2  312.87  4678.2  311.99  4708.2  313.05
  4718.2  312.07  4738.2  313.35  4808.2  314.62  4858.2  313.68  4959.4  315.23
    4984 314.101  4998.2  311.57  5004.1  309.37  5004.6  308.35  5011.9  308.35
  5012.4  309.37  5038.2  314.05  5048.2  314.94  5138.2  315.77  5188.2  318.51
  5208.2  318.58  5338.2   326.6  5378.2  327.78  5438.2  332.79  5504.4  336.71
#Mann= 5 ,-1 , 0
  3873.4     .15       0  4738.2     .15       0  4959.4     .13       0
    4984     .08       0  5038.2     .13       0
Bank Sta=4984,5038.2
XS Rating Curve= 0 ,0
Exp/Cntr=0.3,0.1

Type RM Length L Ch R = 1 ,75485   ,420,420,420
BEGIN DESCRIPTION:
WEST SANDY CREEK 129.0
END DESCRIPTION:
XS GIS Cut Line= 3
      3718402.23     10220917.39      3718361.78     10219891.81
      3718343.21     10219271.56
#Sta/Elev= 30
  3907.2  323.65  4023.6  323.28    4142   321.5  4163.7  321.99  4273.8  319.98
  4373.9   316.8    4399  315.16    4404  315.55    4484  312.88  4614.1  311.69
  4634.1  312.19  4694.1   312.3  4814.2  312.88  4854.3  309.42  4944.3  313.13
  4974.3  312.48  4994.3  306.92  5010.2   305.1  5024.4  305.72    5040 312.731
  5044.4  314.61  5154.4  315.77  5214.4  317.52  5314.5  322.22  5374.5  326.42
  5404.5  327.62  5464.6  332.09  5494.6  333.34  5504.6  334.55  5554.1  336.78
#Mann= 5 ,-1 , 0
  3907.2     .13       0  4634.1     .13       0  4694.1     .13       0
  4974.3     .08       0    5040     .13       0
Bank Sta=4974.3,5040
XS Rating Curve= 0 ,0
Exp/Cntr=0.3,0.1

Type RM Length L Ch R = 1 ,75065   ,174,174,174
BEGIN DESCRIPTION:
WEST SANDY CREEK 128.0
END DESCRIPTION:
XS GIS Cut Line= 3
      3718519.23     10220882.21      3718649.45     10219882.16
      3718482.82     10219317.21
#Sta/Elev= 30
  4178.8   320.4  4250.5  318.36    4280  319.08  4364.1  317.67  4438.1  318.79
  4553.1   317.9    4664  312.75  4714.4  309.51  4749.3  310.26  4774.9  311.77
  4828.4  309.92  4885.9  311.96  4907.5  311.62  4981.5  311.45  4986.7  309.51
    4993  304.56  5000.5  304.56  5006.9  308.19    5017  311.66    5027  312.45
  5117.8  311.18  5168.2  311.46  5365.7     313  5511.6  317.65  5553.3  320.34
  5599.9  321.84  5633.2   325.1  5699.3  328.38    5705  329.46  5776.3  332.76
#Mann= 7 ,-1 , 0
  4178.8     .14       0  4774.9     .14       0  4828.4     .14       0
  4907.5     .11       0  4981.5     .06       0    5017     .11       0
  5168.2     .11       0
#XS Ineff= 1 ,-1
    5027    5340  312.45
Permanent Ineff=
       F
Bank Sta=4981.5,5017
XS Rating Curve= 0 ,0
Exp/Cntr=0.3,0.1

Type RM Length L Ch R = 1 ,74891   ,604,604,604
XS GIS Cut Line= 5
       3718421.8     10221155.63      3718656.18     10220869.17
      3718770.76     10220238.96      3718807.83     10220009.97
      3718583.26     10219311.88
#Sta/Elev= 30
       0  321.11   241.7  319.27   355.1  319.63     480  314.45   581.6  313.39
   662.9  314.39   784.9  311.75   815.4  309.88    1007  310.75  1130.1   310.9
  1140.2  308.21  1147.1  304.04  1152.2  303.81  1170.6  309.07  1190.9  310.65
  1221.3  311.36  1231.4  308.43  1244.7  307.58    1252  311.62  1263.3  311.59
  1283.5  307.46  1295.4   309.5  1304.5  308.92  1322.2  311.31  1346.5   312.1
  1535.6  312.91  1609.1  313.44  1781.9  318.14  1819.3  321.32    1976  330.34
#Mann= 5 ,-1 , 0
       0     .14       0    1007     .11       0  1130.1     .06       0
  1190.9     .11       0  1535.6     .11       0
Bank Sta=1130.1,1190.9
XS Rating Curve= 0 ,0
Exp/Cntr=0.3,0.1

Type RM Length L Ch R = 1 ,74287   ,242,242,242
XS GIS Cut Line= 4
      3719807.22     10221186.88       3719362.5     10220291.18
      3719348.35      10220077.2      3719317.64       10219265.
#Sta/Elev= 30
       0  333.26     123  325.24     207  318.09   212.6  318.36   240.9  315.04
   279.8  313.14   307.9   310.6   414.3  306.48   464.7   306.7   481.5  305.61
   509.5  305.71   531.9  302.11   548.7  306.23   564.7  307.24   593.6  306.15
   688.8  308.14   817.6  307.61   952.1  309.02  1030.2  308.12  1060.3  309.39
    1066  308.21  1070.3  307.32  1080.3     303  1100.4   307.7  1120.4  308.21
  1500.8  311.33    1751   315.7  1921.1  320.23  1991.2  321.44  2026.7  320.84
#Mann= 5 ,-1 , 0
       0     .15       0   952.1     .11       0    1066     .06       0
  1120.4     .11       0  1500.8     .11       0
Bank Sta=1066,1120.4
XS Rating Curve= 0 ,0
Exp/Cntr=0.3,0.1

Type RM Length L Ch R = 1 ,74045   ,401,401,401
BEGIN DESCRIPTION:
WEST SANDY CREEK 127.0
END DESCRIPTION:
XS GIS Cut Line= 3
      3719933.31      10221175.6        3719630.     10220320.09
      3719356.03     10219278.82
#Sta/Elev= 30
  3944.3     331  4037.4   326.3  4062.9  323.49  4256.8  310.03  4288.6  309.49
  4330.2  306.33  4397.3   306.3  4415.9  302.67  4422.9  302.68  4437.2  305.75
  4453.7  307.02  4510.2  306.72  4515.5  305.11  4532.7  306.83  4585.7  305.48
  4695.5  306.74  4788.1  305.06  4953.9  307.54  4985.4  307.25  5001.7  301.89
  5010.4  301.89  5016.4   304.8  5026.8  306.96  5034.6  308.06  5130.2  306.31
  5155.6  305.99  5243.9  311.99    5337  315.67  5595.5  315.63  5928.7     322
#Mann= 7 ,-1 , 0
  3944.3     .15       0  4585.7     .15       0  4788.1     .15       0
  4953.9     .11       0  4985.4     .06       0  5026.8     .11       0
  5130.2     .11       0
Bank Sta=4985.4,5026.8
XS Rating Curve= 0 ,0
Exp/Cntr=0.3,0.1

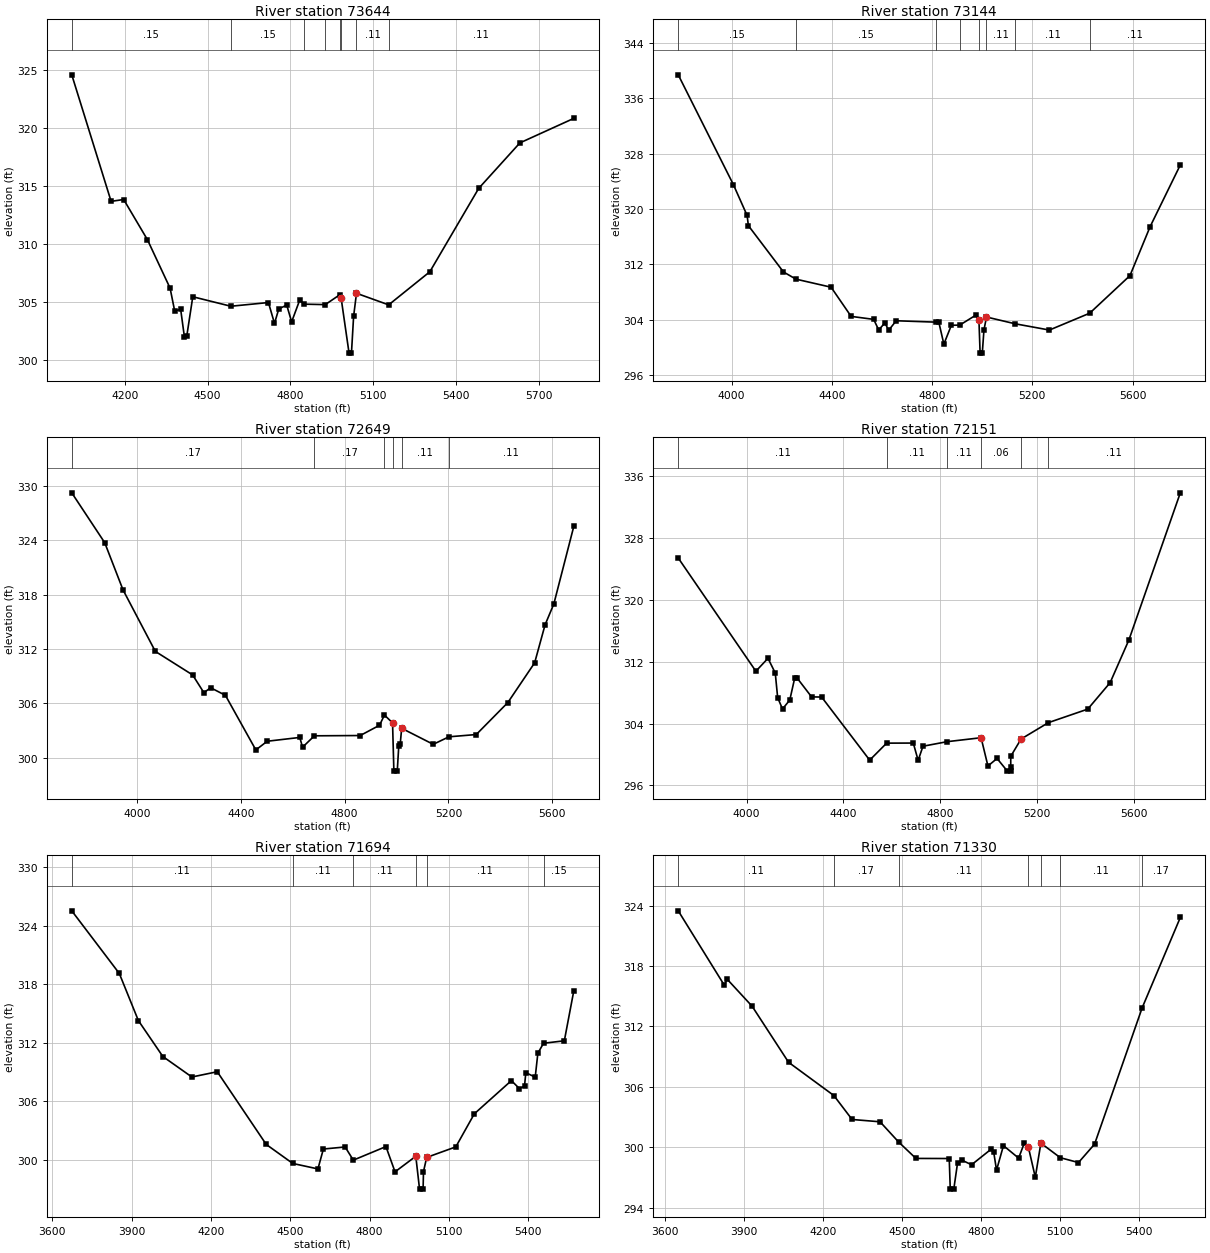
Type RM Length L Ch R = 1 ,73644   ,500,500,500
BEGIN DESCRIPTION:
WEST SANDY CREEK 126.0
END DESCRIPTION:
XS GIS Cut Line= 3
      3720367.86     10220961.09      3719963.93     10220055.82
      3719582.31     10219323.37
#Sta/Elev= 30
  4008.7   324.6  4151.1  313.67  4196.6  313.83  4282.5  310.36  4364.6  306.17
    4381  304.22  4402.9  304.33  4416.5  301.94  4424.8  302.01  4446.7  305.43
  4584.5  304.61  4720.5  304.93  4742.4  303.13    4758  304.38  4786.7  304.71
  4804.5  303.26  4833.2  305.11  4850.2  304.79  4926.1  304.75    4978  305.59
  4983.4  305.35  5012.3  300.56    5021  300.56  5028.8  303.74  5039.2  305.73
  5155.7  304.73  5304.7  307.59  5481.5  314.79  5630.6  318.72  5825.9  320.84
#Mann= 8 ,-1 , 0
  4008.7     .15       0  4584.5     .15       0  4850.2     .15       0
  4926.1     .11       0    4978     .09       0  4983.4     .06       0
  5039.2     .11       0  5155.7     .11       0
Bank Sta=4983.4,5039.2
XS Rating Curve= 0 ,0
Exp/Cntr=0.3,0.1

Type RM Length L Ch R = 1 ,73144   ,495,495,495
BEGIN DESCRIPTION:
WEST SANDY CREEK 125.0
END DESCRIPTION:
XS GIS Cut Line= 3
      3720417.85     10221161.05      3720395.78     10219947.95
      3720317.85      10219161.1
#Sta/Elev= 30
  3786.7  339.36  4006.7  323.53  4061.6  319.07  4066.7   317.6  4206.7  310.92
  4256.8  309.88  4396.8  308.72  4476.8  304.51  4566.8  304.08  4586.8  302.56
  4611.4  303.56  4626.8  302.52  4656.8  303.88    4815  303.68  4826.8  303.67
  4846.9  300.51  4876.9  303.23  4910.1  303.25  4976.9  304.74  4986.9  304.04
  4991.6  299.21  5000.3  299.21  5006.9  302.53    5017  304.42  5131.8  303.44
  5268.2  302.54    5429  304.97  5589.7  310.39  5670.1  317.45  5790.7  326.36
#Mann= 8 ,-1 , 0
  3786.7     .15       0  4256.8     .15       0    4815     .11       0
  4910.1     .11       0  4986.9     .06       0    5017     .11       0
  5131.8     .11       0    5429     .11       0
Bank Sta=4986.9,5017
XS Rating Curve= 0 ,0
Exp/Cntr=0.3,0.1

Type RM Length L Ch R = 1 ,72649   ,498,498,498
BEGIN DESCRIPTION:
WEST SANDY CREEK 124.0
END DESCRIPTION:
XS GIS Cut Line= 3
      3721117.85     10220961.08      3720708.73     10219778.87
      3720417.83     10219161.03
#Sta/Elev= 30
    3749  329.26    3876  323.75  3946.3  318.55  4070.9  311.75  4214.6  309.15
  4257.9  307.19  4283.8  307.74  4340.8   306.9    4458  300.87  4501.9  301.83
  4627.3  302.25  4637.9  301.17  4683.6  302.43    4860  302.46  4934.2  303.59
  4953.4  304.72  4984.6  303.86  4989.7  298.53  5002.7  298.53  5008.5  301.29
    5014  301.48  5019.7  303.26  5141.3  301.49  5201.8  302.32    5307  302.57
  5428.6   306.1  5531.9  310.49    5572  314.68  5605.8  316.99  5682.9  325.58
#Mann= 6 ,-1 , 0
    3749     .17       0  4683.6     .17       0  4953.4     .11       0
  4984.6     .06       0  5019.7     .11       0  5201.8     .11       0
Bank Sta=4984.6,5019.7
XS Rating Curve= 0 ,0
Exp/Cntr=0.3,0.1

Type RM Length L Ch R = 1 ,72151   ,457,457,457
BEGIN DESCRIPTION:
WEST SANDY CREEK 123.0
END DESCRIPTION:
XS GIS Cut Line= 3
      3721135.56     10220871.71      3721107.88     10219589.61
      3720567.86     10219011.08
#Sta/Elev= 30
  3717.6  325.41  4038.3  310.77  4088.3  312.44  4118.3  310.54  4128.3  307.35
  4148.3  305.89  4178.3  307.04  4198.3  309.84  4208.3   309.9  4268.4  307.45
  4309.9  307.43  4508.4  299.27  4578.4  301.47  4688.5  301.48  4708.5  299.24
  4728.5  301.07  4828.5  301.66  4968.5  302.17  4996.8  298.51  5034.4  299.49
  5077.1  297.85  5090.4  297.85  5090.9  298.35  5091.1  299.77  5133.6     302
  5246.5  304.12  5409.1  305.87  5501.5  309.29  5579.1  314.82  5791.4  333.84
#Mann= 6 ,-1 , 0
  3717.6     .11       0  4578.4     .11       0  4828.5     .11       0
  4968.5     .06       0  5133.6     .11       0  5246.5     .11       0
Bank Sta=4968.5,5133.6
XS Rating Curve= 0 ,0
Exp/Cntr=0.3,0.1

Type RM Length L Ch R = 1 ,71694   ,364,364,364
BEGIN DESCRIPTION:
WEST SANDY CREEK 122.0
END DESCRIPTION:
XS GIS Cut Line= 3
      3721185.55     10220885.85       3721499.3     10219590.05
      3721475.04     10219025.11
#Sta/Elev= 30
  3673.6  325.52  3853.4   319.1  3925.5  314.27  4018.1  310.59  4127.8  308.49
  4223.8  309.03    4409  301.58  4509.4  299.63  4604.5  299.07  4625.1  301.11
  4707.4  301.32  4738.3  299.97  4861.7  301.36  4896.1  298.77  4974.6  300.37
  4988.8     297  5002.2     297  5003.7   298.8  5015.8  300.25  5125.9  301.33
    5196  304.72  5336.1  308.12  5366.2  307.31  5385.7  307.55  5390.7  308.94
  5426.2  308.47  5436.2  310.93  5457.7  311.95  5536.3   312.2  5572.3  317.35
#Mann= 6 ,-1 , 0
  3673.6     .11       0  4509.4     .11       0  4738.3     .11       0
  4974.6     .06       0  5015.8     .11       0  5457.7     .15       0
Bank Sta=4974.6,5015.8
XS Rating Curve= 0 ,0
Exp/Cntr=0.3,0.1

Type RM Length L Ch R = 1 ,71330   ,623,623,623
BEGIN DESCRIPTION:
WEST SANDY CREEK 121.0
END DESCRIPTION:
XS GIS Cut Line= 3
      3721381.26     10220937.22      3721822.22     10219617.83
      3721917.85      10219111.1
#Sta/Elev= 30
  3650.3  323.48  3825.5  316.08    3836  316.69  3930.9     314  4069.4  308.43
  4241.3  305.13  4310.5  302.75  4416.8  302.52  4487.7   300.5    4553  298.88
  4679.5  298.87  4683.4  295.83  4696.8  295.83  4711.2  298.45  4727.5  298.71
  4764.3  298.25  4837.7  299.78  4848.2  299.55  4859.1  297.71  4885.4  300.15
  4943.1  298.91  4964.2  300.38  4980.2  299.99  5006.4  297.01  5027.5   300.4
  5101.5  298.95  5170.4  298.47  5231.5   300.3    5412  313.83  5557.1  322.82
#Mann= 7 ,-1 , 0
  3650.3     .11       0  4241.3     .17       0  4487.7     .11       0
  4980.2     .06       0  5027.5     .11       0  5101.5     .11       0
    5412     .17       0
Bank Sta=4980.2,5027.5
XS Rating Curve= 0 ,0
Exp/Cntr=0.3,0.1

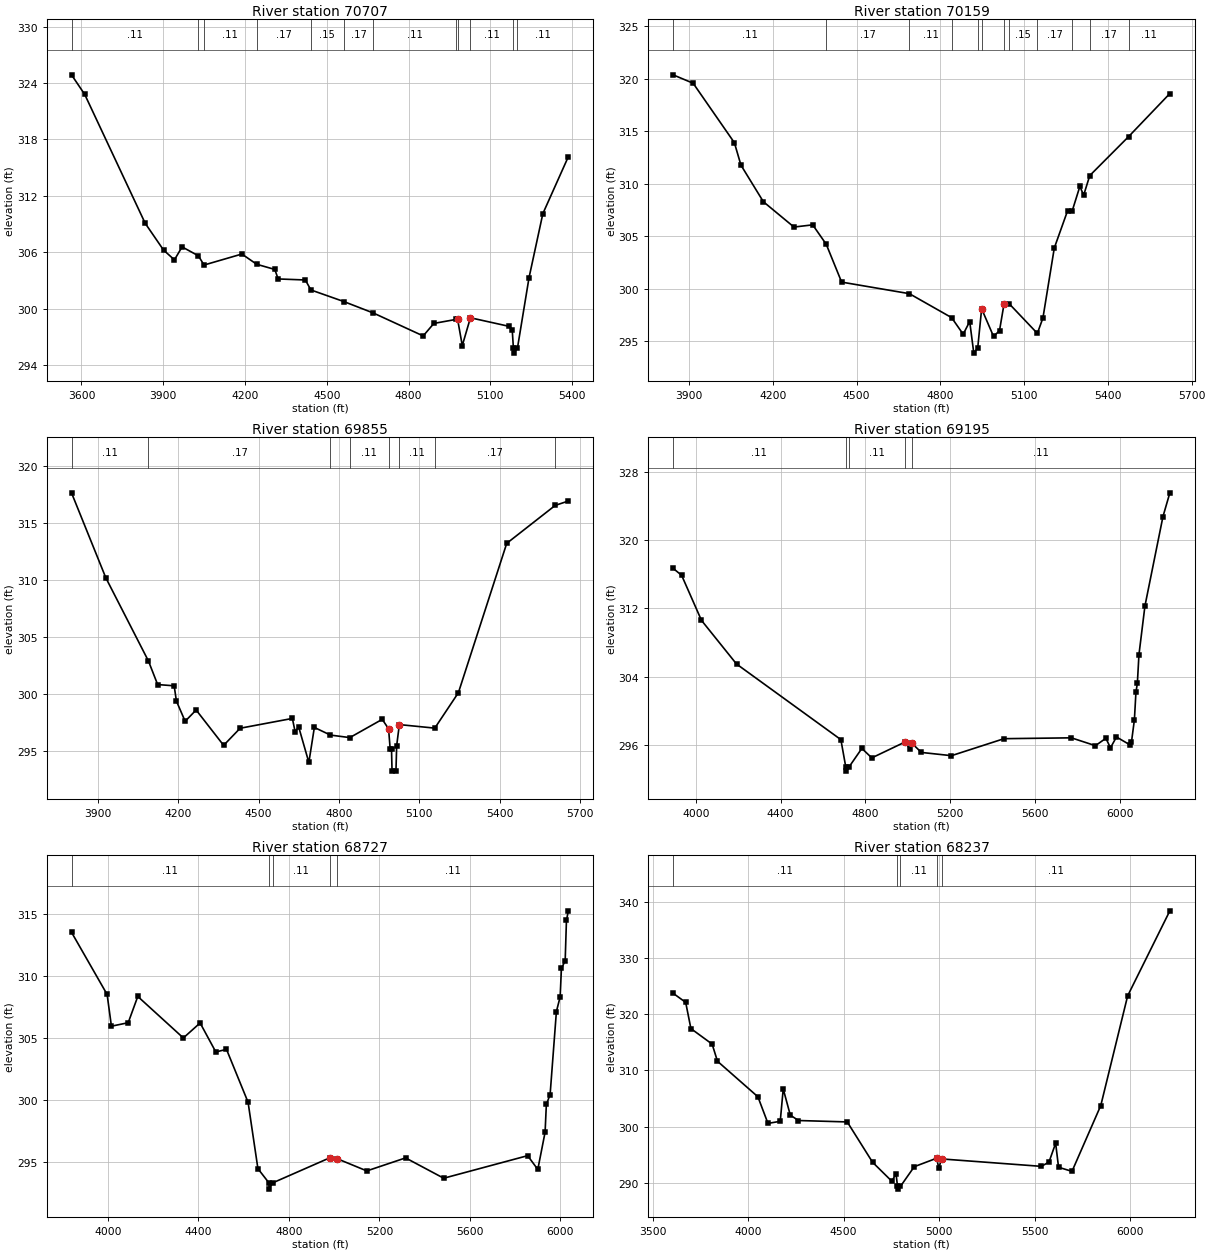
Type RM Length L Ch R = 1 ,70707   ,548,548,548
BEGIN DESCRIPTION:
WEST SANDY CREEK 120.0
END DESCRIPTION:
XS GIS Cut Line= 3
      3721579.16     10221044.91      3722190.27     10219767.13
      3722273.24     10219369.59
#Sta/Elev= 30
  3563.4  324.86    3612  322.77  3833.7  309.07  3901.1  306.22  3940.9  305.18
  3969.1  306.56  4028.8  305.61  4049.6  304.63  4188.4   305.8  4242.7  304.71
  4309.2  304.16  4321.4  303.15  4421.2  303.04  4441.5  301.98  4561.9  300.75
  4670.4  299.53  4853.5  297.09  4892.7  298.42  4974.8  298.85  4979.8  298.85
  4996.9  296.06  5026.8  299.02  5169.9   298.1  5180.1  297.75  5184.5  295.76
    5185  295.26  5199.1  295.76  5241.8  303.29  5292.4  310.09  5385.9  316.15
#Mann= 12 ,-1 , 0
  3563.4     .11       0  4028.8     .17       0  4049.6     .11       0
  4242.7     .17       0  4441.5     .15       0  4561.9     .17       0
  4670.4     .11       0  4974.8     .09       0  4979.8     .06       0
  5026.8     .11       0  5184.5     .09       0  5199.1     .11       0
Bank Sta=4979.8,5026.8
XS Rating Curve= 0 ,0
Exp/Cntr=0.3,0.1

Type RM Length L Ch R = 1 ,70159   ,304,304,304
BEGIN DESCRIPTION:
WEST SANDY CREEK 119.0
END DESCRIPTION:
XS GIS Cut Line= 3
      3722159.02     10221096.99      3722589.58     10219940.74
      3722689.95     10219404.26
#Sta/Elev= 30
  3842.3  320.38  3914.3  319.58    4062  313.92  4085.6  311.78  4165.9   308.3
  4275.5  305.89  4342.6   306.1  4391.1  304.25  4446.2  300.65  4688.8  299.55
  4840.1  297.27  4881.6  295.69    4905   296.9  4919.6  293.89  4933.7  294.39
  4947.7  298.11  4990.4  295.48  5011.7  296.03    5028  298.58  5046.8  298.58
  5147.3  295.77  5167.3  297.24    5208   303.9  5255.4  307.43  5271.7  307.39
  5299.6  309.76  5313.1  308.92    5335  310.79  5473.8  314.49  5621.9   318.6
#Mann= 12 ,-1 , 0
  3842.3     .11       0  4391.1     .17       0  4688.8     .11       0
  4840.1     .17       0  4933.7     .17       0  4947.7     .09       0
    5028     .17       0  5046.8     .15       0  5147.3     .17       0
  5271.7     .11       0    5335     .17       0  5473.8     .11       0
Bank Sta=4947.7,5028
XS Rating Curve= 0 ,0
Exp/Cntr=0.3,0.1

Type RM Length L Ch R = 1 ,69855   ,660,660,660
BEGIN DESCRIPTION:
WEST SANDY CREEK 118.0
END DESCRIPTION:
XS GIS Cut Line= 3
      3722565.27      10221114.4      3722829.16     10219954.63
      3722797.92     10219291.48
#Sta/Elev= 30
  3802.3  317.65  3930.3   310.2  4089.4   302.9  4123.6  300.84  4185.2  300.73
  4193.7  299.39  4226.2  297.62  4267.2  298.61  4369.8  295.51  4431.3  297.01
  4626.2  297.87  4636.4  296.71  4649.8  297.12  4687.7  294.01  4708.2  297.08
  4768.3  296.41  4840.5  296.19  4961.4  297.79  4985.1  296.96    4991   295.2
    4996   295.2    4998  293.25  5012.6  293.25  5015.3  295.49  5025.3  297.33
  5157.5  297.02  5245.6  300.13  5425.8  313.22  5606.9  316.55  5655.6  316.93
#Mann= 8 ,-1 , 0
  3802.3     .11       0  4089.4     .17       0  4768.3     .15       0
  4840.5     .11       0  4985.1     .06       0  5025.3     .11       0
  5157.5     .17       0  5606.9     .11       0
Bank Sta=4985.1,5025.3
XS Rating Curve= 0 ,0
Exp/Cntr=0.3,0.1

Type RM Length L Ch R = 1 ,69195   ,468,468,468
BEGIN DESCRIPTION:
WEST SANDY CREEK 117.0
END DESCRIPTION:
XS GIS Cut Line= 3
      3722877.78     10221315.74      3723384.72     10220152.55
      3724110.43     10219357.39
#Sta/Elev= 30
  3892.3  316.69  3932.8  315.87  4026.5  310.59  4191.9  305.48  4684.6  296.62
  4707.7  293.43  4708.2  292.93  4723.4  293.43  4783.7  295.59  4830.6  294.48
  4988.2  296.35  5010.9  295.48    5021  296.17  5064.6  295.12  5206.7  294.74
  5454.7  296.73  5772.9  296.83  5886.4  295.91  5935.7  296.78  5957.3  295.66
  5985.7  296.93  6049.2  296.01  6056.6  296.35  6070.3  298.94  6077.6  302.17
  6084.3  303.22  6091.8  306.57  6120.1  312.28  6205.2  322.75  6237.7  325.53
#Mann= 5 ,-1 , 0
  3892.3     .11       0  4707.7    .085       0  4723.4     .11       0
  4988.2     .06       0    5021     .11       0
Bank Sta=4988.2,5021
XS Rating Curve= 0 ,0
Exp/Cntr=0.3,0.1

Type RM Length L Ch R = 1 ,68727   ,490,490,490
BEGIN DESCRIPTION:
WEST SANDY CREEK 116.0
END DESCRIPTION:
XS GIS Cut Line= 3
      3723311.81     10221527.54      3723695.59     10220432.12
      3724167.87     10219511.04
#Sta/Elev= 30
  3839.3  313.52  3996.7   308.5  4015.7  305.94  4089.9  306.22  4132.2  308.34
  4333.6  304.99  4407.7   306.2  4477.1  303.86  4524.3  304.07  4619.7   299.8
  4663.2  294.44  4712.1  293.29  4712.6  292.79  4727.8  293.29  4979.9  295.31
  5011.4  295.26  5144.5  294.26  5315.8  295.31  5484.4  293.67  5855.3  295.49
  5900.2  294.38  5932.4  297.38    5938  299.62  5954.6  300.42  5982.4  307.12
    5999  308.31  6004.6   310.6  6021.2  311.22  6026.8  314.47  6035.1  315.25
#Mann= 5 ,-1 , 0
  3839.3     .11       0  4712.1    .085       0  4727.8     .11       0
  4979.9     .06       0  5011.4     .11       0
Bank Sta=4979.9,5011.4
XS Rating Curve= 0 ,0
Exp/Cntr=0.3,0.1

Type RM Length L Ch R = 1 ,68237   ,491,491,491
BEGIN DESCRIPTION:
WEST SANDY CREEK 115.0
END DESCRIPTION:
XS GIS Cut Line= 3
      3724867.84     10221711.05      3724156.79     10220513.67
      3724267.85     10219311.08
#Sta/Elev= 30
  3607.4  323.72  3673.6  322.09  3700.9  317.43    3812  314.67    3840  311.62
  4051.6   305.3  4104.2  300.57  4168.5  300.94  4184.1   306.7  4221.1  302.04
    4264  301.08  4519.2  300.83  4651.7  293.66    4753  290.27  4774.5  291.65
  4782.2  289.38  4782.7  288.88  4797.9  289.38  4869.9  292.87  4986.8  294.37
  4998.6  292.61  5012.6  294.25  5534.9  292.93    5575  293.69  5609.9  297.04
  5625.2  292.77  5695.5  292.04  5846.2  303.75  5986.8  323.25  6207.7  338.37
#Mann= 5 ,-1 , 0
  3607.4     .11       0  4782.2     .09       0  4797.9     .11       0
  4986.8     .06       0  5012.6     .11       0
#XS Ineff= 1 ,-1
  5609.9    5795  297.04
Permanent Ineff=
       F
Bank Sta=4986.8,5012.6
XS Rating Curve= 0 ,0
Exp/Cntr=0.3,0.1

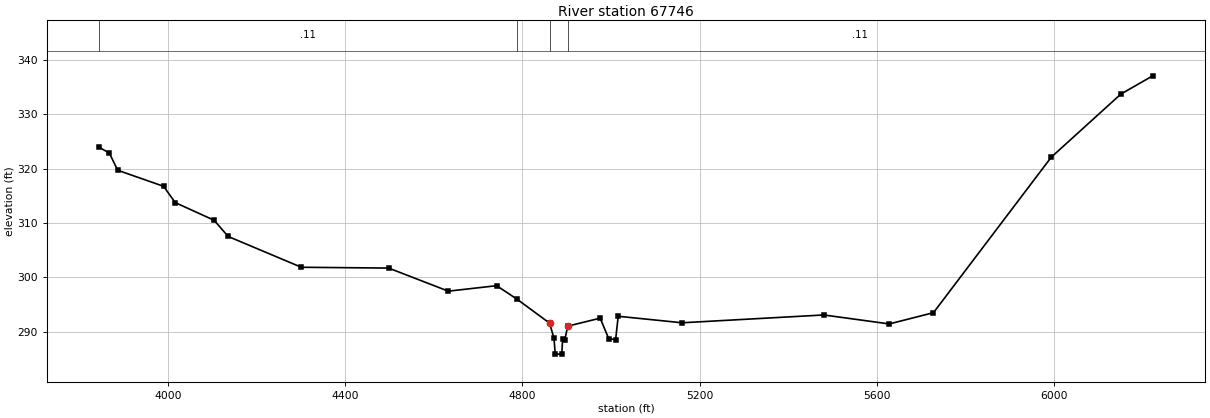
Type RM Length L Ch R = 1 ,67746   ,478,478,478
BEGIN DESCRIPTION:
WEST SANDY CREEK 114.0
END DESCRIPTION:
XS GIS Cut Line= 3
      3724917.84     10221661.04      3724615.31     10220547.09
      3724317.86     10219361.12
#Sta/Elev= 30
  3845.7  323.89  3868.2  322.87  3887.1  319.69  3990.7  316.73    4017  313.73
  4104.7  310.48  4136.4   307.5  4301.6  301.83  4498.5  301.68  4633.2  297.43
  4742.2  298.44  4788.6  295.93  4861.6  291.55  4871.5  288.79  4874.5  285.84
  4889.2  285.84    4891  288.54  4896.2  288.52  4902.6  290.99  4975.8  292.46
  4995.3  288.65  5010.7  288.52  5016.5  292.81  5160.8  291.61  5480.4  293.05
  5628.3   291.4  5727.9  293.47  5993.7  322.09  6150.6   333.7  6222.7  337.07
#Mann= 4 ,-1 , 0
  3845.7     .11       0  4788.6     .17       0  4861.6     .06       0
  4902.6     .11       0
Bank Sta=4861.6,4902.6
XS Rating Curve= 0 ,0
Exp/Cntr=0.3,0.1