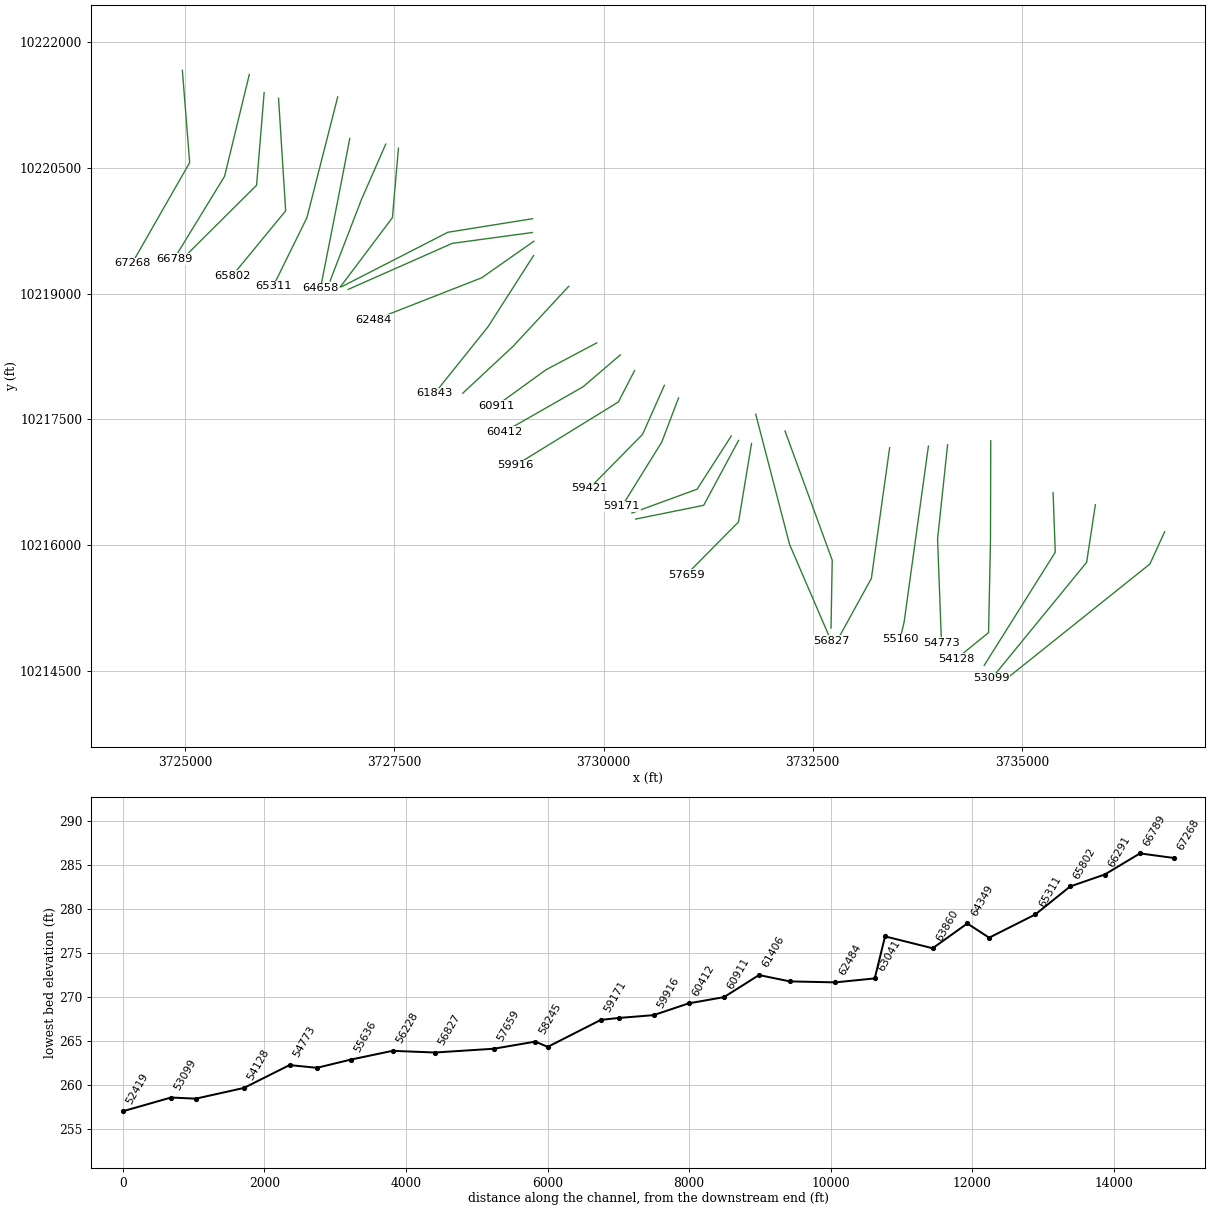
HEC-RAS study WEST SANDY CREEK.prj: WEST SANDY CREEK Base Level Engineering

--- WEST SANDY CREEK.g01 (geometry) --- (continued)

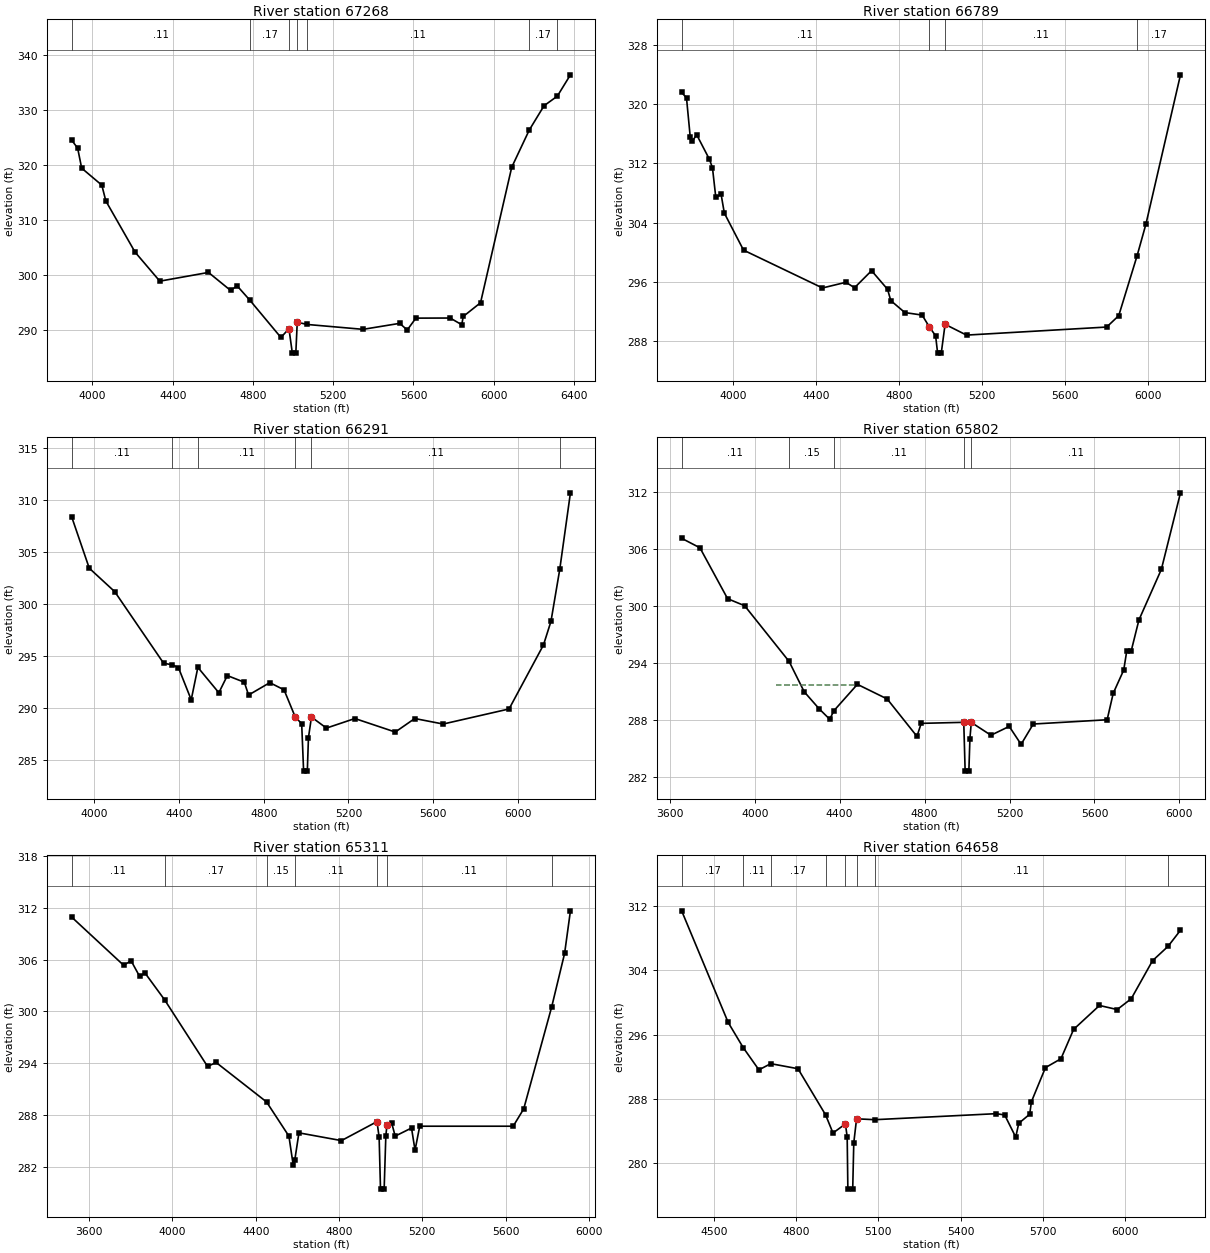
Type RM Length L Ch R = 1 ,67268   ,479,479,479
BEGIN DESCRIPTION:
WEST SANDY CREEK 113.0
END DESCRIPTION:
XS GIS Cut Line= 3
      3724967.85      10221661.1      3725055.12     10220560.46
      3724367.87     10219361.11
#Sta/Elev= 30
  3895.9   324.6    3926  323.12  3946.1  319.48  4046.4  316.39  4066.5  313.51
  4212.1   304.2  4335.5  298.91  4578.1   300.5  4688.4  297.22  4720.9  298.06
  4784.7  295.43  4939.2  288.66  4979.3  290.26  4996.1  285.81  5013.5  285.81
  5020.6  291.44  5069.6  291.03  5348.7  290.14  5531.4  291.23  5568.8  290.02
  5611.9  292.18    5783   292.2  5840.6  290.98  5847.9  292.48  5934.2  294.98
  6089.6  319.64  6176.8   326.4  6250.7  330.84    6317  332.59  6382.3  336.47
#Mann= 7 ,-1 , 0
  3895.9     .11       0  4784.7     .17       0  4979.3     .09       0
  5020.6     .17       0  5069.6     .11       0  6176.8     .17       0
    6317     .11       0
Bank Sta=4979.3,5020.6
XS Rating Curve= 0 ,0
Exp/Cntr=0.3,0.1

Type RM Length L Ch R = 1 ,66789   ,498,498,498
BEGIN DESCRIPTION:
WEST SANDY CREEK 112.0
END DESCRIPTION:
XS GIS Cut Line= 3
      3725767.85     10221611.08       3725472.2     10220397.36
      3724867.87     10219411.09
#Sta/Elev= 30
  3750.8  321.63  3774.2  320.87    3792  315.64  3802.3  314.99  3822.9  315.91
  3884.6  312.57  3899.4  311.43  3915.5  307.41  3941.1  307.82  3956.7  305.28
  4049.3  300.27  4430.1  295.15  4543.3  295.92  4584.5  295.18  4666.8  297.49
  4743.9  294.97  4759.5  293.44  4827.3  291.82  4910.7  291.48  4944.7  289.91
  4975.6  288.68  4985.4  286.33  5002.9  286.33  5021.4  290.23  5124.7  288.77
  5800.8  289.86  5858.9   291.4  5947.5  299.51  5990.4  303.83  6156.7     324
#Mann= 4 ,-1 , 0
  3750.8     .11       0  4944.7     .06       0  5021.4     .11       0
  5947.5     .17       0
Bank Sta=4944.7,5021.4
XS Rating Curve= 0 ,0
Exp/Cntr=0.3,0.1

Type RM Length L Ch R = 1 ,66291   ,489,489,489
BEGIN DESCRIPTION:
WEST SANDY CREEK 111.0
END DESCRIPTION:
XS GIS Cut Line= 3
      3725944.84     10221394.23      3725854.53     10220290.42
      3724967.84     10219411.06
#Sta/Elev= 30
  3892.5  308.41  3975.9  303.45  4096.3  301.19  4327.1  294.31    4369  294.15
  4397.3  293.88  4457.5  290.79  4488.9  293.91    4588  291.47  4628.1  293.12
  4708.4  292.48  4728.4  291.25  4828.8  292.44    4896  291.75  4949.2  289.12
  4979.3   288.5  4988.4  283.93  5005.9  283.93  5011.3  287.15  5025.5  289.13
  5096.2  288.07  5230.6  288.99  5421.4  287.69  5513.4  288.99  5647.7  288.46
  5958.9  289.91  6121.5  296.07  6156.9  298.34  6198.3  303.33  6248.8   310.7
#Mann= 6 ,-1 , 0
  3892.5     .11       0    4369     .15       0  4488.9     .11       0
  4949.2     .06       0  5025.5     .11       0  6198.3     .17       0
Bank Sta=4949.2,5025.5
XS Rating Curve= 0 ,0
Exp/Cntr=0.3,0.1

Type RM Length L Ch R = 1 ,65802   ,491,491,491
BEGIN DESCRIPTION:
WEST SANDY CREEK 110.0
END DESCRIPTION:
XS GIS Cut Line= 3
      3726117.06     10221327.04       3726202.1     10219985.63
      3725562.74      10219210.1
#Sta/Elev= 30
  3655.9  307.09    3742  306.09  3872.3  300.73  3952.5  299.99    4162  294.12
    4233  290.93  4303.2  289.14  4353.3  288.03  4372.9  288.93  4483.5  291.71
  4623.8  290.17  4764.1  286.23  4784.1   287.6  4984.5  287.71    4991  282.57
  5008.5  282.57  5013.5     286  5019.9   287.7  5112.5  286.35  5198.5  287.28
  5254.5  285.39  5311.8  287.53  5659.7  287.98  5688.4  290.77  5737.9  293.22
  5752.3  295.25  5773.1  295.23  5809.4  298.49  5915.1  303.82  6005.1  311.88
#Mann= 5 ,-1 , 0
  3655.9     .11       0    4162     .15       0  4372.9     .11       0
  4984.5     .06       0  5019.9     .11       0
#XS Ineff= 1 ,-1
    4100  4473.5   291.6
Permanent Ineff=
       F
Bank Sta=4984.5,5019.9
XS Rating Curve= 0 ,0
Exp/Cntr=0.3,0.1

Type RM Length L Ch R = 1 ,65311   ,653,653,653
BEGIN DESCRIPTION:
WEST SANDY CREEK 109.0
END DESCRIPTION:
XS GIS Cut Line= 3
      3726823.68     10221342.56      3726456.09     10219904.08
      3726052.82      10219086.2
#Sta/Elev= 30
  3515.3  310.96  3765.4  305.36    3801  305.89  3841.9  304.08  3867.8  304.47
  3961.7  301.37  4168.6  293.62  4209.4  294.09  4451.8  289.51  4559.3  285.54
  4579.9   282.2  4587.4  282.74  4607.5  285.92  4811.7  285.02  4982.5  287.22
  4992.8  285.41  4999.4  279.39  5016.9  279.39    5025  285.57  5030.6  286.86
    5053  287.08  5069.9  285.54  5148.4  286.48  5165.3   283.9  5187.8  286.69
  5636.9  286.69  5687.4   288.7    5822  300.55  5883.9  306.74  5911.9  311.68
#Mann= 7 ,-1 , 0
  3515.3     .11       0  3961.7     .17       0  4451.8     .15       0
  4587.4     .11       0  4982.5     .06       0  5030.6     .11       0
    5822     .17       0
Bank Sta=4982.5,5030.6
XS Rating Curve= 0 ,0
Exp/Cntr=0.3,0.1

Type RM Length L Ch R = 1 ,64658   ,309,309,309
BEGIN DESCRIPTION:
WEST SANDY CREEK 108.0
END DESCRIPTION:
XS GIS Cut Line= 3
      3726967.86     10220847.91      3726850.45     10220240.96
      3726617.85     10219061.07
#Sta/Elev= 30
  4381.8  311.41  4551.7   297.5  4606.3  294.38  4663.8   291.6  4707.1  292.37
  4806.4  291.74  4907.2  285.99  4934.2  283.73  4979.5  284.86    4986  283.26
  4988.5  276.74  5006.2  276.74  5010.1  282.51  5020.3   285.5  5086.8  285.39
  5529.9  286.14  5560.9  285.98  5601.2  283.22  5612.3  284.94  5652.2  286.07
  5658.5  287.63  5709.8  291.88  5766.3  292.98  5812.5  296.64    5907  299.62
  5971.6  299.11  6022.9  300.46  6100.7   305.2  6157.1  306.98  6202.6  308.99
#Mann= 8 ,-1 , 0
  4381.8     .17       0  4606.3     .11       0  4707.1     .17       0
  4907.2     .15       0  4979.5     .09       0  5020.3     .15       0
  5086.8     .11       0  6157.1     .17       0
Bank Sta=4979.5,5020.3
XS Rating Curve= 0 ,0
Exp/Cntr=0.3,0.1

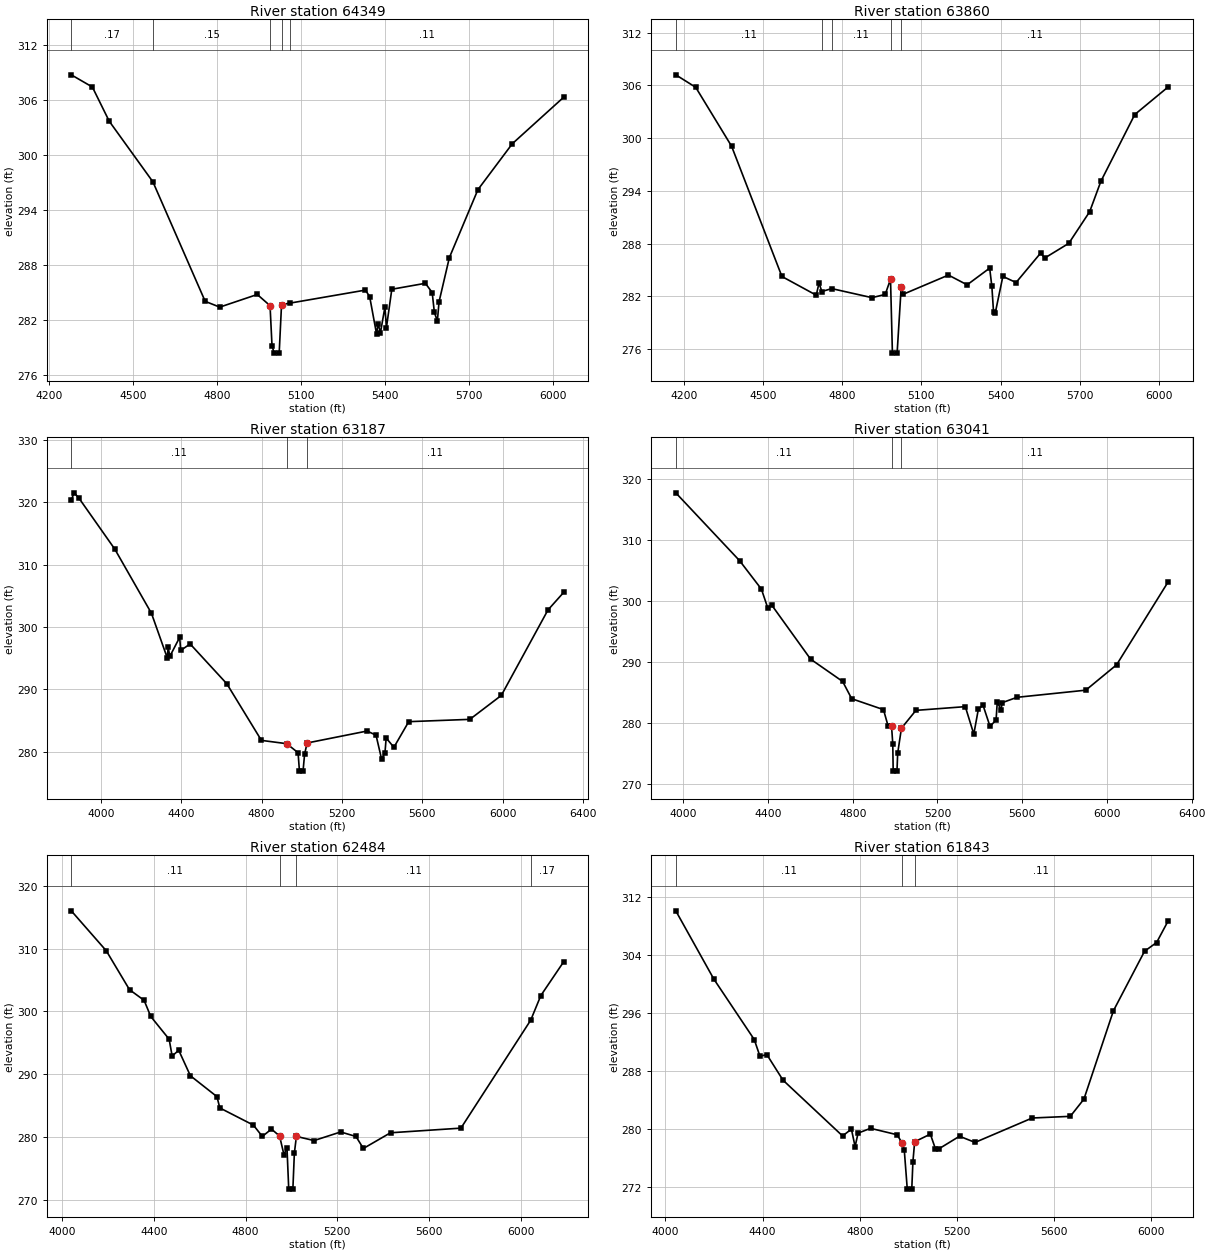
Type RM Length L Ch R = 1 ,64349   ,489,489,489
BEGIN DESCRIPTION:
WEST SANDY CREEK 107.0
END DESCRIPTION:
XS GIS Cut Line= 3
      3727397.53     10220780.11      3727107.12     10220119.31
      3726732.46     10219149.78
#Sta/Elev= 30
  4278.2  308.73  4353.6   307.4  4413.9  303.67  4570.2  297.05  4757.2  284.01
  4809.3  283.38  4943.5  284.76  4989.2  283.54  4996.3  279.13  5004.2  278.36
  5021.9  278.36  5030.3  283.65  5059.1  283.81  5330.5  285.24  5345.6  284.52
  5370.2  280.45  5375.6  281.57  5384.1  280.58  5400.2   283.4  5405.5  281.14
  5424.8  285.33  5544.9  285.98  5569.2  284.97    5577  282.81  5587.7  281.86
  5593.8  283.97  5630.6  288.78  5732.8   296.2  5855.8  301.21  6039.4  306.28
#Mann= 5 ,-1 , 0
  4278.2     .17       0  4570.2     .15       0  4989.2     .09       0
  5030.3     .15       0  5059.1     .11       0
Bank Sta=4989.2,5030.3
XS Rating Curve= 0 ,0
Exp/Cntr=0.3,0.1

Type RM Length L Ch R = 1 ,63860   ,673,673,673
BEGIN DESCRIPTION:
WEST SANDY CREEK 106.0
END DESCRIPTION:
XS GIS Cut Line= 3
      3727549.35     10220731.66      3727477.41     10219904.08
      3726854.76     10219077.57
#Sta/Elev= 30
  4169.3   307.2  4244.8  305.78  4380.7  299.08  4571.4  284.26  4701.6  282.13
  4711.9  283.51  4722.8  282.55  4760.1  282.88  4912.7  281.85  4962.9  282.22
  4982.9  283.95  4990.1  275.54  5007.9  275.54  5023.4  283.06  5029.6  282.22
  5202.4  284.42  5273.2  283.31  5358.6  285.21  5366.9  283.13  5373.2  280.25
  5379.4  280.06  5408.6  284.27  5458.5  283.57  5552.2  286.94  5566.8  286.35
  5658.4  288.03  5737.5  291.63    5780  295.09  5908.3  302.68  6034.8  305.82
#Mann= 5 ,-1 , 0
  4169.3     .11       0  4722.8     .15       0  4760.1     .11       0
  4982.9     .06       0  5023.4     .11       0
Bank Sta=4982.9,5023.4
XS Rating Curve= 0 ,0
Exp/Cntr=0.3,0.1

Type RM Length L Ch R = 1 ,63187   ,146,146,146
BEGIN DESCRIPTION:
WEST SANDY CREEK 105.0
END DESCRIPTION:
XS GIS Cut Line= 3
      3729151.63     10219891.69      3728140.52     10219730.17
      3726871.94     10219081.35
#Sta/Elev= 30
  3853.7  320.35  3867.7  321.51  3891.1  320.69  4070.2  312.48  4252.5  302.19
  4330.7  295.08  4335.8  296.74  4343.6  295.27  4392.8  298.34  4397.9  296.24
  4444.9  297.28  4627.2   290.9  4799.3  281.82  4925.2  281.29  4981.7  279.84
  4988.5  276.89  5006.4  276.89  5014.1   279.6  5026.6   281.4  5325.1  283.32
  5369.5  282.65  5397.3  278.79  5413.9  279.83  5419.8   282.2  5458.3  280.71
  5532.1  284.82    5836  285.19  5992.6  289.03  6224.6  302.73  6302.5  305.54
#Mann= 3 , 0 , 0
  3853.7     .11       0  4925.2     .06       0  5026.6     .11       0
Bank Sta=4925.2,5026.6
XS Rating Curve= 0 ,0
Exp/Cntr=0.3,0.1

Type RM Length L Ch R = 1 ,63041   ,557,557,557
BEGIN DESCRIPTION:
WEST SANDY CREEK 104.0
END DESCRIPTION:
XS GIS Cut Line= 3
      3729148.47     10219726.94      3728192.21     10219597.72
      3726948.51     10219048.55
#Sta/Elev= 30
  3964.4  317.73  4266.1  306.59  4368.7  301.94  4398.9  298.83  4416.5  299.37
  4600.8  290.47  4752.1  286.81  4794.9  283.98    4945  282.19  4966.9  279.49
  4983.1  279.47  4988.8  276.62  4990.8  272.11  5008.7  272.11  5011.9     275
  5029.7  279.14  5098.1  282.07  5331.3  282.68  5371.4  278.18  5393.2  282.32
  5415.1   282.9  5447.9  279.45  5476.6  280.49  5482.1  283.41    5500  282.19
  5505.4  283.33  5575.4  284.21  5900.2  285.38  6045.6  289.54  6288.9  303.13
#Mann= 3 , 0 , 0
  3964.4     .11       0  4983.1     .06       0  5029.7     .11       0
Bank Sta=4983.1,5029.7
XS Rating Curve= 0 ,0
Exp/Cntr=0.3,0.1

Type RM Length L Ch R = 1 ,62484   ,641,641,641
BEGIN DESCRIPTION:
WEST SANDY CREEK 103.0
END DESCRIPTION:
XS GIS Cut Line= 3
      3729167.79     10219623.54      3728544.33     10219187.45
      3727255.39      10218683.5
#Sta/Elev= 30
  4040.9  316.01  4193.4  309.64  4294.6  303.44  4358.1  301.75    4387  299.18
  4467.2  295.55  4480.2  292.88  4509.1  293.78  4559.7  289.73  4675.4   286.4
  4687.9   284.6  4834.3  281.86  4873.1  280.06    4913  281.23  4948.3  280.12
  4967.3  277.15  4980.5  278.26  4988.2  271.66  5006.2  271.66  5012.7   277.4
  5021.6  280.06  5098.6   279.4  5214.4  280.77  5281.1  280.05  5313.3  278.14
  5431.5  280.64  5738.3  281.38  6042.4  298.59  6086.4  302.51  6185.7  307.88
#Mann= 4 ,-1 , 0
  4040.9     .11       0  4948.3     .06       0  5021.6     .11       0
  6042.4     .17       0
Bank Sta=4948.3,5021.6
XS Rating Curve= 0 ,0
Exp/Cntr=0.3,0.1

Type RM Length L Ch R = 1 ,61843   ,437,437,437
BEGIN DESCRIPTION:
WEST SANDY CREEK 102.0
END DESCRIPTION:
XS GIS Cut Line= 3
      3729164.17     10219452.73      3728619.89     10218603.75
      3727982.34     10217810.08
#Sta/Elev= 30
  4042.8  310.08  4199.3  300.69  4365.8  292.36  4389.3  290.05  4417.4   290.3
  4484.1  286.77  4729.3  279.09  4765.6  280.03  4780.8  277.63  4793.1  279.48
  4844.3  280.14  4953.3  279.26  4974.5  278.14  4983.2  277.18  4995.6  271.77
  5014.1  271.77  5018.8  275.54    5026  278.29  5090.6  279.34  5111.4  277.33
  5125.8  277.32  5210.6  279.05  5274.6   278.2  5509.8  281.56  5666.6  281.79
  5722.7  284.16  5844.2  296.33  5972.3  304.52  6021.9  305.72  6069.3  308.69
#Mann= 3 , 0 , 0
  4042.8     .11       0  4974.5     .06       0    5026     .11       0
Bank Sta=4974.5,5026
XS Rating Curve= 0 ,0
Exp/Cntr=0.3,0.1

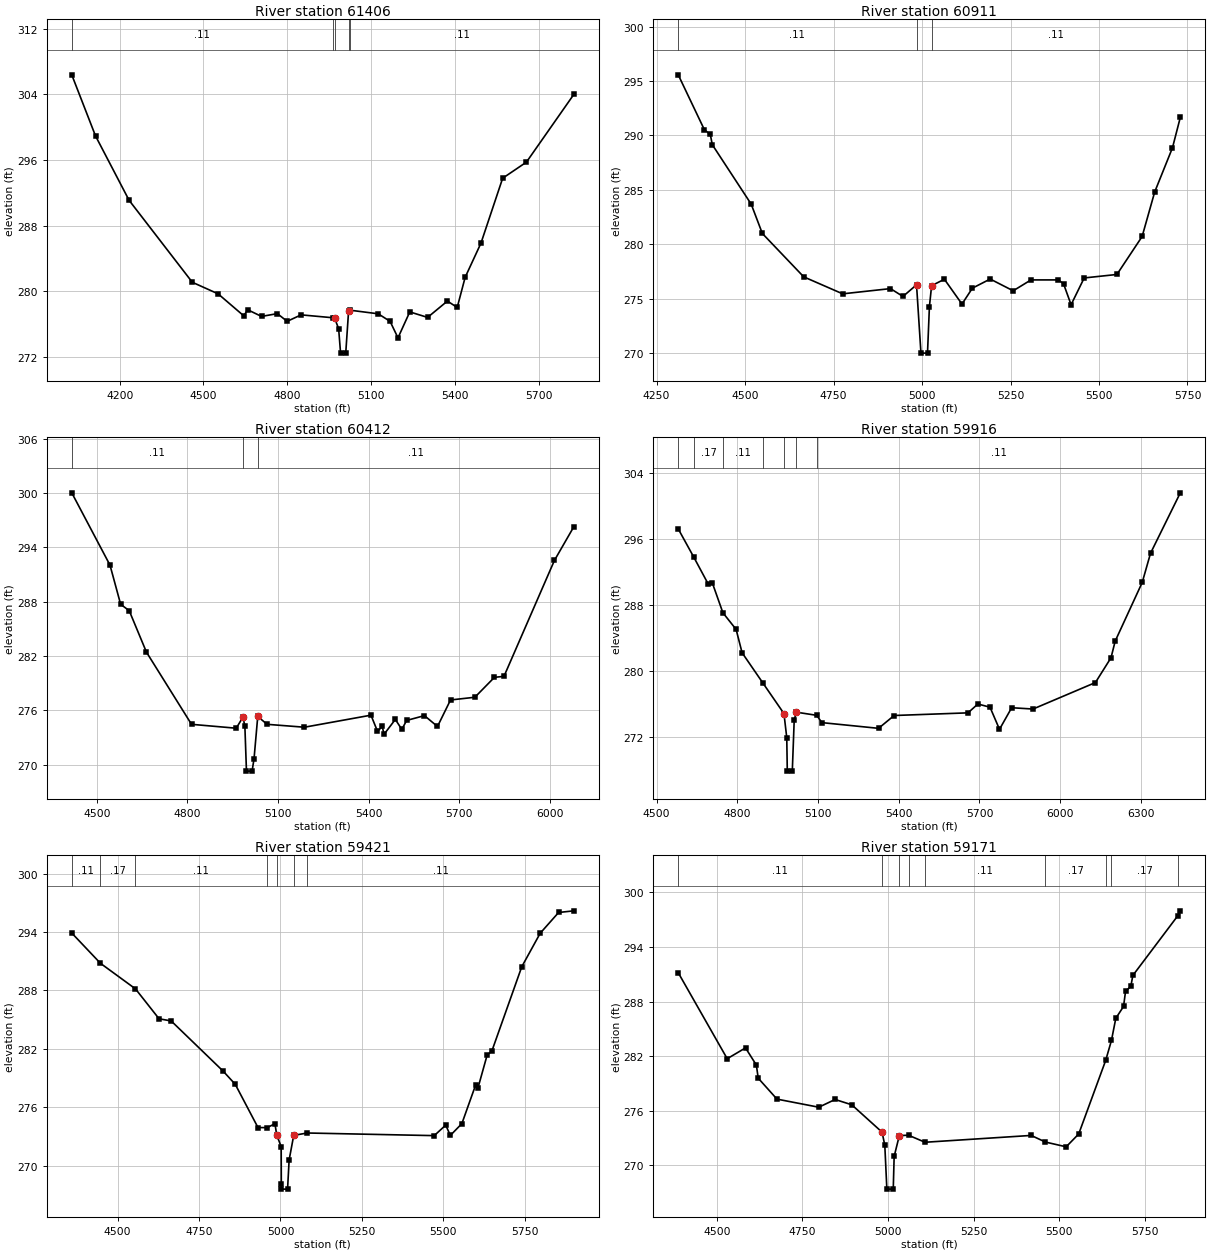
Type RM Length L Ch R = 1 ,61406   ,495,495,495
BEGIN DESCRIPTION:
WEST SANDY CREEK 101.0
END DESCRIPTION:
XS GIS Cut Line= 3
       3729583.4      10219085.5      3728922.37     10218373.56
      3728317.88      10217811.1
#Sta/Elev= 30
  4028.5  306.38  4113.5  298.94  4233.7   291.1  4459.9  281.12  4552.3  279.71
  4644.2  277.03  4658.3  277.77  4707.7  276.96  4764.4   277.3  4799.5  276.36
  4849.4  277.15  4962.5   276.8  4969.6  276.73  4983.8  275.46  4990.7  272.49
  5009.2  272.49  5019.3  277.58  5026.2  277.71  5125.4  277.28  5167.9  276.36
  5196.2  274.35  5238.4  277.51  5302.2  276.84  5373.1  278.83  5408.2  278.05
  5436.6  281.72  5493.3  285.89  5570.9  293.79    5656  295.75  5825.7     304
#Mann= 5 ,-1 , 0
  4028.5     .11       0  4962.5     .09       0  4969.6     .06       0
  5019.3     .09       0  5026.2     .11       0
Bank Sta=4969.6,5019.3
XS Rating Curve= 0 ,0
Exp/Cntr=0.3,0.1

Type RM Length L Ch R = 1 ,60911   ,499,499,499
BEGIN DESCRIPTION:
WEST SANDY CREEK 100.0
END DESCRIPTION:
XS GIS Cut Line= 3
      3729917.87     10218411.08      3729309.09     10218088.86
      3728717.83     10217661.05
#Sta/Elev= 30
  4311.2  295.56  4385.4  290.49  4401.7   290.1  4407.4  289.14  4517.4  283.67
  4548.8  280.98  4665.8  276.99  4775.8  275.43  4910.9  275.91  4946.2  275.19
  4984.5  276.26    4997  269.98  5015.5  269.98  5020.9  274.26  5027.1  276.18
  5063.2  276.77  5112.9  274.49  5142.3  275.95  5192.6  276.79  5257.6  275.71
  5307.9  276.71  5385.2  276.71  5399.9  276.35  5421.2  274.43  5458.2  276.89
  5550.7  277.21  5621.9   280.7  5657.4  284.79  5707.7  288.86  5729.8  291.65
#Mann= 3 , 0 , 0
  4311.2     .11       0  4984.5     .06       0  5027.1     .11       0
Bank Sta=4984.5,5027.1
XS Rating Curve= 0 ,0
Exp/Cntr=0.3,0.1

Type RM Length L Ch R = 1 ,60412   ,496,496,496
BEGIN DESCRIPTION:
WEST SANDY CREEK 99.0
END DESCRIPTION:
XS GIS Cut Line= 3
      3730200.03      10218267.7      3729756.38     10217888.69
       3728817.9     10217353.63
#Sta/Elev= 30
  4416.5  300.01  4543.2  292.02  4578.4   287.7  4606.9  286.99    4664  282.41
  4813.3  274.44  4961.5  274.01  4983.5  275.22  4990.1  274.27  4995.4  269.27
    5014  269.27  5020.5  270.63  5032.8  275.31  5063.7  274.44  5187.6  274.12
    5408  275.45  5429.6  273.67  5445.5   274.2  5451.2  273.33  5488.7  274.98
  5510.3  273.88  5526.2  274.87  5585.2   275.4  5628.4   274.2  5671.6  277.13
  5752.3  277.43  5817.1  279.63  5848.8  279.74  6015.9  292.54  6080.3  296.27
#Mann= 3 , 0 , 0
  4416.5     .11       0  4983.5     .06       0  5032.8     .11       0
Bank Sta=4983.5,5032.8
XS Rating Curve= 0 ,0
Exp/Cntr=0.3,0.1

Type RM Length L Ch R = 1 ,59916   ,495,495,495
BEGIN DESCRIPTION:
WEST SANDY CREEK 98.0
END DESCRIPTION:
XS GIS Cut Line= 3
      3730369.88     10218080.29      3730177.65     10217707.43
      3728945.37     10216950.09
#Sta/Elev= 30
  4580.5  297.19  4638.8  293.75  4692.1  290.52    4707  290.69  4746.5  287.06
  4795.6  285.05  4817.8  282.23  4894.6   278.6  4973.4  274.88  4983.8  271.98
  4985.8  267.93  5004.4  267.93  5011.5   274.1  5019.5  275.05  5095.3  274.67
  5114.2  273.79  5324.9   273.1  5382.9  274.65  5657.4  274.97  5694.1  276.04
  5739.2  275.65  5774.4  272.98  5819.7  275.59    5899  275.43  6130.9  278.63
  6188.9  281.63  6204.3  283.63  6304.9  290.73  6335.7  294.25  6446.4  301.55
#Mann= 7 ,-1 , 0
  4580.5     .11       0  4638.8     .17       0  4746.5     .11       0
  4894.6     .17       0  4973.4     .09       0  5019.5     .17       0
  5095.3     .11       0
Bank Sta=4973.4,5019.5
XS Rating Curve= 0 ,0
Exp/Cntr=0.3,0.1

Type RM Length L Ch R = 1 ,59421   ,250,250,250
BEGIN DESCRIPTION:
WEST SANDY CREEK 97.0
END DESCRIPTION:
XS GIS Cut Line= 3
      3730726.65     10217905.83      3730465.89     10217320.59
      3729833.44     10216679.29
#Sta/Elev= 30
  4359.3  293.89  4447.5  290.78  4554.9  288.16  4627.3  285.09  4664.5  284.87
  4824.3  279.71  4861.3  278.36    4931  273.93  4959.7  273.92    4983  274.33
  4988.5  273.17  5002.2  271.96  5002.6  268.11  5003.1  267.61  5021.8  267.61
  5026.6   270.6  5040.7  273.13  5082.5  273.37  5472.1   273.1  5507.4  274.18
  5521.5  273.12  5556.9  274.33  5599.3  278.31  5606.4     278  5634.7  281.39
  5648.8  281.76  5740.8  290.43  5797.4  293.87  5853.9     296  5900.7  296.17
#Mann= 7 ,-1 , 0
  4359.3     .11       0  4447.5     .17       0  4554.9     .11       0
  4959.7     .15       0  4988.5     .09       0  5040.7     .15       0
  5082.5     .11       0
Bank Sta=4988.5,5040.7
XS Rating Curve= 0 ,0
Exp/Cntr=0.3,0.1

Type RM Length L Ch R = 1 ,59171   ,750,750,750
BEGIN DESCRIPTION:
WEST SANDY CREEK 96.0
END DESCRIPTION:
XS GIS Cut Line= 3
      3730895.93      10217754.8      3730695.41     10217228.75
      3730217.83     10216461.04
#Sta/Elev= 30
  4386.9  291.17    4530  281.72  4583.5  282.91  4615.2  281.02  4620.6  279.58
  4675.4  277.28  4797.6  276.39  4845.2  277.24  4893.9  276.66  4982.5  273.65
  4990.5  272.21  4996.5  267.39  5015.2  267.39  5017.8  270.98    5033  273.28
  5059.9  273.31  5108.1  272.54  5418.2  273.29    5460  272.56  5520.5  272.04
  5557.1  273.45    5636  281.54  5652.8  283.73  5665.5  286.16  5688.1  287.46
    5694  289.13  5709.4  289.67  5715.3  290.87  5845.9  297.39    5854  297.97
#Mann= 9 ,-1 , 0
  4386.9     .11       0  4982.5     .07       0    5033     .11       0
  5059.9     .15       0  5108.1     .11       0    5460     .17       0
    5636     .11       0  5652.8     .17       0  5845.9     .11       0
Bank Sta=4982.5,5033
XS Rating Curve= 0 ,0
Exp/Cntr=0.3,0.1

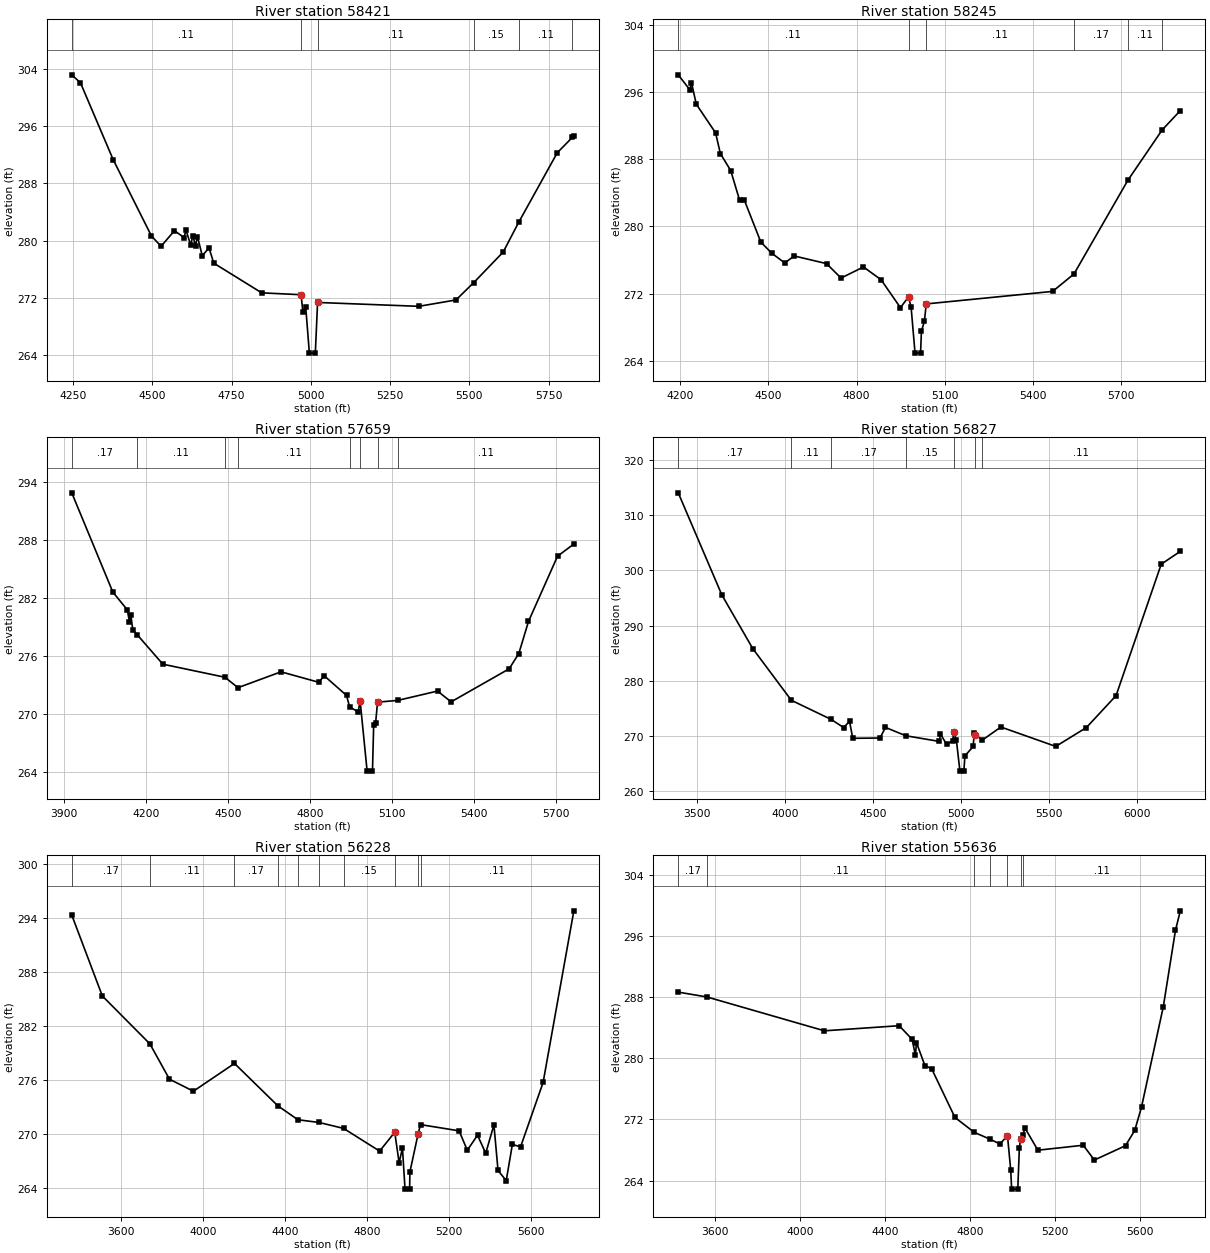
Type RM Length L Ch R = 1 ,58421   ,176,176,176
BEGIN DESCRIPTION:
WEST SANDY CREEK 95.0
END DESCRIPTION:
XS GIS Cut Line= 3
      3731526.13     10217301.65      3731117.96     10216667.57
       3730338.6     10216382.39
#Sta/Elev= 30
  4245.9  303.15  4273.4  302.03  4376.4  291.33  4497.2  280.67  4527.6  279.22
  4569.8   281.4  4600.2  280.45  4606.2  281.49  4621.3  279.37  4627.3  280.71
  4636.5  279.33  4642.5  280.59  4657.6   277.9  4678.8  279.01    4694  276.87
  4845.2  272.73  4969.3  272.47  4975.2  270.03  4983.9  270.79  4995.5  264.32
  5014.3  264.32  5021.4  271.39  5340.9  270.85    5458  271.74  5514.1  274.16
  5607.1  278.43  5655.6  282.55  5777.5  292.27  5825.1  294.42  5829.9  294.63
#Mann= 6 ,-1 , 0
  4245.9     .11       0  4969.3     .06       0  5021.4     .11       0
  5514.1     .15       0  5655.6     .11       0  5825.1     .17       0
Bank Sta=4969.3,5021.4
XS Rating Curve= 0 ,0
Exp/Cntr=0.3,0.1

Type RM Length L Ch R = 1 ,58245   ,586,586,586
BEGIN DESCRIPTION:
WEST SANDY CREEK 94.0
END DESCRIPTION:
XS GIS Cut Line= 3
      3731612.86     10217248.32       3731196.2     10216474.91
      3730383.71     10216310.85
#Sta/Elev= 30
  4193.6  298.06    4233  296.28  4238.7  297.13  4254.9  294.57  4320.6  291.15
  4336.8  288.69  4372.2  286.65  4402.5   283.1  4417.7   283.2  4474.4  278.15
    4512  276.81  4555.8  275.66    4588  276.49  4697.8  275.58  4747.3  273.86
  4823.5  275.18  4883.4  273.66  4949.3  270.33  4976.8  271.63  4985.6  270.36
  4998.9  264.92  5017.7  264.92  5020.6  267.51    5031  268.76  5036.9  270.78
  5466.8  272.27  5539.5  274.35  5722.4  285.49  5839.3   291.5    5901   293.8
#Mann= 6 ,-1 , 0
  4193.6     .11       0  4976.8     .06       0  5036.9     .11       0
  5539.5     .17       0  5722.4     .11       0  5839.3     .17       0
Bank Sta=4976.8,5036.9
XS Rating Curve= 0 ,0
Exp/Cntr=0.3,0.1

Type RM Length L Ch R = 1 ,57659   ,832,832,832
BEGIN DESCRIPTION:
WEST SANDY CREEK 93.0
END DESCRIPTION:
XS GIS Cut Line= 3
      3731767.84     10217211.03      3731612.87     10216276.99
      3730987.86     10215646.77
#Sta/Elev= 30
  3929.6  292.92  4079.4  282.66  4132.3  280.81  4140.4  279.59  4145.4  280.26
  4152.6  278.73    4169  278.22  4262.3  275.18  4488.9  273.83    4537  272.75
  4694.1  274.39  4831.7  273.31    4852  273.98  4933.6  271.94  4944.6  270.76
  4976.1  270.24  4983.2  271.37  5008.7  264.11  5028.3  264.11  5032.6  268.87
  5039.7  269.09  5046.8  271.25  5120.5  271.43    5266   272.4  5315.5  271.28
  5527.6   274.7  5562.9  276.28  5598.3  279.61  5704.4  286.36    5764  287.62
#Mann= 8 ,-1 , 0
  3929.6     .17       0    4169     .11       0  4488.9     .15       0
    4537     .11       0  4944.6     .15       0  4983.2     .09       0
  5046.8     .15       0  5120.5     .11       0
Bank Sta=4983.2,5046.8
XS Rating Curve= 0 ,0
Exp/Cntr=0.3,0.1

Type RM Length L Ch R = 1 ,56827   ,599,599,599
BEGIN DESCRIPTION:
WEST SANDY CREEK 92.0
END DESCRIPTION:
XS GIS Cut Line= 3
      3731817.86     10217561.05      3732223.05      10216006.9
      3732717.85     10214861.08
#Sta/Elev= 30
  3393.9  314.03  3641.9  295.55  3817.6  285.85  4036.7   276.5  4262.8  273.04
  4334.3  271.56  4367.7   272.7    4386  269.62    4541  269.67    4572  271.59
  4687.6  270.08  4878.6  269.05  4883.8  270.43  4919.1  268.54  4954.4  269.18
  4959.6  270.71    4975  269.33  4995.2  263.68  5017.5  263.68  5023.7  266.44
  5070.7  268.14  5076.2  270.54  5082.6  270.27  5123.2  269.31  5228.1  271.66
  5540.1  268.15  5714.4  271.57  5882.8  277.34  6139.6  301.12  6248.1  303.44
#Mann= 7 ,-1 , 0
  3393.9     .17       0  4036.7     .11       0  4262.8     .17       0
  4687.6     .15       0  4959.6     .09       0  5082.6     .15       0
  5123.2     .11       0
Bank Sta=4959.6,5082.6
XS Rating Curve= 0 ,0
Exp/Cntr=0.3,0.1

Type RM Length L Ch R = 1 ,56228   ,592,592,592
BEGIN DESCRIPTION:
WEST SANDY CREEK 91.0
END DESCRIPTION:
XS GIS Cut Line= 3
      3732167.86     10217361.05      3732731.95     10215820.69
      3732717.85     10215011.11
#Sta/Elev= 30
  3359.6  294.29  3508.7  285.31  3740.9  279.99  3836.4  276.07  3953.2  274.74
  4153.6  277.82  4365.1  273.12  4463.2  271.57  4566.4  271.27    4686  270.61
  4861.9  268.09  4935.7  270.18    4957   266.8  4973.3  268.42  4985.9  263.87
  5008.3  263.87  5009.6  265.77  5049.6  269.99  5061.6  271.03  5249.7  270.34
  5289.7  268.19  5339.7  269.85  5379.7  267.85  5419.7  271.01  5439.7  265.94
  5479.7  264.81  5509.7  268.83  5549.7  268.56  5659.7  275.71  5809.7  294.76
#Mann= 10 ,-1 , 0
  3359.6     .17       0  3740.9     .11       0  4153.6     .17       0
  4365.1     .15       0  4463.2     .17       0  4566.4     .11       0
    4686     .15       0  4935.7     .09       0  5049.6     .15       0
  5061.6     .11       0
Bank Sta=4935.7,5049.6
XS Rating Curve= 0 ,0
Exp/Cntr=0.3,0.1

Type RM Length L Ch R = 1 ,55636   ,476,476,476
BEGIN DESCRIPTION:
WEST SANDY CREEK 90.0
END DESCRIPTION:
XS GIS Cut Line= 3
      3733417.85     10217161.04      3733199.72     10215603.74
      3732817.83     10214911.04
#Sta/Elev= 30
  3427.5  288.68  3563.5  288.04  4115.7  283.61  4467.5  284.28  4528.1  282.51
  4544.1  280.43  4549.1  282.05  4588.7  279.06  4620.5  278.64  4730.1  272.26
  4820.5  270.32  4894.9  269.41  4942.1  268.79  4977.4  269.87  4992.6  265.39
    4997  262.87  5025.9  262.87  5033.3  268.24    5039  269.48  5048.7  269.98
  5060.8  270.82  5120.4  267.97  5334.2  268.62  5386.3  266.68    5533  268.56
  5576.6  270.57  5608.3  273.62    5711  286.78  5768.1  296.76    5791  299.33
#Mann= 7 ,-1 , 0
  3427.5     .17       0  3563.5     .11       0  4820.5     .15       0
  4894.9     .11       0  4977.4     .06       0    5039     .09       0
  5048.7     .11       0
Bank Sta=4977.4,5039
XS Rating Curve= 0 ,0
Exp/Cntr=0.3,0.1

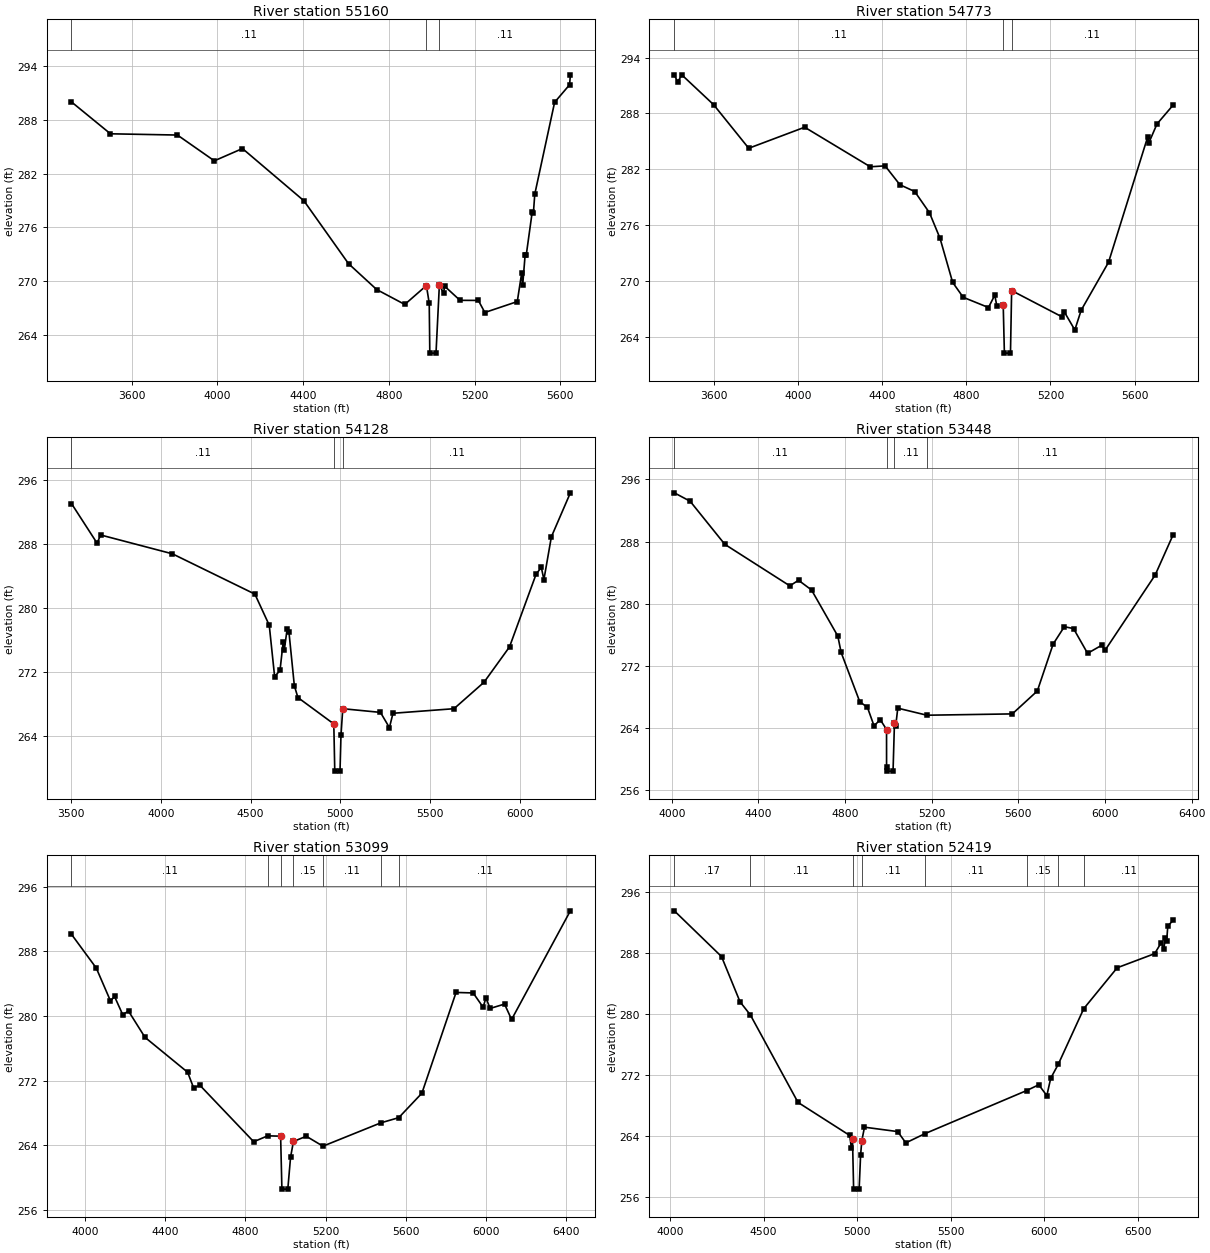
Type RM Length L Ch R = 1 ,55160   ,387,387,387
BEGIN DESCRIPTION:
WEST SANDY CREEK 89.0
END DESCRIPTION:
XS GIS Cut Line= 3
      3733881.21     10217181.19      3733591.15     10215083.92
      3733542.76      10214879.5
#Sta/Elev= 30
  3319.7  290.01  3501.5  286.45    3814  286.31  3986.1  283.43  4117.3   284.8
  4403.8  278.97    4612  271.94  4743.2  269.05  4874.5  267.38  4975.4  269.49
  4988.6  267.51  4991.3  261.94  5020.2  261.94    5036   269.6  5055.3  268.62
  5060.4  269.42  5132.2  267.84  5217.7  267.83    5248  266.48  5399.4   267.7
  5419.5  270.84  5424.6  269.56  5435.8  272.87    5441  272.87  5469.2  277.75
  5474.4  277.56    5481  279.71  5573.5  289.97  5643.4  291.93    5647  293.04
#Mann= 3 , 0 , 0
  3319.7     .11       0  4975.4     .06       0    5036     .11       0
Bank Sta=4975.4,5036
XS Rating Curve= 0 ,0
Exp/Cntr=0.3,0.1

Type RM Length L Ch R = 1 ,54773   ,645,645,645
BEGIN DESCRIPTION:
WEST SANDY CREEK 88.0
END DESCRIPTION:
XS GIS Cut Line= 3
      3734110.37     10217196.79      3733990.59     10216071.84
      3734037.39     10214834.14
#Sta/Elev= 30
  3413.3  292.15  3429.1  291.38  3449.2  292.14  3600.1  288.94  3766.8  284.26
  4032.5  286.52  4344.3  282.27  4414.6  282.37    4485  280.34  4555.4  279.61
  4625.4  277.33  4675.5  274.59  4735.5  269.85  4785.6  268.25  4905.6  267.15
  4935.7  268.48  4945.7  267.28  4975.7  267.43  4981.3  262.25  5010.2  262.25
  5015.7  268.97  5255.9  266.14  5265.9  266.68  5315.9  264.74    5346  266.86
    5476  272.01  5662.1  285.48  5667.1  284.82  5706.2  286.87  5783.2  288.91
#Mann= 3 , 0 , 0
  3413.3     .11       0  4975.7     .06       0  5015.7     .11       0
Bank Sta=4975.7,5015.7
XS Rating Curve= 0 ,0
Exp/Cntr=0.3,0.1

Type RM Length L Ch R = 1 ,54128   ,680,680,680
BEGIN DESCRIPTION:
WEST SANDY CREEK 87.0
END DESCRIPTION:
XS GIS Cut Line= 4
        3734626.     10217243.72      3734622.92     10216060.89
      3734599.96     10214957.25       3734215.4     10214645.44
#Sta/Elev= 30
  3501.2  293.04  3643.8   288.1  3663.8  289.12  4063.8  286.77  4523.9  281.74
  4603.9  277.86  4633.9  271.45  4663.9  272.21  4681.4  275.71    4688  274.79
  4703.9  277.42  4713.9  276.99  4743.9   270.3  4763.9  268.83  4963.9  265.54
  4969.3  259.65  4998.5  259.65  5003.9  264.12  5013.9  267.44    5224  266.98
    5274  265.08    5294  266.87  5634.1  267.44  5801.4  270.74  5943.6  275.15
  6092.3  284.25  6121.1  285.07  6135.4  283.55  6177.1  288.89    6283  294.38
#Mann= 3 , 0 , 0
  3501.2     .11       0  4963.9     .06       0  5013.9     .11       0
#XS Ineff= 1 ,-1
    4550  4703.9  277.42
Permanent Ineff=
       F
Bank Sta=4963.9,5013.9
XS Rating Curve= 0 ,0
Exp/Cntr=0.3,0.1

Type RM Length L Ch R = 1 ,53448   ,349,349,349
BEGIN DESCRIPTION:
WEST SANDY CREEK 86.0
END DESCRIPTION:
XS GIS Cut Line= 3
      3735370.79     10216623.93      3735396.84     10215915.59
      3734547.87     10214566.62
#Sta/Elev= 30
  4012.1  294.27    4085  293.19  4245.1  287.64  4545.3  282.29  4585.3  283.01
  4645.4  281.76  4766.8  275.82  4782.1  273.71    4868  267.37  4903.5  266.64
    4934  264.26  4962.6  265.06  4991.7  263.79  4991.8  258.93  4992.3  258.43
  5021.7  258.43  5028.2   264.6  5034.1  264.27  5043.5  266.54  5177.8  265.63
  5572.2   265.8  5687.6  268.75  5760.6  274.79  5812.3  277.03  5854.7  276.79
  5919.6   273.6  5985.4  274.65  6000.7  274.01  6231.5  283.68  6314.8  288.89
#Mann= 4 ,-1 , 0
  4012.1     .11       0  4991.7     .09       0  5028.2     .11       0
  5177.8     .11       0
Bank Sta=4991.7,5028.2
XS Rating Curve= 0 ,0
Exp/Cntr=0.3,0.1

Type RM Length L Ch R = 1 ,53099   ,680,680,680
BEGIN DESCRIPTION:
WEST SANDY CREEK 85.0
END DESCRIPTION:
XS GIS Cut Line= 3
        3735876.     10216483.29      3735771.84     10215795.79
      3734636.41     10214410.37
#Sta/Elev= 30
  3933.3  290.12  4056.9  285.94  4127.7  281.87  4147.9  282.42  4188.4  280.18
  4217.5  280.61  4299.7  277.36  4512.1  273.04  4542.4  271.08  4572.7  271.44
  4841.5  264.43  4911.1  265.16  4975.7  265.12  4982.1  258.56  5011.5  258.56
  5025.3  262.52  5039.6  264.46  5103.5  265.11  5186.7  263.88  5475.2  266.77
  5564.4  267.41  5679.8  270.44  5850.1  282.92  5935.3  282.86  5984.8   281.1
  5999.2  282.24    6020  280.94  6091.8  281.48  6126.9  279.57  6419.9  293.03
#Mann= 7 ,-1 , 0
  3933.3     .11       0  4911.1     .15       0  4975.7     .09       0
  5039.6     .15       0  5186.7     .11       0  5475.2     .15       0
  5564.4     .11       0
Bank Sta=4975.7,5039.6
XS Rating Curve= 0 ,0
Exp/Cntr=0.3,0.1

Type RM Length L Ch R = 1 ,52419   ,470,470,470
BEGIN DESCRIPTION:
WEST SANDY CREEK 84.0
END DESCRIPTION:
XS GIS Cut Line= 3
      3736704.14      10216160.4      3736527.04     10215774.96
      3734773.71     10214375.41
#Sta/Elev= 30
  4022.7  293.52  4275.1  287.52  4374.1  281.58  4429.3  279.86  4684.1  268.38
    4961  264.04  4969.1  262.41  4975.5  263.59  4981.5     257    5011     257
  5018.7  261.42  5025.1  263.32  5039.5  265.13  5217.2  264.55  5260.5  263.07
  5362.9  264.28  5906.1  269.93  5971.4  270.69  6014.6  269.27  6035.4  271.55
  6075.7  273.38    6212  280.68  6390.9  286.05  6591.1   287.9  6626.3  289.34
  6640.7  288.51  6647.1  289.96  6655.1   289.5  6661.5  291.53  6690.3  292.28
#Mann= 8 ,-1 , 0
  4022.7     .17       0  4429.3     .11       0  4975.5     .06       0
  5025.1     .11       0  5362.9     .11       0  5906.1     .15       0
  6075.7     .17       0    6212     .11       0
Bank Sta=4975.5,5025.1
XS Rating Curve= 0 ,0
Exp/Cntr=0.3,0.1