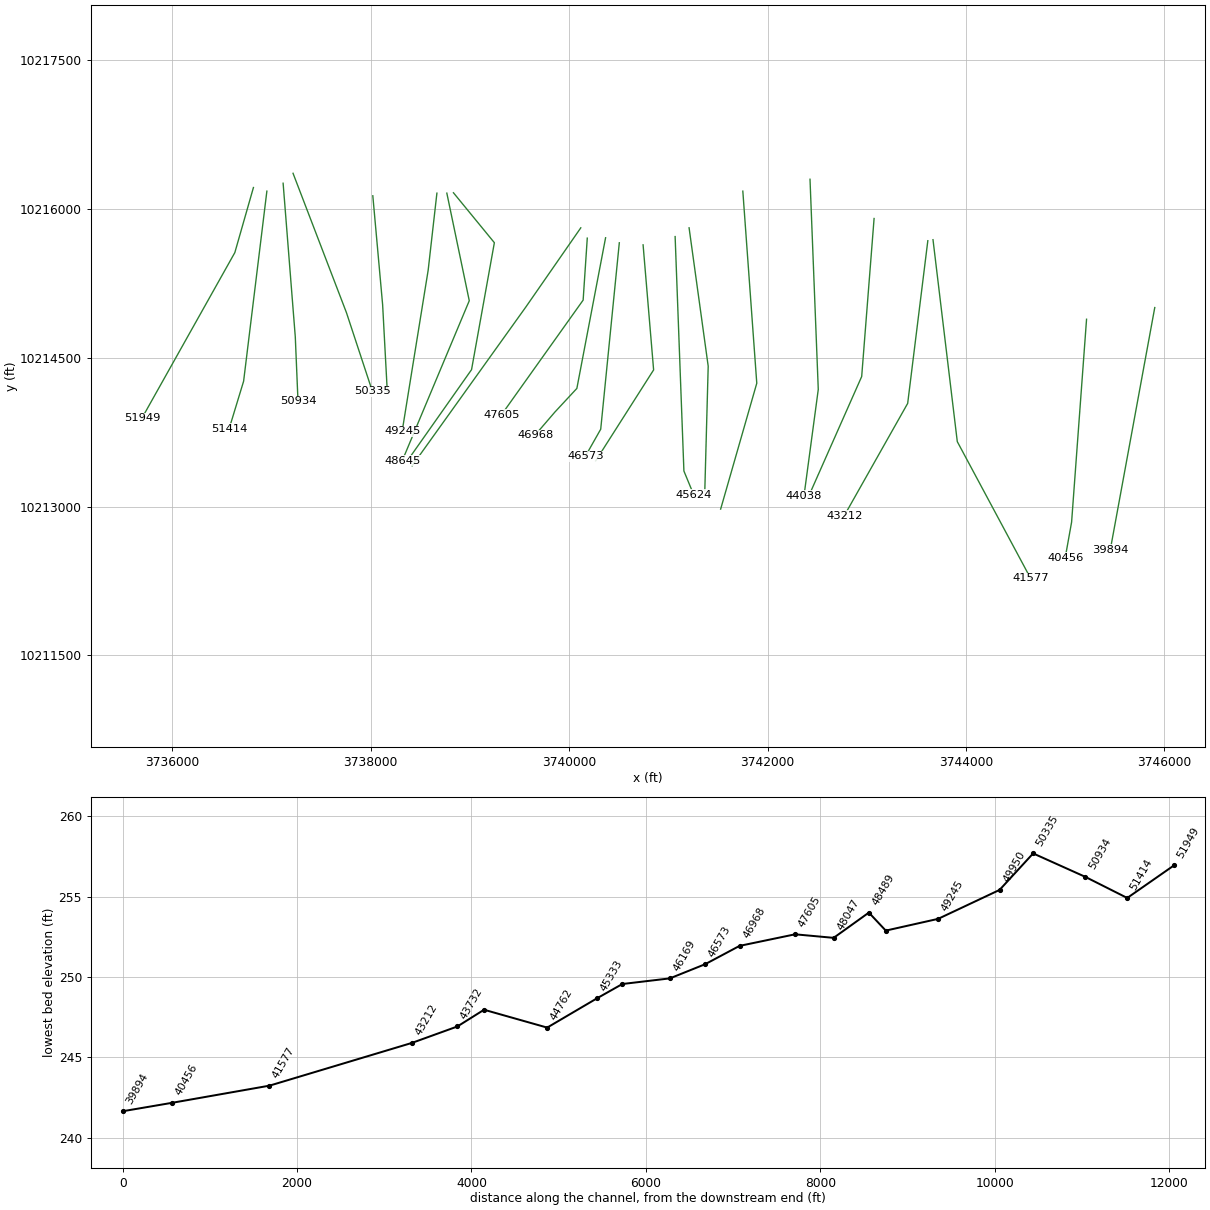
HEC-RAS study WEST SANDY CREEK.prj: WEST SANDY CREEK Base Level Engineering

--- WEST SANDY CREEK.g01 (geometry) --- (continued)

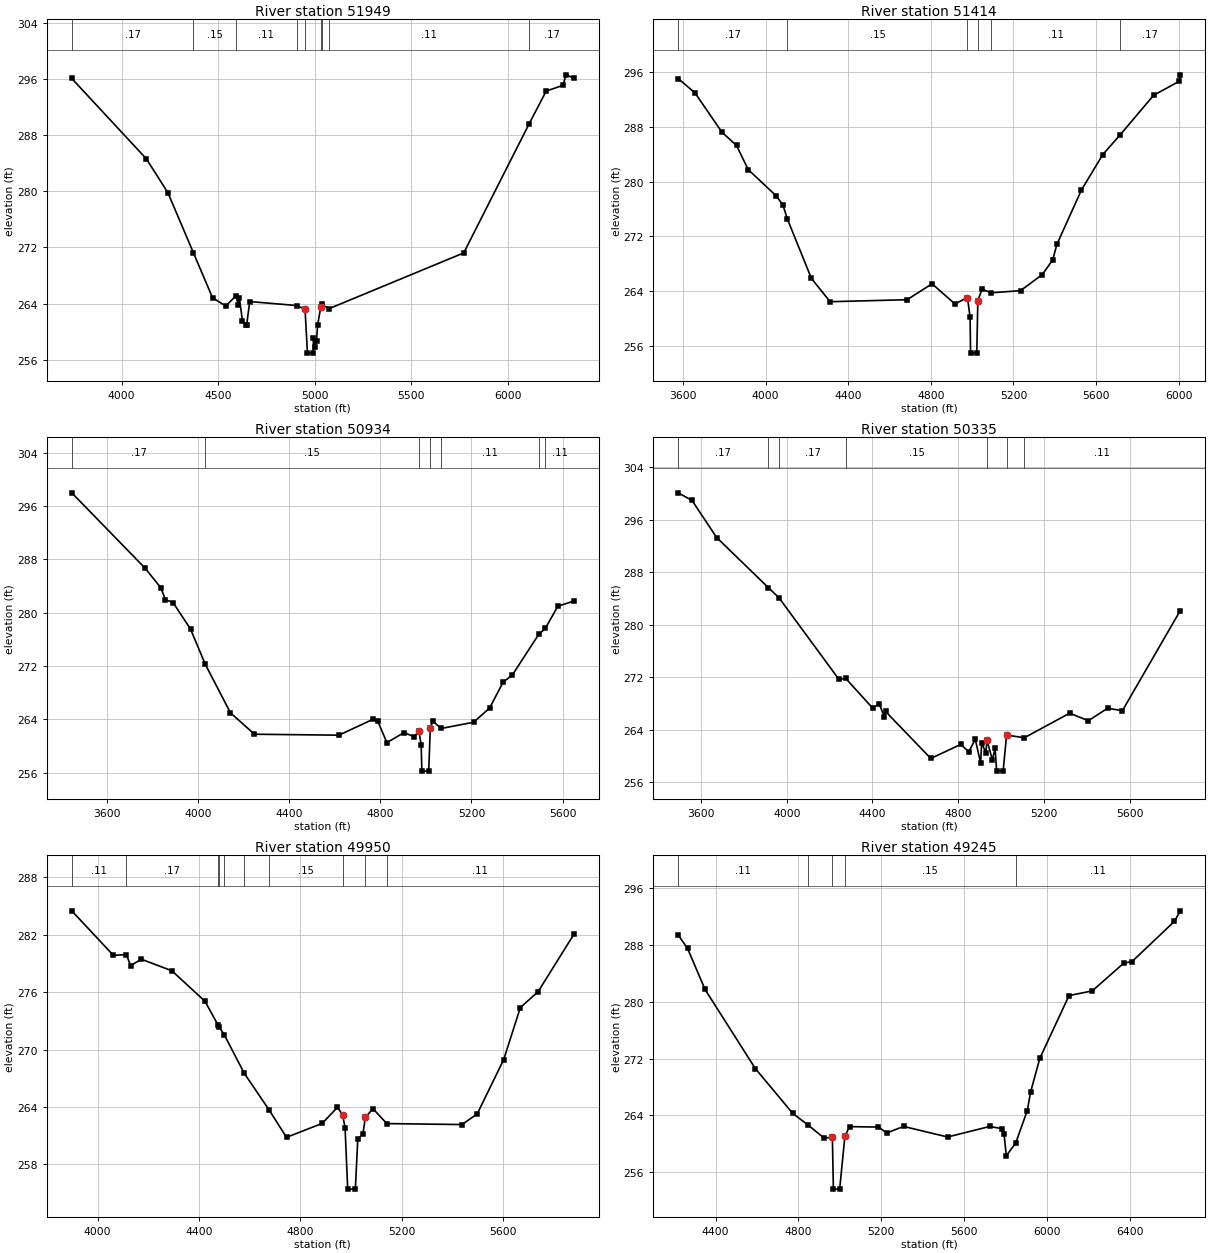
Type RM Length L Ch R = 1 ,51949   ,535,535,535
BEGIN DESCRIPTION:
WEST SANDY CREEK 83.0
END DESCRIPTION:
XS GIS Cut Line= 3
      3736818.71     10216217.67      3736631.21     10215561.42
      3735693.71     10213889.55
#Sta/Elev= 30
  3741.6  296.09  4127.5  284.64  4239.3   279.8  4371.8  271.21  4470.4  264.83
  4538.4  263.65  4592.8  265.13  4603.5  263.78  4609.2  264.77  4625.2  261.58
  4641.1  260.92  4646.9  260.93  4662.8  264.28  4905.9  263.72  4949.3  263.18
  4961.7  256.93  4991.7  256.93  4992.6  259.02  4998.4  257.75  5008.6  258.65
  5014.3  260.91  5030.3  263.46    5036  263.87  5073.7  263.27  5770.9  271.22
  6108.4  289.57  6197.7  294.29  6284.4  295.11  6300.4  296.61  6340.9  296.15
#Mann= 9 ,-1 , 0
  3741.6     .17       0  4371.8     .15       0  4592.8     .11       0
  4905.9     .15       0  4949.3     .09       0  5030.3     .12       0
    5036     .15       0  5073.7     .11       0  6108.4     .17       0
Bank Sta=4949.3,5030.3
XS Rating Curve= 0 ,0
Exp/Cntr=0.3,0.1

Type RM Length L Ch R = 1 ,51414   ,480,480,480
BEGIN DESCRIPTION:
WEST SANDY CREEK 82.0
END DESCRIPTION:
XS GIS Cut Line= 3
      3736954.13     10216181.23      3736719.75     10214264.54
      3736574.01     10213785.69
#Sta/Elev= 30
  3576.5  295.06  3657.3  292.98  3788.2  287.22  3858.7  285.28  3915.4  281.75
  4050.2  277.93  4083.4  276.58  4105.2  274.51  4221.4  265.84  4312.1  262.43
  4684.8  262.72  4805.7  265.05  4916.6   262.1    4977  263.04  4989.9   260.2
  4992.2  254.91  5022.3  254.91  5027.4  262.56  5047.5  264.25  5092.4  263.73
  5234.3  264.05  5339.7   266.4  5390.1  268.55  5410.2  270.81    5529  278.76
  5632.7  283.95  5716.9  286.84  5878.4  292.61  6002.4  294.66    6008  295.61
#Mann= 6 ,-1 , 0
  3576.5     .17       0  4105.2     .15       0    4977     .09       0
  5027.4     .15       0  5092.4     .11       0  5716.9     .17       0
Bank Sta=4977,5027.4
XS Rating Curve= 0 ,0
Exp/Cntr=0.3,0.1

Type RM Length L Ch R = 1 ,50934   ,599,599,599
BEGIN DESCRIPTION:
WEST SANDY CREEK 81.0
END DESCRIPTION:
XS GIS Cut Line= 3
      3737117.85     10216261.05      3737240.58      10214710.1
      3737267.85     10214061.07
#Sta/Elev= 30
  3444.2  298.01  3765.6  286.72  3835.4  283.76  3855.5  281.97  3889.2  281.53
  3965.8  277.55  4030.8  272.25  4141.4  264.97  4246.7  261.76  4617.8  261.62
  4768.3  264.02  4788.4   263.7  4828.5   260.5  4902.9  261.99  4948.9   261.4
  4968.9  262.26    4979  260.18    4982  256.22  5012.1  256.22    5019  262.64
  5029.1  263.74  5067.4  262.63  5209.2  263.56  5279.3  265.68  5339.3   269.6
  5379.4  270.65  5495.7  276.77    5524  277.64  5579.5  280.98  5649.6  281.76
#Mann= 7 ,-1 , 0
  3444.2     .17       0  4030.8     .15       0  4968.9     .09       0
    5019     .15       0  5067.4     .11       0  5495.7     .17       0
    5524     .11       0
Bank Sta=4968.9,5019
XS Rating Curve= 0 ,0
Exp/Cntr=0.3,0.1

Type RM Length L Ch R = 1 ,50335   ,385,385,385
BEGIN DESCRIPTION:
WEST SANDY CREEK 80.0
END DESCRIPTION:
XS GIS Cut Line= 3
      3737217.83     10216361.12       3737756.4     10214954.92
      3738017.85     10214161.07
#Sta/Elev= 30
  3494.2  300.13  3558.5  298.97  3673.5  293.31  3914.1  285.68  3964.4  284.11
  4243.8  271.67  4275.4  271.82    4401  267.29  4431.1  267.98  4455.7  265.96
  4461.1  266.78  4672.2  259.61  4811.4  261.75  4849.6  260.64  4879.6  262.54
  4904.3  258.94  4909.6  261.99    4929  260.47  4934.3  262.43    4959  259.41
    4972  261.14  4979.3  257.68  5009.5  257.68  5025.5  263.18  5108.2  262.77
  5319.9  266.52  5406.8  265.37  5496.9  267.27  5565.7   266.9  5835.8  282.18
#Mann= 7 ,-1 , 0
  3494.2     .17       0  3914.1     .11       0  3964.4     .17       0
  4275.4     .15       0  4934.3     .09       0  5025.5     .15       0
  5108.2     .11       0
Bank Sta=4934.3,5025.5
XS Rating Curve= 0 ,0
Exp/Cntr=0.3,0.1

Type RM Length L Ch R = 1 ,49950   ,705,705,705
BEGIN DESCRIPTION:
WEST SANDY CREEK 79.0
END DESCRIPTION:
XS GIS Cut Line= 3
      3738021.84     10216134.33      3738120.79     10215035.38
      3738167.67     10214160.33
#Sta/Elev= 30
  3898.2   284.5  4062.1  279.85  4113.9  279.92    4130  278.77  4172.6  279.44
  4293.1  278.23  4423.6  275.04  4474.9  272.56    4479  272.36  4499.4  271.55
  4577.6  267.55    4676   263.7  4744.9  260.82  4885.4  262.28  4945.7  263.95
  4965.8  263.21  4975.8  261.84  4986.2  255.41  5016.4  255.41  5025.9  260.64
    5046  261.16    5056  262.93    5086  263.81  5140.6  262.26  5436.5  262.16
  5496.6  263.26  5601.3  268.95  5666.9  274.39    5737  276.05  5877.9  282.04
#Mann= 10 ,-1 , 0
  3898.2     .11       0  4113.9     .17       0  4474.9     .15       0
    4479     .17       0  4499.4     .15       0  4577.6     .17       0
    4676     .15       0  4965.8     .09       0    5056     .15       0
  5140.6     .11       0
Bank Sta=4965.8,5056
XS Rating Curve= 0 ,0
Exp/Cntr=0.3,0.1

Type RM Length L Ch R = 1 ,49245   ,600,600,600
BEGIN DESCRIPTION:
WEST SANDY CREEK 78.0
END DESCRIPTION:
XS GIS Cut Line= 3
      3738667.85     10216161.09      3738579.89     10215385.16
      3738317.85     10213761.07
#Sta/Elev= 30
  4219.1  289.39    4264  287.51  4348.6  281.73  4591.5  270.59  4772.6  264.27
  4843.8   262.7  4923.6  260.81  4963.9   260.9  4968.8  253.61  4999.1  253.61
  5024.4  261.06    5047  262.41  5186.5  262.35    5227  261.52    5308  262.44
  5520.7  260.95  5723.3  262.43  5784.1  262.13  5793.4  261.35  5804.4  258.31
    5850  260.12  5905.7  264.68    5922  267.32  5966.4  272.04  6107.3  280.86
  6219.7  281.53  6371.6  285.43  6412.1  285.66  6616.7  291.32  6645.1   292.8
#Mann= 5 ,-1 , 0
  4219.1     .11       0  4843.8     .15       0  4963.9     .09       0
  5024.4     .15       0    5850     .11       0
Bank Sta=4963.9,5024.4
XS Rating Curve= 0 ,0
Exp/Cntr=0.3,0.1

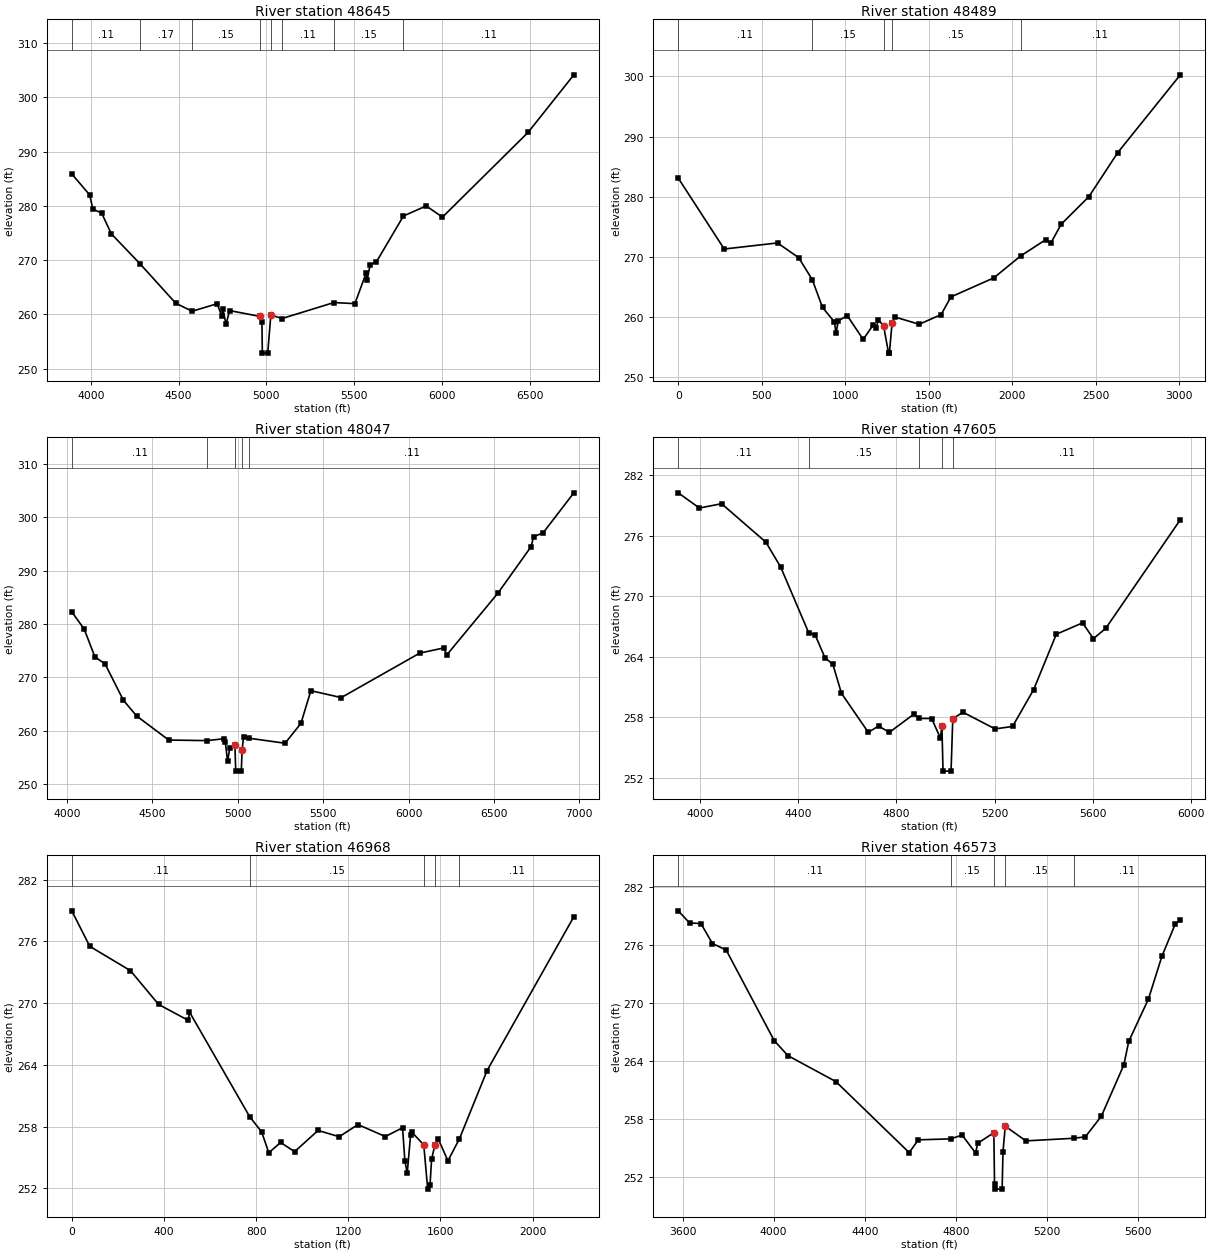
Type RM Length L Ch R = 1 ,48645   ,194,194,194
BEGIN DESCRIPTION:
WEST SANDY CREEK 77.0
END DESCRIPTION:
XS GIS Cut Line= 3
      3738767.85      10216161.1      3738993.96     10215075.91
      3738317.84     10213461.04
#Sta/Elev= 30
  3891.5  285.91  3993.7  282.02  4011.5  279.43  4061.6  278.68  4116.8  274.86
  4278.8  269.39    4484  262.06  4577.5   260.6  4718.9  261.98    4747  259.67
  4752.1  260.99    4770  258.19  4790.4  260.72  4964.1  259.64  4974.3  258.62
  4976.8  252.88  5007.4  252.88  5025.1  259.91  5089.1  259.26  5384.5   262.2
  5503.9     262    5568  267.65  5573.5  266.38  5590.7  269.16  5626.5   269.7
  5780.4  278.15  5909.8     280  6002.6  277.94  6490.5  293.57  6750.7  304.16
#Mann= 8 ,-1 , 0
  3891.5     .11       0  4278.8     .17       0  4577.5     .15       0
  4964.1     .09       0  5025.1     .15       0  5089.1     .11       0
  5384.5     .15       0  5780.4     .11       0
Bank Sta=4964.1,5025.1
XS Rating Curve= 0 ,0
Exp/Cntr=0.3,0.1

Type RM Length L Ch R = 1 ,48489   ,404,404,404
XS GIS Cut Line= 4
      3738834.62     10216164.67      3739246.95      10215661.2
      3739016.91     10214380.81      3738409.27      10213517.1
#Sta/Elev= 30
       0   283.1   275.5  271.31   594.9  272.32     722  269.86   803.3  266.19
   864.3  261.59   935.4   259.2   945.5  257.31   958.7  259.35  1012.4  260.24
  1108.1  256.27  1169.1  258.75  1183.6  258.11  1199.5  259.51    1230  258.56
    1260     254    1265     254  1280.8  258.95    1296  260.02  1443.4   258.8
  1574.6   260.4  1633.3  263.34  1890.4  266.51  2050.4  270.14    2202  272.87
  2231.6  272.28  2294.4  275.44  2460.7  280.04  2633.2  287.35  3007.7  300.27
#Mann= 5 ,-1 , 0
       0     .11       0   803.3     .15       0    1230     .09       0
  1280.8     .15       0  2050.4     .11       0
Bank Sta=1230,1280.8
XS Rating Curve= 0 ,0
Exp/Cntr=0.3,0.1

Type RM Length L Ch R = 1 ,48047   ,442,442,442
BEGIN DESCRIPTION:
WEST SANDY CREEK 76.0
END DESCRIPTION:
XS GIS Cut Line= 3
      3740117.82     10215811.03      3739563.36     10215011.59
      3738417.86     10213411.08
#Sta/Elev= 30
  4027.1  282.31    4100  279.05  4162.8  273.84  4221.8  272.55  4329.7  265.71
  4407.4  262.76  4595.1  258.26  4821.5  258.15  4917.3  258.51  4926.1  257.98
  4939.8  254.28  4953.1   256.8  4982.9  257.31  4987.5  252.43  5020.1  252.43
  5025.2  256.46  5033.3  258.87  5065.6   258.6  5276.6  257.66  5369.6  261.39
  5427.7  267.52  5605.8  266.22  6065.3  274.56  6207.8  275.54  6222.5  274.17
  6524.7  285.86  6717.6  294.52  6732.3  296.37  6788.8  297.14  6968.2  304.62
#Mann= 5 ,-1 , 0
  4027.1     .11       0  4821.5     .15       0  4982.9     .09       0
  5025.2     .15       0  5065.6     .11       0
Bank Sta=4982.9,5025.2
XS Rating Curve= 0 ,0
Exp/Cntr=0.3,0.1

Type RM Length L Ch R = 1 ,47605   ,637,637,637
BEGIN DESCRIPTION:
WEST SANDY CREEK 75.0
END DESCRIPTION:
XS GIS Cut Line= 3
      3740183.29     10215707.23      3740141.63     10215082.25
      3739318.74     10213926.05
#Sta/Elev= 30
  3911.5  280.26  3997.8  278.75    4088  279.18  4268.4  275.37  4328.6  272.91
  4443.3  266.36  4468.9  266.18    4509  263.92  4541.7  263.23  4576.3  260.38
  4685.7   256.5  4727.5  257.12  4771.8   256.5  4870.7  258.29  4892.9  257.88
  4943.9  257.87  4979.6  255.93  4985.7  257.11  4990.3  252.65    5023  252.65
    5030  257.86  5071.8  258.49  5202.1  256.84  5273.5  257.08  5359.5  260.74
  5451.8  266.23  5558.7  267.36    5603  265.79  5653.4  266.82    5957  277.59
#Mann= 5 ,-1 , 0
  3911.5     .11       0  4443.3     .15       0  4892.9     .11       0
  4985.7     .06       0    5030     .11       0
Bank Sta=4985.7,5030
XS Rating Curve= 0 ,0
Exp/Cntr=0.3,0.1

Type RM Length L Ch R = 1 ,46968   ,395,395,395
XS GIS Cut Line= 4
      3740367.85     10215711.07      3740078.34     10214191.61
      3739856.26     10213952.43      3739657.14     10213720.76
#Sta/Elev= 30
       0  278.96    78.2  275.51   254.5  273.15   376.7  269.87   505.7  268.32
   510.8  269.13   771.6  258.98   823.8  257.49   855.1  255.46     906  256.46
   967.1  255.57  1068.9  257.63  1160.5  257.02  1241.9   258.2  1360.7  257.04
  1435.4  257.89  1445.5  254.65  1455.7   253.5  1470.1  257.15  1476.1  257.45
  1527.4  256.23  1544.5  251.93  1554.6  252.33  1561.4  254.83  1575.6  256.21
  1589.8  256.83  1632.3  254.68  1682.2  256.82  1802.3  263.45  2178.7  278.39
#Mann= 5 ,-1 , 0
       0     .11       0   771.6     .15       0  1527.4     .07       0
  1575.6     .15       0  1682.2     .11       0
Bank Sta=1527.4,1575.6
XS Rating Curve= 0 ,0
Exp/Cntr=0.3,0.1

Type RM Length L Ch R = 1 ,46573   ,404,404,404
BEGIN DESCRIPTION:
WEST SANDY CREEK 73.0
END DESCRIPTION:
XS GIS Cut Line= 3
      3740506.21     10215660.39      3740318.71     10213780.17
      3740163.22     10213505.47
#Sta/Elev= 30
    3581  279.58  3630.6  278.33  3680.8  278.26  3731.1   276.2  3791.4  275.53
  4002.4  266.16  4062.7   264.6  4273.7  261.91  4595.3  254.57  4635.5  255.89
  4778.6  255.99  4827.8  256.39  4886.8  254.53  4896.8  255.54  4967.2  256.63
  4970.2  251.29  4970.9  250.79  5003.6  250.79  5007.4  254.68  5017.4   257.3
  5107.9  255.78  5317.7  256.05  5369.1   256.2  5439.5  258.34    5538  263.63
  5559.7  266.07  5646.2  270.46  5705.4  274.88  5764.6  278.25  5786.2  278.58
#Mann= 5 ,-1 , 0
    3581     .11       0  4778.6     .15       0  4967.2     .09       0
  5017.4     .15       0  5317.7     .11       0
Bank Sta=4967.2,5017.4
XS Rating Curve= 0 ,0
Exp/Cntr=0.3,0.1

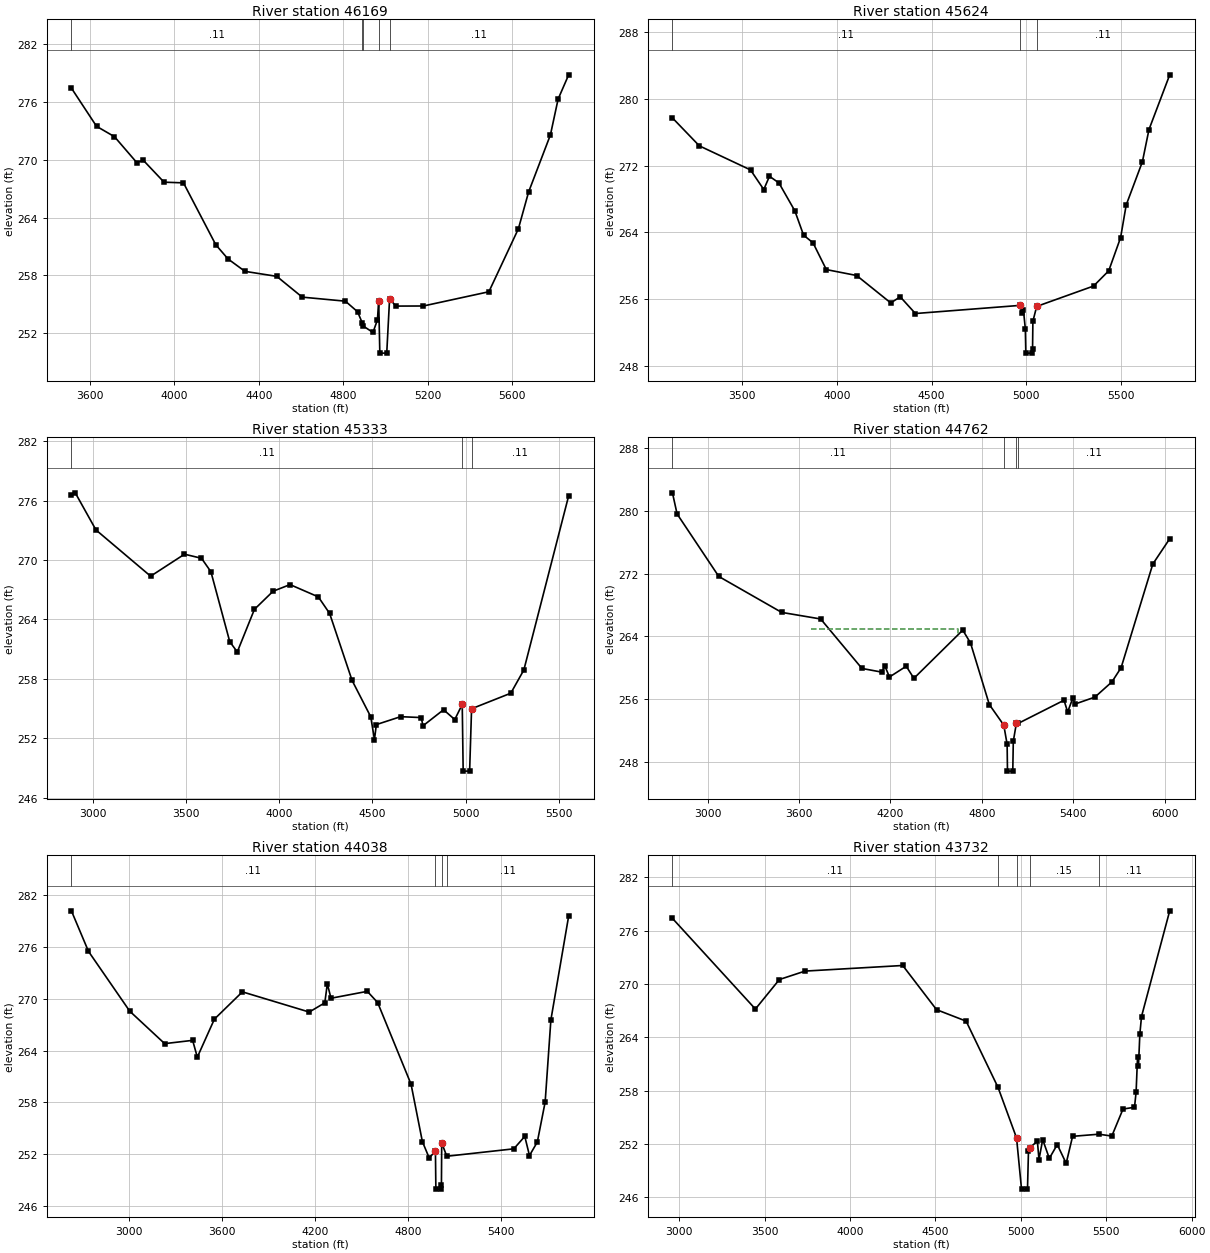
Type RM Length L Ch R = 1 ,46169   ,545,545,545
BEGIN DESCRIPTION:
WEST SANDY CREEK 72.0
END DESCRIPTION:
XS GIS Cut Line= 3
      3740745.79     10215639.54      3740851.95     10214378.34
      3740267.86     10213461.08
#Sta/Elev= 30
  3513.3  277.46  3632.2  273.49  3717.1  272.41  3822.9  269.71    3853  269.97
  3951.7  267.68  4043.6  267.61  4196.4  261.18  4254.4   259.7  4334.7  258.41
  4485.2  257.89  4605.6  255.73  4809.9  255.31  4867.5  254.21  4889.9  253.04
    4894  252.73  4940.3  252.06  4961.5  253.37  4967.4  255.35  4972.8  249.91
  5005.5  249.91    5019  255.56  5048.4   254.8  5178.8  254.81  5488.9  256.29
  5628.5  262.84  5676.8  266.66  5780.1   272.6  5816.5  276.32  5866.4  278.84
#Mann= 5 ,-1 , 0
  3513.3     .11       0  4889.9     .15       0    4894     .11       0
  4967.4     .06       0    5019     .11       0
Bank Sta=4967.4,5019
XS Rating Curve= 0 ,0
Exp/Cntr=0.3,0.1

Type RM Length L Ch R = 1 ,45624   ,291,291,291
BEGIN DESCRIPTION:
WEST SANDY CREEK 71.0
END DESCRIPTION:
XS GIS Cut Line= 3
      3741068.71     10215722.89      3741157.25     10213358.29
      3741256.22     10213118.68
#Sta/Elev= 30
    3132  277.71  3273.9  274.37  3544.1  271.49  3614.2  269.14  3644.2  270.73
  3694.2  269.93  3778.2  266.59  3824.3  263.68  3874.3  262.76  3944.4  259.56
  4104.5  258.85  4284.6  255.57  4334.7   256.3  4414.7   254.3  4965.1  255.27
  4975.1  254.31  4985.1  254.73  4995.1  252.48  4997.8  249.56  5032.4  249.56
  5033.3  250.06  5035.1  253.38  5055.2  255.15  5355.4  257.59  5435.4  259.41
  5498.2  263.39  5527.7  267.29  5613.3  272.47    5648  276.32  5757.5  282.87
#Mann= 3 ,-1 , 0
    3132     .11       0  4965.1     .06       0  5055.2     .11       0
Bank Sta=4965.1,5055.2
XS Rating Curve= 0 ,0
Exp/Cntr=0.3,0.1

Type RM Length L Ch R = 1 ,45333   ,571,571,571
BEGIN DESCRIPTION:
WEST SANDY CREEK 70.0
END DESCRIPTION:
XS GIS Cut Line= 3
      3741209.33     10215811.45      3741402.04     10214415.59
      3741367.85     10213161.06
#Sta/Elev= 30
  2886.9  276.55  2907.5  276.78  3018.5  273.03  3311.3  268.36  3492.8  270.58
  3583.8  270.17  3634.3  268.81  3735.3  261.74  3775.6  260.71  3867.4  265.01
  3967.4  266.84  4058.3  267.51  4209.7  266.27  4270.3   264.6  4390.6  257.83
  4490.6  254.16  4510.6  251.86  4520.6  253.37  4650.7  254.17  4760.7  254.08
  4770.7  253.25  4880.7  254.87  4940.8  253.88  4980.8  255.41  4985.8  248.67
  5020.4  248.67  5030.8  254.97  5240.9  256.54  5310.9  258.89    5551  276.48
#Mann= 3 , 0 , 0
  2886.9     .11       0  4980.8     .06       0  5030.8     .11       0
#XS Ineff= 1 ,-1
    3550  4058.3  267.51
Permanent Ineff=
       F
Bank Sta=4980.8,5030.8
XS Rating Curve= 0 ,0
Exp/Cntr=0.3,0.1

Type RM Length L Ch R = 1 ,44762   ,724,724,724
BEGIN DESCRIPTION:
Mapping XS b441cb63
END DESCRIPTION:
XS GIS Cut Line= 3
        3741751.      10216181.2      3741891.63     10214243.71
      3741527.51     10212974.49
#Sta/Elev= 30
  2769.5   282.3  2799.9  279.61  3073.4  271.65  3486.1  267.07  3742.2  266.23
  4012.9  259.93  4143.2  259.46  4163.3  260.25  4193.4  258.84  4303.6  260.21
  4353.8  258.67  4674.6  264.81  4725.2  263.18  4848.8  255.33  4943.7  252.71
  4965.6  250.27  4967.9  246.85  5002.7  246.85  5006.1  250.65  5026.9  253.01
  5038.3  252.93    5339  255.88  5362.7  254.38  5396.4  256.14  5411.9   255.4
  5541.8  256.28  5653.4  258.22  5713.6  260.03  5921.6  273.23  6032.5  276.45
#Mann= 4 ,-1 , 0
  2769.5     .11       0  4943.7     .06       0  5026.9     .09       0
  5038.3     .11       0
#XS Ineff= 1 ,-1
    3680  4644.5  264.95
Permanent Ineff=
       F
Bank Sta=4943.7,5026.9
XS Rating Curve= 0 ,0
Exp/Cntr=0.3,0.1

Type RM Length L Ch R = 1 ,44038   ,306,306,306
BEGIN DESCRIPTION:
WEST SANDY CREEK 69.0
END DESCRIPTION:
XS GIS Cut Line= 3
      3742428.09     10216301.01      3742511.42     10214181.21
      3742367.85     10213111.04
#Sta/Elev= 30
  2631.9  280.21  2741.9  275.51  3007.5  268.58  3232.3  264.82  3412.4   265.2
  3442.5  263.25  3552.5  267.66  3732.7  270.82    4163  268.48  4263.1  269.55
  4279.4  271.75  4303.1  270.08  4536.8  270.88  4603.4  269.58  4818.4  260.12
  4891.3  253.47  4935.1  251.58  4975.4  252.36  4978.2  247.96  5013.1  247.96
    5014  248.46  5015.8  253.33  5048.3  251.77  5479.9  252.63  5550.6  254.07
  5580.8  251.85  5631.3  253.42  5681.7  258.05  5718.6  267.57  5833.1  279.61
#Mann= 4 ,-1 , 0
  2631.9     .11       0  4975.4     .06       0  5015.8     .11       0
  5048.3     .11       0
Bank Sta=4975.4,5015.8
XS Rating Curve= 0 ,0
Exp/Cntr=0.3,0.1

Type RM Length L Ch R = 1 ,43732   ,520,520,520
BEGIN DESCRIPTION:
WEST SANDY CREEK 68.0
END DESCRIPTION:
XS GIS Cut Line= 3
      3743073.92     10215905.16      3742948.92     10214311.42
      3742417.86     10213111.08
#Sta/Elev= 30
  2960.3  277.38  3445.9  267.18  3586.3   270.5  3736.5  271.45  4308.5  272.08
  4506.4  267.11  4679.6  265.82  4866.5  258.36  4974.8  252.68  5003.9  246.92
  5038.9  246.92  5044.7  251.26  5051.4  251.57  5096.8  252.31  5106.1  250.25
  5127.9  252.49  5166.7  250.38  5213.2  251.93  5265.3  249.82  5302.9  252.86
  5456.9   253.1  5532.5  252.89  5598.1  255.93  5665.3  256.13  5674.7  257.82
  5683.1  261.77  5688.6  260.77  5696.6  264.36  5706.4  266.34  5871.5  278.23
#Mann= 5 ,-1 , 0
  2960.3     .11       0  4866.5     .15       0  4974.8     .09       0
  5051.4     .15       0  5456.9     .11       0
Bank Sta=4974.8,5051.4
XS Rating Curve= 0 ,0
Exp/Cntr=0.3,0.1

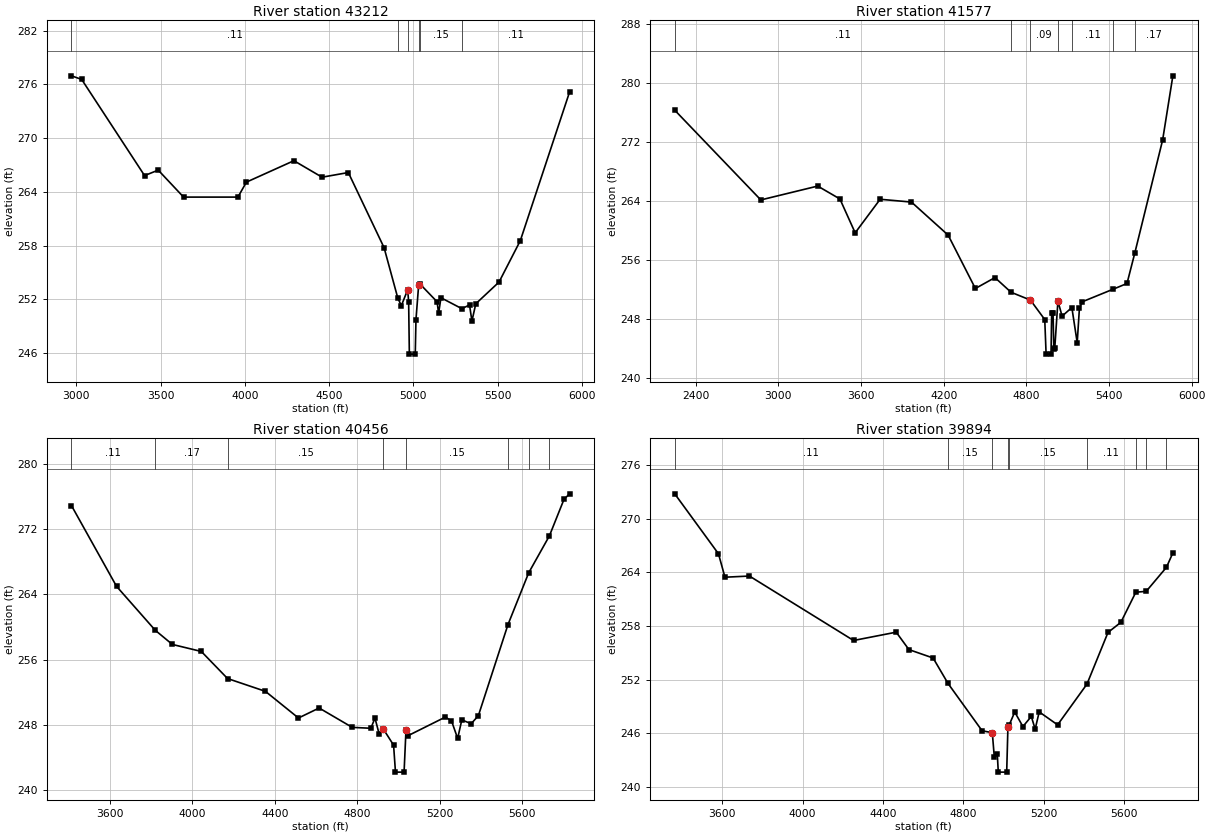
Type RM Length L Ch R = 1 ,43212   ,1635,1635,1635
BEGIN DESCRIPTION:
WEST SANDY CREEK 67.0
END DESCRIPTION:
XS GIS Cut Line= 3
      3743615.58      10215681.2      3743412.46     10214040.59
      3742772.58     10212906.49
#Sta/Elev= 30
  2971.2  276.95  3031.8  276.55    3405  265.82    3486  266.43  3636.4  263.42
  3958.8  263.42  4009.2  265.09    4291  267.48    4458  265.64  4613.8  266.16
  4825.9  257.78  4907.6  252.14  4928.4  251.31    4966  253.08  4971.7  251.75
  4975.9   245.9  5010.9   245.9  5015.1  249.74    5031  253.59  5037.1  253.76
  5140.5  251.74  5149.4  250.45  5163.4  252.19  5287.6  250.97  5332.9  251.39
  5347.1  249.59  5370.1  251.52  5507.9  253.94  5634.2  258.56  5926.5  275.15
#Mann= 6 ,-1 , 0
  2971.2     .11       0  4907.6     .15       0    4966     .09       0
    5031     .12       0  5037.1     .15       0  5287.6     .11       0
Bank Sta=4966,5031
XS Rating Curve= 0 ,0
Exp/Cntr=0.3,0.1

Type RM Length L Ch R = 1 ,41577   ,1121,1121,1121
BEGIN DESCRIPTION:
WEST SANDY CREEK 66.0
END DESCRIPTION:
XS GIS Cut Line= 3
      3743667.67     10215691.66      3743912.46     10213655.17
      3744651.75     10212275.51
#Sta/Elev= 30
  2247.3  276.32  2872.3  264.15  3285.3  266.03  3446.5  264.28  3557.2  259.69
  3738.5  264.24  3965.9  263.86  4232.1  259.38  4429.9  252.14  4572.1  253.62
  4688.8  251.63  4829.6  250.57  4933.6  247.93  4943.4  243.24  4979.1  243.24
  4983.8  248.76  4993.7  248.81  4999.4  243.88  5006.5  244.11  5029.2  250.43
  5059.5  248.39  5130.4  249.56  5169.2  244.79  5185.4   249.5  5207.4  250.35
  5430.8  252.05  5530.7  252.82  5587.6  256.97  5789.3  272.27  5863.7  280.98
#Mann= 7 ,-1 , 0
  2247.3     .11       0  4688.8     .15       0  4829.6     .09       0
  5029.2     .15       0  5130.4     .11       0  5430.8     .15       0
  5587.6     .17       0
Bank Sta=4829.6,5029.2
XS Rating Curve= 0 ,0
Exp/Cntr=0.3,0.1

Type RM Length L Ch R = 1 ,40456   ,562,562,562
BEGIN DESCRIPTION:
WEST SANDY CREEK 65.0
END DESCRIPTION:
XS GIS Cut Line= 3
      3745215.29     10214889.15       3745064.6     10212843.46
       3745000.3      10212484.5
#Sta/Elev= 30
  3413.3  274.93    3632     265  3819.8   259.6  3902.7  257.86  4043.1     257
  4170.4  253.67  4353.9   252.1  4514.3  248.82  4614.6  250.05  4775.1  247.67
  4865.3  247.56  4885.4  248.81  4905.4  246.88  4925.5  247.48  4975.6  245.49
  4984.8  242.17  5026.5  242.17  5035.8  247.37  5045.8  246.65  5226.3  248.93
  5256.4  248.48  5286.4  246.31  5306.5  248.59  5351.9  248.12  5386.7   249.1
  5530.3  260.29  5630.8  266.66  5731.4  271.21  5802.2   275.7  5829.2  276.37
#Mann= 8 ,-1 , 0
  3413.3     .11       0  3819.8     .17       0  4170.4     .15       0
  4925.5     .09       0  5035.8     .15       0  5530.3     .17       0
  5630.8     .11       0  5731.4     .17       0
Bank Sta=4925.5,5035.8
XS Rating Curve= 0 ,0
Exp/Cntr=0.3,0.1

Type RM Length L Ch R = 1 ,39894   ,137,137,137
BEGIN DESCRIPTION:
WEST SANDY CREEK 64.0
END DESCRIPTION:
XS GIS Cut Line= 3
      3745902.79     10215007.16      3745593.77     10213323.18
      3745454.87     10212566.22
#Sta/Elev= 30
  3362.8  272.79  3580.7  266.08    3613  263.46    3735  263.59  4253.8  256.38
  4466.2  257.31  4529.5  255.36    4650  254.42  4724.4  251.57    4894  246.28
  4944.9  246.06    4955  243.32  4969.7  243.68  4974.8  241.65  5016.6  241.65
  5022.8  246.73  5027.9  246.87  5056.7  248.37  5097.4  246.75  5139.3  247.88
  5158.4  246.46  5178.7  248.39  5270.2  246.94  5416.5   251.5  5521.3  257.28
  5585.4  258.41  5659.9  261.78  5711.7  261.88  5812.3  264.56  5844.5  266.18
#Mann= 9 ,-1 , 0
  3362.8     .11       0  4724.4     .15       0  4944.9     .09       0
  5022.8     .12       0  5027.9     .15       0  5416.5     .11       0
  5659.9     .17       0  5711.7     .11       0  5812.3     .17       0
Bank Sta=4944.9,5022.8
XS Rating Curve= 0 ,0
Exp/Cntr=0.3,0.1