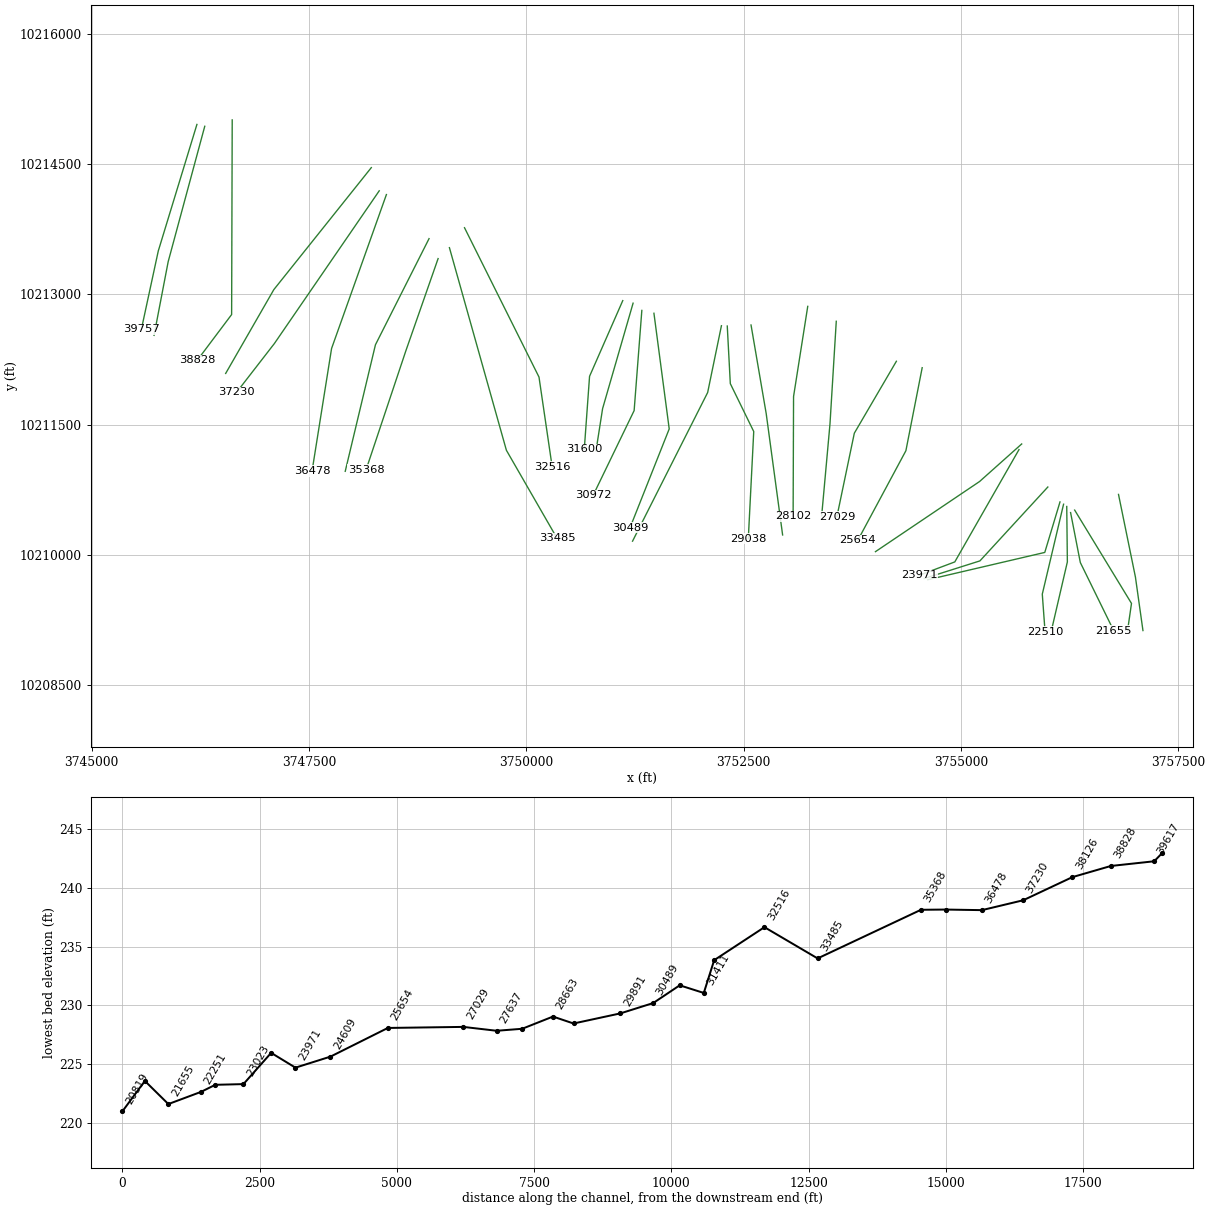
HEC-RAS study WEST SANDY CREEK.prj: WEST SANDY CREEK Base Level Engineering

--- WEST SANDY CREEK.g01 (geometry) --- (continued)

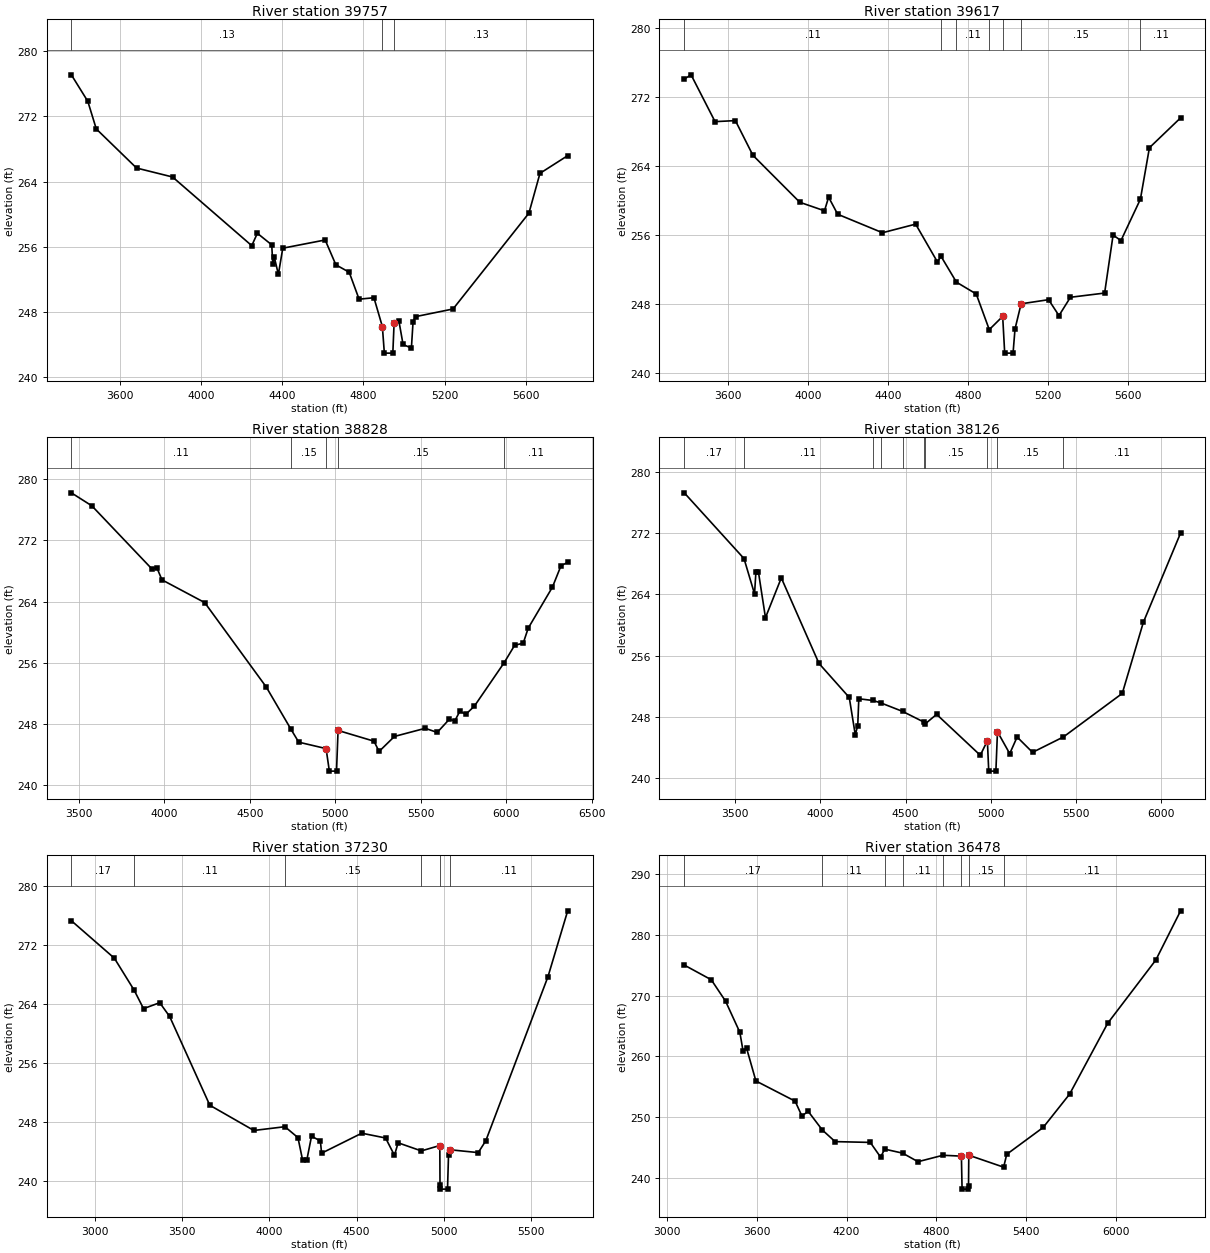
Type RM Length L Ch R = 1 ,39757   ,140,140,140
BEGIN DESCRIPTION:
WEST SANDY CREEK 63.0
END DESCRIPTION:
XS GIS Cut Line= 3
      3746211.83     10214958.62      3745767.38     10213500.26
      3745572.93     10212597.45
#Sta/Elev= 30
  3359.3   277.1  3440.4  273.85  3482.2  270.46  3680.8  265.66  3858.5  264.56
  4249.1  256.13  4276.7  257.65  4347.6  256.23  4352.8  253.88  4360.3  254.72
  4380.4   252.6  4402.1  255.82  4611.2  256.83    4664  253.78  4729.7  252.87
  4778.5  249.56  4851.7  249.74  4893.3   246.2  4903.1  242.94  4944.9  242.94
  4951.2  246.65  4975.1  246.86  4995.4     244  5036.5  243.56  5044.7  246.79
    5057  247.42    5242  248.36  5616.1  260.12  5670.7  265.01  5807.4  267.18
#Mann= 3 , 0 , 0
  3359.3     .13       0  4893.3     .08       0  4951.2     .13       0
#XS Ineff= 1 ,-1
    4080  4611.2  256.83
Permanent Ineff=
       F
Bank Sta=4893.3,4951.2
XS Rating Curve= 0 ,0
Exp/Cntr=0.3,0.1

Type RM Length L Ch R = 1 ,39617   ,789,789,789
BEGIN DESCRIPTION:
WEST SANDY CREEK 62.0
END DESCRIPTION:
XS GIS Cut Line= 3
      3746302.09     10214937.72       3745881.1     10213376.28
      3745718.77     10212528.08
#Sta/Elev= 30
  3382.8  274.12  3416.9  274.61  3536.7  269.17  3638.3  269.29  3725.9  265.26
  3960.3   259.8  4083.6  258.81  4104.3  260.39  4149.5  258.41  4373.5  256.26
  4539.3  257.26  4647.8  252.88  4666.4  253.51  4743.1  250.52  4842.2  249.14
  4907.3     245  4974.3  246.54  4984.4  242.27  5026.2  242.27  5035.9  245.07
  5066.4     248  5203.7  248.48  5255.7  246.63  5312.9  248.76  5483.8  249.25
  5526.2     256  5565.3  255.34  5662.7  260.16  5707.8  266.14  5863.6  269.61
#Mann= 7 ,-1 , 0
  3382.8     .11       0  4666.4     .15       0  4743.1     .11       0
  4907.3     .15       0  4974.3     .09       0  5066.4     .15       0
  5662.7     .11       0
Bank Sta=4974.3,5066.4
XS Rating Curve= 0 ,0
Exp/Cntr=0.3,0.1

Type RM Length L Ch R = 1 ,38828   ,702,702,702
BEGIN DESCRIPTION:
WEST SANDY CREEK 61.0
END DESCRIPTION:
XS GIS Cut Line= 3
      3746617.85     10215011.11      3746611.13     10212767.62
      3746215.31     10212239.86
#Sta/Elev= 30
  3456.7   278.2  3576.7   276.5  3926.7  268.29  3956.7  268.43  3986.7  266.84
  4236.7  263.87  4596.7  252.85  4740.3  247.37  4786.7  245.65  4946.7  244.81
  4965.8  241.87  5007.7  241.87  5016.7  247.18  5226.7  245.78  5256.7  244.44
  5346.7   246.4  5526.7  247.46  5596.7  246.92  5666.7  248.62  5700.2  248.45
  5728.9  249.68  5764.3  249.29  5814.3  250.36  5988.1  256.02  6049.7   258.3
  6099.7  258.57  6128.9  260.53  6270.9   265.9  6320.9  268.69  6359.9  269.12
#Mann= 5 ,-1 , 0
  3456.7     .11       0  4740.3     .15       0  4946.7     .09       0
  5016.7     .15       0  5988.1     .11       0
Bank Sta=4946.7,5016.7
XS Rating Curve= 0 ,0
Exp/Cntr=0.3,0.1

Type RM Length L Ch R = 1 ,38126   ,896,896,896
BEGIN DESCRIPTION:
WEST SANDY CREEK 60.0
END DESCRIPTION:
XS GIS Cut Line= 3
      3748217.85     10214461.07      3747096.57     10213055.02
      3746542.69     10212089.05
#Sta/Elev= 30
  3201.6  277.23  3552.1  268.65  3613.9  264.04    3622  266.92  3636.4  266.95
    3678  260.94  3770.9  266.13  3991.9  254.97  4169.6  250.53  4204.8  245.67
  4219.3  246.85  4225.6  250.36  4307.3  250.14    4353  249.84  4482.6  248.71
  4609.3   247.3  4612.3  247.03    4682  248.33  4938.3  242.99  4979.9  244.88
  4987.9  240.92  5029.8  240.92  5039.1  246.06    5111   243.2  5154.4  245.37
  5244.8  243.37    5426  245.38  5771.3  251.06    5895  260.34  6113.5  271.99
#Mann= 10 ,-1 , 0
  3201.6     .17       0  3552.1     .11       0  4307.3     .15       0
    4353     .11       0  4482.6     .15       0  4609.3     .11       0
  4612.3     .15       0  4979.9     .09       0  5039.1     .15       0
    5426     .11       0
Bank Sta=4979.9,5039.1
XS Rating Curve= 0 ,0
Exp/Cntr=0.3,0.1

Type RM Length L Ch R = 1 ,37230   ,752,752,752
BEGIN DESCRIPTION:
WEST SANDY CREEK 59.0
END DESCRIPTION:
XS GIS Cut Line= 3
      3748309.02      10214193.8      3747102.53     10212433.11
      3746668.42     10211871.79
#Sta/Elev= 30
  2865.6  275.33    3112  270.25  3225.5  265.91  3279.2  263.41  3371.9  264.22
  3428.8  262.35  3658.9  250.32  3911.4   246.9  4089.3  247.41    4164  245.93
    4191  242.84  4214.5  242.86  4241.8  246.12  4292.5  245.48  4299.4  243.82
  4529.7  246.53  4666.2  245.88    4717  243.53  4737.9  245.23  4870.9  244.13
  4976.9  244.86    4978  239.45    4979  238.95    5021  238.95  5026.8   243.6
  5033.2  244.29  5197.1   243.9  5240.6  245.52  5596.7  267.75  5709.6  276.67
#Mann= 6 ,-1 , 0
  2865.6     .17       0  3225.5     .11       0  4089.3     .15       0
  4870.9     .11       0  4976.9     .06       0  5033.2     .11       0
Bank Sta=4976.9,5033.2
XS Rating Curve= 0 ,0
Exp/Cntr=0.3,0.1

Type RM Length L Ch R = 1 ,36478   ,662,662,662
BEGIN DESCRIPTION:
WEST SANDY CREEK 58.0
END DESCRIPTION:
XS GIS Cut Line= 3
      3748391.51     10214150.45      3747760.78     10212376.54
      3747536.58     10210965.34
#Sta/Elev= 30
  3117.3  275.04  3297.4  272.62  3392.6   269.1  3488.1  263.96  3509.3  260.92
  3533.5   261.3  3595.2  255.94  3856.9  252.61    3902  250.17  3944.1  250.93
  4038.6  247.85  4123.9  245.94  4358.4  245.81    4427  243.39  4454.9   244.7
  4574.2  244.04  4676.8  242.63    4843  243.69  4966.3  243.55  4970.9  238.11
  5012.9  238.11  5013.9  238.61  5015.7   243.7  5248.2  241.73  5268.8  243.85
  5511.8  248.27  5688.4  253.77  5942.5  265.45  6263.8  275.88  6428.9  283.98
#Mann= 8 ,-1 , 0
  3117.3     .17       0  4038.6     .11       0  4454.9     .15       0
  4574.2     .11       0    4843     .15       0  4966.3     .09       0
  5015.7     .15       0  5248.2     .11       0
Bank Sta=4966.3,5015.7
XS Rating Curve= 0 ,0
Exp/Cntr=0.3,0.1

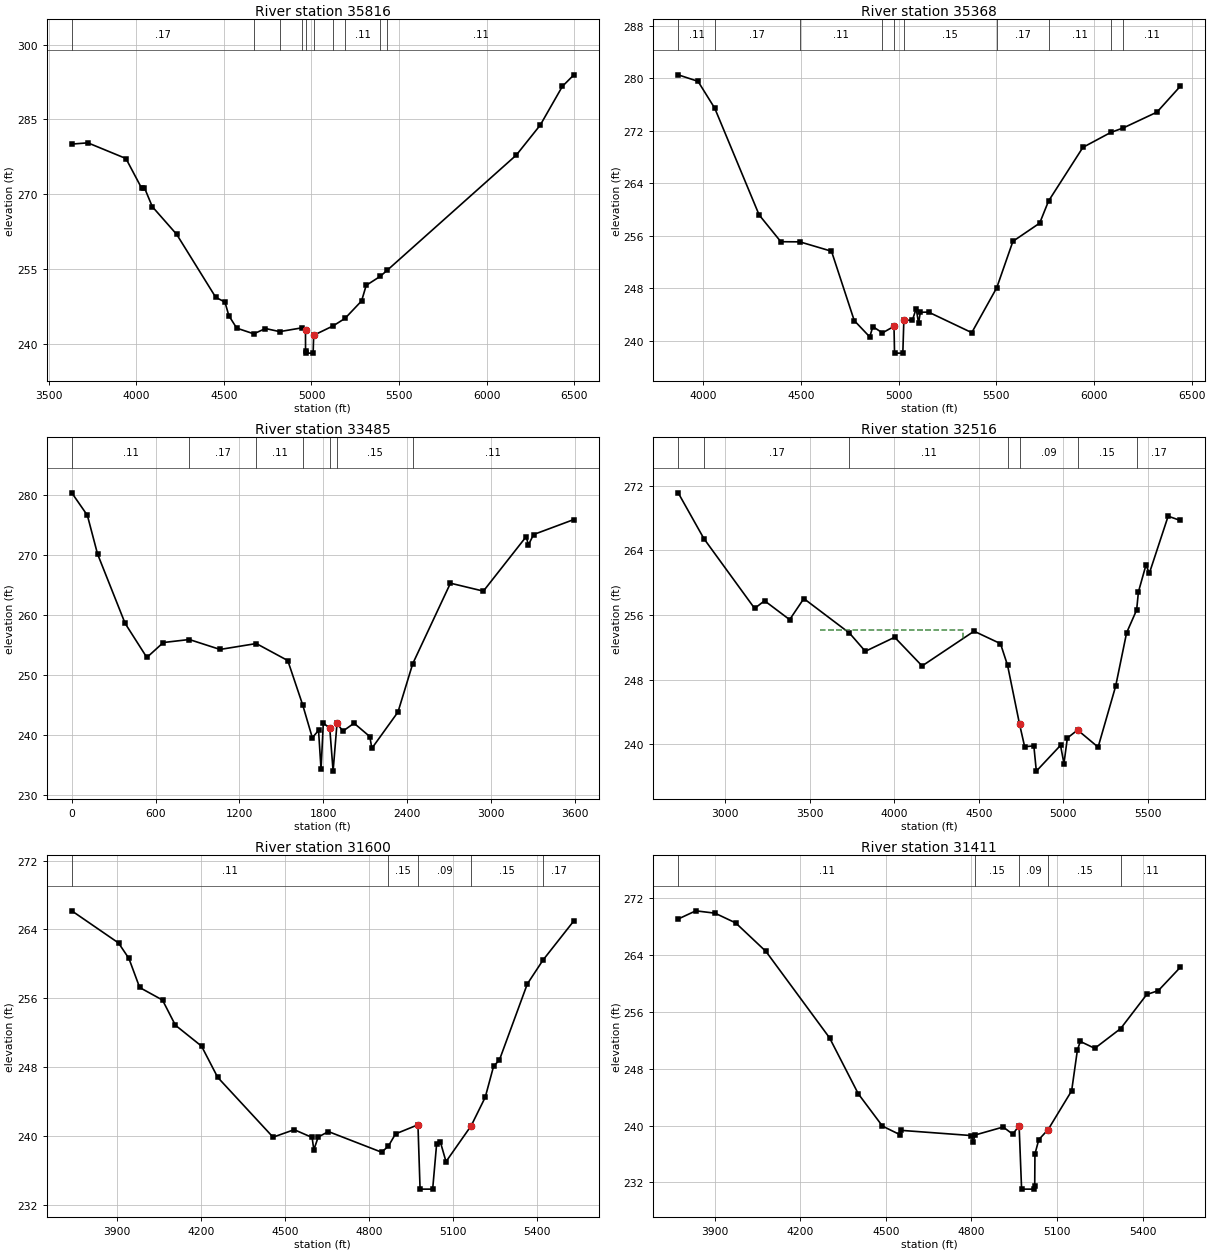
Type RM Length L Ch R = 1 ,35816   ,448,448,448
BEGIN DESCRIPTION:
WEST SANDY CREEK 57.0
END DESCRIPTION:
XS GIS Cut Line= 3
      3748881.96     10213642.61      3748265.46     10212419.49
      3747917.85     10210961.05
#Sta/Elev= 30
  3630.3  280.05  3722.2   280.3  3939.7  277.16  4028.9  271.25  4045.6   271.3
  4090.2  267.52  4229.7  261.96  4452.7  249.35  4505.5  248.39  4527.9  245.66
  4572.7  243.17  4670.1  242.03  4737.1  243.09  4818.1  242.47  4945.7  243.23
  4965.8  242.72  4965.9  238.66  4966.9  238.16  5009.3  238.16  5012.5  241.74
  5123.7  243.62  5191.9  245.13  5286.2  248.62  5312.5  251.74  5392.1  253.53
  5432.5  254.76  6170.3  277.85  6307.1  283.86  6433.5  291.62  6499.3  293.93
#Mann= 10 ,-1 , 0
  3630.3     .17       0  4670.1     .11       0  4818.1     .15       0
  4945.7     .11       0  4965.8     .06       0  5012.5     .11       0
  5123.7     .17       0  5191.9     .11       0  5392.1     .17       0
  5432.5     .11       0
Bank Sta=4965.8,5012.5
XS Rating Curve= 0 ,0
Exp/Cntr=0.3,0.1

Type RM Length L Ch R = 1 ,35368   ,1883,1883,1883
BEGIN DESCRIPTION:
WEST SANDY CREEK 56.0
END DESCRIPTION:
XS GIS Cut Line= 3
      3748986.14     10213412.61      3748613.98     10212346.08
      3748157.15     10210977.72
#Sta/Elev= 30
  3870.4  280.53    3972  279.54  4057.8  275.44  4285.1  259.19  4396.3  255.11
  4493.6  255.09  4655.8  253.66  4772.3   243.1  4851.7  240.61  4867.6  242.18
  4916.7  241.22    4976  242.22  4978.7  238.14  5021.2  238.14  5026.4  243.15
  5070.3  243.16  5089.6  244.93  5101.9  242.69  5110.7  244.36  5152.9  244.39
  5374.3  241.26  5502.3   248.1  5585.1  255.17  5722.2  257.94  5767.5   261.3
  5943.6  269.48    6086  271.75  6150.4  272.44  6323.1  274.85  6442.6  278.79
#Mann= 10 ,-1 , 0
  3870.4     .11       0  4057.8     .17       0  4493.6     .11       0
  4916.7     .15       0    4976     .09       0  5026.4     .15       0
  5502.3     .17       0  5767.5     .11       0    6086     .17       0
  6150.4     .11       0
Bank Sta=4976,5026.4
XS Rating Curve= 0 ,0
Exp/Cntr=0.3,0.1

Type RM Length L Ch R = 1 ,33485   ,969,969,969
BEGIN DESCRIPTION:
SANDY CREEK 55.0
END DESCRIPTION:
XS GIS Cut Line= 3
      3749116.34     10213538.45      3749771.72     10211203.38
      3750353.81     10210189.92
#Sta/Elev= 30
       0  280.29   111.5  276.55   184.2  270.13   381.6  258.58   537.2   252.9
     655  255.39     841  255.89  1061.1  254.24  1320.4  255.22  1545.7  252.39
  1653.1  244.96  1721.3  239.55  1765.8  240.78  1783.7   234.3  1799.9  242.01
  1846.1  241.12    1870     234    1898  241.98  1939.5  240.64  2019.9  241.97
  2132.6  239.75  2147.3  237.79  2334.2  243.83  2439.5  251.85  2709.6  265.26
  2945.4  263.94  3251.6     273  3267.5  271.62  3304.4  273.35  3593.1  275.85
#Mann= 7 ,-1 , 0
       0     .11       0     841     .17       0  1320.4     .11       0
  1653.1     .15       0  1846.1     .09       0    1898     .15       0
  2439.5     .11       0
Bank Sta=1846.1,1898
XS Rating Curve= 0 ,0
Exp/Cntr=0.3,0.1

Type RM Length L Ch R = 1 ,32516   ,916,916,916
BEGIN DESCRIPTION:
WEST SANDY CREEK 54.0
END DESCRIPTION:
XS GIS Cut Line= 3
      3749289.94      10213768.5      3750146.72     10212047.13
      3750298.63      10211009.8
#Sta/Elev= 30
  2721.1  271.11    2873  265.45  3173.5   256.8  3232.1  257.75  3380.7  255.41
  3464.6  258.02  3734.6  253.75  3828.5  251.49    4002  253.23  4164.4  249.68
  4471.9  253.98  4628.3  252.44  4670.2  249.75    4741  242.48  4771.3  239.68
  4825.6  239.79  4840.4  236.66  4983.5  239.85  5003.8   237.6    5024  240.76
  5084.6  241.75  5205.9  239.63  5309.7  247.17  5374.5  253.78  5433.9  256.61
  5444.4  258.84  5488.9  262.16  5509.1  261.15  5620.3  268.22  5692.3  267.69
#Mann= 7 ,-1 , 0
  2721.1     .11       0    2873     .17       0  3734.6     .11       0
  4670.2     .15       0    4741     .09       0  5084.6     .15       0
  5433.9     .17       0
#XS Ineff= 1 ,-1
    3560  4404.9  254.09
Permanent Ineff=
       F
Bank Sta=4741,5084.6
XS Rating Curve= 0 ,0
Exp/Cntr=0.3,0.1

Type RM Length L Ch R = 1 ,31600   ,189,189,189
BEGIN DESCRIPTION:
WEST SANDY CREEK 53.0
END DESCRIPTION:
XS GIS Cut Line= 3
      3751110.26     10212928.21      3750728.31     10212055.81
      3750667.63     10211214.94
#Sta/Elev= 30
  3738.3  266.16  3905.4  262.43  3942.6  260.63    3981  257.26  4062.7   255.8
  4108.8  252.88  4202.3  250.45    4260  246.83    4458  239.88  4533.6  240.75
  4597.6  239.85  4603.8  238.41  4619.4   239.9    4656  240.53  4845.8  238.14
  4869.7  238.81  4895.9  240.26  4976.1  241.32  4983.7  233.85  5028.7  233.85
  5042.8  239.07  5056.3  239.32  5076.4  237.04  5166.6  241.22  5216.7  244.52
  5246.8  248.15  5266.9   248.8  5367.1  257.67  5423.4  260.45  5533.7     265
#Mann= 5 ,-1 , 0
  3738.3     .11       0  4869.7     .15       0  4976.1     .09       0
  5166.6     .15       0  5423.4     .17       0
Bank Sta=4976.1,5166.6
XS Rating Curve= 0 ,0
Exp/Cntr=0.3,0.1

Type RM Length L Ch R = 1 ,31411   ,439,439,439
BEGIN DESCRIPTION:
WEST SANDY CREEK 52.0
END DESCRIPTION:
XS GIS Cut Line= 3
      3751228.97     10212898.72      3750878.27     10211683.42
      3750802.05     10211194.92
#Sta/Elev= 30
  3772.3  269.03    3834  270.18  3901.3  269.85  3973.8  268.48  4079.9  264.47
  4302.6  252.33  4403.5  244.45    4488  239.92  4548.5  238.73  4553.7  239.32
  4799.7  238.59  4804.9  237.72  4813.6  238.68    4911  239.79  4944.6  238.78
  4966.8  239.98  4975.5  231.06  5020.5  231.06  5021.5  231.56  5022.3     236
  5035.8  238.02  5068.6  239.44  5150.9  244.88  5171.1  250.63  5181.3  251.82
  5231.9  250.85  5322.6  253.63    5414  258.42  5454.5  258.96  5531.6  262.24
#Mann= 5 ,-1 , 0
  3772.3     .11       0  4813.6     .15       0  4966.8     .09       0
  5068.6     .15       0  5322.6     .11       0
Bank Sta=4966.8,5068.6
XS Rating Curve= 0 ,0
Exp/Cntr=0.3,0.1

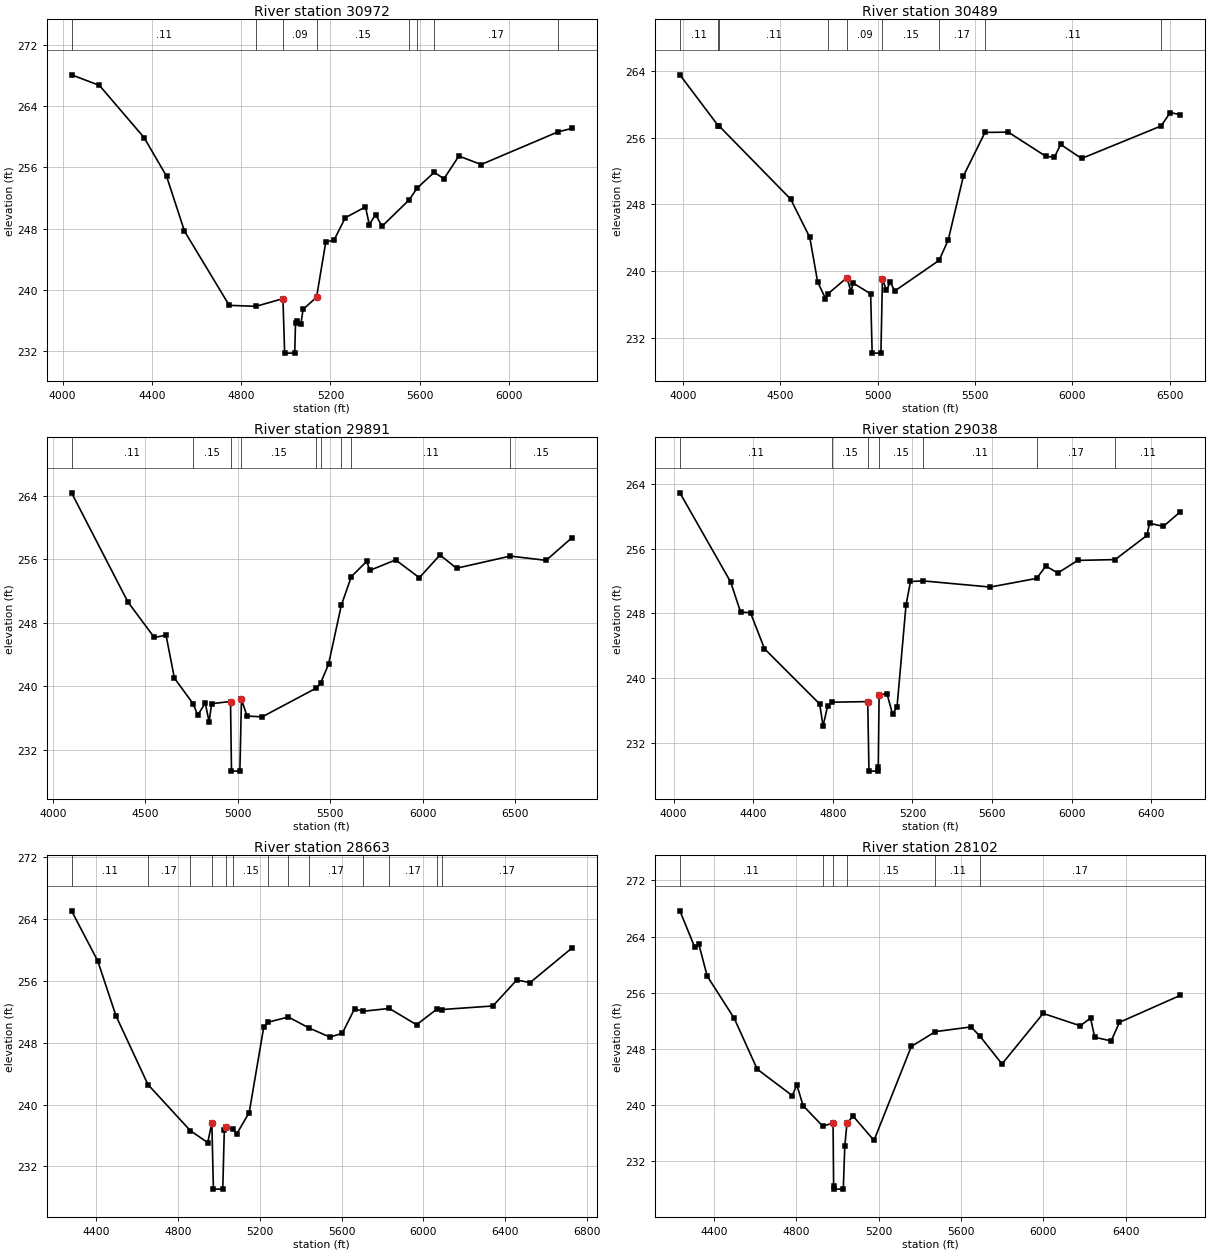
Type RM Length L Ch R = 1 ,30972   ,483,483,483
BEGIN DESCRIPTION:
WEST SANDY CREEK 51.0
END DESCRIPTION:
XS GIS Cut Line= 3
      3751329.66     10212815.34      3751241.12     10211660.85
      3750769.57     10210684.33
#Sta/Elev= 30
  4040.5  268.11  4165.1  266.73  4365.7  259.89    4466  254.85  4546.3  247.67
  4746.8  237.96  4866.8  237.83  4987.5  238.84  4995.1  231.71  5040.2  231.71
  5043.8  235.59  5048.8  235.97  5067.8  235.49  5077.8  237.44    5138  239.02
  5179.4  246.24  5216.1  246.48  5266.9  249.42  5357.3  250.84  5374.3  248.52
  5402.5  249.84  5431.3   248.3  5553.8  251.78  5588.3  253.29    5665  255.35
    5709  254.52  5775.6  257.49  5875.5  256.38    6219  260.64  6282.8  261.11
#Mann= 8 ,-1 , 0
  4040.5     .11       0  4866.8     .15       0  4987.5     .09       0
    5138     .15       0  5553.8     .17       0  5588.3     .11       0
    5665     .17       0    6219     .11       0
#XS Ineff= 1 ,-1
  5357.3    5560  250.84
Permanent Ineff=
       F
Bank Sta=4987.5,5138
XS Rating Curve= 0 ,0
Exp/Cntr=0.3,0.1

Type RM Length L Ch R = 1 ,30489   ,598,598,598
BEGIN DESCRIPTION:
WEST SANDY CREEK 50.0
END DESCRIPTION:
XS GIS Cut Line= 3
      3751468.83     10212782.65      3751644.53     10211449.67
      3751193.12     10210309.06
#Sta/Elev= 30
  3984.1   263.5  4181.1  257.41  4186.3  257.36  4553.1  248.63  4651.4  244.05
  4691.7  238.73  4732.1  236.73  4746.2  237.32    4843  239.24  4863.2  237.52
  4873.3  238.59  4964.1   237.3  4971.8   230.2  5016.9   230.2  5024.6  239.09
  5044.8  237.72  5064.9  238.69  5088.2  237.64  5315.8   241.3  5362.5  243.73
  5440.9  251.41  5551.5  256.61  5671.3  256.64  5864.8  253.74  5908.5  253.65
  5940.1  255.17  6047.7  253.49  6456.3  257.38  6503.2  258.99  6555.3  258.72
#Mann= 9 ,-1 , 0
  3984.1     .11       0  4181.1     .15       0  4186.3     .11       0
  4746.2     .15       0    4843     .09       0  5024.6     .15       0
  5315.8     .17       0  5551.5     .11       0  6456.3     .15       0
Bank Sta=4843,5024.6
XS Rating Curve= 0 ,0
Exp/Cntr=0.3,0.1

Type RM Length L Ch R = 1 ,29891   ,853,853,853
BEGIN DESCRIPTION:
WEST SANDY CREEK 49.0
END DESCRIPTION:
XS GIS Cut Line= 3
       3752245.2     10212638.94      3752086.67     10211868.86
       3751222.9     10210155.95
#Sta/Elev= 30
  4101.8  264.34  4405.9  250.62  4548.8  246.14  4612.3  246.42  4657.5  241.02
  4758.3  237.81  4783.7  236.37  4824.5  237.89  4844.9  235.52  4858.8  237.81
  4960.7  238.08    4966  229.32  5011.3  229.32  5019.9  238.34    5050  236.25
  5131.9  236.15  5424.1  239.77  5447.1  240.37  5490.3  242.76  5559.3  250.18
  5613.6   253.8  5696.8  255.72  5713.5  254.58  5852.9   255.9  5981.1  253.66
  6092.7  256.52  6181.9  254.85  6472.8  256.38  6666.3  255.84  6806.4  258.71
#Mann= 9 ,-1 , 0
  4101.8     .11       0  4758.3     .15       0  4960.7     .09       0
  5019.9     .15       0  5424.1     .17       0  5447.1     .11       0
  5559.3     .15       0  5613.6     .11       0  6472.8     .15       0
Bank Sta=4960.7,5019.9
XS Rating Curve= 0 ,0
Exp/Cntr=0.3,0.1

Type RM Length L Ch R = 1 ,29038   ,375,375,375
BEGIN DESCRIPTION:
WEST SANDY CREEK 48.0
END DESCRIPTION:
XS GIS Cut Line= 4
      3752312.26     10212635.42      3752347.41     10211971.39
      3752616.78      10211419.4      3752554.45     10210186.25
#Sta/Elev= 30
  4031.8  262.93  4286.5   251.9  4336.6  248.17  4386.6  248.07  4456.7  243.62
    4734  236.78    4751  234.04  4773.5  236.48  4795.8     237  4975.3  237.07
  4981.5  228.46  5027.3  228.46  5028.3  228.96  5032.4  237.91  5071.9  238.06
    5100  235.51  5122.6  236.45  5167.6  249.03  5190.1  251.95  5253.9  252.02
  5590.7  251.26  5823.5  252.33    5870  253.86  5930.1     253  6030.2  254.56
  6217.9  254.66  6377.4  257.65  6390.7  259.15  6460.8  258.78  6545.7  260.59
#Mann= 7 ,-1 , 0
  4031.8     .11       0  4795.8     .15       0  4975.3     .09       0
  5032.4     .15       0  5253.9     .11       0  5823.5     .17       0
  6217.9     .11       0
Bank Sta=4975.3,5032.4
XS Rating Curve= 0 ,0
Exp/Cntr=0.3,0.1

Type RM Length L Ch R = 1 ,28663   ,561,561,561
BEGIN DESCRIPTION:
WEST SANDY CREEK 47.0
END DESCRIPTION:
XS GIS Cut Line= 3
      3752585.69     10212647.19      3752760.29     10211625.33
      3752948.98     10210227.48
#Sta/Elev= 30
  4279.7  265.06  4407.6  258.58  4497.1  251.46  4653.2  242.58  4860.3  236.62
  4945.3  235.07  4965.6  237.58  4973.2  229.05    5019  229.05  5026.5   236.7
  5033.1  237.04  5067.1  236.84  5087.4   236.2  5148.2  238.96  5219.2     250
    5241  250.65  5339.9  251.32  5438.6  249.93  5542.7  248.72  5603.2  249.21
  5663.8   252.4  5704.3  252.06  5833.1  252.43  5966.5  250.32  6067.3  252.37
  6091.3  252.29  6339.8  252.75  6456.3  256.11  6521.5  255.77  6726.9  260.26
#Mann= 13 ,-1 , 0
  4279.7     .11       0  4653.2     .17       0  4860.3     .11       0
  4965.6     .06       0  5033.1     .11       0  5067.1     .15       0
    5241     .17       0  5339.9     .11       0  5438.6     .17       0
  5704.3     .15       0  5833.1     .17       0  6067.3     .11       0
  6091.3     .17       0
Bank Sta=4965.6,5033.1
XS Rating Curve= 0 ,0
Exp/Cntr=0.3,0.1

Type RM Length L Ch R = 1 ,28102   ,465,465,465
BEGIN DESCRIPTION:
WEST SANDY CREEK 46.0
END DESCRIPTION:
XS GIS Cut Line= 3
      3753238.03     10212861.97      3753074.84     10211823.03
       3753069.8     10210445.01
#Sta/Elev= 30
  4235.4  267.66  4307.2   262.5  4327.4   262.9  4367.9  258.37  4499.5  252.33
  4610.8   245.1  4781.1  241.33  4803.2  242.87  4833.5   239.9  4929.4  236.97
    4979  237.44  4981.7  228.51  4982.7  228.01  5028.6  228.01    5036  234.12
  5046.6  237.41  5076.5  238.41  5177.7  234.95    5359  248.34    5476  250.45
    5649  251.12  5692.7  249.78    5799  245.84    5999  253.04    6179  251.28
    6229  252.38    6249  249.65    6329  249.12    6369  251.77  6665.1  255.62
#Mann= 6 ,-1 , 0
  4235.4     .11       0  4929.4     .15       0    4979     .09       0
  5046.6     .15       0    5476     .11       0  5692.7     .17       0
#XS Ineff= 1 ,-1
    5649    6450  251.12
Permanent Ineff=
       F
Bank Sta=4979,5046.6
XS Rating Curve= 0 ,0
Exp/Cntr=0.3,0.1

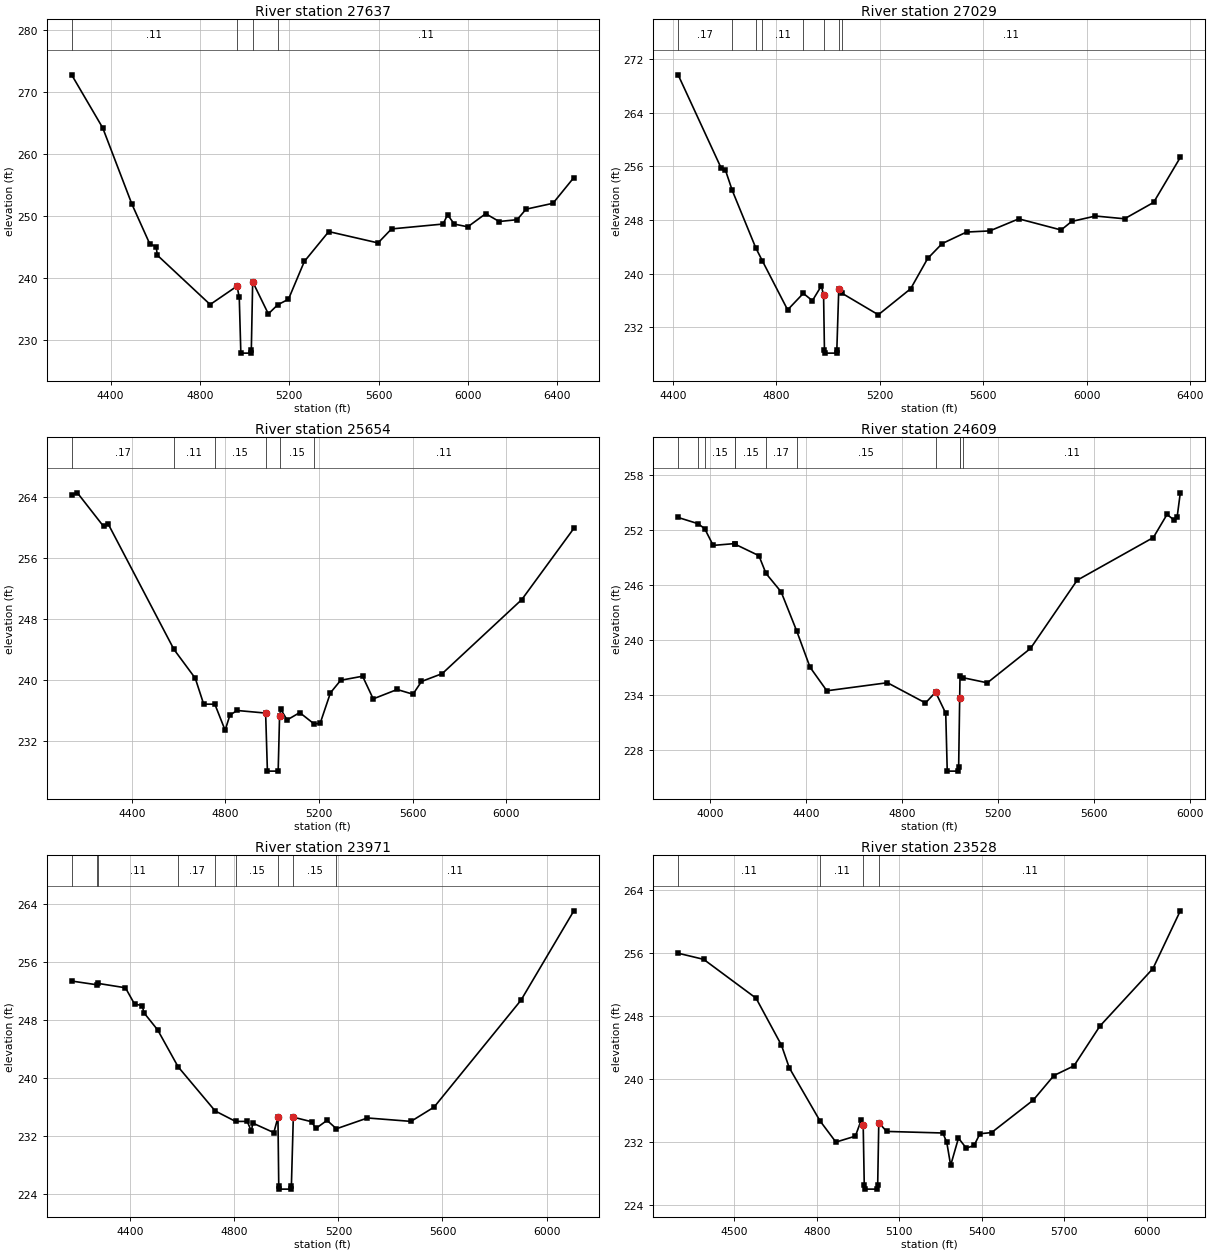
Type RM Length L Ch R = 1 ,27637   ,608,608,608
BEGIN DESCRIPTION:
WEST SANDY CREEK 45.0
END DESCRIPTION:
XS GIS Cut Line= 3
      3753566.16     10212690.15       3753493.8     10211505.99
       3753398.2     10210447.97
#Sta/Elev= 30
  4225.3  272.79  4364.6  264.21  4494.9  251.92    4575  245.49  4603.8  245.02
  4608.8  243.66  4845.5  235.69  4965.8  238.66  4975.8  236.87  4982.9  227.84
  5028.8  227.84  5029.8  228.34  5035.9  239.37    5106  234.18  5147.5  235.63
  5196.2  236.55  5267.3  242.65  5376.5  247.47  5597.3  245.64  5657.6   247.9
  5888.5  248.69  5908.6  250.19  5938.7  248.68    5999  248.24  6079.3  250.36
  6139.5   249.1  6219.9  249.39    6260  251.09  6380.5  252.04    6474  256.19
#Mann= 4 ,-1 , 0
  4225.3     .11       0  4965.8     .09       0  5035.9     .11       0
  5147.5     .11       0
Bank Sta=4965.8,5035.9
XS Rating Curve= 0 ,0
Exp/Cntr=0.3,0.1

Type RM Length L Ch R = 1 ,27029   ,1375,1375,1375
BEGIN DESCRIPTION:
WEST SANDY CREEK 44.0
END DESCRIPTION:
XS GIS Cut Line= 3
      3754257.56     10212229.18      3753773.83     10211400.33
      3753573.97     10210440.09
#Sta/Elev= 30
  4420.9  269.66  4587.8  255.71  4603.5  255.48  4630.1  252.42    4721  243.86
  4746.4  241.93  4844.1  234.62  4904.7  237.08  4939.7  235.99  4974.5   238.2
    4983  236.79  4986.3  228.67  4987.3  228.17  5033.2  228.17  5034.2  228.67
  5041.7  237.75  5055.7  237.06  5194.5  233.89  5319.5  237.77  5385.2  242.28
  5441.1   244.5  5535.4  246.22    5625  246.39  5737.3  248.19  5900.8  246.53
  5941.6   247.8  6033.5  248.61  6145.9   248.2  6258.3  250.64  6361.4  257.35
#Mann= 8 ,-1 , 0
  4420.9     .17       0  4630.1     .11       0    4721     .15       0
  4746.4     .11       0  4904.7     .15       0    4983     .09       0
  5041.7     .15       0  5055.7     .11       0
Bank Sta=4983,5041.7
XS Rating Curve= 0 ,0
Exp/Cntr=0.3,0.1

Type RM Length L Ch R = 1 ,25654   ,1045,1045,1045
BEGIN DESCRIPTION:
WEST SANDY CREEK 43.0
END DESCRIPTION:
XS GIS Cut Line= 3
      3754554.45       10212155.      3754366.94     10211197.95
      3753813.42     10210164.96
#Sta/Elev= 30
  4142.6   264.3    4167  264.56  4279.1  260.16  4299.5  260.44  4579.9  244.04
  4671.2  240.25  4707.1  236.86  4754.9  236.85  4798.8  233.44  4819.2  235.41
  4849.7  236.03    4972  235.69  4979.6  228.08  5025.6  228.08  5031.6  235.29
  5036.7  236.18  5063.7  234.79  5117.8  235.75  5179.2  234.27  5205.1  234.34
  5249.2  238.35    5293  239.99  5386.6  240.52    5432  237.55  5534.3  238.78
  5602.1  238.16  5638.3  239.83  5726.9  240.86  6067.3  250.57  6289.8   259.9
#Mann= 6 ,-1 , 0
  4142.6     .17       0  4579.9     .11       0  4754.9     .15       0
    4972     .09       0  5031.6     .15       0  5179.2     .11       0
Bank Sta=4972,5031.6
XS Rating Curve= 0 ,0
Exp/Cntr=0.3,0.1

Type RM Length L Ch R = 1 ,24609   ,638,638,638
BEGIN DESCRIPTION:
WEST SANDY CREEK 42.0
END DESCRIPTION:
XS GIS Cut Line= 3
      3755698.99     10211276.09      3755214.44     10210843.27
      3754017.02     10210034.99
#Sta/Elev= 30
  3866.4  253.33  3948.5  252.66    3977  252.12  4012.6  250.28  4102.7  250.48
  4104.9   250.4  4203.3  249.16  4232.9  247.22    4296  245.21  4360.8  240.95
  4416.4  236.99  4486.6  234.41  4739.3  235.29  4898.1  233.08  4940.2  234.26
  4982.5  231.96  4988.8  225.64  5035.4  225.64  5036.4  226.14  5040.7 233.631
  5042.1  236.07  5054.3  235.84    5156  235.28  5335.9  239.03  5530.7  246.48
  5848.4  251.14  5905.4  253.66  5935.3  253.04  5947.7   253.4  5960.8  256.02
#Mann= 11 ,-1 , 0
  3866.4     .15       0  3948.5     .11       0    3977     .15       0
  4102.7     .11       0  4104.9     .15       0  4232.9     .17       0
  4360.8     .15       0  4940.2     .09       0  5040.7     .12       0
  5042.1     .15       0  5054.3     .11       0
Bank Sta=4940.2,5040.7
XS Rating Curve= 0 ,0
Exp/Cntr=0.3,0.1

Type RM Length L Ch R = 1 ,23971   ,443,443,443
BEGIN DESCRIPTION:
WEST SANDY CREEK 41.0
END DESCRIPTION:
XS GIS Cut Line= 3
      3755667.86     10211211.08      3754929.44      10209916.7
      3754517.88     10209761.08
#Sta/Elev= 30
  4174.7  253.39  4272.4  252.87  4276.9  253.06  4381.4  252.46  4416.5  250.21
  4446.2  250.01    4452  249.04  4505.3  246.65  4583.8  241.57  4726.3  235.48
  4805.1  234.03  4849.5  234.04  4865.3   232.7  4871.1   233.8  4951.8  232.49
  4967.6  234.61  4970.7   225.2  4971.7   224.7  5018.3   224.7  5019.3   225.2
  5026.7  234.62  5097.2  233.99  5113.1  233.06  5156.3  234.18  5192.3  233.02
  5311.8  234.51  5478.9  234.04  5567.8  236.01  5901.8  250.75  6104.9  263.07
#Mann= 9 ,-1 , 0
  4174.7     .11       0  4272.4     .15       0  4276.9     .11       0
  4583.8     .17       0  4726.3     .11       0  4805.1     .15       0
  4967.6     .09       0  5026.7     .15       0  5192.3     .11       0
Bank Sta=4967.6,5026.7
XS Rating Curve= 0 ,0
Exp/Cntr=0.3,0.1

Type RM Length L Ch R = 1 ,23528   ,505,505,505
BEGIN DESCRIPTION:
WEST SANDY CREEK 40.0
END DESCRIPTION:
XS GIS Cut Line= 3
      3755999.76     10210779.98      3755218.51     10209928.42
      3754579.12     10209725.68
#Sta/Elev= 30
  4295.6  256.01  4388.4  255.23  4579.1  250.28  4671.5  244.29  4699.8  241.42
  4811.1  234.68  4869.4  231.95  4940.3  232.71  4961.3  234.73  4968.7  234.09
  4972.6  226.46  4973.6  225.96  5020.4  225.96  5021.4  226.46  5025.4  234.43
  5053.8  233.31  5258.5  233.11  5272.7  231.91  5286.8  228.99  5315.2  232.46
  5343.6  231.18  5371.9  231.52  5393.4  233.02  5435.4  233.16  5587.2   237.3
  5662.3  240.43  5735.2  241.66  5829.6  246.73  6022.6  254.06    6122  261.41
#Mann= 4 ,-1 , 0
  4295.6     .11       0  4811.1     .11       0  4968.7     .06       0
  5025.4     .11       0
Bank Sta=4968.7,5025.4
XS Rating Curve= 0 ,0
Exp/Cntr=0.3,0.1

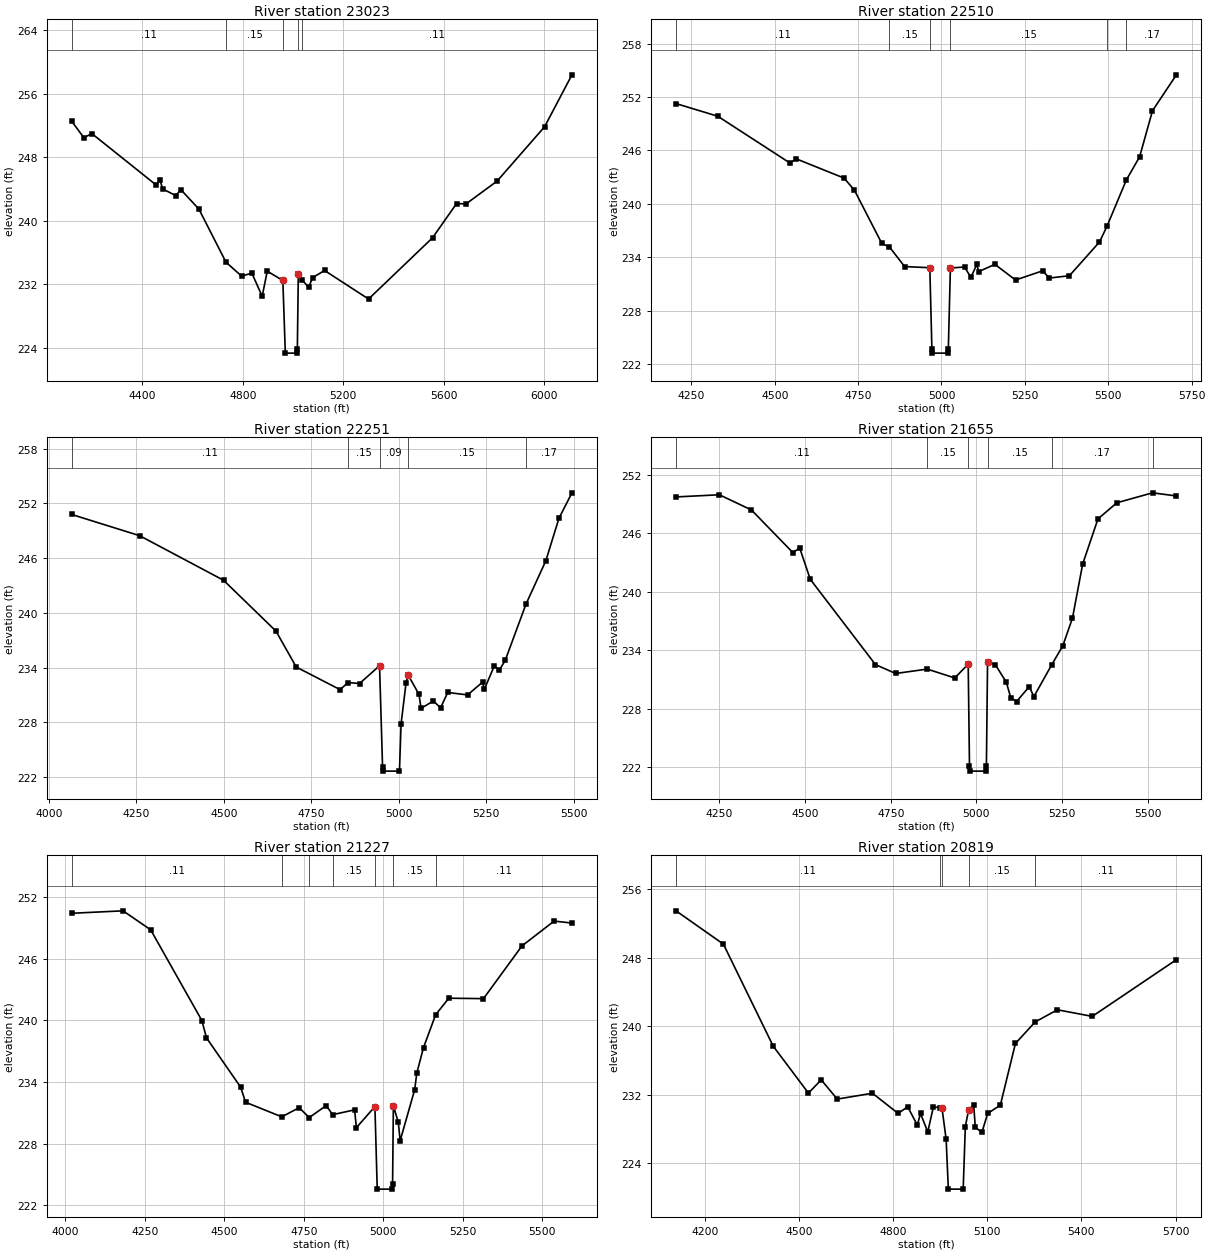
Type RM Length L Ch R = 1 ,23023   ,513,513,513
BEGIN DESCRIPTION:
WEST SANDY CREEK 39.0
END DESCRIPTION:
XS GIS Cut Line= 3
      3756139.57     10210608.06       3755964.6     10210026.07
      3754617.87     10209711.08
#Sta/Elev= 30
  4118.6  252.57  4167.7  250.45    4199  250.99  4454.7  244.51  4470.5  245.13
  4480.9  244.01  4533.1  243.16  4553.8   243.9  4625.1  241.47  4733.1  234.76
  4794.9  233.02    4836  233.38    4877  230.47  4897.2  233.63  4959.2  232.46
  4969.1   223.3  5015.9   223.3  5016.9   223.8  5020.8  233.29  5037.3  232.49
  5061.9  231.59  5077.4  232.81  5125.1  233.72  5300.2  230.12  5554.8  237.84
  5650.4  242.16  5687.8  242.11  5811.6  244.99  6000.6  251.84  6109.4  258.39
#Mann= 5 ,-1 , 0
  4118.6     .11       0  4733.1     .15       0  4959.2     .09       0
  5020.8     .15       0  5037.3     .11       0
Bank Sta=4959.2,5020.8
XS Rating Curve= 0 ,0
Exp/Cntr=0.3,0.1

Type RM Length L Ch R = 1 ,22510   ,259,259,259
BEGIN DESCRIPTION:
WEST SANDY CREEK 38.0
END DESCRIPTION:
XS GIS Cut Line= 3
      3756180.74      10210581.6      3755935.96     10209545.17
      3755967.85     10209111.09
#Sta/Elev= 30
  4204.1  251.26  4329.3  249.84  4545.9  244.58  4564.3  245.06  4708.1  242.89
    4739  241.53  4821.2  235.55  4843.6  235.18  4889.5  232.96    4965  232.83
  4971.2  223.74  4972.2  223.24  5019.5  223.24  5020.5  223.74  5026.7   232.8
    5069  232.91  5088.3  231.75  5106.1  233.22  5111.3  232.39  5160.2  233.21
  5221.9  231.45  5303.2  232.48  5323.3  231.67  5383.5  231.93  5473.7  235.72
  5495.9  237.46  5554.4   242.7    5594  245.28  5632.6  250.46  5704.3  254.49
#Mann= 6 ,-1 , 0
  4204.1     .11       0  4843.6     .15       0    4965     .09       0
  5026.7     .15       0  5495.9     .11       0  5554.4     .17       0
Bank Sta=4965,5026.7
XS Rating Curve= 0 ,0
Exp/Cntr=0.3,0.1

Type RM Length L Ch R = 1 ,22251   ,596,596,596
BEGIN DESCRIPTION:
WEST SANDY CREEK 37.0
END DESCRIPTION:
XS GIS Cut Line= 3
       3756217.2     10210555.61      3756224.36     10209916.77
      3756045.56      10209145.1
#Sta/Elev= 30
  4064.4   250.8    4259  248.47    4499  243.58    4649     238    4707  234.06
  4832.3  231.58  4855.3  232.36    4888  232.25  4945.2   234.2  4953.8  223.14
  4954.8  222.64  5002.1  222.64  5006.8  227.82  5021.1  232.36  5027.3  233.16
  5058.1  231.05  5063.8  229.53  5099.2  230.33  5119.7  229.59  5140.3  231.27
    5197     231  5239.7   232.4  5244.8  231.61  5273.7  234.21  5287.5  233.71
  5304.5  234.78  5364.2  240.98  5420.7  245.71  5458.2  250.37  5495.4  253.17
#Mann= 5 ,-1 , 0
  4064.4     .11       0  4855.3     .15       0  4945.2     .09       0
  5027.3     .15       0  5364.2     .17       0
Bank Sta=4945.2,5027.3
XS Rating Curve= 0 ,0
Exp/Cntr=0.3,0.1

Type RM Length L Ch R = 1 ,21655   ,428,428,428
BEGIN DESCRIPTION:
WEST SANDY CREEK 36.0
END DESCRIPTION:
XS GIS Cut Line= 3
      3756261.48     10210485.27      3756373.42     10209909.65
      3756756.86     10209125.59
#Sta/Elev= 30
    4124  249.71  4250.5  249.93    4344  248.37  4464.5  244.01  4484.8  244.46
  4515.4  241.27  4705.6  232.52  4764.5  231.61  4856.7  232.06  4936.9  231.15
    4976  232.57  4979.8   222.1  4980.8   221.6  5028.1   221.6  5029.1   222.1
  5032.5  232.82    5055  232.52  5087.3  230.71    5100  229.14    5117  228.73
  5154.1  230.26  5167.6  229.24  5219.4  232.49  5252.1  234.46  5280.1  237.29
  5309.9  242.83  5354.5  247.46  5409.6  249.11  5513.5  250.13  5583.2  249.81
#Mann= 6 ,-1 , 0
    4124     .11       0  4856.7     .15       0    4976     .09       0
  5032.5     .15       0  5219.4     .17       0  5513.5     .11       0
Bank Sta=4976,5032.5
XS Rating Curve= 0 ,0
Exp/Cntr=0.3,0.1

Type RM Length L Ch R = 1 ,21227   ,408,408,408
BEGIN DESCRIPTION:
WEST SANDY CREEK 35.0
END DESCRIPTION:
XS GIS Cut Line= 3
      3756308.37      10210513.9        3756962.      10209438.4
      3756916.94     10209125.57
#Sta/Elev= 30
  4019.2  250.43  4181.2  250.67  4268.2  248.82  4429.2  239.99  4443.8   238.3
  4551.3   233.5  4566.8  232.03  4680.7  230.61  4735.4   231.5  4767.2  230.54
  4820.7  231.71  4840.6  230.82  4909.8  231.29  4915.6  229.56  4973.8  231.61
  4981.1  223.57  5028.4  223.57  5029.4  224.07  5031.9  231.67  5047.4  230.09
  5053.2  228.28  5099.1  233.27  5105.5  234.86  5126.8  237.36  5164.9  240.55
  5206.3  242.16  5315.5  242.12  5436.7  247.26  5537.7  249.67  5593.8  249.48
#Mann= 7 ,-1 , 0
  4019.2     .11       0  4680.7     .15       0  4767.2     .11       0
  4840.6     .15       0  4973.8     .09       0  5031.9     .15       0
  5164.9     .11       0
Bank Sta=4973.8,5031.9
XS Rating Curve= 0 ,0
Exp/Cntr=0.3,0.1

Type RM Length L Ch R = 1 ,20819   ,715,715,715
BEGIN DESCRIPTION:
WEST SANDY CREEK 34.0
END DESCRIPTION:
XS GIS Cut Line= 3
       3756812.7     10210694.44      3757007.14     10209743.09
      3757093.87     10209125.57
#Sta/Elev= 30
  4108.2  253.47  4259.2  249.58  4417.8  237.68  4530.1   232.2  4570.9  233.74
    4622   231.5  4734.2  232.18  4815.9  229.83  4846.5   230.6  4877.1  228.46
  4887.4  229.82  4910.4  227.66  4928.2  230.57  4950.6  230.51  4955.8  230.45
    4969   226.8    4976  220.99  5023.3  220.99  5030.2  228.28  5040.5  230.24
  5056.8  230.81  5061.9  228.22  5082.8   227.6  5101.5  229.83  5141.8  230.79
  5189.8  237.99  5252.6   240.5  5323.6  241.92  5434.7  241.15  5702.8  247.77
#Mann= 5 ,-1 , 0
  4108.2     .11       0  4950.6     .15       0  4955.8     .09       0
  5040.5     .15       0  5252.6     .11       0
Bank Sta=4955.8,5040.5
XS Rating Curve= 0 ,0
Exp/Cntr=0.3,0.1