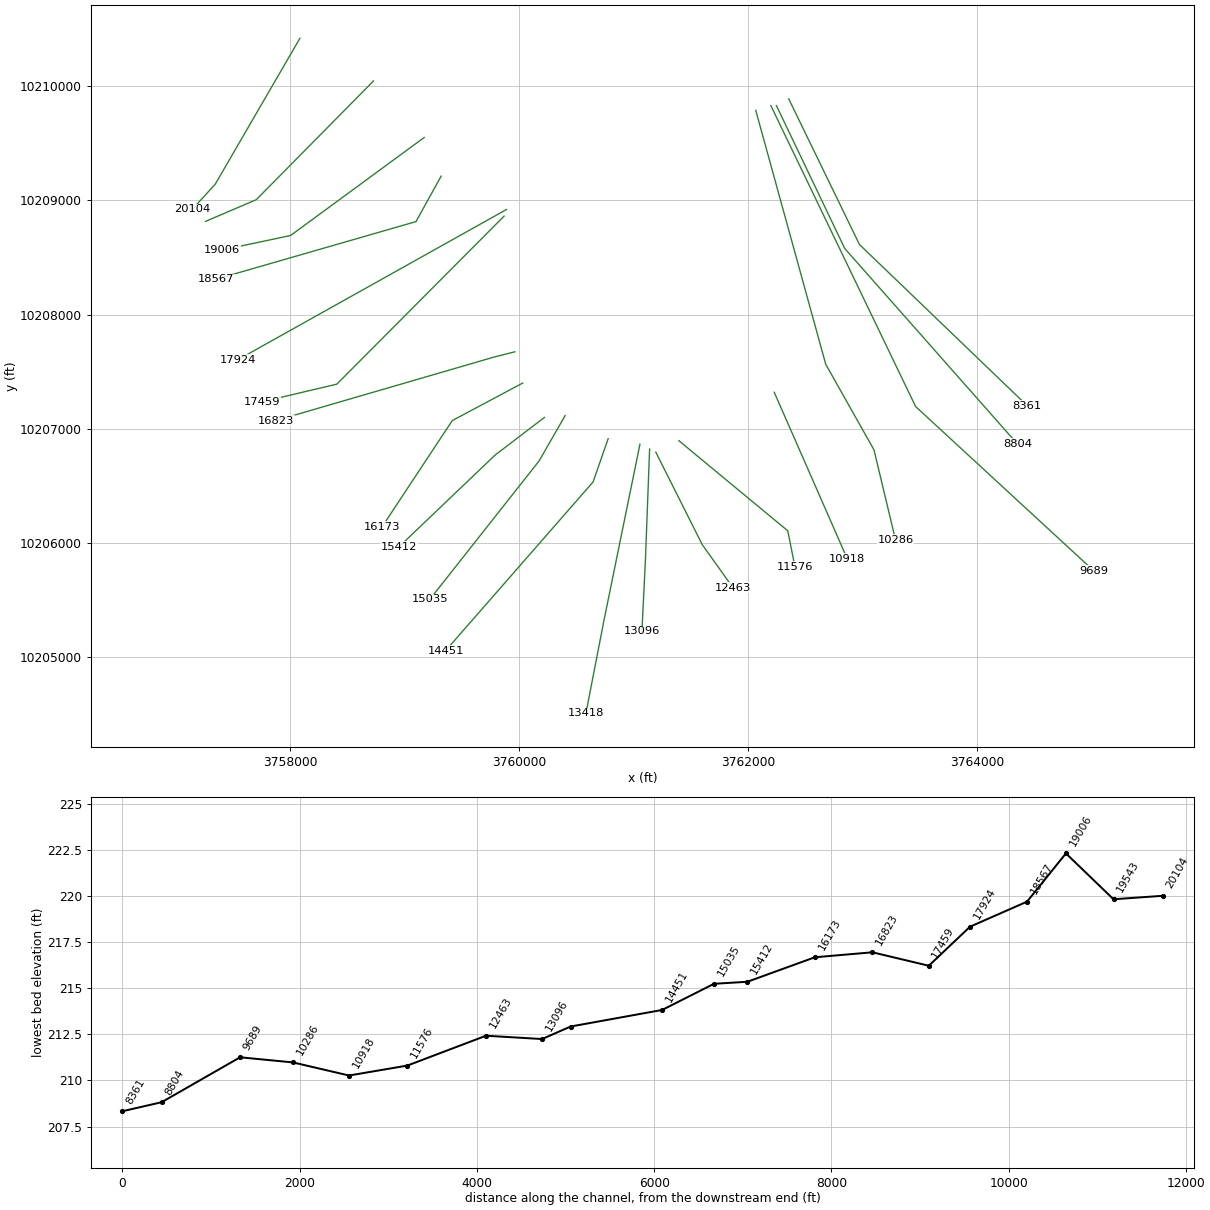
HEC-RAS study WEST SANDY CREEK.prj: WEST SANDY CREEK Base Level Engineering

--- WEST SANDY CREEK.g01 (geometry) --- (continued)

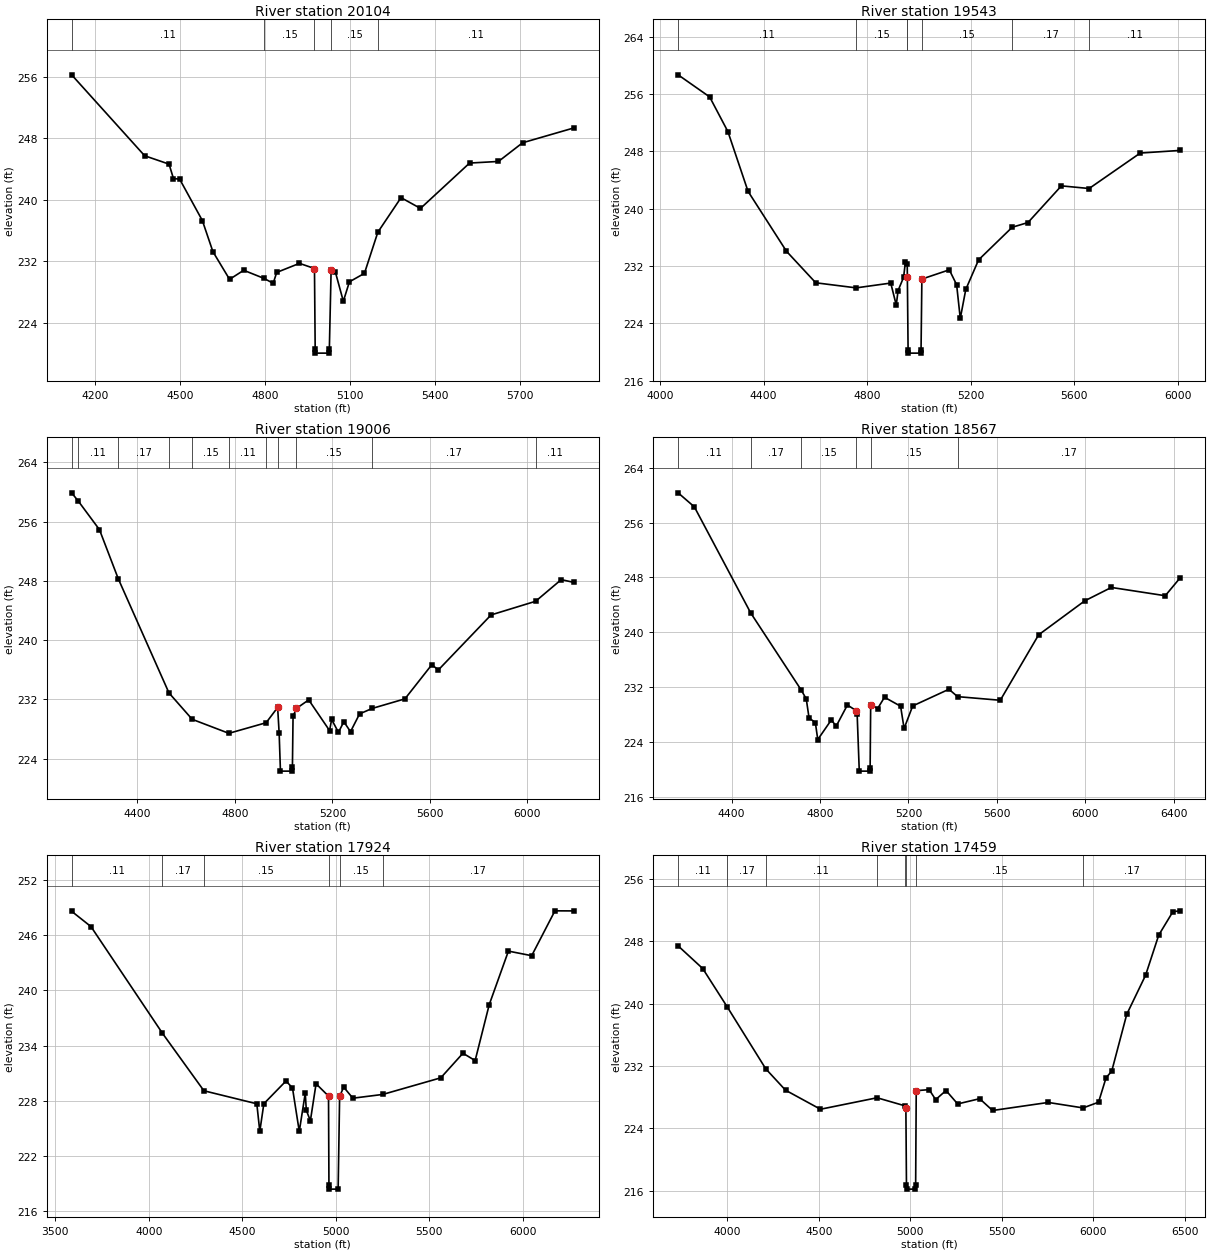
Type RM Length L Ch R = 1 ,20104   ,561,561,561
BEGIN DESCRIPTION:
WEST SANDY CREEK 33.0
END DESCRIPTION:
XS GIS Cut Line= 3
      3758083.52     10210416.68      3757343.62     10209140.28
      3757142.73     10208920.37
#Sta/Elev= 30
  4118.1  256.24  4375.9  245.71    4462  244.62  4477.7  242.73  4499.3  242.68
  4579.6  237.28  4616.9  233.23  4675.7  229.63  4725.6  230.81  4798.3  229.74
  4829.7  229.11  4842.1  230.53  4922.5  231.71  4975.5  231.04    4978  220.53
    4979  220.03    5027  220.03    5028  220.53  5034.3  230.89  5049.3  230.58
  5077.4  226.78  5098.9  229.31  5151.9  230.41  5199.2  235.76  5281.1  240.26
  5349.8  238.86  5523.2  244.76  5625.2  244.97  5710.4   247.4  5891.3  249.33
#Mann= 5 ,-1 , 0
  4118.1     .11       0  4798.3     .15       0  4975.5     .09       0
  5034.3     .15       0  5199.2     .11       0
Bank Sta=4975.5,5034.3
XS Rating Curve= 0 ,0
Exp/Cntr=0.3,0.1

Type RM Length L Ch R = 1 ,19543   ,537,537,537
BEGIN DESCRIPTION:
WEST SANDY CREEK 32.0
END DESCRIPTION:
XS GIS Cut Line= 3
      3758727.07      10210044.1      3757702.21      10209004.9
      3757259.67     10208815.53
#Sta/Elev= 30
  4069.7  258.69  4191.5  255.61  4262.2  250.76    4340  242.42  4488.5  234.06
  4601.6  229.66  4757.9  228.95  4891.5  229.62  4912.8  226.54  4919.8  228.57
  4941.1  230.42  4948.1  232.55  4955.2  232.35  4955.7  230.53  4958.5  220.34
  4959.5  219.84  5007.6  219.84  5008.6  220.34  5011.8  230.18  5117.8  231.47
  5146.1  229.39  5160.2  224.68  5181.5  228.73    5231  232.86  5360.8  237.41
  5421.9  238.07    5551  243.19  5658.2  242.82  5855.8  247.77  6010.6  248.14
#Mann= 7 ,-1 , 0
  4069.7     .11       0  4757.9     .15       0  4955.2     .12       0
  4955.7     .09       0  5011.8     .15       0  5360.8     .17       0
  5658.2     .11       0
Bank Sta=4955.7,5011.8
XS Rating Curve= 0 ,0
Exp/Cntr=0.3,0.1

Type RM Length L Ch R = 1 ,19006   ,439,439,439
BEGIN DESCRIPTION:
WEST SANDY CREEK 31.0
END DESCRIPTION:
XS GIS Cut Line= 3
      3759169.78     10209549.32      3758002.17      10208691.7
      3757404.18     10208564.96
#Sta/Elev= 30
  4130.4  259.87  4158.2  258.73  4244.5   254.9  4321.6  248.28  4529.6  232.88
  4624.8  229.32  4775.3  227.43  4928.2  228.86  4975.4  230.92  4981.6  227.43
  4986.9  222.33    5035  222.33    5036  222.83  5038.6  229.72  5052.6  230.79
  5102.8  231.94  5188.4   227.8  5196.9   229.3  5224.7  227.57    5247  228.99
  5274.3  227.65  5311.5  230.05  5363.4  230.79  5497.6  232.08  5607.7  236.68
  5634.7  235.98  5850.9   243.4  6033.5  245.24  6138.7  248.16  6190.4  247.79
#Mann= 11 ,-1 , 0
  4130.4     .17       0  4158.2     .11       0  4321.6     .17       0
  4529.6     .11       0  4624.8     .15       0  4775.3     .11       0
  4928.2     .15       0  4975.4     .09       0  5052.6     .15       0
  5363.4     .17       0  6033.5     .11       0
Bank Sta=4975.4,5052.6
XS Rating Curve= 0 ,0
Exp/Cntr=0.3,0.1

Type RM Length L Ch R = 1 ,18567   ,643,643,643
BEGIN DESCRIPTION:
WEST SANDY CREEK 30.0
END DESCRIPTION:
XS GIS Cut Line= 3
      3759317.87     10209211.11      3759098.19     10208813.49
      3757352.45     10208309.86
#Sta/Elev= 30
  4158.2  260.36  4231.6  258.31  4486.4  242.82  4714.8  231.56  4737.7  230.26
  4750.4  227.48  4778.8   226.8  4789.8  224.32  4851.3   227.2    4873  226.27
  4923.8  229.37  4962.7  228.56  4967.9  228.02  4977.5  219.71  5025.6  219.71
  5026.6  220.21  5029.1  229.44  5060.4  228.84  5091.6   230.5  5164.4  229.19
  5180.2  225.94  5219.1  229.23    5383  231.67    5422  230.59  5615.2  230.06
  5788.7  239.62  5997.1  244.58  6117.6  246.54  6361.3  245.33  6429.4  247.97
#Mann= 6 ,-1 , 0
  4158.2     .11       0  4486.4     .17       0  4714.8     .15       0
  4962.7     .09       0  5029.1     .15       0    5422     .17       0
Bank Sta=4962.7,5029.1
XS Rating Curve= 0 ,0
Exp/Cntr=0.3,0.1

Type RM Length L Ch R = 1 ,17924   ,465,465,465
BEGIN DESCRIPTION:
WEST SANDY CREEK 29.0
END DESCRIPTION:
XS GIS Cut Line= 2
      3759888.59     10208919.14      3757544.77     10207606.61
#Sta/Elev= 30
  3587.4  248.63  3690.8  246.96  4073.3  235.33  4294.8  229.07  4577.9  227.65
  4593.8  224.64  4615.5  227.66  4734.2  230.14  4768.7  229.37    4805  224.64
    4837  228.81  4842.7  226.94  4864.4   225.8  4894.8  229.83  4961.4  228.49
  4963.7  218.85  4964.7  218.35  5012.9  218.35  5020.8  228.45  5042.4  229.47
  5091.6  228.26  5251.6  228.67  5561.9  230.48  5680.6  233.16  5745.7  232.36
    5821  238.45  5923.7  244.29  6048.2  243.79  6172.6  248.68  6273.7  248.67
#Mann= 6 ,-1 , 0
  3587.4     .11       0  4073.3     .17       0  4294.8     .15       0
  4961.4     .09       0  5020.8     .15       0  5251.6     .17       0
Bank Sta=4961.4,5020.8
XS Rating Curve= 0 ,0
Exp/Cntr=0.3,0.1

Type RM Length L Ch R = 1 ,17459   ,636,636,636
BEGIN DESCRIPTION:
WEST SANDY CREEK 28.0
END DESCRIPTION:
XS GIS Cut Line= 3
      3759867.87     10208861.09      3758406.28     10207391.33
       3757753.1     10207236.83
#Sta/Elev= 30
  3731.5  247.38  3865.9  244.48  3999.5  239.58  4210.3  231.64  4318.4   228.9
  4509.3  226.46  4818.6  227.93    4969  226.91    4976  226.68  4979.2  216.73
  4980.2  216.23  5028.4  216.23  5029.4  216.73  5032.6  228.84  5103.3  228.97
  5138.7  227.69  5195.3  228.86  5258.9  227.14  5379.1  227.81  5449.8   226.3
  5753.9  227.33  5944.2  226.63  6028.7  227.36  6069.9   230.5  6100.7  231.33
  6182.9  238.62  6285.6  243.61  6357.6  248.76    6435  251.76  6475.5  251.87
#Mann= 8 ,-1 , 0
  3731.5     .11       0  3999.5     .17       0  4210.3     .11       0
  4818.6     .15       0    4969     .12       0    4976     .09       0
  5032.6     .15       0  5944.2     .17       0
Bank Sta=4976,5032.6
XS Rating Curve= 0 ,0
Exp/Cntr=0.3,0.1

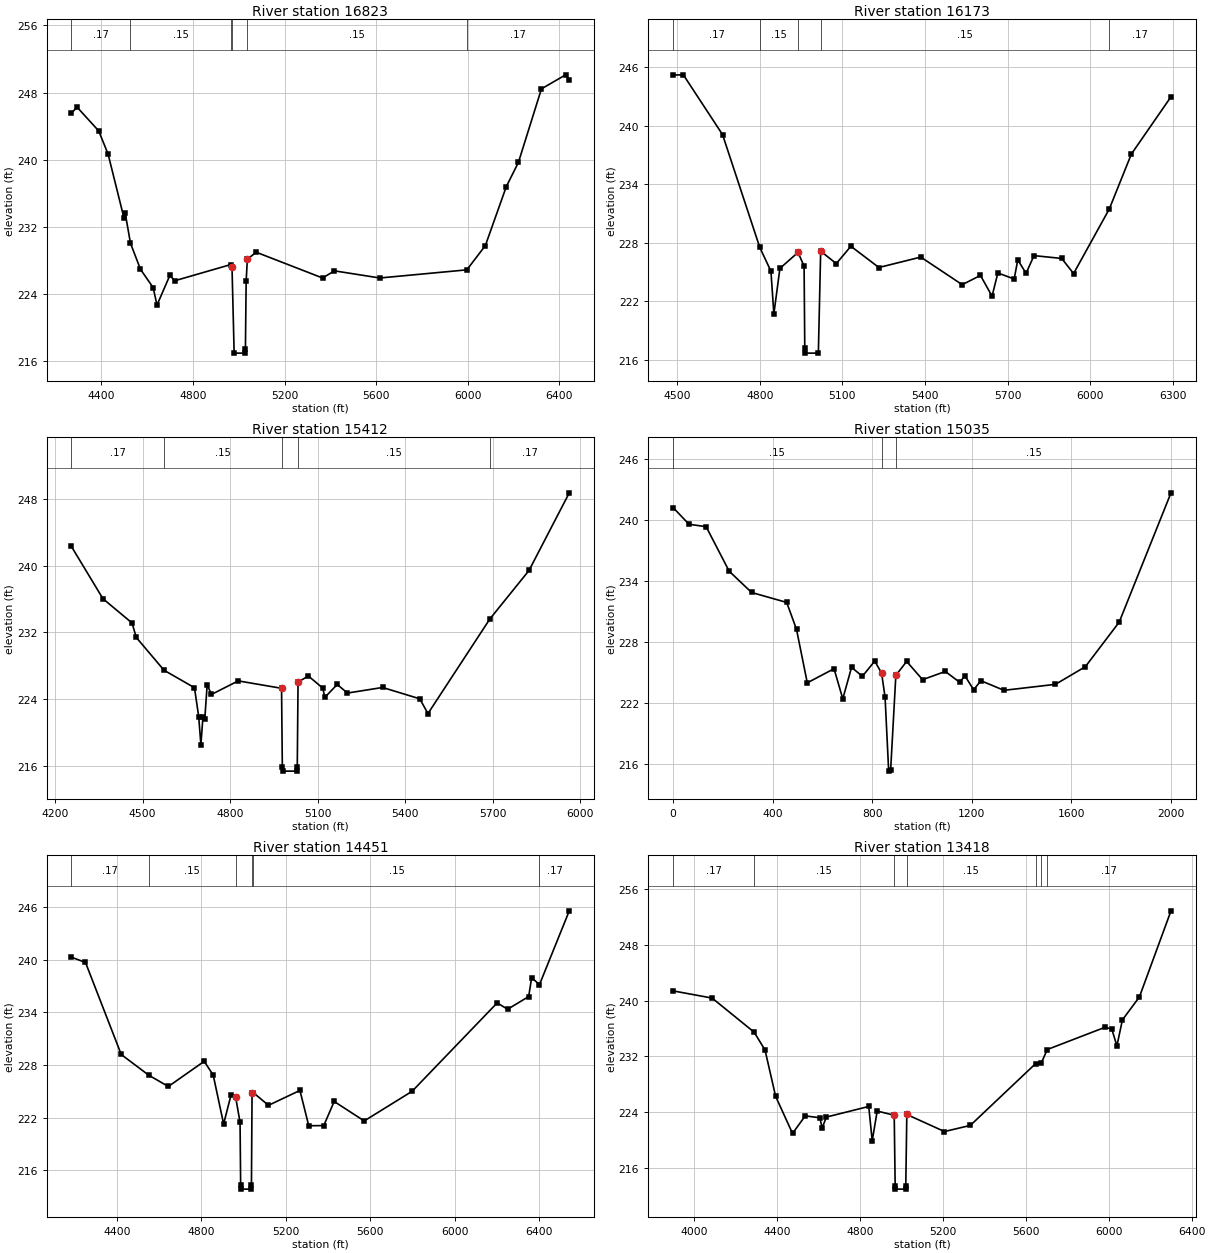
Type RM Length L Ch R = 1 ,16823   ,650,650,650
BEGIN DESCRIPTION:
WEST SANDY CREEK 27.0
END DESCRIPTION:
XS GIS Cut Line= 3
      3759962.27     10207674.34      3759777.36     10207627.46
      3757873.69     10207072.77
#Sta/Elev= 30
  4269.3  245.58  4294.5  246.24  4388.4  243.43  4429.4  240.66  4498.4  233.09
  4503.6  233.71    4527  230.06  4570.6  226.95  4626.2  224.76  4642.8  222.68
  4699.1  226.22  4720.2  225.58  4965.1  227.51  4970.3  227.25  4979.7  216.96
  5027.9  216.96  5028.9  217.46  5032.1  225.51  5037.3  228.15    5076  228.98
  5365.7  225.91  5417.8  226.76  5615.7  225.91  5995.6  226.88  6076.4  229.77
  6167.8  236.79  6220.8  239.68  6321.3  248.44    6427  250.11  6442.9  249.51
#Mann= 6 ,-1 , 0
  4269.3     .17       0    4527     .15       0  4965.1     .12       0
  4970.3     .09       0  5037.3     .15       0  5995.6     .17       0
Bank Sta=4970.3,5037.3
XS Rating Curve= 0 ,0
Exp/Cntr=0.3,0.1

Type RM Length L Ch R = 1 ,16173   ,761,761,761
BEGIN DESCRIPTION:
WEST SANDY CREEK 26.0
END DESCRIPTION:
XS GIS Cut Line= 3
      3760030.58     10207400.77      3759415.38     10207072.77
      3758803.53     10206145.88
#Sta/Elev= 30
  4485.4  245.21  4522.5  245.23  4664.8   239.1  4799.9  227.54  4840.5  225.09
  4851.1   220.7  4873.1  225.38  4938.9  227.02  4960.9  225.61  4963.4  217.19
  4964.4  216.69  5012.7  216.69  5021.1  227.15  5077.8  225.87  5130.9  227.65
  5232.5  225.47  5384.6  226.54  5535.1  223.71  5601.3  224.66  5643.4  222.53
  5664.5  224.91  5723.8  224.29  5736.8  226.26  5766.9  224.87  5795.7  226.69
  5896.3   226.4  5939.5  224.85  6069.1  231.47  6149.2   237.1  6293.2  242.98
#Mann= 5 ,-1 , 0
  4485.4     .17       0  4799.9     .15       0  4938.9     .09       0
  5021.1     .15       0  6069.1     .17       0
Bank Sta=4938.9,5021.1
XS Rating Curve= 0 ,0
Exp/Cntr=0.3,0.1

Type RM Length L Ch R = 1 ,15412   ,377,377,377
BEGIN DESCRIPTION:
WEST SANDY CREEK 25.0
END DESCRIPTION:
XS GIS Cut Line= 3
      3760220.62     10207100.25       3759790.9      10206772.1
      3758947.53     10205966.19
#Sta/Elev= 30
    4256  242.32  4364.1  236.05  4463.8  233.14  4478.4   231.4  4573.4  227.47
  4677.9  225.37  4692.4  221.91  4699.9  218.52    4707  221.88  4713.2   221.6
  4721.5  225.74    4736  224.56    4828  226.19  4976.5   225.3  4979.2  215.86
  4980.2  215.36  5029.4  215.36  5030.4  215.86  5033.1  226.04  5068.3  226.78
    5118  225.32  5124.9  224.21  5167.4  225.76  5202.6  224.73    5323   225.4
  5450.4  224.04  5478.6  222.27    5691  233.63    5825  239.44  5963.2  248.76
#Mann= 5 ,-1 , 0
    4256     .17       0  4573.4     .15       0  4976.5     .09       0
  5033.1     .15       0    5691     .17       0
Bank Sta=4976.5,5033.1
XS Rating Curve= 0 ,0
Exp/Cntr=0.3,0.1

Type RM Length L Ch R = 1 ,15035   ,584,584,584
BEGIN DESCRIPTION:
WEST SANDY CREEK 24.0
END DESCRIPTION:
XS GIS Cut Line= 3
      3760401.41     10207116.46      3760174.49     10206720.48
      3759218.33     10205507.67
#Sta/Elev= 30
       0  241.24    63.8   239.6   132.6  239.36   225.2  234.97   315.3  232.87
   456.4  231.89   495.8  229.23   539.1  223.96   646.6  225.35   681.8  222.38
   717.1  225.49   760.4   224.6   810.1   226.1   837.7  224.93   851.7  222.54
   866.2  215.25   874.2   215.4     895  224.69   938.4  226.07  1002.5  224.27
  1093.8  225.08  1151.6  224.01  1172.4  224.66  1207.7  223.27  1236.6  224.17
  1329.6  223.22  1536.4  223.81  1656.6  225.55  1792.7  229.95  2000.8   242.7
#Mann= 3 , 0 , 0
       0     .15       0   837.7     .09       0     895     .15       0
Bank Sta=837.7,895
XS Rating Curve= 0 ,0
Exp/Cntr=0.3,0.1

Type RM Length L Ch R = 1 ,14451   ,1033,1033,1033
BEGIN DESCRIPTION:
WEST SANDY CREEK 23.0
END DESCRIPTION:
XS GIS Cut Line= 3
      3760777.37     10206913.95      3760645.42     10206535.45
      3759357.22     10205059.75
#Sta/Elev= 30
  4183.9  240.29  4250.5  239.69  4419.9  229.19  4550.2  226.83  4643.2  225.54
  4813.2  228.41  4855.9  226.84  4905.2  221.26  4940.3  224.57  4962.2  224.32
  4983.1  221.45  4985.9  214.33  4986.9  213.83  5036.1  213.83  5037.1  214.33
    5040  224.85  5046.7  224.82  5117.9  223.39  5266.9  225.09  5308.7  221.06
  5379.9  221.08  5429.2  223.83  5571.6  221.61  5798.5  224.99  6201.9  235.08
  6251.3  234.35    6351   235.8  6365.2  237.95  6402.3  237.16  6543.6  245.58
#Mann= 6 ,-1 , 0
  4183.9     .17       0  4550.2     .15       0  4962.2     .09       0
    5040     .12       0  5046.7     .15       0  6402.3     .17       0
Bank Sta=4962.2,5040
XS Rating Curve= 0 ,0
Exp/Cntr=0.3,0.1

Type RM Length L Ch R = 1 ,13418   ,322,322,322
BEGIN DESCRIPTION:
WEST SANDY CREEK 22.0
END DESCRIPTION:
XS GIS Cut Line= 3
      3761055.14     10206865.29      3760742.64     10205334.06
      3760582.91     10204511.11
#Sta/Elev= 30
  3899.3   241.4  4087.3  240.37  4290.4  235.46  4342.5   232.9  4393.5  226.26
  4475.1  220.93  4536.4  223.45  4606.8  223.18    4618  221.72  4638.4  223.28
  4842.6   224.8  4859.4  219.88  4883.4  224.14  4965.5  223.55  4970.1  213.43
  4971.1  212.93  5020.3  212.93  5021.3  213.43  5026.3  223.65  5207.9   221.2
  5332.5  222.08  5647.6  230.96  5674.4  231.01  5703.7  232.98  5982.7  236.18
  6015.2   235.9  6039.5   233.5  6066.1  237.24    6148  240.53  6300.4   252.9
#Mann= 7 ,-1 , 0
  3899.3     .17       0  4290.4     .15       0  4965.5     .09       0
  5026.3     .15       0  5647.6     .17       0  5674.4     .11       0
  5703.7     .17       0
Bank Sta=4965.5,5026.3
XS Rating Curve= 0 ,0
Exp/Cntr=0.3,0.1

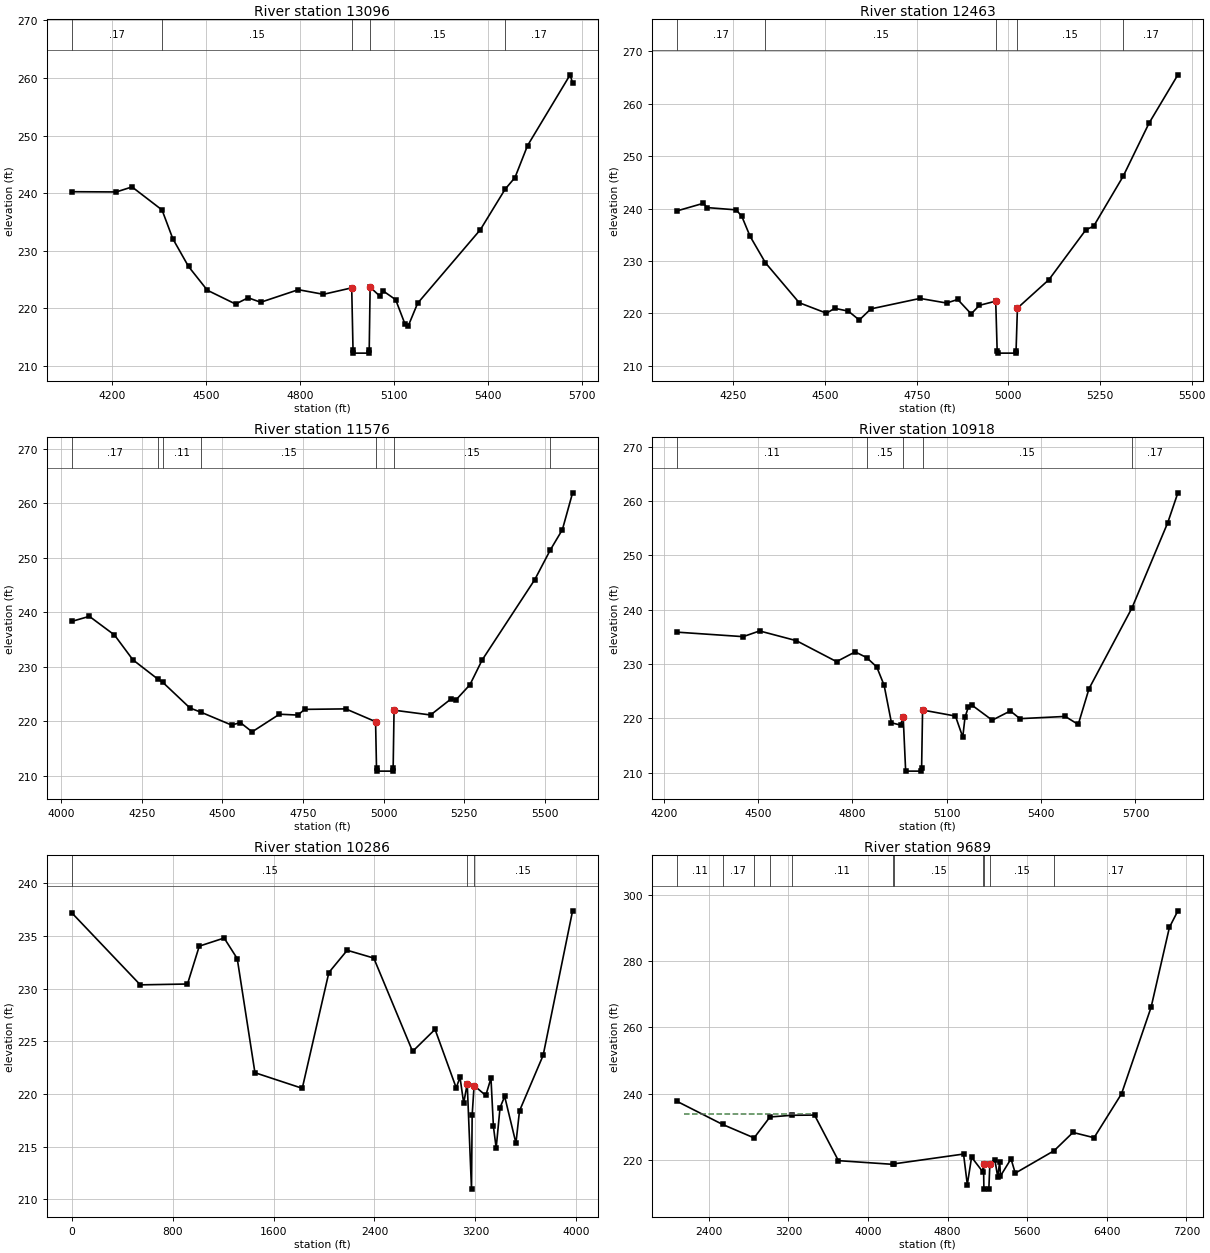
Type RM Length L Ch R = 1 ,13096   ,633,633,633
BEGIN DESCRIPTION:
WEST SANDY CREEK 21.0
END DESCRIPTION:
XS GIS Cut Line= 3
      3761139.58     10206823.61      3761103.75     10205868.78
       3761072.5     10205227.54
#Sta/Elev= 30
  4072.3  240.27  4214.9  240.23    4265   241.1  4360.7   237.1  4395.1   232.1
  4445.1  227.29  4505.1  223.17  4595.2  220.77  4635.2  221.86  4675.3  221.08
  4795.3  223.26  4875.4  222.46  4965.5  223.58  4969.7  212.75  4970.7  212.25
  5020.3  212.25  5021.3  212.75  5024.2   223.7  5055.5  222.13  5065.6  223.05
  5105.6  221.53  5135.6  217.26  5145.7  216.96  5175.7  220.91  5375.9  233.69
  5454.6   240.7  5486.1  242.73  5526.1  248.27  5661.9  260.56  5669.8  259.14
#Mann= 5 ,-1 , 0
  4072.3     .17       0  4360.7     .15       0  4965.5     .09       0
  5024.2     .15       0  5454.6     .17       0
Bank Sta=4965.5,5024.2
XS Rating Curve= 0 ,0
Exp/Cntr=0.3,0.1

Type RM Length L Ch R = 1 ,12463   ,887,887,887
BEGIN DESCRIPTION:
WEST SANDY CREEK 20.0
END DESCRIPTION:
XS GIS Cut Line= 3
      3761194.02     10206795.87       3761599.4     10205987.64
      3761867.88     10205611.04
#Sta/Elev= 30
  4095.8  239.54  4168.3     241  4178.1  240.18  4257.8  239.74  4273.1  238.48
  4295.4  234.72  4337.5  229.64  4429.5  222.04  4503.9  220.04  4526.3  220.97
  4563.5  220.44  4593.4  218.74  4624.9  220.86    4759  222.86  4831.6  221.98
  4861.9  222.66  4898.6  219.91    4921  221.54  4965.6  222.34  4969.5  212.93
  4970.5  212.43  5020.1  212.43  5021.1  212.93  5024.8  221.01  5110.9  226.45
  5211.7  235.96  5232.6  236.61  5313.1  246.13  5383.8  256.27  5462.5  265.49
#Mann= 5 ,-1 , 0
  4095.8     .17       0  4337.5     .15       0  4965.6     .09       0
  5024.8     .15       0  5313.1     .17       0
Bank Sta=4965.6,5024.8
XS Rating Curve= 0 ,0
Exp/Cntr=0.3,0.1

Type RM Length L Ch R = 1 ,11576   ,658,658,658
BEGIN DESCRIPTION:
WEST SANDY CREEK 19.0
END DESCRIPTION:
XS GIS Cut Line= 3
      3761395.44     10206896.54      3762346.81     10206108.36
      3762409.28     10205795.99
#Sta/Elev= 30
  4032.4  238.32  4087.5  239.26  4165.4  235.83  4222.5  231.27  4299.1  227.76
  4315.1  227.14  4399.6  222.41  4434.5  221.62  4528.6  219.28  4555.9  219.73
  4592.4  218.03  4677.1  221.27  4734.4  221.11  4755.2  222.16  4882.8  222.25
  4975.3   219.9  4978.2  211.31  4979.2  210.81  5028.8  210.81  5029.8  211.31
  5032.6  222.01  5145.9  221.13  5209.8   224.1  5224.1  223.87  5267.8  226.67
  5305.9  231.24    5469     246  5517.3  251.46  5554.7  255.19  5586.4  261.96
#Mann= 7 ,-1 , 0
  4032.4     .17       0  4299.1     .15       0  4315.1     .11       0
  4434.5     .15       0  4975.3     .09       0  5032.6     .15       0
  5517.3     .17       0
Bank Sta=4975.3,5032.6
XS Rating Curve= 0 ,0
Exp/Cntr=0.3,0.1

Type RM Length L Ch R = 1 ,10918   ,632,632,632
BEGIN DESCRIPTION:
WEST SANDY CREEK 18.0
END DESCRIPTION:
XS GIS Cut Line= 2
      3762228.76     10207320.16      3762867.85     10205861.09
#Sta/Elev= 30
    4242  235.86  4452.7  235.03    4505  236.08  4621.9  234.29  4749.7  230.43
  4808.7  232.22  4845.1  231.19  4877.5  229.45  4900.9  226.08  4924.2  219.17
  4953.1  218.75  4961.5  220.31  4969.4  210.27  5019.1  210.27  5020.1  210.77
  5023.2  221.52  5127.7  220.41    5151  216.53    5158  220.15    5169  222.13
  5179.9  222.43  5244.6  219.65  5302.2  221.35  5332.7  219.93  5476.8  220.34
  5518.1  218.86  5552.4  225.45  5689.1  240.33  5802.6     256  5834.9  261.51
#Mann= 5 ,-1 , 0
    4242     .11       0  4845.1     .15       0  4961.5     .09       0
  5023.2     .15       0  5689.1     .17       0
Bank Sta=4961.5,5023.2
XS Rating Curve= 0 ,0
Exp/Cntr=0.3,0.1

Type RM Length L Ch R = 1 ,10286   ,597,597,597
XS GIS Cut Line= 4
      3762067.11     10209786.51      3762678.89     10207564.74
      3763100.26     10206816.72      3763287.78     10206031.98
#Sta/Elev= 30
       0   237.2   544.4  230.35   918.4  230.43  1011.7  234.02  1208.8  234.79
  1312.5  232.84  1452.8  222.02  1827.8  220.54  2038.6  231.52  2183.8  233.63
  2394.4  232.89  2702.1  224.04  2879.9  226.13  3047.5  220.59  3077.7  221.58
  3106.8  219.14    3135  220.97  3168.8  210.98    3174  218.01  3189.4   220.8
  3281.9  219.86    3323   221.5  3342.4  216.93  3364.2  214.88    3395  218.71
  3431.6  219.77  3520.9  215.34  3549.2   218.4  3736.5  223.67  3969.8  237.37
#Mann= 3 , 0 , 0
       0     .15       0    3135     .09       0  3189.4     .15       0
#XS Ineff= 1 ,-1
    1235  2183.8  233.63
Permanent Ineff=
       F
Bank Sta=3135,3189.4
XS Rating Curve= 0 ,0
Exp/Cntr=0.3,0.1

Type RM Length L Ch R = 1 ,9689    ,885,885,885
BEGIN DESCRIPTION:
WEST SANDY CREEK 16.0
END DESCRIPTION:
XS GIS Cut Line= 3
      3762199.07     10209828.14      3763464.03     10207195.58
      3765017.89     10205761.04
#Sta/Elev= 30
  2079.3  237.73  2538.1  230.76  2855.4  226.69  3014.8     233  3236.1  233.51
  3462.9  233.57  3702.8  219.84  4248.2  218.73  4262.9  218.88  4960.6  221.83
  4998.4  212.64  5041.4  220.88  5154.8  216.44  5161.6  218.75  5165.1  211.26
  5214.8  211.26  5225.1  218.95    5275  220.18  5303.3  215.06  5324.3  219.44
  5331.7  215.21  5437.7  220.38  5480.3  216.07  5871.5  222.85  6060.3  228.34
  6272.4  226.75  6548.6  239.99  6845.7  266.06    7030  290.15  7114.8  295.11
#Mann= 11 ,-1 , 0
  2079.3     .11       0  2538.1     .17       0  2855.4     .11       0
  3014.8     .17       0  3236.1     .11       0  4248.2     .17       0
  4262.9     .15       0  5154.8     .12       0  5161.6     .09       0
  5225.1     .15       0  5871.5     .17       0
#XS Ineff= 1 ,-1
    2150  3440.7  234.02
Permanent Ineff=
       F
Bank Sta=5161.6,5225.1
XS Rating Curve= 0 ,0
Exp/Cntr=0.3,0.1

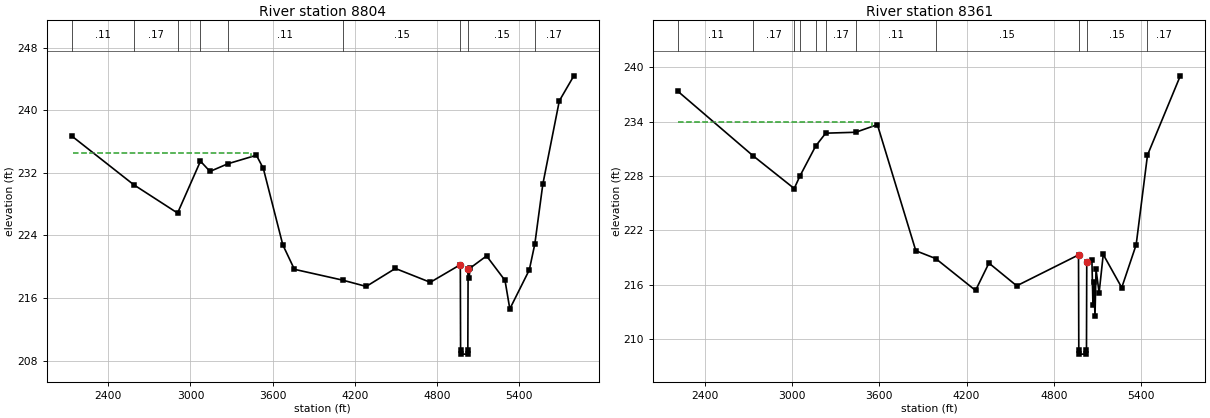
Type RM Length L Ch R = 1 ,8804    ,443,443,443
BEGIN DESCRIPTION:
WEST SANDY CREEK 15.0
END DESCRIPTION:
XS GIS Cut Line= 3
      3762247.69     10209828.14      3762844.89     10208578.17
      3764354.05     10206867.79
#Sta/Elev= 30
  2132.5  236.71    2585  230.48  2905.8  226.85  3072.8  233.48  3142.6  232.17
  3272.8  233.15  3481.3  234.24  3531.9  232.55    3674  222.79  3758.6  219.66
    4110  218.28  4283.2  217.47  4495.7  219.77  4750.8     218    4970  220.25
    4972  209.32  4973.1  208.82  5023.8  208.82  5024.8  209.32  5026.9  219.73
  5034.3  218.54  5041.1  219.81  5161.6  221.37  5296.3  218.24  5331.4   214.6
  5473.6  219.58    5514   222.9  5572.3  230.53  5692.8  241.19  5798.8  244.39
#Mann= 9 ,-1 , 0
  2132.5     .11       0    2585     .17       0  2905.8     .11       0
  3072.8     .17       0  3272.8     .11       0    4110     .15       0
    4970     .09       0  5026.9     .15       0    5514     .17       0
#XS Ineff= 1 ,-1
    2140    3443  234.47
Permanent Ineff=
       F
Bank Sta=4970,5026.9
XS Rating Curve= 0 ,0
Exp/Cntr=0.3,0.1

Type RM Length L Ch R = 1 ,8361    ,539,539,539
BEGIN DESCRIPTION:
WEST SANDY CREEK 14.0
END DESCRIPTION:
XS GIS Cut Line= 3
       3762355.3     10209887.22      3762973.36      10208612.9
      3764438.64     10207203.18
#Sta/Elev= 30
  2218.4  237.32    2732  230.24  3015.9  226.61  3053.6  227.94  3163.4   231.3
  3232.2  232.72  3438.3  232.82  3587.2  233.66  3851.2  219.74  3987.7  218.88
  4261.6  215.36  4353.4  218.38  4544.3  215.87  4968.8  219.28  4970.7  208.83
  4971.8  208.33  5022.5  208.33  5023.5  208.83  5025.4  218.55  5060.7  218.72
  5067.9   213.8  5074.8   216.3    5082   212.5    5089   217.7  5110.3   215.1
  5138.6  219.33  5265.7  215.67  5364.7   220.4  5442.6   230.3    5668  239.05
#Mann= 11 ,-1 , 0
  2218.4     .11       0    2732     .17       0  3015.9     .15       0
  3053.6     .17       0  3163.4     .11       0  3232.2     .17       0
  3438.3     .11       0  3987.7     .15       0  4968.8     .09       0
  5025.4     .15       0  5442.6     .17       0
#XS Ineff= 1 ,-1
    2220  3547.8  233.98
Permanent Ineff=
       F
Bank Sta=4968.8,5025.4
XS Rating Curve= 0 ,0
Exp/Cntr=0.3,0.1