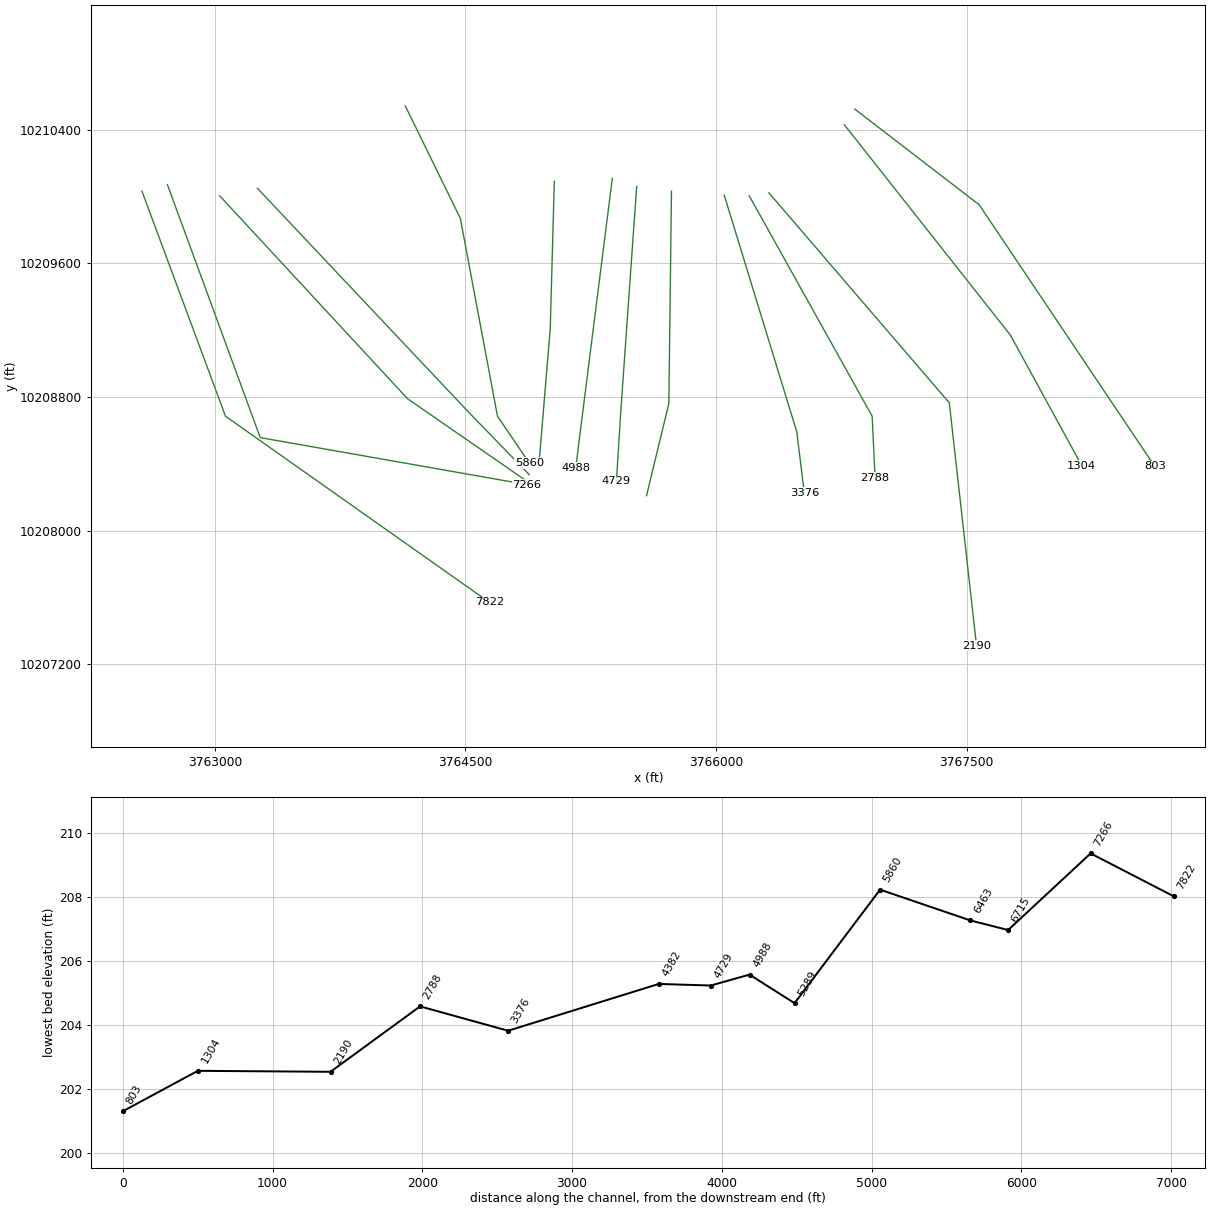
HEC-RAS study WEST SANDY CREEK.prj: WEST SANDY CREEK Base Level Engineering

--- WEST SANDY CREEK.g01 (geometry) --- (continued)

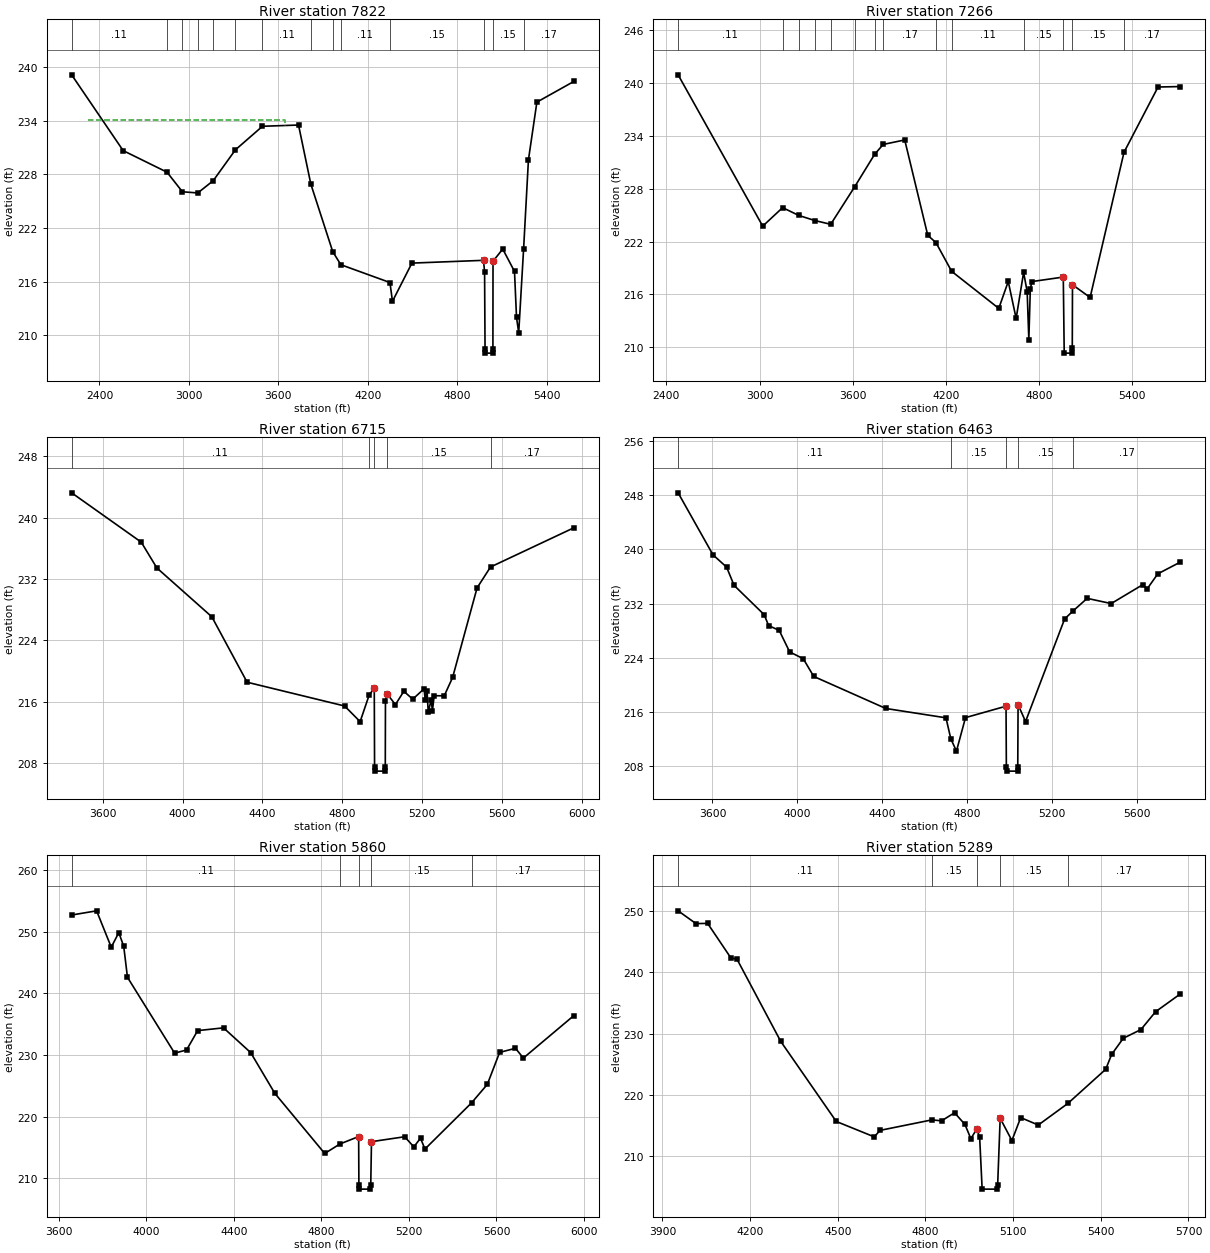
Type RM Length L Ch R = 1 ,7822    ,556,556,556
BEGIN DESCRIPTION:
WEST SANDY CREEK 13.0
END DESCRIPTION:
XS GIS Cut Line= 3
      3762563.64     10210033.03      3763063.85     10208685.54
       3764643.2     10207571.44
#Sta/Elev= 30
  2213.3  239.11    2559  230.64  2853.3  228.23  2956.6  226.04  3059.9  225.91
  3163.3  227.28  3312.3  230.73  3493.8  233.36  3735.8   233.5  3818.4   226.9
  3965.6  219.34  4019.9  217.89  4349.3   215.9  4366.2   213.8  4496.8  218.07
  4977.2  218.38  4984.4  217.08  4987.5  208.51  4988.6  208.01  5039.3  208.01
  5040.3  208.51    5041  218.28  5106.3  219.64  5185.2  217.14  5198.7     212
  5213.4  210.29  5246.2  219.63  5278.7  229.61  5335.4  236.06  5583.4  238.37
#Mann= 14 ,-1 , 0
  2213.3     .11       0  2853.3     .15       0  2956.6     .11       0
  3059.9     .17       0  3163.3     .11       0  3312.3     .17       0
  3493.8     .11       0  3818.4     .17       0  3965.6     .15       0
  4019.9     .11       0  4349.3     .15       0  4977.2     .09       0
    5041     .15       0  5246.2     .17       0
#XS Ineff= 1 ,-1
    2320  3643.6  234.03
Permanent Ineff=
       F
Bank Sta=4977.2,5041
XS Rating Curve= 0 ,0
Exp/Cntr=0.3,0.1

Type RM Length L Ch R = 1 ,7266    ,551,551,551
BEGIN DESCRIPTION:
WEST SANDY CREEK 12.0
END DESCRIPTION:
XS GIS Cut Line= 3
      3762716.42     10210071.22      3763271.97     10208557.34
      3764869.21     10208276.09
#Sta/Elev= 30
  2475.7  240.89  3020.6  223.74  3148.8  225.84    3252  224.96  3355.3  224.38
  3458.5  223.95  3613.9  228.23  3741.3  231.88  3796.4     233  3935.2  233.51
  4083.6   222.7  4136.5  221.87  4237.4  218.62    4541  214.42    4602  217.47
  4652.7  213.28    4701   218.5  4723.8   216.3  4734.5  210.88  4744.1  216.64
  4754.3  217.46  4956.4  217.97  4962.4  209.35  5013.2  209.35  5014.3  209.95
  5015.7   217.1  5129.2  215.66  5347.5  232.11  5566.6  239.51  5710.1  239.56
#Mann= 14 ,-1 , 0
  2475.7     .11       0  3148.8     .15       0    3252     .11       0
  3355.3     .17       0  3458.5     .11       0  3613.9     .17       0
  3741.3     .11       0  3796.4     .17       0  4136.5     .15       0
  4237.4     .11       0    4701     .15       0  4956.4     .09       0
  5015.7     .15       0  5347.5     .17       0
#XS Ineff= 1 ,-1
    2650  3935.2  233.51
Permanent Ineff=
       F
Bank Sta=4956.4,5015.7
XS Rating Curve= 0 ,0
Exp/Cntr=0.3,0.1

Type RM Length L Ch R = 1 ,6715    ,252,252,252
BEGIN DESCRIPTION:
WEST SANDY CREEK 11.0
END DESCRIPTION:
XS GIS Cut Line= 3
       3763028.9     10210005.28      3764153.92     10208789.98
      3764862.21     10208300.42
#Sta/Elev= 30
  3443.9  243.24  3792.7  236.81  3870.9  233.45  4146.5  227.08  4323.4  218.55
  4812.1  215.45  4889.8  213.41  4934.5  216.83  4960.7  217.81  4962.2  207.56
  4963.3  206.96  5014.8  206.96  5015.9  207.56  5016.8  216.06  5024.2  217.06
  5066.7  215.63  5108.9  217.37  5153.4  216.34  5210.2  217.69  5216.3  216.22
  5225.1  217.46  5231.2  214.61  5246.1  216.29  5252.1  214.81  5260.9  216.79
  5311.4  216.78  5353.5  219.18  5475.9  230.84  5543.3  233.57    5961  238.68
#Mann= 5 ,-1 , 0
  3443.9     .11       0  4934.5     .15       0  4960.7     .09       0
  5024.2     .15       0  5543.3     .17       0
Bank Sta=4960.7,5024.2
XS Rating Curve= 0 ,0
Exp/Cntr=0.3,0.1

Type RM Length L Ch R = 1 ,6463    ,603,603,603
BEGIN DESCRIPTION:
WEST SANDY CREEK 10.0
END DESCRIPTION:
XS GIS Cut Line= 3
      3763254.61      10210050.4      3764517.85     10208711.07
      3764882.51     10208335.71
#Sta/Elev= 30
  3438.3  248.35  3602.6  239.19  3666.6  237.38  3701.7  234.69  3843.4  230.36
  3864.4  228.75  3914.2  228.04  3963.5  224.86  4027.4  223.86  4076.8  221.24
  4416.2  216.51  4699.4  215.13  4722.4  212.01  4748.8  210.22  4791.3  215.16
  4982.2  216.85  4983.7  207.86  4984.8  207.26  5036.3  207.26  5037.4  207.86
  5038.9  217.08  5074.1  214.58  5258.1  229.73  5298.8  230.94  5364.2  232.77
  5477.3     232    5626  234.79  5647.1  234.19  5696.7  236.39  5802.7  238.12
#Mann= 5 ,-1 , 0
  3438.3     .11       0  4722.4     .15       0  4982.2     .09       0
  5038.9     .15       0  5298.8     .17       0
Bank Sta=4982.2,5038.9
XS Rating Curve= 0 ,0
Exp/Cntr=0.3,0.1

Type RM Length L Ch R = 1 ,5860    ,571,571,571
BEGIN DESCRIPTION:
Mapping XS bd6e4e9f
END DESCRIPTION:
XS GIS Cut Line= 4
      3764140.03     10210543.45      3764469.89     10209869.84
      3764692.11     10208685.81      3764882.47     10208405.47
#Sta/Elev= 30
  3659.9  252.75  3773.9  253.43  3840.7  247.52  3875.3  249.89  3897.8  247.65
  3914.8  242.63  4130.2  230.31  4184.8  230.83  4235.4  233.97  4353.5  234.42
  4477.5   230.4  4587.7  223.79  4815.7  214.01    4885  215.55  4970.7  216.76
  4971.8  208.82  4972.9  208.22  5024.7  208.22  5025.9  208.82  5029.3  215.93
  5180.9  216.73  5222.7  215.08  5253.2  216.49  5273.5  214.73  5486.5  222.24
  5558.4  225.24  5614.5  230.43    5687   231.1  5722.9  229.51  5953.5  236.41
#Mann= 5 ,-1 , 0
  3659.9     .11       0    4885     .15       0  4970.7     .09       0
  5029.3     .15       0  5486.5     .17       0
Bank Sta=4970.7,5029.3
XS Rating Curve= 0 ,0
Exp/Cntr=0.3,0.1

Type RM Length L Ch R = 1 ,5289    ,301,301,301
BEGIN DESCRIPTION:
WEST SANDY CREEK 9.0
END DESCRIPTION:
XS GIS Cut Line= 3
      3765032.39     10210092.04      3765008.08     10209210.12
      3764938.64     10208376.76
#Sta/Elev= 30
  3953.6  250.05  4014.6  247.97  4054.6     248  4134.6  242.34  4154.6  242.21
  4304.7  228.77  4494.8  215.71  4624.8   213.2  4644.8  214.26  4822.2  215.97
    4855  215.81  4899.5  217.13  4935.2  215.22  4955.3  212.91  4975.4  214.46
  4985.4  213.18    4994  204.68  5045.8  204.68    5047  205.28  5055.7  216.23
  5095.8   212.6  5125.9  216.34  5186.1  215.13  5287.3  218.65  5416.9  224.22
    5437  226.63  5477.1  229.28  5537.3  230.69  5587.5   233.6  5672.1   236.5
#Mann= 5 ,-1 , 0
  3953.6     .11       0  4822.2     .15       0  4975.4     .09       0
  5055.7     .15       0  5287.3     .17       0
Bank Sta=4975.4,5055.7
XS Rating Curve= 0 ,0
Exp/Cntr=0.3,0.1

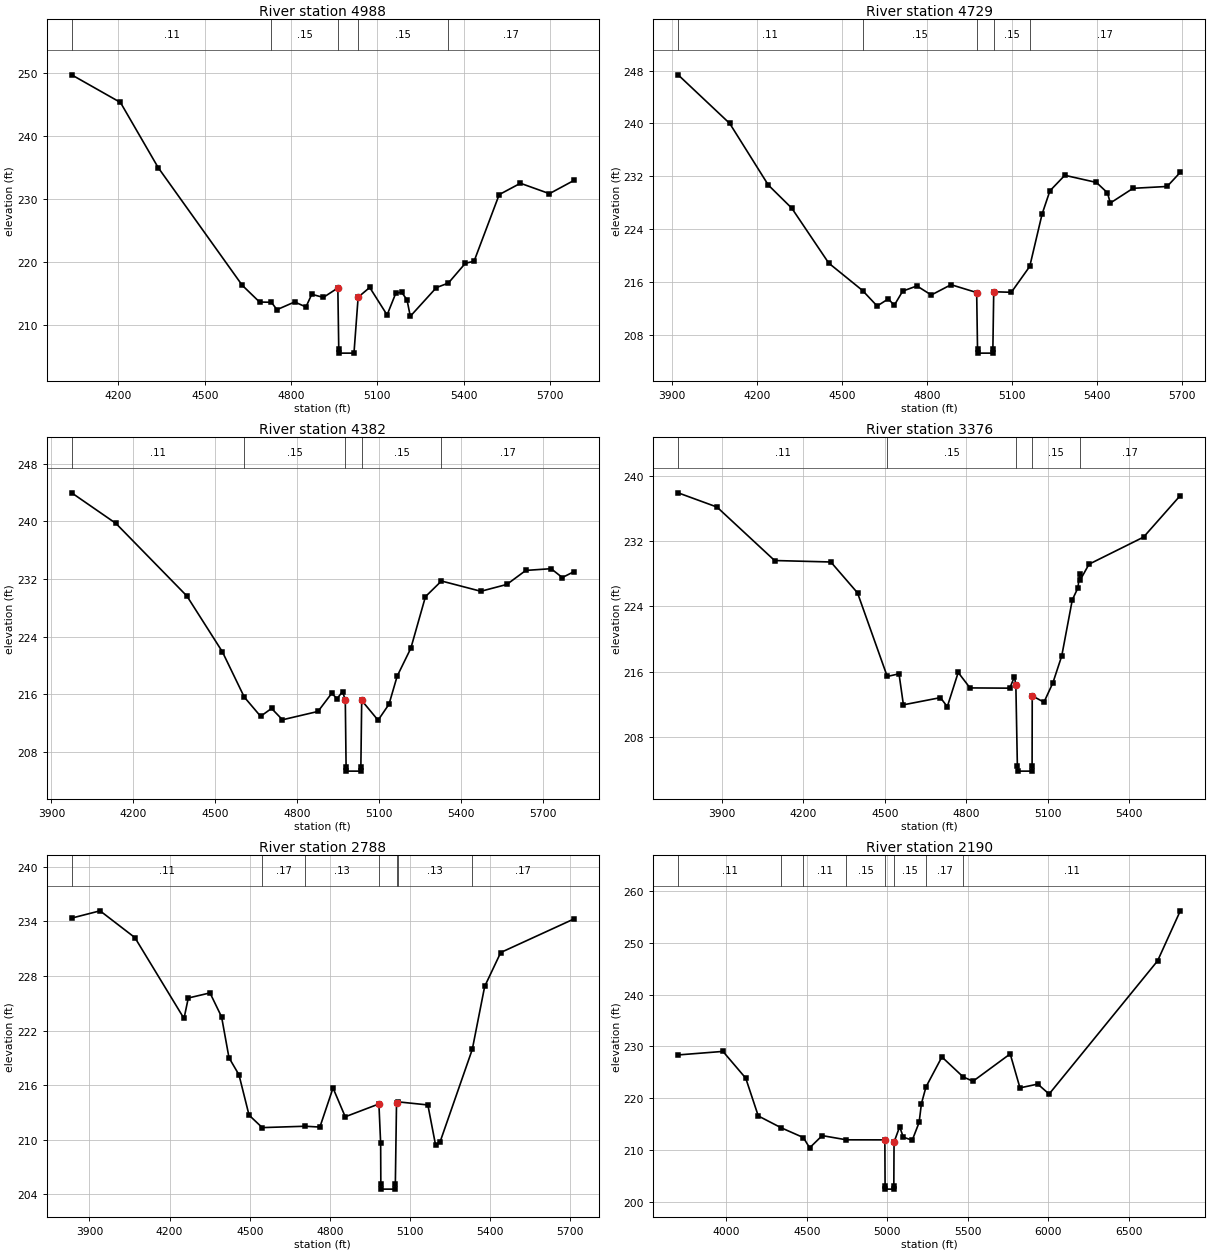
Type RM Length L Ch R = 1 ,4988    ,259,259,259
BEGIN DESCRIPTION:
WEST SANDY CREEK 8.0
END DESCRIPTION:
XS GIS Cut Line= 3
      3765379.61     10210109.45      3765192.11     10208626.79
      3765160.86     10208376.81
#Sta/Elev= 30
  4037.3  249.69    4207  245.31  4338.1  234.99  4630.4  216.33  4690.8  213.67
  4731.9  213.63  4751.3  212.46  4812.7  213.68  4852.1  212.89  4872.3   214.9
  4912.6   214.4    4963   215.9  4966.2  206.17  4967.3  205.57  5019.1  205.57
  5033.6  214.44  5073.9  215.98  5134.3  211.62  5164.6  215.08  5184.7  215.23
  5203.5  214.02    5215  211.41  5305.7  215.96  5347.2  216.67  5406.5  219.82
  5436.7  220.13  5524.1   230.7    5598   232.5  5698.8  230.85  5783.7  232.94
#Mann= 5 ,-1 , 0
  4037.3     .11       0  4731.9     .15       0    4963     .09       0
  5033.6     .15       0  5347.2     .17       0
Bank Sta=4963,5033.6
XS Rating Curve= 0 ,0
Exp/Cntr=0.3,0.1

Type RM Length L Ch R = 1 ,4729    ,347,347,347
BEGIN DESCRIPTION:
WEST SANDY CREEK 7.0
END DESCRIPTION:
XS GIS Cut Line= 3
      3765525.44     10210060.81      3765431.69     10208734.42
        3765404.     10208294.79
#Sta/Elev= 30
  3922.9  247.36  4104.8     240  4240.9  230.67  4323.6  227.17    4454  218.85
  4573.3   214.7  4624.4  212.36  4664.2  213.45  4684.5  212.45  4714.6  214.62
  4764.7   215.4  4815.3  214.03    4885  215.59  4975.3   214.4  4978.3  205.83
  4979.4  205.23  5031.2  205.23  5032.4  205.83  5035.4  214.52  5097.5  214.44
  5162.4  218.36  5205.8  226.27  5233.5   229.8    5286  232.15  5397.3  231.07
  5436.3   229.5  5446.3  227.95  5526.5  230.18  5646.7  230.46  5693.1   232.6
#Mann= 5 ,-1 , 0
  3922.9     .11       0  4573.3     .15       0  4975.3     .09       0
  5035.4     .15       0  5162.4     .17       0
Bank Sta=4975.3,5035.4
XS Rating Curve= 0 ,0
Exp/Cntr=0.3,0.1

Type RM Length L Ch R = 1 ,4382    ,1006,1006,1006
BEGIN DESCRIPTION:
WEST SANDY CREEK 6.0
END DESCRIPTION:
XS GIS Cut Line= 3
      3765733.78     10210033.06      3765718.04     10208761.75
      3765584.47      10208210.1
#Sta/Elev= 30
  3973.8  243.98  4135.8  239.73  4395.8  229.63  4525.8  221.87  4605.9  215.58
  4665.8   212.9  4705.8     214  4745.9  212.42  4875.9  213.58  4925.9  216.09
  4945.9  215.37  4965.9  216.35  4975.9  215.16  4978.8  205.88    4980  205.28
  5031.8  205.28  5032.9  205.88  5035.9  215.11  5095.9  212.36  5135.9  214.58
  5165.9  218.49  5215.9  222.37  5269.4  229.54    5328  231.72  5472.3  230.29
  5567.4  231.24  5636.9  233.19  5729.5  233.43  5770.6   232.2  5812.8  233.01
#Mann= 5 ,-1 , 0
  3973.8     .11       0  4605.9     .15       0  4975.9     .09       0
  5035.9     .15       0    5328     .17       0
Bank Sta=4975.9,5035.9
XS Rating Curve= 0 ,0
Exp/Cntr=0.3,0.1

Type RM Length L Ch R = 1 ,3376    ,588,588,588
BEGIN DESCRIPTION:
WEST SANDY CREEK 5.0
END DESCRIPTION:
XS GIS Cut Line= 3
      3766049.75     10210008.74      3766483.78     10208592.06
      3766528.91     10208227.52
#Sta/Elev= 30
  3738.6   237.9  3881.6  236.16  4093.8  229.61  4300.9  229.43  4399.1  225.65
  4508.6  215.41  4551.9  215.74  4568.1  211.94  4704.3  212.82  4729.7  211.71
  4769.8   215.9  4813.4  214.01  4959.8  213.98  4976.8  215.37  4982.1  214.39
  4987.7  204.42  4988.9  203.82  5040.8  203.82  5041.9  204.42  5042.4  213.04
  5085.6  212.26  5118.3  214.62  5151.1  217.93  5189.9  224.79  5210.9  226.28
  5216.6  228.01  5219.6  227.26  5251.5  229.16  5452.4  232.48  5587.6  237.57
#Mann= 5 ,-1 , 0
  3738.6     .11       0  4508.6     .15       0  4982.1     .09       0
  5042.4     .15       0  5219.6     .17       0
Bank Sta=4982.1,5042.4
XS Rating Curve= 0 ,0
Exp/Cntr=0.3,0.1

Type RM Length L Ch R = 1 ,2788    ,598,598,598
BEGIN DESCRIPTION:
WEST SANDY CREEK 4.0
END DESCRIPTION:
XS GIS Cut Line= 3
      3766199.05     10210005.27      3766935.17     10208685.81
      3766952.53     10208317.73
#Sta/Elev= 30
  3833.7  234.36    3940  235.16  4070.3  232.22  4254.2  223.33  4270.2  225.58
  4351.4  226.14  4394.8  223.51  4422.5  219.02  4459.9  217.14  4497.6  212.71
    4547  211.34  4707.4  211.49  4762.7   211.4  4811.9  215.69  4857.6  212.53
  4983.6  213.94  4990.1   209.6  4990.8  205.18    4992  204.58    5044  204.58
  5045.1  205.18  5049.5  214.07  5055.3  214.17  5166.8  213.83  5195.8   209.4
  5211.8  209.71    5333  219.93  5379.4  226.85  5439.5  230.58  5713.1  234.26
#Mann= 7 ,-1 , 0
  3833.7     .11       0    4547     .17       0  4707.4     .13       0
  4983.6     .09       0  5049.5     .12       0  5055.3     .13       0
    5333     .17       0
Bank Sta=4983.6,5049.5
XS Rating Curve= 0 ,0
Exp/Cntr=0.3,0.1

Type RM Length L Ch R = 1 ,2190    ,886,886,886
BEGIN DESCRIPTION:
WEST SANDY CREEK 3.0
END DESCRIPTION:
XS GIS Cut Line= 3
      3766317.13      10210022.6      3767396.97     10208765.67
      3767560.17     10207310.78
#Sta/Elev= 30
  3700.7  228.37  3979.3  229.05  4120.9   223.9  4198.8  216.63  4341.8  214.34
  4478.9  212.47  4518.2  210.49  4596.1  212.84    4747  212.03  4985.6  212.02
    4987  203.14  4988.2  202.54  5040.2  202.54  5041.3  203.14  5042.7  211.59
  5077.8  214.56  5099.8  212.55  5155.7  211.95  5198.5  215.38  5212.8  218.99
  5241.3  222.22  5340.1  227.98  5472.2  224.14  5533.5  223.31  5764.6  228.57
  5825.3  222.03    5936  222.76  6006.4  220.84  6680.6  246.48  6821.8  256.11
#Mann= 8 ,-1 , 0
  3700.7     .11       0  4341.8     .17       0  4478.9     .11       0
    4747     .15       0  4985.6     .09       0  5042.7     .15       0
  5241.3     .17       0  5472.2     .11       0
Bank Sta=4985.6,5042.7
XS Rating Curve= 0 ,0
Exp/Cntr=0.3,0.1

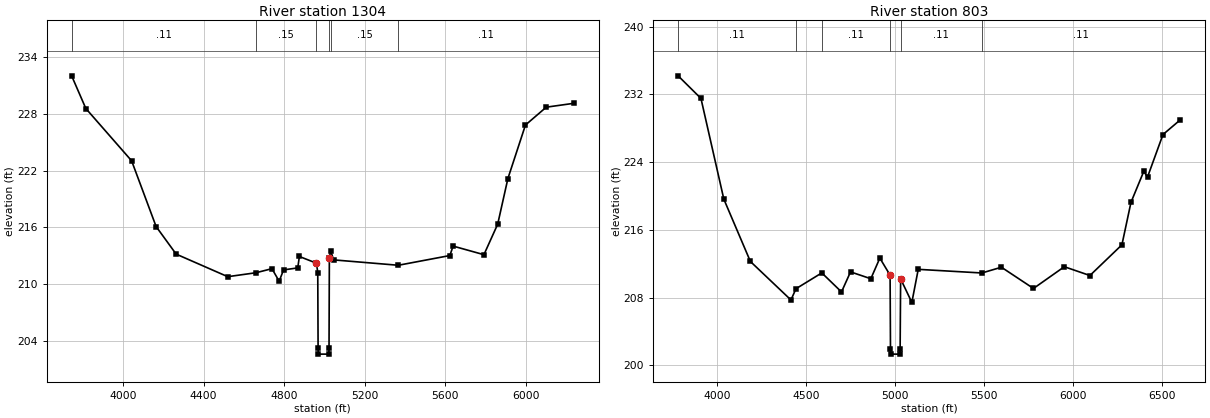
Type RM Length L Ch R = 1 ,1304    ,501,501,501
BEGIN DESCRIPTION:
WEST SANDY CREEK 2.0
END DESCRIPTION:
XS GIS Cut Line= 3
      3766768.52     10210430.58      3767763.29     10209170.19
      3768190.36     10208388.97
#Sta/Elev= 30
  3743.8  232.04  3814.3  228.58  4041.9  223.04  4163.6  216.08  4263.2  213.16
  4519.7  210.77  4660.4  211.19  4739.3  211.62  4775.1  210.29  4797.1  211.49
  4867.6   211.7  4875.6  212.91  4960.6   212.2    4967  211.21  4968.7  203.17
  4969.8  202.57  5021.8  202.57    5023  203.17  5024.7   212.8  5031.1  213.54
  5045.5  212.55  5367.4  211.98  5623.6  213.01  5639.7  214.01  5792.9   213.1
  5861.3  216.33    5912  221.16  5999.3  226.83  6102.7  228.72  6239.8  229.13
#Mann= 6 ,-1 , 0
  3743.8     .11       0  4660.4     .15       0  4960.6     .09       0
  5024.7     .12       0  5031.1     .15       0  5367.4     .11       0
Bank Sta=4960.6,5024.7
XS Rating Curve= 0 ,0
Exp/Cntr=0.3,0.1

Type RM Length L Ch R = 1 ,803     ,0,0,0
BEGIN DESCRIPTION:
WEST SANDY CREEK 1.0
END DESCRIPTION:
XS GIS Cut Line= 3
      3766830.98     10210524.37      3767575.79     10209951.44
       3768627.1     10208384.89
#Sta/Elev= 30
  3778.9   234.2  3907.4  231.53  4036.1  219.63  4185.6  212.26  4413.9  207.71
  4442.3  209.04  4587.6  210.91  4698.4  208.66  4749.2  211.03  4863.5  210.22
  4914.2  212.66  4971.9  210.64  4974.1  201.91  4975.2  201.31  5027.2  201.31
  5028.4  201.91  5031.2   210.2  5094.3  207.42  5130.3  211.33  5488.4   210.9
  5598.4  211.58  5778.8  209.07  5952.5  211.64  6096.5   210.6  6276.6  214.23
  6327.6  219.25  6399.6  222.91  6420.6  222.23  6507.6  227.26  6605.2     229
#Mann= 6 ,-1 , 0
  3778.9     .11       0  4442.3     .15       0  4587.6     .11       0
  4971.9     .07       0  5031.2     .11       0  5488.4     .11       0
Bank Sta=4971.9,5031.2
XS Rating Curve= 0 ,0
Exp/Cntr=0.3,0.1
Stream Node=WEST SANDY CREEK,Reach-1         , 0 , 0 ,Upstream end
Stream Node=WEST SANDY CREEK,Reach-1         , 0 , 1 ,Downstream end

Chan Stop Cuts=-1
Use User Specified Reach Order=0
Composite Channel Slope=5