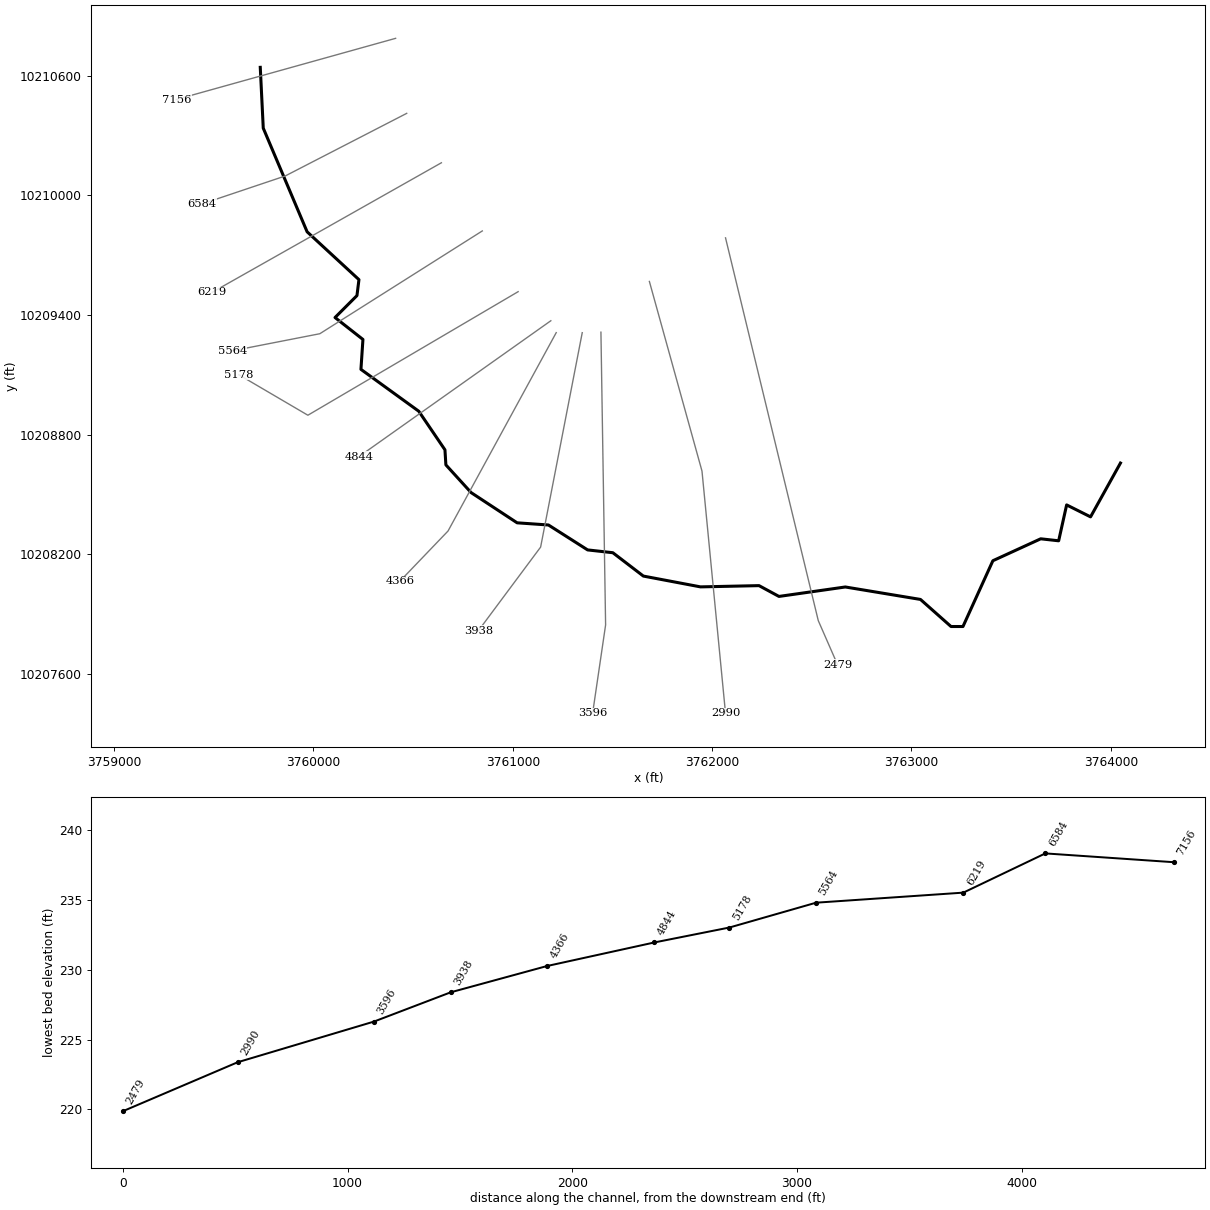
--- WFSJR 001.prj (project) ---

Proj Title=WFSJR 001 Base Level Engineering
Current Plan=p01
Default Exp/Contr=0.3,0.1
English Units
Geom File=g01
Flow File=f01
Plan File=p01
Y Axis Title=Elevation
X Axis Title(PF)=Main Channel Distance
X Axis Title(XS)=Station
BEGIN DESCRIPTION:
WFSJR 001
END DESCRIPTION:
DSS Export Rating Curves= 0
DSS Export Rating Curve Sorted= 0
DSS Export Volume Flow Curves= 0
DXF OffsetX= 0
DXF OffsetY= 0
DXF ScaleX= 1
DXF ScaleY= 10

--- WFSJR 001.p01 (plan) ---

Plan Title=Multiple Run
Program Version=4.10
Short Identifier=Multiple
Geom File=g01
Flow File=f01
Subcritical Flow
K Sum by GR= 0
Std Step Tol= 0.01
Critical Tol= 0.01
Num of Std Step Trials= 20
Max Error Tol= 0.3
Flow Tol Ratio= 0.001
Split Flow NTrial= 30
Split Flow Tol= 0.02
Split Flow Ratio= 0.02
Log Output Level= 0
Friction Slope Method= 1
Unsteady Friction Slope Method= 2
Unsteady Bridges Friction Slope Method= 1
Parabolic Critical Depth
Global Vel Dist= 1 , 1 , 1
Global Log Level= 0
CheckData=True
Encroach Param=-1 ,0,0, 0
BEGIN DESCRIPTION:
Multiple Run
END DESCRIPTION:
Computation Interval=1HOUR
Output Interval=1HOUR
Run HTab= 0
Run UNet= 0
Run PostProcess= 0
Run WQNet= 0
UNET Theta= 1
UNET Theta Warmup= 1
UNET ZTol= 0.02
UNET ZSATol= 0.05
UNET MxIter= 20
UNET MaxInSteps= 0
UNET DtIC= 0
UNET DtMin= 0
UNET MaxCRTS= 20
UNET WFStab= 2
UNET SFStab= 1
UNET WFX= 1
UNET SFX= 1
UNET DSS MLevel= 4
UNET DZMax Abort= 100
UNET Convert EG Bridges= 0
UNET Use Existing IB Tables=-1
UNET Froude Reduction=False
UNET Froude Limit= 1
UNET Froude Power= 10
UNET Time Slicing=0,0, 5
UNET Junction Losses=0
Instantaneous Interval=1HOUR
Write IC File= 0
Write IC File at Sim End=0
Echo Input=False
Echo Parameters=False
Echo Output=False
Write Detailed= 0
WQ AD Non Conservative
WQ ULTIMATE=-1
WQ Max Comp Step=1HOUR
WQ Output Interval=15MIN
WQ Output Selected Increments= 0
WQ Output face flow=0
WQ Output face velocity=0
WQ Output face area=0
WQ Output face dispersion=0
WQ Output cell volume=0
WQ Output cell surface area=0
WQ Output cell continuity=0
WQ Output cumulative cell continuity=0
WQ Output face conc=0
WQ Output face dconc_dx=0
WQ Output face courant=0
WQ Output face peclet=0
WQ Output face adv mass=0
WQ Output face disp mass=0
WQ Output cell mass=0
WQ Output cell source sink temp=0
WQ Output cell source sink nsm=0
WQ Output MaxMinRange=-1
WQ Daily Max Min Mean=-1
WQ Daily Range=0
WQ Daily Time=0
WQ Create Restart=0
WQ Fixed Restart=0
WQ System Summary=0
WQ Use Fixed Temperature=0
Sorting and Armoring Iterations= 10
XS Update Threshold= 0.02
Hydraulics Update Threshold= 0.02
Energy Slope Method= 1
Volume Change Method= 0
XS Weighting Method= 0
Number of US Weighted Cross Sections= 1
Number of DS Weighted Cross Sections= 1
Upstream XS Weight=0.25
Main XS Weight=0.5
Downstream XS Weight=0.25
Number of DS XS's Weighted with US Boundary= 1
Upstream Boundary Weight= 1
Weight of XSs Associated with US Boundary= 0
Number of US XS's Weighted with DS Boundary= 1
Downstream Boundary Weight= 0.5
Weight of XSs Associated with DS Boundary= 0.5
Sediment Output Level= 4
Mass or Volume Output= 0
Output Increment Type= 1
Profile and TS Output Increment= 10
XS Output Flag= 0
XS Output Increment= 10
Disregard all LS=0
Disregard all Conn=0
Disregard all Breaches=0
Disregard all Pumps=0

--- WFSJR 001.f01 (steady flow) ---

Flow Title=Multiple
Program Version=4.10
Number of Profiles= 7
Profile Names=10-year,25-year,50-year,1pct_min,100-year,1pct_plu,500-year
River Rch & RM=WFSJR 001,Reach-1         ,7156
     696     946    1281     571    1724    5206    3228
Boundary for River Rch & Prof#=WFSJR 001,Reach-1         , 1
Up Type= 0
Dn Type= 3
Dn Slope=0.007
Boundary for River Rch & Prof#=WFSJR 001,Reach-1         , 2
Up Type= 0
Dn Type= 3
Dn Slope=0.007
Boundary for River Rch & Prof#=WFSJR 001,Reach-1         , 3
Up Type= 0
Dn Type= 3
Dn Slope=0.007
Boundary for River Rch & Prof#=WFSJR 001,Reach-1         , 4
Up Type= 0
Dn Type= 3
Dn Slope=0.007
Boundary for River Rch & Prof#=WFSJR 001,Reach-1         , 5
Up Type= 0
Dn Type= 3
Dn Slope=0.007
Boundary for River Rch & Prof#=WFSJR 001,Reach-1         , 6
Up Type= 0
Dn Type= 3
Dn Slope=0.007
Boundary for River Rch & Prof#=WFSJR 001,Reach-1         , 7
Up Type= 0
Dn Type= 3
Dn Slope=0.007
DSS Import GetInterval= 0
DSS Import GetPeak= 0
DSS Import FillOption= 0

--- WFSJR 001.g01 (geometry) ---

Geom Title=Existing Conditions
Program Version=4.10

River Reach=WFSJR 001       ,Reach-1
Reach XY= 30
      3759733.23     10210641.84      3759748.23     10210336.84
      3759968.23     10209816.84      3760228.23     10209576.84
      3760218.23     10209496.84      3760108.23     10209386.84
      3760248.23     10209276.84      3760238.23     10209126.84
      3760528.23     10208916.84      3760659.65     10208723.19
      3760664.34     10208647.67       3760790.9     10208508.61
      3761021.63     10208357.04      3761178.92     10208346.11
      3761375.27     10208221.11      3761501.83     10208207.04
      3761654.96     10208089.86      3761941.42     10208035.69
      3762235.17     10208041.94      3762335.17     10207987.77
      3762667.98     10208035.17      3763045.06     10207972.67
      3763198.23     10207836.84      3763258.23     10207836.84
      3763408.23     10208166.84      3763648.23     10208276.84
      3763738.23     10208266.84      3763778.23     10208446.84
      3763898.23     10208386.84      3764048.23     10208656.84

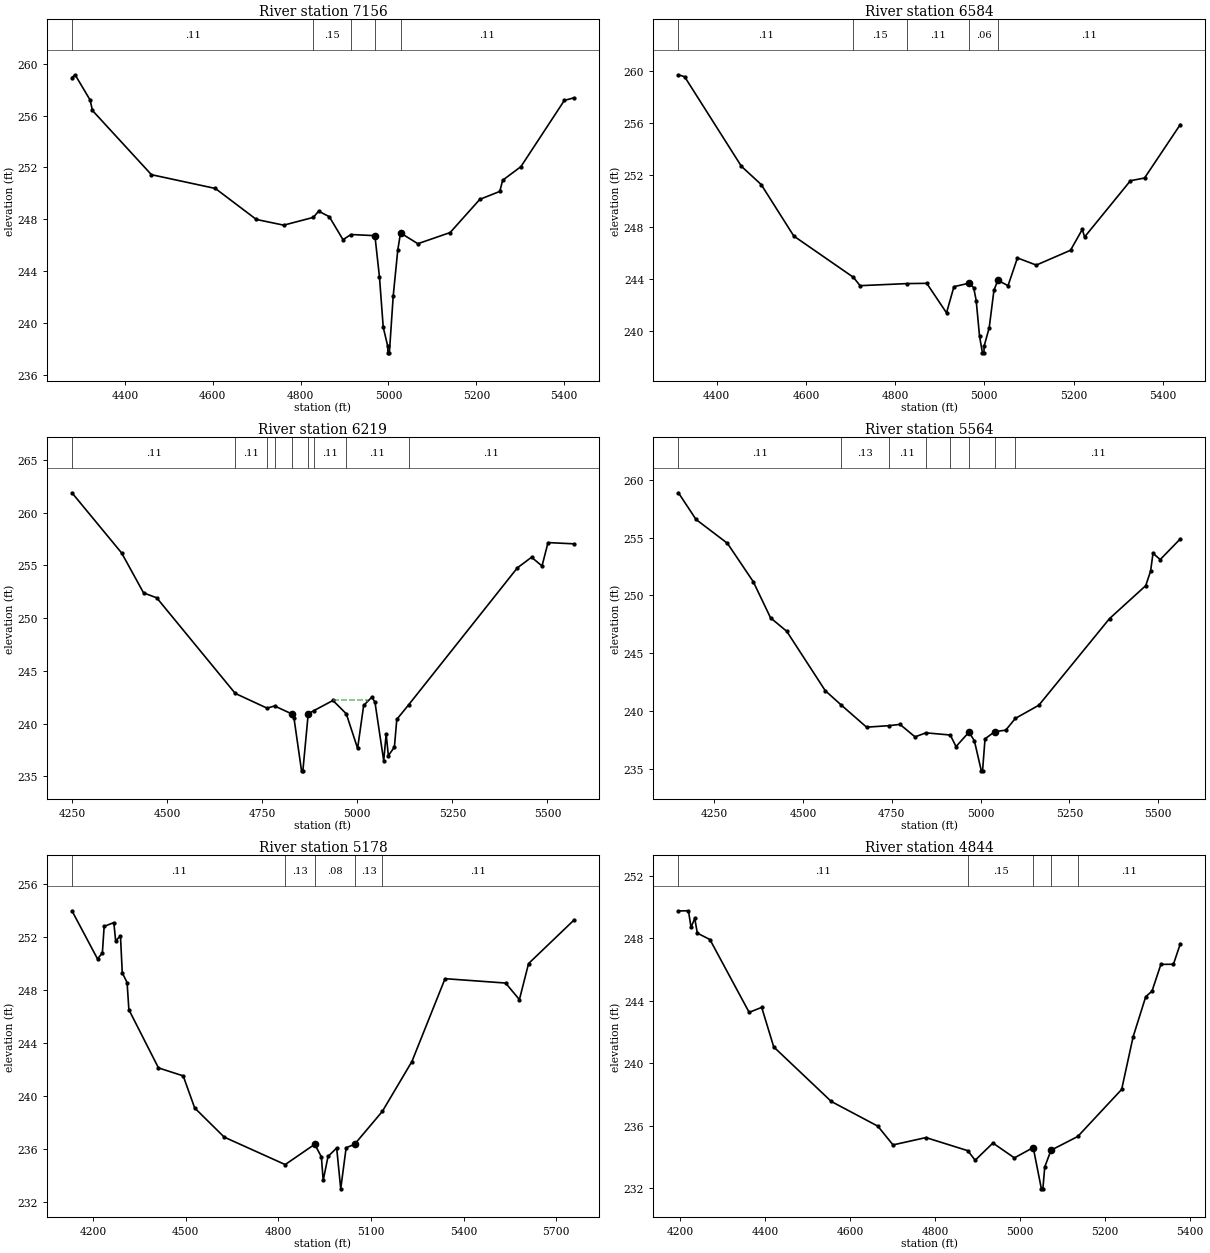
Type RM Length L Ch R = 1 ,7156    ,572,572,572
BEGIN DESCRIPTION:
WFSJR 001 10.0
END DESCRIPTION:
XS GIS Cut Line= 2
      3760412.14     10210787.35      3759311.75     10210480.39
#Sta/Elev= 30
  4279.6  258.93  4286.8  259.14    4321  257.19  4326.2  256.39  4460.5  251.44
  4605.9  250.38  4699.3  247.99  4761.6  247.55  4829.1  248.15    4841  248.63
  4865.4   248.2  4896.6  246.43  4914.6  246.83  4969.2  246.74  4979.6  243.53
  4988.1  239.69  4998.4  238.21  4998.6  237.71  5002.1  237.71  5010.8  242.08
  5021.2  245.63  5027.5  246.95  5066.9  246.12  5140.4  246.98    5208  249.54
  5253.4  250.15  5259.9  251.01  5301.5  252.06  5400.5  257.17    5422  257.36
#Mann= 5 ,-1 , 0
  4279.6     .11       0  4829.1     .15       0  4914.6     .11       0
  4969.2     .06       0  5027.5     .11       0
Bank Sta=4969.2,5027.5
XS Rating Curve= 0 ,0
Exp/Cntr=0.3,0.1

Type RM Length L Ch R = 1 ,6584    ,365,365,365
BEGIN DESCRIPTION:
WFSJR 001 9.0
END DESCRIPTION:
XS GIS Cut Line= 3
      3760467.82     10210411.05      3759858.23     10210096.84
       3759441.8     10209956.96
#Sta/Elev= 30
  4314.2   259.7  4328.1  259.55  4455.4  252.67  4499.7  251.27  4572.9  247.31
  4706.6  244.14  4721.4   243.5  4826.9  243.66  4870.9  243.68  4915.2  241.41
  4931.8  243.42  4966.7   243.7  4976.1  243.34  4981.7  242.36  4989.2  239.62
  4995.7  238.34  4999.2  238.34  4999.4  238.84  5010.9  240.27  5021.5  243.15
  5030.3  243.91  5053.1   243.5  5074.2  245.63  5116.4  245.08  5193.2  246.22
  5219.5  247.82  5224.7  247.24  5327.4  251.56  5359.1  251.77  5439.3  255.88
#Mann= 5 ,-1 , 0
  4314.2     .11       0  4706.6     .15       0  4826.9     .11       0
  4966.7     .06       0  5030.3     .11       0
Bank Sta=4966.7,5030.3
XS Rating Curve= 0 ,0
Exp/Cntr=0.3,0.1

Type RM Length L Ch R = 1 ,6219    ,655,655,655
BEGIN DESCRIPTION:
WFSJR 001 8.0
END DESCRIPTION:
XS GIS Cut Line= 2
      3760641.85     10210163.18      3759492.36     10209513.46
#Sta/Elev= 30
  4249.2  261.89    4380  256.18  4437.6   252.4  4472.3  251.93  4678.8  242.87
  4762.6  241.47  4782.2  241.68  4827.5  240.93  4833.3  240.54  4853.2  235.53
  4856.7  235.53  4870.8  240.95  4885.8  241.24  4935.8   242.2  4970.9  240.94
  5000.7  237.66  5016.6  241.73  5038.3  242.52  5046.4  242.03  5069.4  236.48
  5075.8  239.02  5081.6  236.97  5097.5  237.78  5103.8  240.41    5135  241.79
  5420.9  254.77  5458.4  255.78  5485.8  254.95  5501.7  257.17  5569.6  257.05
#Mann= 9 ,-1 , 0
  4249.2     .11       0  4678.8     .11       0  4762.6     .11       0
  4782.2     .11       0  4827.5     .06       0  4870.8     .11       0
  4885.8     .11       0  4970.9     .11       0    5135     .11       0
#XS Ineff= 2 ,-1
  4935.8    5025   242.2  5038.3    5175  242.52
Permanent Ineff=
       T       T
Bank Sta=4827.5,4870.8
XS Rating Curve= 0 ,0
Exp/Cntr=0.3,0.1

Type RM Length L Ch R = 1 ,5564    ,386,386,386
BEGIN DESCRIPTION:
WFSJR 001 7.0
END DESCRIPTION:
XS GIS Cut Line= 3
      3760847.04      10209821.2      3760031.96     10209305.59
      3759592.34     10209219.74
#Sta/Elev= 30
  4149.7  258.88  4199.3  256.57  4287.5  254.51  4360.4  251.18  4409.1  248.05
  4454.5  246.89  4562.9  241.75  4606.3  240.55  4679.2  238.59  4741.9  238.72
  4773.3  238.83  4815.6  237.75  4846.2   238.1  4914.8  237.91  4930.9  236.91
  4967.4  238.16  4982.6  237.41  5002.1  234.81  5005.6  234.81  5012.5  237.58
  5040.3  238.21  5070.8  238.33  5097.9  239.35    5164  240.49  5362.9  247.99
  5464.8  250.84  5478.5  252.11  5485.2  253.64  5505.5   253.1  5562.1  254.89
#Mann= 8 ,-1 , 0
  4149.7     .11       0  4606.3     .13       0  4741.9     .11       0
  4846.2     .11       0  4914.8     .11       0  4967.4     .06       0
  5040.3     .11       0  5097.9     .11       0
Bank Sta=4967.4,5040.3
XS Rating Curve= 0 ,0
Exp/Cntr=0.3,0.1

Type RM Length L Ch R = 1 ,5178    ,334,334,334
BEGIN DESCRIPTION:
WFSJR 001 6.0
END DESCRIPTION:
XS GIS Cut Line= 3
      3761026.75     10209516.53      3759972.06     10208896.73
      3759625.75     10209099.83
#Sta/Elev= 30
  4131.8     254  4214.6  250.37  4230.3  250.82    4236  252.82  4267.4  253.11
  4273.2  251.75  4288.9  252.09  4294.7  249.32  4310.3  248.59  4316.1  246.54
  4411.9  242.15  4491.9  241.55  4529.1  239.13  4624.8  236.93  4822.1  234.86
  4917.8  236.39  4939.3  235.44  4945.1  233.66  4960.8  235.47  4988.8  236.11
  5001.9  233.03  5019.4  236.13  5046.8  236.39  5136.6  238.87  5232.3  242.63
  5339.6  248.88  5535.7  248.55  5580.3   247.3    5610  250.02  5756.6  253.29
#Mann= 5 ,-1 , 0
  4131.8     .11       0  4822.1     .13       0  4917.8     .08       0
  5046.8     .13       0  5136.6     .11       0
Bank Sta=4917.8,5046.8
XS Rating Curve= 0 ,0
Exp/Cntr=0.3,0.1

Type RM Length L Ch R = 1 ,4844    ,478,478,478
BEGIN DESCRIPTION:
WFSJR 001 5.0
END DESCRIPTION:
XS GIS Cut Line= 2
      3761190.78     10209370.67      3760227.28     10208688.41
#Sta/Elev= 30
  4196.5  249.74  4220.1  249.75  4226.2  248.69  4234.9  249.26    4241  248.32
  4270.6  247.91  4362.9  243.25  4392.4  243.57  4420.7  241.04  4556.1  237.55
  4665.6  235.97  4701.3  234.77  4778.8  235.24  4877.2   234.4  4894.5  233.79
  4936.3  234.89  4986.8  233.94  5031.1   234.6  5050.3  231.96  5053.8  231.96
  5058.2  233.36  5072.9  234.43  5135.9  235.31  5239.1  238.32  5266.1  241.69
  5295.7  244.25  5310.5  244.61  5331.4  246.32  5360.9  246.33  5377.1  247.64
#Mann= 5 ,-1 , 0
  4196.5     .11       0  4877.2     .15       0  5031.1     .09       0
  5072.9     .15       0  5135.9     .11       0
Bank Sta=5031.1,5072.9
XS Rating Curve= 0 ,0
Exp/Cntr=0.3,0.1

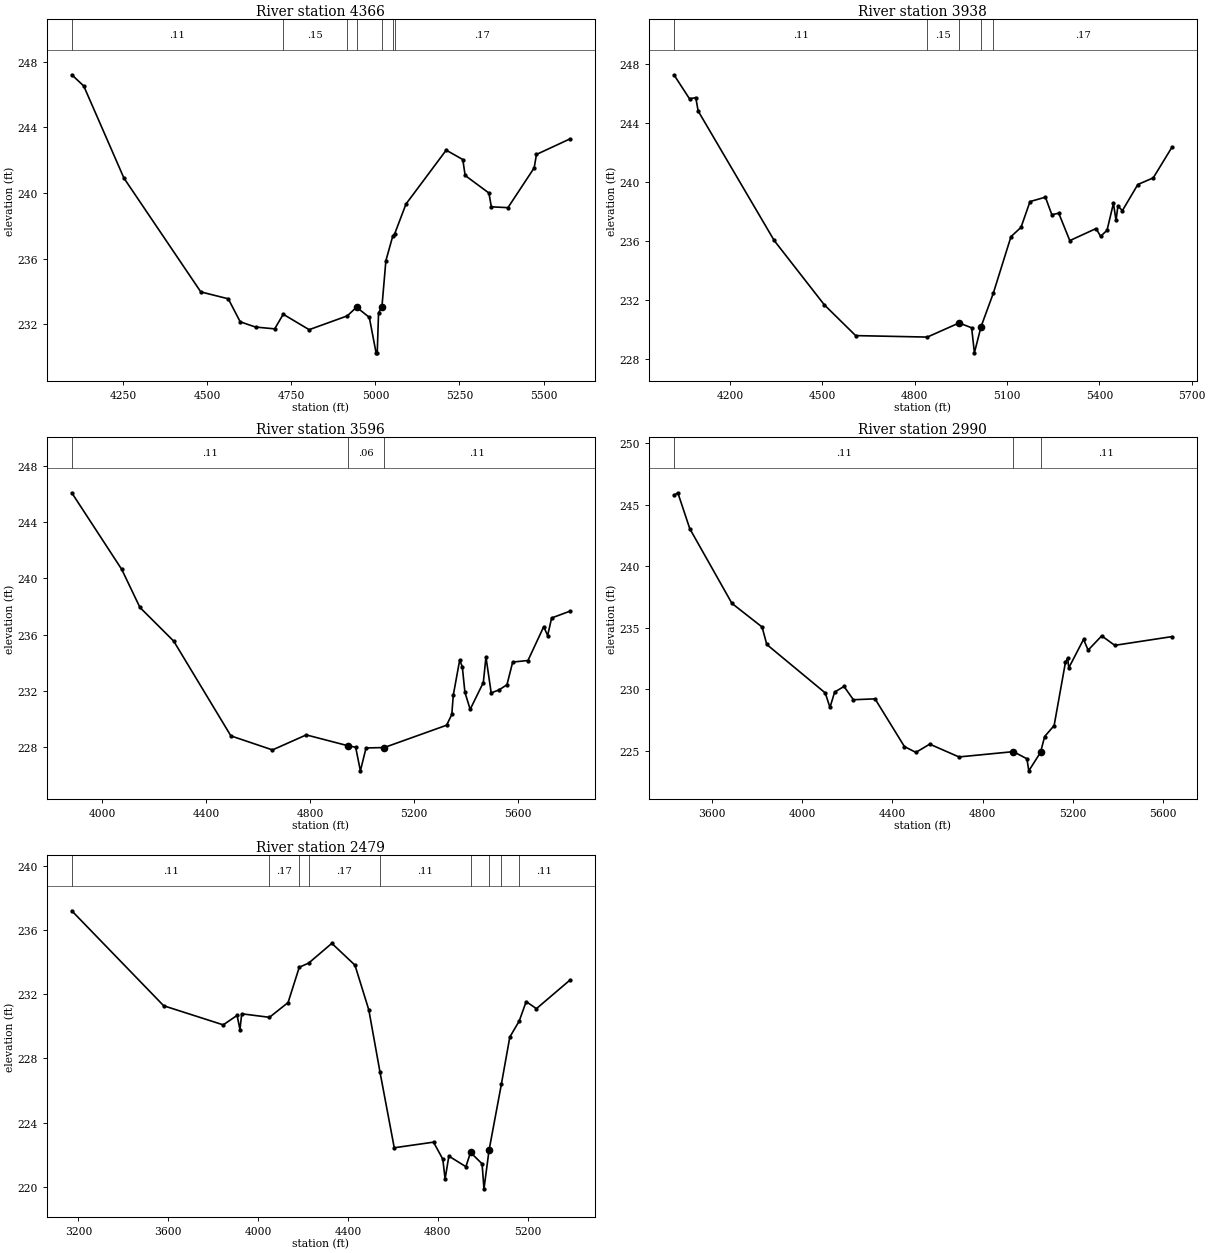
Type RM Length L Ch R = 1 ,4366    ,428,428,428
BEGIN DESCRIPTION:
WFSJR 001 4.0
END DESCRIPTION:
XS GIS Cut Line= 3
      3761217.83     10209311.04      3760675.18       10208316.
      3760434.26     10208064.72
#Sta/Elev= 30
  4096.6   247.2  4132.2  246.52  4251.8  240.91  4480.5  233.98  4562.2  233.56
  4597.7  232.16  4643.3  231.84  4700.3  231.73  4725.7  232.62  4802.8  231.68
  4916.3  232.52  4943.8  233.05  4981.8  232.43  5001.9  230.27  5005.4  230.27
  5009.3  232.71  5019.2  233.04  5031.1  235.88  5051.7  237.39  5056.8  237.49
  5090.9  239.33  5210.5  242.61  5259.9  242.04  5266.9  241.07  5337.6     240
  5344.8  239.16  5394.2  239.11  5472.2  241.53  5479.1  242.35  5578.1  243.29
#Mann= 7 ,-1 , 0
  4096.6     .11       0  4725.7     .15       0  4916.3     .11       0
  4943.8     .06       0  5019.2     .11       0  5051.7     .15       0
  5056.8     .17       0
Bank Sta=4943.8,5019.2
XS Rating Curve= 0 ,0
Exp/Cntr=0.3,0.1

Type RM Length L Ch R = 1 ,3938    ,342,342,342
BEGIN DESCRIPTION:
WFSJR 001 3.0
END DESCRIPTION:
XS GIS Cut Line= 3
      3761348.36     10209310.79      3761139.58     10208235.29
      3760827.54     10207816.04
#Sta/Elev= 30
  4017.7  247.27  4068.3  245.64  4088.7  245.72  4096.4  244.81  4343.4  236.02
  4506.4  231.65  4608.2  229.56    4841  229.46  4944.4  230.42  4985.1  230.09
    4994  228.39  5015.7  230.17  5055.5  232.44  5112.9  236.28  5145.5  236.91
  5174.7  238.66  5224.8  238.96  5245.6  237.77  5268.1  237.87    5304  236.01
  5389.5  236.83  5404.1   236.3    5425  236.71  5445.8  238.54  5454.2  237.39
  5460.4  238.35    5475  238.05  5525.1  239.82  5575.2  240.27  5635.9  242.35
#Mann= 5 ,-1 , 0
  4017.7     .11       0    4841     .15       0  4944.4     .09       0
  5015.7     .15       0  5055.5     .17       0
Bank Sta=4944.4,5015.7
XS Rating Curve= 0 ,0
Exp/Cntr=0.3,0.1

Type RM Length L Ch R = 1 ,3596    ,606,606,606
BEGIN DESCRIPTION:
WFSJR 001 2.0
END DESCRIPTION:
XS GIS Cut Line= 3
      3761442.11     10209313.42      3761465.55     10207844.67
      3761400.45     10207401.97
#Sta/Elev= 30
  3883.2   246.1  4075.6  240.64  4145.6  237.93  4275.6  235.53  4495.6  228.78
  4655.6  227.78  4785.7  228.85  4945.7  228.08  4975.7  227.97  4993.9  226.29
  5015.7  227.92  5085.7  227.95  5325.7  229.54  5345.7  230.31  5351.4  231.68
    5376  234.18  5386.1   233.7  5396.2  231.88  5416.4  230.67    5467  232.58
  5477.1   234.4  5497.3  231.84  5527.6  232.06  5557.9  232.42    5580  234.04
  5638.8  234.15  5699.4  236.56  5714.5  235.93  5729.8  237.18  5799.6  237.66
#Mann= 3 , 0 , 0
  3883.2     .11       0  4945.7     .06       0  5085.7     .11       0
Bank Sta=4945.7,5085.7
XS Rating Curve= 0 ,0
Exp/Cntr=0.3,0.1

Type RM Length L Ch R = 1 ,2990    ,511,511,511
BEGIN DESCRIPTION:
Mapping XS 3bab5ab5
END DESCRIPTION:
XS GIS Cut Line= 3
      3761685.16     10209567.79      3761949.06     10208616.37
      3762067.11     10207401.13
#Sta/Elev= 30
  3431.7  245.77    3449  245.98    3502  243.06  3688.9  236.99  3822.6  235.07
  3843.4  233.65  4102.8  229.71  4123.6  228.53  4144.3  229.78  4185.9  230.24
  4227.4  229.16  4323.5  229.23  4453.9  225.35  4504.7  224.88  4565.9  225.55
  4695.6  224.51  4936.8  224.94    4997  224.36  5005.3  223.38  5057.3  224.88
  5075.6  226.17  5117.6  227.06  5167.8   232.2  5177.6  232.54  5182.6  231.75
  5248.2  234.07  5268.3  233.19  5328.6  234.35  5386.5  233.58    5640  234.29
#Mann= 3 , 0 , 0
  3431.7     .11       0  4936.8     .06       0  5057.3     .11       0
Bank Sta=4936.8,5057.3
XS Rating Curve= 0 ,0
Exp/Cntr=0.3,0.1

Type RM Length L Ch R = 1 ,2479    ,0,0,0
BEGIN DESCRIPTION:
WFSJR 001 1.0
END DESCRIPTION:
XS GIS Cut Line= 3
      3762067.11      10209786.5      3762532.39     10207866.37
      3762629.19     10207645.11
#Sta/Elev= 30
  3170.8   237.2  3580.1  231.28  3845.2  230.09  3906.9  230.68  3919.7   229.8
  3927.5  230.78    4051  230.56  4133.9  231.48  4183.7  233.68  4225.5  233.94
  4328.8  235.17  4431.7  233.81  4493.4  231.02  4543.2  227.14  4606.6  222.43
  4781.5  222.78  4822.7  221.72    4833  220.49  4849.8  221.91  4925.6  221.25
  4946.2  222.14  4997.6  221.43  5006.1  219.87  5028.5  222.26  5083.4  226.38
  5121.1  229.33    5163  230.33    5194  231.54  5239.6   231.1    5388  232.87
#Mann= 9 ,-1 , 0
  3170.8     .11       0    4051     .17       0  4183.7     .11       0
  4225.5     .17       0  4543.2     .11       0  4946.2     .06       0
  5028.5     .11       0  5083.4     .17       0    5163     .11       0
Bank Sta=4946.2,5028.5
XS Rating Curve= 0 ,0
Exp/Cntr=0.3,0.1

Chan Stop Cuts=-1
Use User Specified Reach Order=0
Composite Channel Slope=5