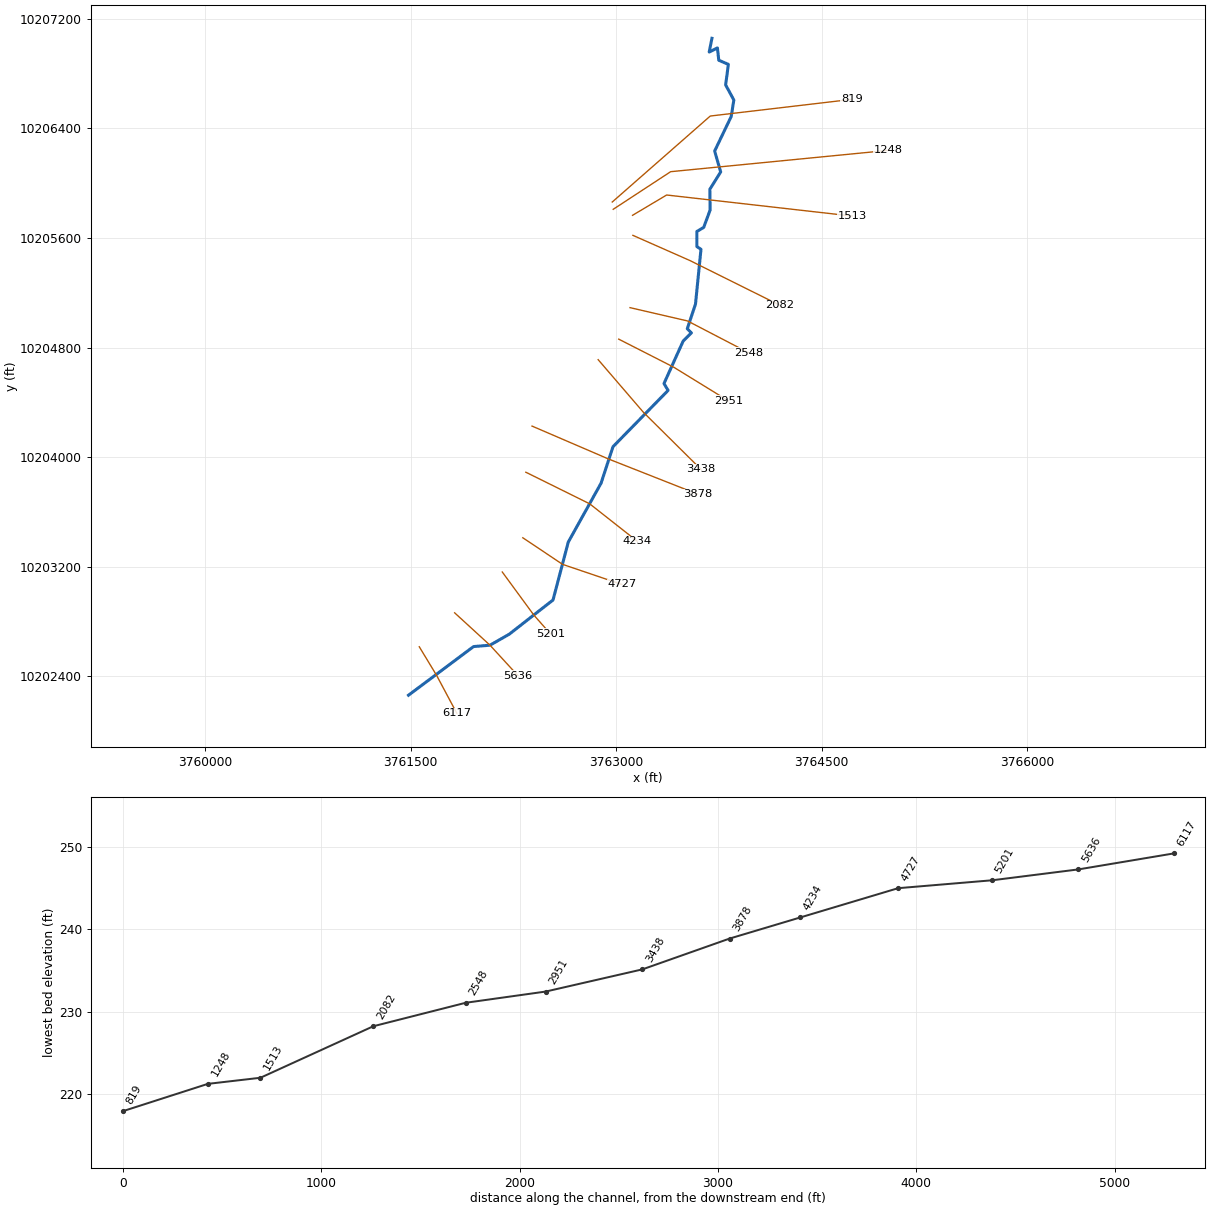
--- WFSJR 002.prj (project) ---

Proj Title=WFSJR 002 Base Level Engineering
Current Plan=p01
Default Exp/Contr=0.3,0.1
English Units
Geom File=g01
Flow File=f01
Plan File=p01
Y Axis Title=Elevation
X Axis Title(PF)=Main Channel Distance
X Axis Title(XS)=Station
BEGIN DESCRIPTION:
WFSJR 002
END DESCRIPTION:
DSS Export Rating Curves= 0
DSS Export Rating Curve Sorted= 0
DSS Export Volume Flow Curves= 0
DXF OffsetX= 0
DXF OffsetY= 0
DXF ScaleX= 1
DXF ScaleY= 10

--- WFSJR 002.p01 (plan) ---

Plan Title=Multiple Run
Program Version=4.10
Short Identifier=Multiple
Geom File=g01
Flow File=f01
Subcritical Flow
K Sum by GR= 0
Std Step Tol= 0.01
Critical Tol= 0.01
Num of Std Step Trials= 20
Max Error Tol= 0.3
Flow Tol Ratio= 0.001
Split Flow NTrial= 30
Split Flow Tol= 0.02
Split Flow Ratio= 0.02
Log Output Level= 0
Friction Slope Method= 1
Unsteady Friction Slope Method= 2
Unsteady Bridges Friction Slope Method= 1
Parabolic Critical Depth
Global Vel Dist= 1 , 1 , 1
Global Log Level= 0
CheckData=True
Encroach Param=-1 ,0,0, 0
BEGIN DESCRIPTION:
Multiple Run
END DESCRIPTION:
Computation Interval=1HOUR
Output Interval=1HOUR
Run HTab= 0
Run UNet= 0
Run PostProcess= 0
Run WQNet= 0
UNET Theta= 1
UNET Theta Warmup= 1
UNET ZTol= 0.02
UNET ZSATol= 0.05
UNET MxIter= 20
UNET MaxInSteps= 0
UNET DtIC= 0
UNET DtMin= 0
UNET MaxCRTS= 20
UNET WFStab= 2
UNET SFStab= 1
UNET WFX= 1
UNET SFX= 1
UNET DSS MLevel= 4
UNET DZMax Abort= 100
UNET Convert EG Bridges= 0
UNET Use Existing IB Tables=-1
UNET Froude Reduction=False
UNET Froude Limit= 1
UNET Froude Power= 10
UNET Time Slicing=0,0, 5
UNET Junction Losses=0
Instantaneous Interval=1HOUR
Write IC File= 0
Write IC File at Sim End=0
Echo Input=False
Echo Parameters=False
Echo Output=False
Write Detailed= 0
WQ AD Non Conservative
WQ ULTIMATE=-1
WQ Max Comp Step=1HOUR
WQ Output Interval=15MIN
WQ Output Selected Increments= 0
WQ Output face flow=0
WQ Output face velocity=0
WQ Output face area=0
WQ Output face dispersion=0
WQ Output cell volume=0
WQ Output cell surface area=0
WQ Output cell continuity=0
WQ Output cumulative cell continuity=0
WQ Output face conc=0
WQ Output face dconc_dx=0
WQ Output face courant=0
WQ Output face peclet=0
WQ Output face adv mass=0
WQ Output face disp mass=0
WQ Output cell mass=0
WQ Output cell source sink temp=0
WQ Output cell source sink nsm=0
WQ Output MaxMinRange=-1
WQ Daily Max Min Mean=-1
WQ Daily Range=0
WQ Daily Time=0
WQ Create Restart=0
WQ Fixed Restart=0
WQ System Summary=0
WQ Use Fixed Temperature=0
Sorting and Armoring Iterations= 10
XS Update Threshold= 0.02
Hydraulics Update Threshold= 0.02
Energy Slope Method= 1
Volume Change Method= 0
XS Weighting Method= 0
Number of US Weighted Cross Sections= 1
Number of DS Weighted Cross Sections= 1
Upstream XS Weight=0.25
Main XS Weight=0.5
Downstream XS Weight=0.25
Number of DS XS's Weighted with US Boundary= 1
Upstream Boundary Weight= 1
Weight of XSs Associated with US Boundary= 0
Number of US XS's Weighted with DS Boundary= 1
Downstream Boundary Weight= 0.5
Weight of XSs Associated with DS Boundary= 0.5
Sediment Output Level= 4
Mass or Volume Output= 0
Output Increment Type= 1
Profile and TS Output Increment= 10
XS Output Flag= 0
XS Output Increment= 10
Disregard all LS=0
Disregard all Conn=0
Disregard all Breaches=0
Disregard all Pumps=0

--- WFSJR 002.f01 (steady flow) ---

Flow Title=Multiple
Program Version=4.10
Number of Profiles= 7
Profile Names=10-year,25-year,50-year,1pct_min,100-year,1pct_plu,500-year
River Rch & RM=WFSJR 002,Reach-1         ,6117
    1170    1667    2332    1074    3242    9791    6481
Boundary for River Rch & Prof#=WFSJR 002,Reach-1         , 1
Up Type= 0
Dn Type= 3
Dn Slope=0.012
Boundary for River Rch & Prof#=WFSJR 002,Reach-1         , 2
Up Type= 0
Dn Type= 3
Dn Slope=0.012
Boundary for River Rch & Prof#=WFSJR 002,Reach-1         , 3
Up Type= 0
Dn Type= 3
Dn Slope=0.012
Boundary for River Rch & Prof#=WFSJR 002,Reach-1         , 4
Up Type= 0
Dn Type= 3
Dn Slope=0.012
Boundary for River Rch & Prof#=WFSJR 002,Reach-1         , 5
Up Type= 0
Dn Type= 3
Dn Slope=0.012
Boundary for River Rch & Prof#=WFSJR 002,Reach-1         , 6
Up Type= 0
Dn Type= 3
Dn Slope=0.012
Boundary for River Rch & Prof#=WFSJR 002,Reach-1         , 7
Up Type= 0
Dn Type= 3
Dn Slope=0.012
DSS Import GetInterval= 0
DSS Import GetPeak= 0
DSS Import FillOption= 0

--- WFSJR 002.g01 (geometry) ---

Geom Title=Existing Conditions
Program Version=4.10

River Reach=WFSJR 002       ,Reach-1
Reach XY= 30
      3761483.23     10202261.84      3761958.23     10202616.84
      3762078.23     10202626.84      3762218.23     10202706.84
      3762538.23     10202956.84      3762649.55     10203379.52
      3762889.14     10203810.07      3762975.94      10204075.7
      3763378.23     10204486.84      3763348.23     10204536.84
      3763488.23     10204846.84      3763548.23     10204906.84
      3763518.23     10204936.84      3763578.23     10205116.84
      3763618.23     10205516.84      3763588.23     10205536.84
      3763588.23     10205646.84      3763638.23     10205676.84
      3763685.07     10205803.68      3763683.04     10205955.13
      3763762.11     10206081.64      3763718.05     10206234.13
      3763838.96     10206486.11      3763858.23     10206606.84
      3763798.23     10206716.84      3763818.23     10206866.84
      3763748.23     10206896.84      3763738.23     10206986.84
      3763678.23     10206956.84      3763698.23     10207056.84

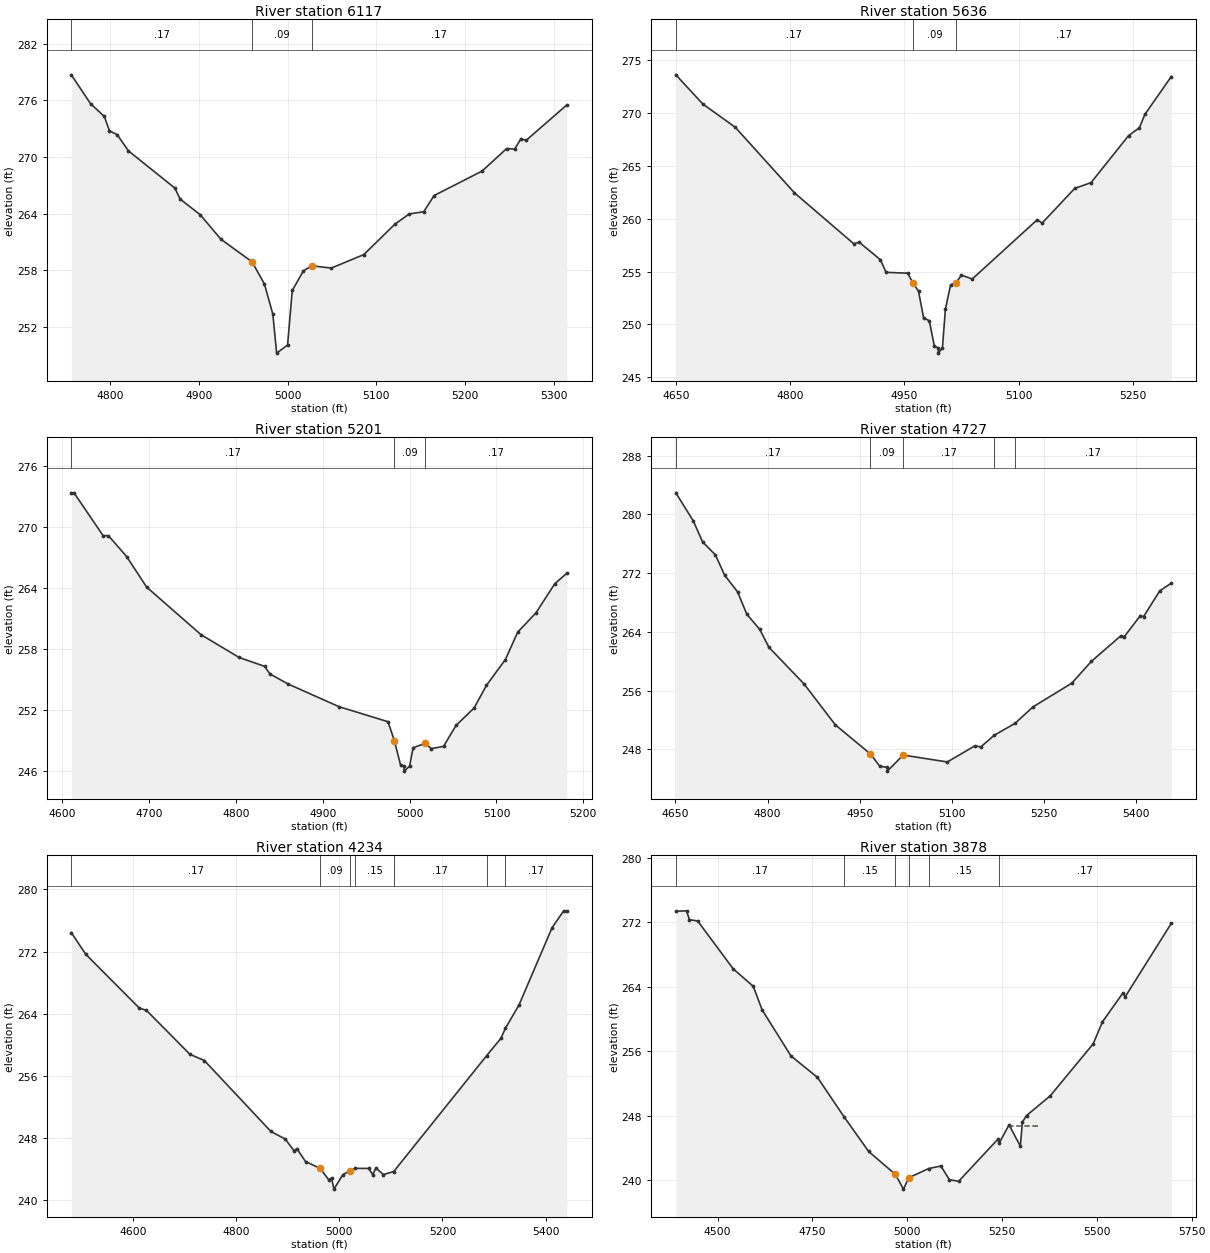
Type RM Length L Ch R = 1 ,6117    ,481,481,481
BEGIN DESCRIPTION:
WFSJR 002 12.0
END DESCRIPTION:
XS GIS Cut Line= 3
      3761562.06     10202615.34      3761688.23     10202406.84
      3761836.39      10202129.2
#Sta/Elev= 30
  4756.3  278.72    4778  275.66  4793.5  274.31  4799.3  272.78    4808  272.38
  4820.7  270.66    4873  266.72  4878.9  265.56  4901.6  263.89  4924.9   261.3
    4960   258.9  4973.9  256.56  4983.4  253.37  4987.7  249.23    5000  250.08
  5005.3  255.87  5017.9  257.95  5027.3  258.49  5049.3  258.24  5085.9  259.67
  5120.8  262.88  5137.1  263.98  5153.4  264.21  5165.2  265.93  5219.2  268.52
  5246.9  270.91  5255.9  270.85  5263.1  271.95  5268.8  271.77  5314.7  275.53
#Mann= 3 , 0 , 0
  4756.3     .17       0    4960     .09       0  5027.3     .17       0
Bank Sta=4960,5027.3
XS Rating Curve= 0 ,0
Exp/Cntr=0.3,0.1

Type RM Length L Ch R = 1 ,5636    ,435,435,435
BEGIN DESCRIPTION:
WFSJR 002 11.0
END DESCRIPTION:
XS GIS Cut Line= 3
      3761820.18     10202863.15      3762078.23     10202626.84
      3762281.28     10202405.46
#Sta/Elev= 30
  4650.1  273.61  4685.5  270.85  4728.1  268.65  4805.8  262.45  4883.5  257.64
  4890.9  257.77  4918.6  256.12    4926  254.93  4954.4  254.85  4961.2  253.93
  4968.6  253.14  4975.3  250.61  4982.7  250.36  4989.5  247.93  4994.4  247.79
  4994.6  247.29    5000  247.79  5003.9  251.46  5010.7  253.74  5018.1  253.96
  5024.9  254.67  5039.1   254.3  5124.2  259.89    5131   259.6  5173.5  262.86
  5195.1  263.42  5244.4  267.87  5258.6  268.61  5265.6  269.86  5300.4  273.45
#Mann= 3 , 0 , 0
  4650.1     .17       0  4961.2     .09       0  5018.1     .17       0
Bank Sta=4961.2,5018.1
XS Rating Curve= 0 ,0
Exp/Cntr=0.3,0.1

Type RM Length L Ch R = 1 ,5201    ,474,474,474
BEGIN DESCRIPTION:
WFSJR 002 10.0
END DESCRIPTION:
XS GIS Cut Line= 3
      3762167.87     10203161.05      3762398.23     10202846.84
      3762517.88     10202711.04
#Sta/Elev= 30
  4610.4  273.35  4613.5  273.35    4647  269.14  4653.2  269.13  4674.1  267.08
  4697.2  264.07  4759.7   259.4  4803.7  257.15    4833  256.28  4839.2  255.53
  4860.1  254.54  4918.7  252.31  4975.1  250.83  4982.4  248.97  4989.7  246.53
  4993.5  246.47  4993.7  245.97    5000  246.47    5004  248.27  5018.2  248.71
  5024.9  248.18  5039.1  248.41  5053.4  250.46  5074.3  252.19  5088.5  254.41
  5110.3  256.95  5124.5  259.65  5145.4  261.53  5167.2  264.41    5181  265.44
#Mann= 3 ,-1 , 0
  4610.4     .17       0  4982.4     .09       0  5018.2     .17       0
Bank Sta=4982.4,5018.2
XS Rating Curve= 0 ,0
Exp/Cntr=0.3,0.1

Type RM Length L Ch R = 1 ,4727    ,493,493,493
BEGIN DESCRIPTION:
WFSJR 002 9.0
END DESCRIPTION:
XS GIS Cut Line= 3
      3762317.89     10203411.05      3762608.23     10203216.84
      3763041.26     10203070.17
#Sta/Elev= 30
  4650.7  282.95  4679.2  279.11  4694.2  276.27  4715.2  274.48  4730.2  271.71
  4751.2  269.45  4766.3  266.39  4787.3  264.33  4802.3  261.88  4859.3  256.91
  4910.4  251.31  4967.4  247.35  4982.5   245.7  4994.8  245.51    4995  245.01
  5020.7   247.2  5092.6  246.26  5136.9  248.43  5147.4  248.33  5168.5  249.87
  5202.9  251.53  5231.9  253.76  5295.2     257  5326.9  259.96  5375.4  263.49
  5380.7  263.35  5406.9  266.22  5412.1  266.08  5438.3  269.58  5457.2  270.64
#Mann= 5 ,-1 , 0
  4650.7     .17       0  4967.4     .09       0  5020.7     .17       0
  5168.5     .15       0  5202.9     .17       0
Bank Sta=4967.4,5020.7
XS Rating Curve= 0 ,0
Exp/Cntr=0.3,0.1

Type RM Length L Ch R = 1 ,4234    ,356,356,356
BEGIN DESCRIPTION:
WFSJR 002 8.0
END DESCRIPTION:
XS GIS Cut Line= 3
      3762339.84     10203889.62       3762805.8     10203659.03
      3763152.36     10203386.14
#Sta/Elev= 30
  4480.1  274.43  4508.2  271.64  4611.8  264.74  4625.9  264.43  4710.1  258.79
  4738.1  257.99  4867.1  248.88  4895.1  247.89    4912  246.39  4917.5  246.66
  4934.4     245  4962.4  244.14  4979.3  242.67  4984.8   242.9  4989.4  241.46
  5006.9  243.33  5021.3  243.84  5030.9  244.13  5056.6  244.12  5064.7  243.33
    5071  244.17  5085.5  243.33  5105.4  243.72  5285.8  258.63  5313.2  260.83
  5322.2  262.15  5348.4  265.13  5412.6  275.07    5435  277.23  5441.1  277.23
#Mann= 7 ,-1 , 0
  4480.1     .17       0  4962.4     .09       0  5021.3     .17       0
  5030.9     .15       0  5105.4     .17       0  5285.8     .15       0
  5322.2     .17       0
Bank Sta=4962.4,5021.3
XS Rating Curve= 0 ,0
Exp/Cntr=0.3,0.1

Type RM Length L Ch R = 1 ,3878    ,440,440,440
BEGIN DESCRIPTION:
WFSJR 002 7.0
END DESCRIPTION:
XS GIS Cut Line= 3
      3762384.96     10204226.44       3762945.2      10203985.4
      3763593.08     10203729.99
#Sta/Elev= 30
  4390.1  273.39  4418.4  273.44  4425.9  272.34  4447.7  272.18  4541.5  266.23
  4594.1  264.08  4617.6  261.15  4693.6  255.43  4763.4  252.77  4834.7   247.8
  4898.3  243.58  4968.9  240.73  4990.2   238.9  5004.1  240.31  5056.6  241.45
  5088.8  241.77  5111.5  240.06  5135.9  239.88  5238.8  245.08  5242.8  244.63
  5268.5  246.87  5298.3  244.24  5303.8  247.23  5314.6  248.03  5376.8  250.46
  5490.4  256.93  5514.8  259.66    5569  263.26  5574.3  262.74  5696.4  271.89
#Mann= 6 ,-1 , 0
  4390.1     .17       0  4834.7     .15       0  4968.9     .09       0
  5004.1     .17       0  5056.6     .15       0  5242.8     .17       0
#XS Ineff= 1 ,-1
  5273.9    5350  246.76
Permanent Ineff=
       F
Bank Sta=4968.9,5004.1
XS Rating Curve= 0 ,0
Exp/Cntr=0.3,0.1

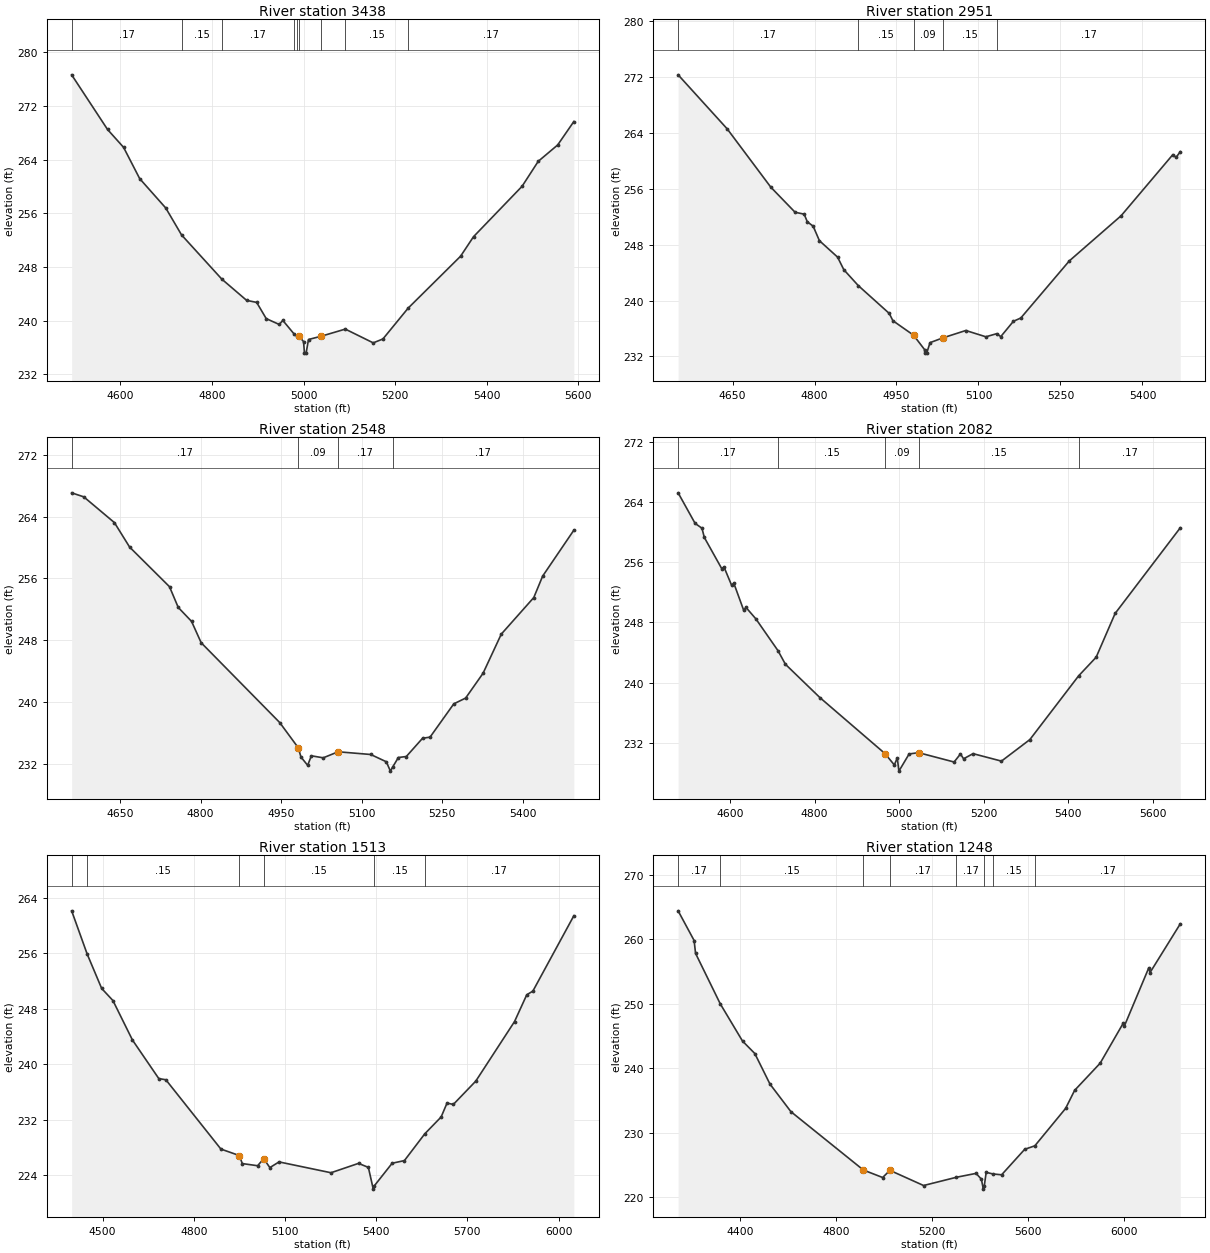
Type RM Length L Ch R = 1 ,3438    ,487,487,487
BEGIN DESCRIPTION:
WFSJR 002 6.0
END DESCRIPTION:
XS GIS Cut Line= 3
      3762867.87     10204711.04      3763198.23     10204326.84
      3763617.84     10203911.09
#Sta/Elev= 30
  4493.3  276.63  4571.7  268.49  4606.8  265.82    4642  261.16    4699  256.78
  4733.5  252.77  4821.4  246.19  4875.7  243.02  4897.6  242.72  4918.5   240.3
    4947  239.43  4954.7  240.04  4979.9  237.97  4985.7  237.75  4989.8   237.7
    5000  236.88  5002.1  235.16  5005.6  235.16  5010.9  237.19  5039.2  237.69
  5091.3  238.74  5152.3  236.69  5173.5  237.27  5228.7  241.87  5343.2   249.6
  5371.5  252.51  5477.6  260.02  5512.9  263.74  5555.4  266.18  5590.7  269.67
#Mann= 9 ,-1 , 0
  4493.3     .17       0  4733.5     .15       0  4821.4     .17       0
  4979.9     .15       0  4985.7     .17       0  4989.8     .09       0
  5039.2     .17       0  5091.3     .15       0  5228.7     .17       0
Bank Sta=4989.8,5039.2
XS Rating Curve= 0 ,0
Exp/Cntr=0.3,0.1

Type RM Length L Ch R = 1 ,2951    ,403,403,403
BEGIN DESCRIPTION:
WFSJR 002 5.0
END DESCRIPTION:
XS GIS Cut Line= 3
      3763017.81     10204861.09      3763418.23     10204656.84
      3763817.89     10204411.05
#Sta/Elev= 30
  4550.5  272.32  4640.3  264.58  4720.1  256.23  4764.5  252.64  4781.1  252.37
  4786.8  251.28  4797.5  250.65    4809  248.57  4842.2  246.22  4853.6  244.42
  4880.1  242.14  4936.8  238.15  4943.4  237.11  4981.2  235.04  5001.4  232.97
  5001.7  232.47  5005.3  232.47  5011.3  233.97  5034.3  234.64  5076.8  235.71
  5113.5  234.81  5133.6  235.26  5140.7  234.83  5163.9  237.03  5177.4   237.5
  5266.2  245.68  5360.9  252.14  5455.6   260.9  5461.4  260.49  5469.2  261.32
#Mann= 5 ,-1 , 0
  4550.5     .17       0  4880.1     .15       0  4981.2     .09       0
  5034.3     .15       0  5133.6     .17       0
Bank Sta=4981.2,5034.3
XS Rating Curve= 0 ,0
Exp/Cntr=0.3,0.1

Type RM Length L Ch R = 1 ,2548    ,466,466,466
BEGIN DESCRIPTION:
WFSJR 002 4.0
END DESCRIPTION:
XS GIS Cut Line= 3
      3763100.24     10205091.01      3763520.15     10204993.88
      3763967.84     10204761.08
#Sta/Elev= 30
  4559.9  267.07  4582.5  266.55  4639.6  263.22  4667.9  260.06  4742.2  254.94
  4758.5  252.26  4783.3  250.46  4801.2   247.7  4947.5  237.39  4982.3  234.11
  4987.1  232.93  4999.6  231.86  5006.5  233.09  5028.6  232.83  5056.4  233.61
  5117.1  233.26  5146.1  232.32  5153.8  231.11  5157.7  231.61  5168.6  232.87
  5183.4     233  5213.7  235.36  5227.6   235.5  5271.8   239.8  5293.9  240.55
  5326.4  243.76  5360.3  248.81  5420.9  253.54  5437.4  256.31  5495.5  262.24
#Mann= 4 ,-1 , 0
  4559.9     .17       0  4982.3     .09       0  5056.4     .17       0
  5157.7     .17       0
Bank Sta=4982.3,5056.4
XS Rating Curve= 0 ,0
Exp/Cntr=0.3,0.1

Type RM Length L Ch R = 1 ,2082    ,569,569,569
BEGIN DESCRIPTION:
WFSJR 002 3.0
END DESCRIPTION:
XS GIS Cut Line= 3
      3763121.12     10205618.78      3763537.78     10205434.75
      3764193.47     10205108.64
#Sta/Elev= 30
    4477  265.22  4517.2  261.16  4533.4  260.52    4539  259.29    4580  255.17
  4585.5  255.37  4603.3  252.97  4608.8  253.21  4632.1  249.62  4637.5     250
  4660.8  248.49  4713.2  244.26  4730.8  242.45  4812.3  238.03  4966.1   230.6
  4988.4  229.08  4995.4  230.02  4999.2  228.26  5023.4  230.54  5045.8  230.71
  5129.8  229.47  5144.8  230.54  5152.2   229.9  5174.6  230.58  5241.8  229.59
    5309  232.45  5424.4  240.92  5465.8  243.39  5510.6   249.2  5664.8  260.58
#Mann= 5 ,-1 , 0
    4477     .17       0  4713.2     .15       0  4966.1     .09       0
  5045.8     .15       0  5424.4     .17       0
Bank Sta=4966.1,5045.8
XS Rating Curve= 0 ,0
Exp/Cntr=0.3,0.1

Type RM Length L Ch R = 1 ,1513    ,265,265,265
BEGIN DESCRIPTION:
WFSJR 002 2.0
END DESCRIPTION:
XS GIS Cut Line= 3
       3763118.8     10205765.01      3763367.64     10205913.22
      3764721.81      10205759.5
#Sta/Elev= 30
  4397.9  262.09  4449.1  255.85  4496.7  250.91  4533.7  249.17  4597.9  243.49
  4684.7  237.93  4707.9  237.76    4889  227.78  4949.4  226.85  4959.5  225.69
  5009.8  225.38  5029.9  226.39  5050.1  225.11  5080.3  225.93  5251.3  224.37
  5341.9  225.72  5374.3  225.14  5390.4  222.01  5394.3  222.51  5452.6  225.74
  5492.9  226.12  5560.2  229.99  5613.7   232.4  5633.1   234.4  5653.9  234.21
  5727.8  237.57  5855.2  246.14  5895.5     250  5915.6  250.53  6050.4  261.38
#Mann= 6 ,-1 , 0
  4397.9     .17       0  4449.1     .15       0  4949.4     .09       0
  5029.9     .15       0  5394.3     .15       0  5560.2     .17       0
Bank Sta=4949.4,5029.9
XS Rating Curve= 0 ,0
Exp/Cntr=0.3,0.1

Type RM Length L Ch R = 1 ,1248    ,429,429,429
BEGIN DESCRIPTION:
Mapping XS 8e059398
END DESCRIPTION:
XS GIS Cut Line= 3
      3762977.83     10205808.89      3763396.92      10206083.4
      3764984.13     10206238.83
#Sta/Elev= 30
  4141.1  264.39  4207.9  259.79  4213.9   257.8    4317  249.98  4409.9  244.21
  4461.2  242.28  4524.4  237.55  4611.9  233.27  4914.3  224.23  4994.7  223.07
  5024.9  224.18  5165.5  221.83  5302.8  223.11  5384.6  223.71  5406.7  222.81
  5414.9  221.27  5418.8  221.77  5426.8  223.87  5455.2  223.62  5491.2  223.49
  5587.5  227.44  5629.8  227.98  5758.3  233.78  5795.8  236.57  5902.4  240.78
  5998.9  246.99  6003.9  246.58  6105.5  255.57  6110.5  254.82  6236.9  262.38
#Mann= 8 ,-1 , 0
  4141.1     .17       0    4317     .15       0  4914.3     .09       0
  5024.9     .17       0  5302.8     .17       0  5418.8     .17       0
  5455.2     .15       0  5629.8     .17       0
Bank Sta=4914.3,5024.9
XS Rating Curve= 0 ,0
Exp/Cntr=0.3,0.1

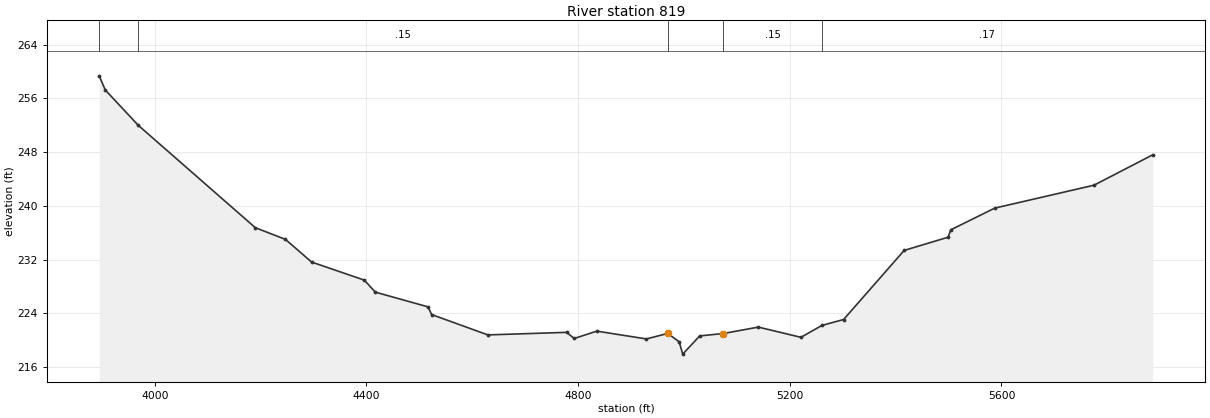
Type RM Length L Ch R = 1 ,819     ,0,0,0
BEGIN DESCRIPTION:
WFSJR 002 1.0
END DESCRIPTION:
XS GIS Cut Line= 3
      3762970.57       10205862.      3763686.05     10206489.65
      3764718.05     10206611.15
#Sta/Elev= 30
    3895  259.35  3906.3  257.26  3968.9  251.98    4190  236.76  4246.9  235.02
  4296.3  231.65  4395.9  228.96  4416.8  227.17  4516.4  224.98  4523.1  223.84
  4629.4  220.81  4778.3  221.19  4792.6  220.28  4835.3  221.37  4929.1  220.21
  4969.4  221.03  4990.9  219.79  4997.7  217.95  5029.8  220.66  5073.9  221.01
  5140.6  221.97  5221.1  220.45  5260.7  222.22  5301.7   223.1  5416.2  233.38
  5499.2  235.34  5504.2  236.44  5587.3  239.67  5774.9  243.08  5885.9   247.6
#Mann= 5 ,-1 , 0
    3895     .17       0  3968.9     .15       0  4969.4     .09       0
  5073.9     .15       0  5260.7     .17       0
Bank Sta=4969.4,5073.9
XS Rating Curve= 0 ,0
Exp/Cntr=0.3,0.1

Chan Stop Cuts=-1
Use User Specified Reach Order=0
Composite Channel Slope=5