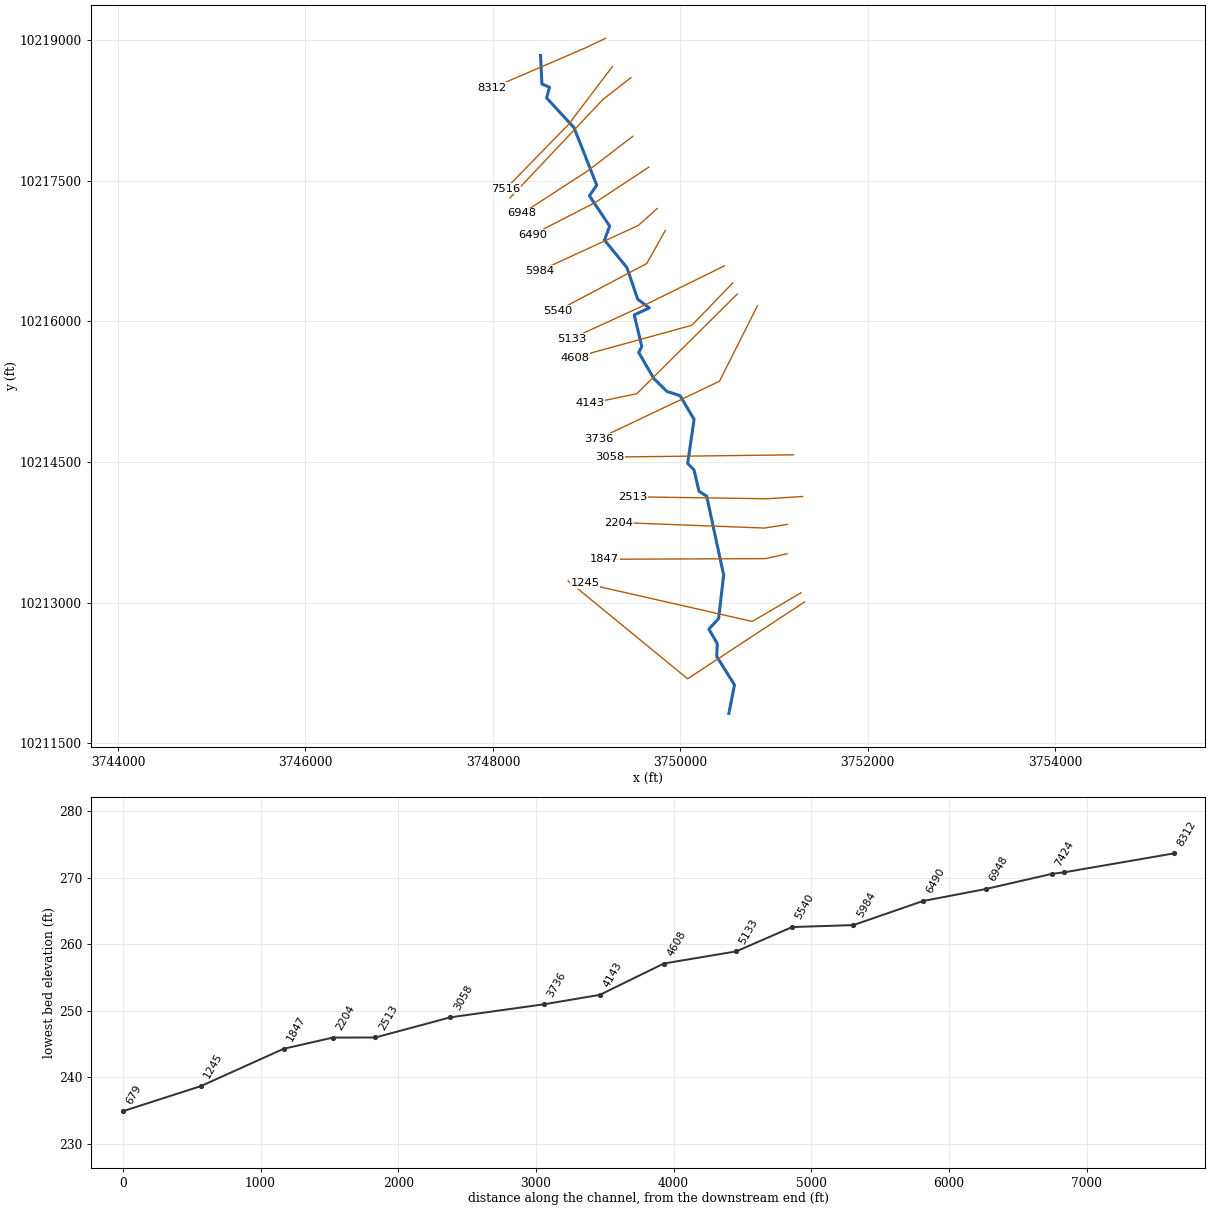
--- WFSJR 003.prj (project) ---

Proj Title=WFSJR 003 Base Level Engineering
Current Plan=p01
Default Exp/Contr=0.3,0.1
English Units
Geom File=g01
Flow File=f01
Plan File=p01
Y Axis Title=Elevation
X Axis Title(PF)=Main Channel Distance
X Axis Title(XS)=Station
BEGIN DESCRIPTION:
WFSJR 003
END DESCRIPTION:
DSS Export Rating Curves= 0
DSS Export Rating Curve Sorted= 0
DSS Export Volume Flow Curves= 0
DXF OffsetX= 0
DXF OffsetY= 0
DXF ScaleX= 1
DXF ScaleY= 10

--- WFSJR 003.p01 (plan) ---

Plan Title=Multiple Run
Program Version=4.10
Short Identifier=Multiple
Geom File=g01
Flow File=f01
Subcritical Flow
K Sum by GR= 0
Std Step Tol= 0.01
Critical Tol= 0.01
Num of Std Step Trials= 20
Max Error Tol= 0.3
Flow Tol Ratio= 0.001
Split Flow NTrial= 30
Split Flow Tol= 0.02
Split Flow Ratio= 0.02
Log Output Level= 0
Friction Slope Method= 1
Unsteady Friction Slope Method= 2
Unsteady Bridges Friction Slope Method= 1
Parabolic Critical Depth
Global Vel Dist= 1 , 1 , 1
Global Log Level= 0
CheckData=True
Encroach Param=-1 ,0,0, 0
BEGIN DESCRIPTION:
Multiple Run
END DESCRIPTION:
Computation Interval=1HOUR
Output Interval=1HOUR
Run HTab= 0
Run UNet= 0
Run PostProcess= 0
Run WQNet= 0
UNET Theta= 1
UNET Theta Warmup= 1
UNET ZTol= 0.02
UNET ZSATol= 0.05
UNET MxIter= 20
UNET MaxInSteps= 0
UNET DtIC= 0
UNET DtMin= 0
UNET MaxCRTS= 20
UNET WFStab= 2
UNET SFStab= 1
UNET WFX= 1
UNET SFX= 1
UNET DSS MLevel= 4
UNET DZMax Abort= 100
UNET Convert EG Bridges= 0
UNET Use Existing IB Tables=-1
UNET Froude Reduction=False
UNET Froude Limit= 1
UNET Froude Power= 10
UNET Time Slicing=0,0, 5
UNET Junction Losses=0
Instantaneous Interval=1HOUR
Write IC File= 0
Write IC File at Sim End=0
Echo Input=False
Echo Parameters=False
Echo Output=False
Write Detailed= 0
WQ AD Non Conservative
WQ ULTIMATE=-1
WQ Max Comp Step=1HOUR
WQ Output Interval=15MIN
WQ Output Selected Increments= 0
WQ Output face flow=0
WQ Output face velocity=0
WQ Output face area=0
WQ Output face dispersion=0
WQ Output cell volume=0
WQ Output cell surface area=0
WQ Output cell continuity=0
WQ Output cumulative cell continuity=0
WQ Output face conc=0
WQ Output face dconc_dx=0
WQ Output face courant=0
WQ Output face peclet=0
WQ Output face adv mass=0
WQ Output face disp mass=0
WQ Output cell mass=0
WQ Output cell source sink temp=0
WQ Output cell source sink nsm=0
WQ Output MaxMinRange=-1
WQ Daily Max Min Mean=-1
WQ Daily Range=0
WQ Daily Time=0
WQ Create Restart=0
WQ Fixed Restart=0
WQ System Summary=0
WQ Use Fixed Temperature=0
Sorting and Armoring Iterations= 10
XS Update Threshold= 0.02
Hydraulics Update Threshold= 0.02
Energy Slope Method= 1
Volume Change Method= 0
XS Weighting Method= 0
Number of US Weighted Cross Sections= 1
Number of DS Weighted Cross Sections= 1
Upstream XS Weight=0.25
Main XS Weight=0.5
Downstream XS Weight=0.25
Number of DS XS's Weighted with US Boundary= 1
Upstream Boundary Weight= 1
Weight of XSs Associated with US Boundary= 0
Number of US XS's Weighted with DS Boundary= 1
Downstream Boundary Weight= 0.5
Weight of XSs Associated with DS Boundary= 0.5
Sediment Output Level= 4
Mass or Volume Output= 0
Output Increment Type= 1
Profile and TS Output Increment= 10
XS Output Flag= 0
XS Output Increment= 10
Disregard all LS=0
Disregard all Conn=0
Disregard all Breaches=0
Disregard all Pumps=0

--- WFSJR 003.f01 (steady flow) ---

Flow Title=Multiple
Program Version=4.10
Number of Profiles= 7
Profile Names=10-year,25-year,50-year,1pct_min,100-year,1pct_plu,500-year
River Rch & RM=WFSJR 003,Reach-1         ,8312
     931    1295    1783     806    2435    7354    4702
River Rch & RM=WFSJR 003,Reach-1         ,2513
     946    1313    1803     814    2458    7423    4728
Boundary for River Rch & Prof#=WFSJR 003,Reach-1         , 1
Up Type= 0
Dn Type= 3
Dn Slope=0.007
Boundary for River Rch & Prof#=WFSJR 003,Reach-1         , 2
Up Type= 0
Dn Type= 3
Dn Slope=0.007
Boundary for River Rch & Prof#=WFSJR 003,Reach-1         , 3
Up Type= 0
Dn Type= 3
Dn Slope=0.007
Boundary for River Rch & Prof#=WFSJR 003,Reach-1         , 4
Up Type= 0
Dn Type= 3
Dn Slope=0.007
Boundary for River Rch & Prof#=WFSJR 003,Reach-1         , 5
Up Type= 0
Dn Type= 3
Dn Slope=0.007
Boundary for River Rch & Prof#=WFSJR 003,Reach-1         , 6
Up Type= 0
Dn Type= 3
Dn Slope=0.007
Boundary for River Rch & Prof#=WFSJR 003,Reach-1         , 7
Up Type= 0
Dn Type= 3
Dn Slope=0.007
DSS Import GetInterval= 0
DSS Import GetPeak= 0
DSS Import FillOption= 0

--- WFSJR 003.g01 (geometry) ---

Geom Title=Existing Conditions
Program Version=4.10

River Reach=WFSJR 003       ,Reach-1
Reach XY= 30
      3748508.23     10218836.84      3748522.96     10218533.42
      3748603.81     10218498.36      3748572.86     10218384.45
      3748865.76     10218066.69      3749107.41     10217453.41
      3749029.54     10217340.02      3749245.88     10217016.81
      3749190.23      10216867.7      3749430.14     10216573.19
      3749545.02     10216236.05      3749668.63     10216143.65
       3749508.1     10216068.84      3749588.72      10215731.6
      3749556.25     10215666.67      3749717.33     10215389.47
      3749857.18     10215252.12      3749997.03     10215207.16
      3750146.74     10214954.32      3750078.39     10214483.67
      3750146.37     10214415.13      3750198.64     10214187.34
      3750281.38     10214133.61       3750462.2     10213293.45
      3750408.47     10212828.59      3750304.41     10212716.85
      3750393.97     10212561.61      3750388.12     10212424.86
      3750577.59     10212121.73      3750518.23     10211816.84

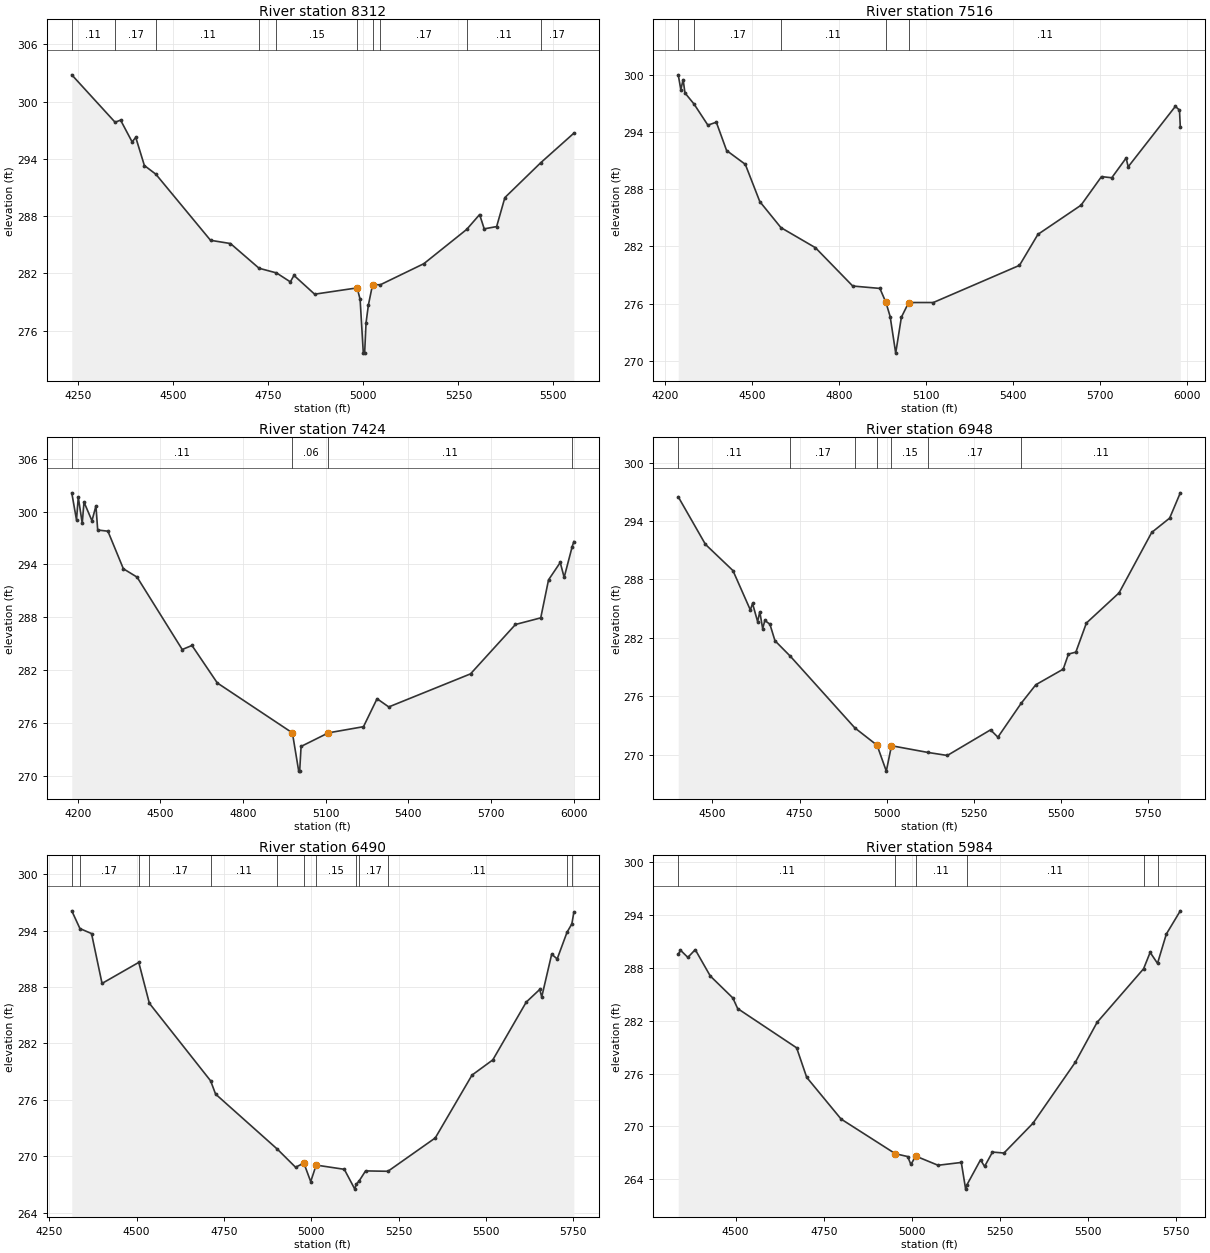
Type RM Length L Ch R = 1 ,8312    ,796,796,796
BEGIN DESCRIPTION:
WFSJR 003 16.0
END DESCRIPTION:
XS GIS Cut Line= 3
      3749201.22     10219020.24      3748982.44     10218916.06
      3747991.14     10218489.73
#Sta/Elev= 30
  4232.5  302.82  4346.5  297.85    4361  298.07  4391.3  295.79  4400.9  296.26
  4423.6  293.31  4453.8   292.4  4597.7  285.47  4650.2  285.13  4725.4  282.54
  4771.3  282.05  4807.8  281.11  4817.3  281.79  4871.7  279.82  4983.5  280.48
  4991.4  279.28  4999.8  273.64  5003.3  273.64    5007  276.82  5013.2  278.69
  5024.1  280.81  5044.7  280.81  5159.2  283.02  5271.8  286.61  5305.9  288.17
    5318  286.67  5350.7  286.91  5372.4  289.95  5466.4  293.59  5553.9   296.7
#Mann= 10 ,-1 , 0
  4232.5     .11       0  4346.5     .17       0  4453.8     .11       0
  4725.4     .17       0  4771.3     .15       0  4983.5     .09       0
  5024.1     .15       0  5044.7     .17       0  5271.8     .11       0
  5466.4     .17       0
Bank Sta=4983.5,5024.1
XS Rating Curve= 0 ,0
Exp/Cntr=0.3,0.1

Type RM Length L Ch R = 1 ,7516    ,92,92,92
BEGIN DESCRIPTION:
WFSJR 003 15.0
END DESCRIPTION:
XS GIS Cut Line= 3
      3749274.12     10218718.16      3748808.83     10218103.56
      3748138.72     10217416.09
#Sta/Elev= 30
  4245.4     300  4254.3  298.46  4262.3  299.49  4268.6   298.1    4300  296.93
  4347.6  294.72  4376.7  295.03  4412.1  292.06  4476.6  290.61  4526.6   286.7
  4599.4  283.97  4718.4  281.86    4847  277.84  4940.6  277.59  4961.4  276.12
    4976  274.64  4995.1   270.8  5014.7  274.57  5039.9  276.11  5124.8  276.11
  5421.9  280.01  5485.4  283.26    5634  286.32  5704.6  289.32    5740   289.2
  5789.5  291.27  5796.6  290.35  5959.2  296.69  5973.4   296.3  5976.3  294.52
#Mann= 5 ,-1 , 0
  4245.4     .11       0    4300     .17       0  4599.4     .11       0
  4961.4     .06       0  5039.9     .11       0
Bank Sta=4961.4,5039.9
XS Rating Curve= 0 ,0
Exp/Cntr=0.3,0.1

Type RM Length L Ch R = 1 ,7424    ,476,476,476
BEGIN DESCRIPTION:
Mapping XS e8d8b705
END DESCRIPTION:
XS GIS Cut Line= 3
      3749472.03     10218600.09      3749173.41     10218367.45
      3748181.92     10217317.02
#Sta/Elev= 30
  4177.9  302.12  4195.1  299.05  4201.5  301.63  4215.9  298.67  4222.3  301.07
  4251.2  298.95  4265.7  300.64    4272   297.9  4309.1  297.77  4365.2  293.51
    4415  292.56    4579  284.35  4614.4  284.81  4706.3  280.56    4979 274.897
  5001.9  270.56  5005.4  270.56  5010.5  273.36  5109.6   274.9  5237.1   275.6
  5286.4  278.77  5328.9  277.84  5625.8  281.59  5788.9  287.19  5880.7  287.94
    5909  292.25  5951.5  294.22  5965.7  292.53    5995  296.03  6000.9  296.59
#Mann= 4 ,-1 , 0
  4177.9     .11       0    4979     .06       0  5109.6     .11       0
    5995     .17       0
Bank Sta=4979,5109.6
XS Rating Curve= 0 ,0
Exp/Cntr=0.3,0.1

Type RM Length L Ch R = 1 ,6948    ,458,458,458
BEGIN DESCRIPTION:
WFSJR 003 14.0
END DESCRIPTION:
XS GIS Cut Line= 3
      3749492.85     10217975.08      3749013.69     10217607.03
      3748312.61     10217152.37
#Sta/Elev= 30
  4401.9  296.49    4480   291.6  4558.8  288.91  4608.7  284.86    4615  285.53
  4629.5  283.67  4635.8  284.67    4644  282.95  4650.3  283.78  4664.8   283.4
  4679.3   281.7  4723.8  280.09  4908.4  272.74  4972.1  270.96  4998.6   268.3
  5013.4  270.91    5118  270.22  5173.6  269.91  5297.5  272.54  5318.6  271.79
  5385.1  275.26  5427.4  277.18  5505.9  278.78    5521  280.33  5542.1  280.53
  5572.4  283.52  5666.1  286.62  5759.7  292.83  5811.1   294.3  5841.7   296.9
#Mann= 7 ,-1 , 0
  4401.9     .11       0  4723.8     .17       0  4908.4     .15       0
  4972.1     .09       0  5013.4     .15       0    5118     .17       0
  5385.1     .11       0
Bank Sta=4972.1,5013.4
XS Rating Curve= 0 ,0
Exp/Cntr=0.3,0.1

Type RM Length L Ch R = 1 ,6490    ,506,506,506
BEGIN DESCRIPTION:
WFSJR 003 13.0
END DESCRIPTION:
XS GIS Cut Line= 3
      3749663.03     10217645.25      3749090.38     10217267.71
      3748421.42     10216923.76
#Sta/Elev= 30
  4314.1  296.12  4337.5  294.23  4370.7   293.7  4400.8  288.39    4506  290.63
  4536.3  286.28  4711.8  278.02    4726  276.61  4903.1  270.74  4955.1  268.82
  4978.9  269.26  4998.5  267.29  5014.1  269.05  5094.7   268.6  5124.8  266.49
  5128.5  266.99  5136.6  267.33  5155.7  268.43  5219.7  268.39  5355.3  271.94
  5460.5  278.63  5520.1  280.25  5615.8   286.4  5654.5  287.75  5660.2  286.95
  5688.7   291.5  5704.5     291  5732.7  293.84  5746.5  294.73  5752.2  295.97
#Mann= 13 ,-1 , 0
  4314.1     .11       0  4337.5     .17       0    4506     .11       0
  4536.3     .17       0  4711.8     .11       0  4903.1     .15       0
  4978.9     .09       0  5014.1     .15       0  5128.5     .15       0
  5136.6     .17       0  5219.7     .11       0  5732.7     .15       0
  5746.5     .11       0
Bank Sta=4978.9,5014.1
XS Rating Curve= 0 ,0
Exp/Cntr=0.3,0.1

Type RM Length L Ch R = 1 ,5984    ,444,444,444
BEGIN DESCRIPTION:
WFSJR 003 12.0
END DESCRIPTION:
XS GIS Cut Line= 3
      3749753.28     10217204.26      3749551.88      10217023.7
       3748503.3     10216541.07
#Sta/Elev= 30
  4337.2  289.53  4343.6  290.01  4364.5  289.19  4385.5  290.07  4428.1  287.08
  4492.2  284.58  4505.8  283.38  4673.2  278.92  4701.7  275.57  4799.3  270.83
  4953.4  266.89  4988.3  266.57  4997.4  265.67  5011.3  266.62  5074.5  265.58
  5140.5   265.9  5152.8  262.87  5156.6  263.37    5195  266.19  5206.6  265.45
    5229  267.08  5261.6  266.97  5343.8  270.35  5464.2  277.29  5525.8  281.81
  5657.8   287.9  5676.4  289.76  5697.3  288.51  5722.3  291.84    5762  294.48
#Mann= 6 ,-1 , 0
  4337.2     .11       0  4953.4     .06       0  5011.3     .11       0
  5156.6     .11       0  5657.8     .15       0  5697.3     .11       0
Bank Sta=4953.4,5011.3
XS Rating Curve= 0 ,0
Exp/Cntr=0.3,0.1

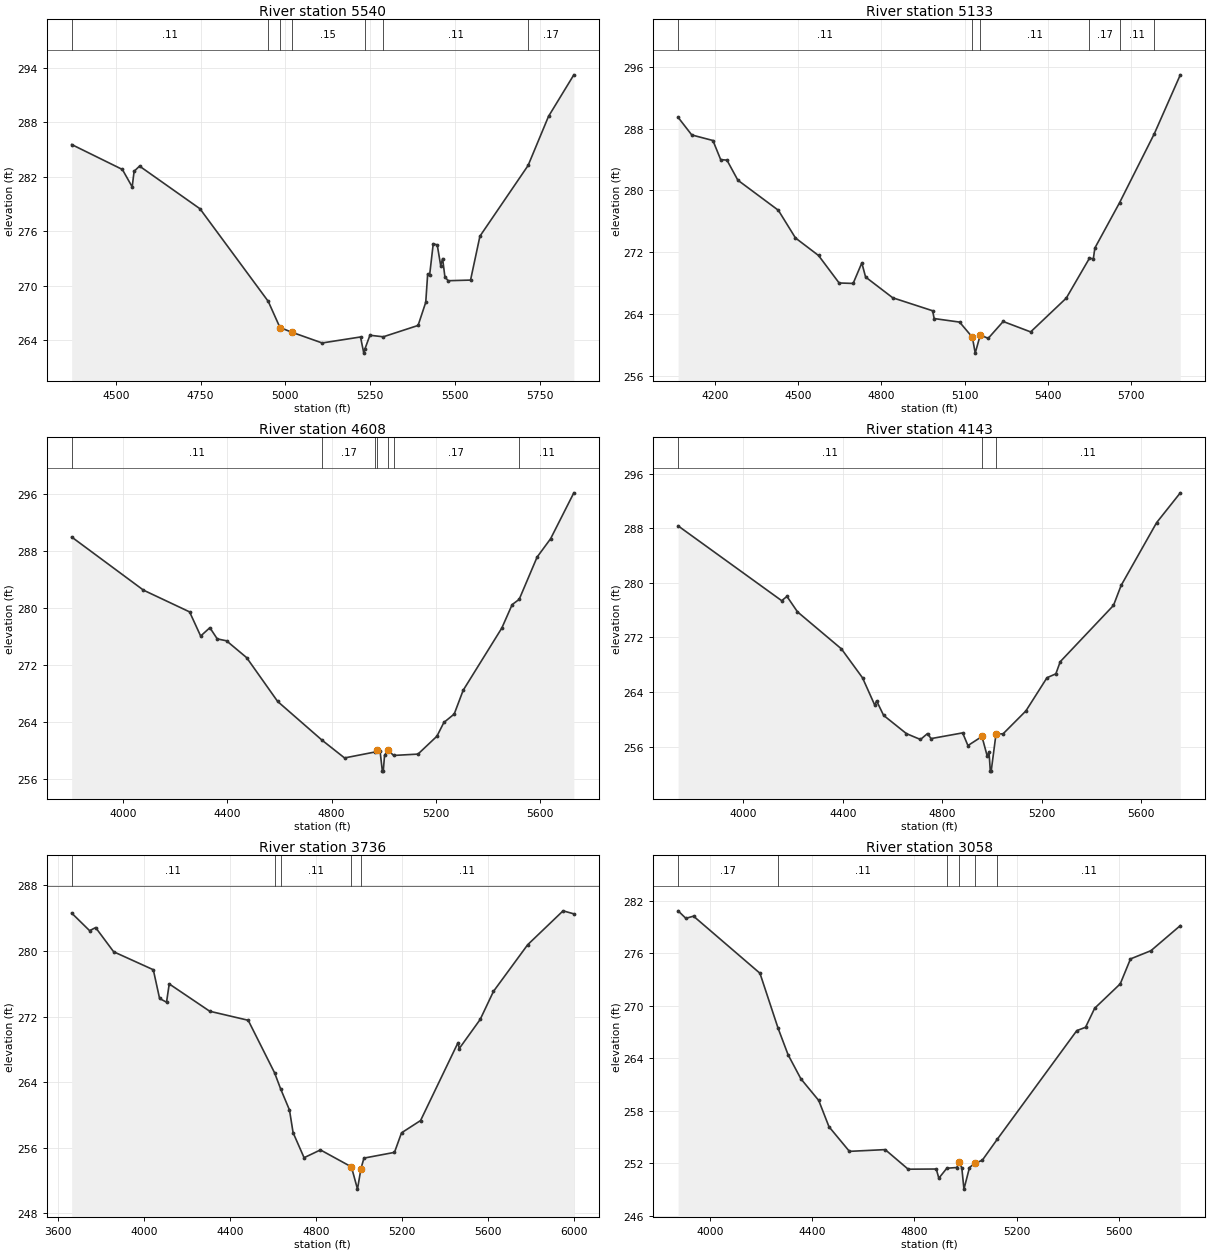
Type RM Length L Ch R = 1 ,5540    ,407,407,407
BEGIN DESCRIPTION:
WFSJR 003 11.0
END DESCRIPTION:
XS GIS Cut Line= 3
      3749840.08     10216971.62      3749642.16     10216617.45
      3748691.85     10216114.54
#Sta/Elev= 30
  4369.6  285.57  4519.2  282.82  4548.1   280.9  4553.8  282.62  4569.8  283.19
    4748  278.49  4949.4  268.28  4983.9   265.4  5018.4  264.89  5108.3   263.7
  5221.4  264.36  5231.1  262.58  5234.8  263.08  5249.2  264.55  5288.6  264.38
  5391.2  265.63  5413.8  268.18  5419.5  271.31  5425.2  271.17  5435.9  274.64
  5447.7   274.5  5457.9  272.22  5463.5     273  5470.3  270.98  5479.9  270.56
  5545.9  270.63  5573.6  275.47  5715.6  283.26  5775.8  288.67  5850.5  293.25
#Mann= 7 ,-1 , 0
  4369.6     .11       0  4949.4     .15       0  4983.9     .09       0
  5018.4     .15       0  5234.8     .15       0  5288.6     .11       0
  5715.6     .17       0
Bank Sta=4983.9,5018.4
XS Rating Curve= 0 ,0
Exp/Cntr=0.3,0.1

Type RM Length L Ch R = 1 ,5133    ,525,525,525
BEGIN DESCRIPTION:
WFSJR 003 10.0
END DESCRIPTION:
XS GIS Cut Line= 3
      3750472.01     10216593.14      3749634.92     10216181.11
      3748837.34      10215815.7
#Sta/Elev= 30
    4067  289.47  4116.2  287.19  4192.4  286.47  4220.5  283.99    4243  283.93
  4282.3  281.33  4428.3  277.43  4490.1  273.84  4573.2  271.57  4647.4  268.01
  4697.9  267.95  4729.2  270.61  4742.8  268.78  4840.7  266.09  4984.4  264.41
    4990   263.4  5081.7  262.94  5127.7  260.98    5138  258.92  5156.2  261.28
  5184.7  260.83  5238.8  263.02  5337.8  261.67  5466.3  266.05  5549.8  271.22
  5563.8  271.14  5569.3  272.54  5658.2   278.4  5783.9  287.37  5877.3  294.98
#Mann= 6 ,-1 , 0
    4067     .11       0  5127.7     .06       0  5156.2     .11       0
  5549.8     .17       0  5658.2     .11       0  5783.9     .17       0
Bank Sta=5127.7,5156.2
XS Rating Curve= 0 ,0
Exp/Cntr=0.3,0.1

Type RM Length L Ch R = 1 ,4608    ,465,465,465
BEGIN DESCRIPTION:
WFSJR 003 9.0
END DESCRIPTION:
XS GIS Cut Line= 3
       3750558.8     10216409.08      3750121.33     10215957.72
      3748872.07     10215614.18
#Sta/Elev= 30
  3803.9  289.96  4079.1   282.5  4255.8  279.45  4298.2  276.06  4333.5  277.23
  4361.8  275.66  4397.3  275.39  4474.4  273.03  4593.2  266.88  4763.1  261.45
  4849.6  258.95  4966.9  259.79  4975.4  260.12  4985.7  259.89  4994.4   257.1
  4997.9   257.1  5002.9  259.34  5016.9  260.04  5037.3   259.3  5130.9  259.49
  5203.5     262  5230.1  263.93  5269.7  265.11  5304.1  268.45  5452.1  277.18
  5491.7  280.47  5518.7  281.21  5587.3  287.14  5639.1  289.72  5728.1  296.16
#Mann= 7 ,-1 , 0
  3803.9     .11       0  4763.1     .17       0  4966.9     .11       0
  4975.4     .06       0  5016.9     .11       0  5037.3     .17       0
  5518.7     .11       0
Bank Sta=4975.4,5016.9
XS Rating Curve= 0 ,0
Exp/Cntr=0.3,0.1

Type RM Length L Ch R = 1 ,4143    ,407,407,407
BEGIN DESCRIPTION:
WFSJR 003 8.0
END DESCRIPTION:
XS GIS Cut Line= 3
      3750607.45     10216291.07      3749534.52     10215227.51
      3749034.49     10215124.38
#Sta/Elev= 30
  3737.2  288.36  4154.1  277.39  4175.3  278.02  4217.7  275.75  4394.5  270.32
  4479.4  266.08  4528.9  262.05    4536   262.7  4564.3  260.57  4656.2  257.89
  4712.7  257.03    4741   257.9  4755.2  257.16  4882.4     258  4903.7  256.14
  4960.2  257.47  4981.4  254.58  4988.5  255.21  4993.8  252.39  4997.3  252.39
  5016.8  257.86  5045.1  257.86    5137  261.22  5221.9  266.09  5257.5  266.66
  5275.2  268.44  5489.6   276.7  5520.2  279.62  5663.2  288.84  5758.5  293.21
#Mann= 3 , 0 , 0
  3737.2     .11       0  4960.2     .06       0  5016.8     .11       0
Bank Sta=4960.2,5016.8
XS Rating Curve= 0 ,0
Exp/Cntr=0.3,0.1

Type RM Length L Ch R = 1 ,3736    ,678,678,678
BEGIN DESCRIPTION:
WFSJR 003 7.0
END DESCRIPTION:
XS GIS Cut Line= 3
      3750822.71     10216166.04      3750417.85     10215361.07
      3749124.95     10214745.99
#Sta/Elev= 30
  3665.1  284.62  3748.6  282.47  3776.5  282.85  3860.2   279.9  4044.4  277.71
  4073.6  274.21  4105.8  273.75  4118.4  275.98  4306.6  272.65  4485.2  271.55
  4607.9  265.14  4635.7   263.2  4676.9  260.62  4693.8  257.85  4744.8   254.8
  4820.8  255.75  4964.8  253.68  4992.9  250.97  5009.1  253.48  5022.9  254.75
  5164.7  255.45  5197.4  257.83  5285.9  259.33    5460  268.83  5465.5   268.1
  5562.8  271.65  5624.5  275.07  5783.5  280.76    5948  284.89  5997.9  284.52
#Mann= 5 ,-1 , 0
  3665.1     .11       0  4607.9     .17       0  4635.7     .11       0
  4964.8     .06       0  5009.1     .11       0
Bank Sta=4964.8,5009.1
XS Rating Curve= 0 ,0
Exp/Cntr=0.3,0.1

Type RM Length L Ch R = 1 ,3058    ,545,545,545
BEGIN DESCRIPTION:
WFSJR 003 6.0
END DESCRIPTION:
XS GIS Cut Line= 2
      3751208.17     10214575.78      3749242.82     10214551.47
#Sta/Elev= 30
  3875.6  280.85  3905.9  279.99  3935.9  280.24  4195.9  273.71  4266.9  267.42
    4306  264.39    4356  261.64    4426  259.16    4466  256.16    4546  253.34
    4686  253.54    4776   251.3    4886  251.32    4896  250.27  4927.3  251.41
    4966  251.49    4976  252.12    4986  251.43  4994.3  249.02    5016  251.49
    5036  251.96    5066  252.32  5124.6  254.72    5436  267.15  5470.2  267.53
    5506  269.71  5606.1   272.5  5646.1  275.35  5726.1  276.29  5841.1  279.16
#Mann= 6 ,-1 , 0
  3875.6     .17       0  4266.9     .11       0  4927.3     .15       0
    4976     .09       0    5036     .15       0  5124.6     .11       0
Bank Sta=4976,5036
XS Rating Curve= 0 ,0
Exp/Cntr=0.3,0.1

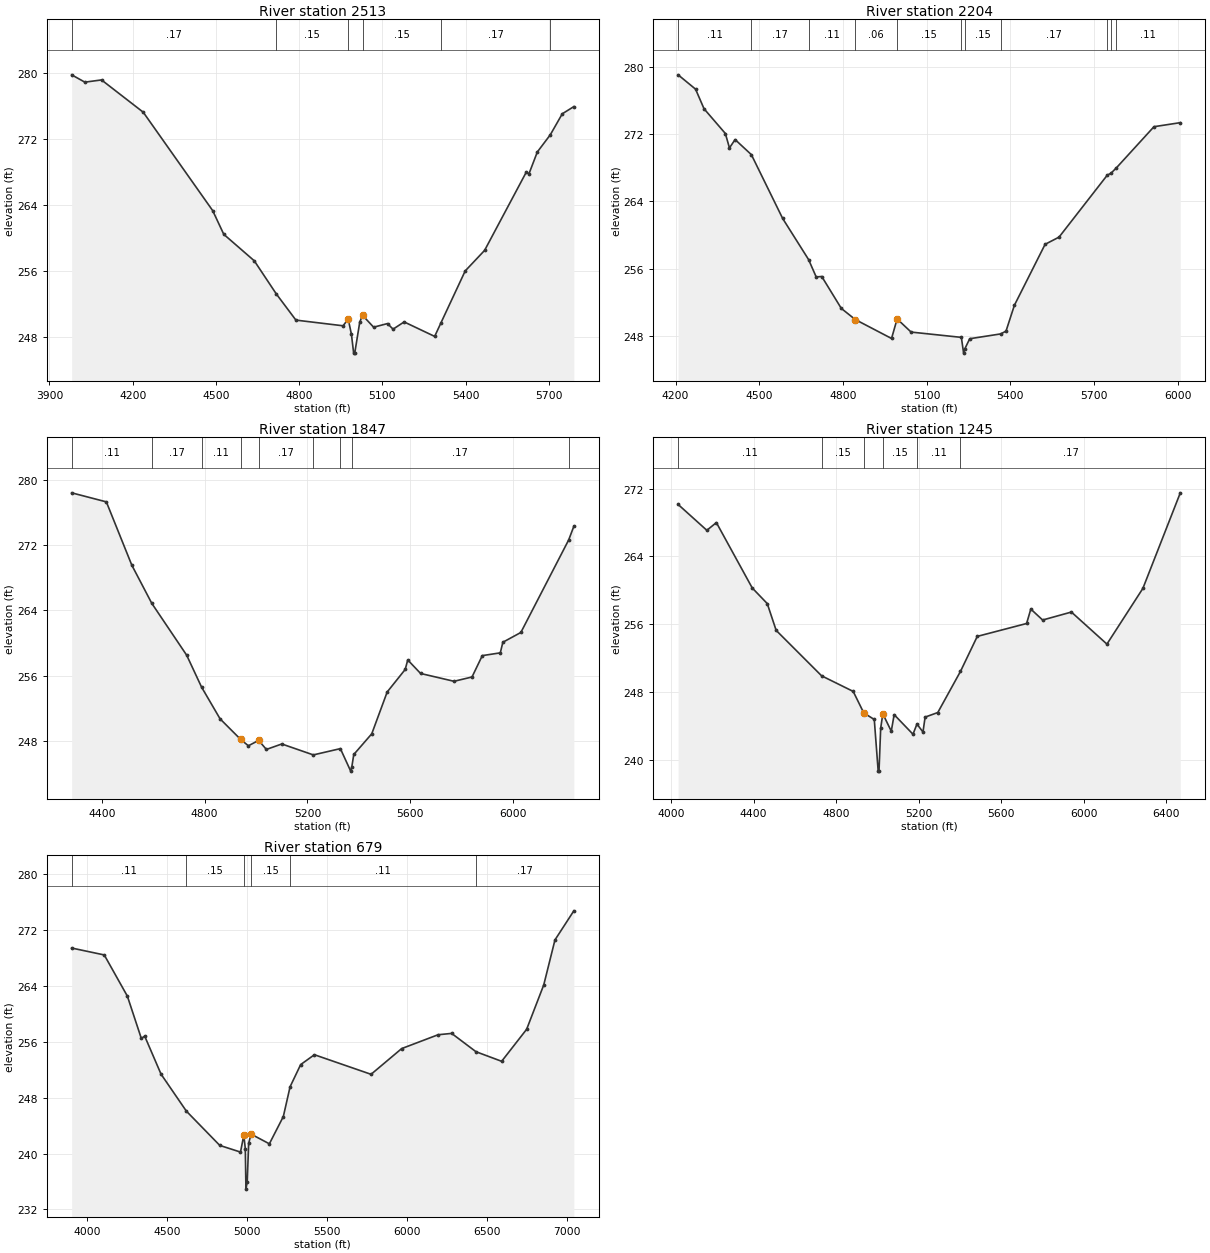
Type RM Length L Ch R = 1 ,2513    ,309,309,309
BEGIN DESCRIPTION:
WFSJR 003 5.0
END DESCRIPTION:
XS GIS Cut Line= 3
      3751305.36     10214131.34      3750926.88     10214107.03
      3749496.29     10214127.86
#Sta/Elev= 30
    3980  279.79  4027.6   278.9  4087.7  279.17    4238  275.25  4488.3   263.3
  4528.3  260.42  4638.3   257.2  4717.4  253.19  4788.3     250  4958.3  249.31
  4976.8  250.13  4988.4  248.27  4996.4  245.99  5000.3  245.99  5018.4  249.76
  5028.4  250.58  5068.4  249.14  5118.4  249.58  5138.4   248.9  5178.4  249.78
  5288.4  248.02  5310.1   249.6  5398.4  255.97  5468.4  258.47  5618.4  267.96
  5628.4  267.78  5658.4  270.42  5705.2  272.51  5748.4  275.06    5790  275.93
#Mann= 6 ,-1 , 0
    3980     .17       0  4717.4     .15       0  4976.8     .09       0
  5028.4     .15       0  5310.1     .17       0  5705.2     .11       0
Bank Sta=4976.8,5028.4
XS Rating Curve= 0 ,0
Exp/Cntr=0.3,0.1

Type RM Length L Ch R = 1 ,2204    ,357,357,357
BEGIN DESCRIPTION:
WFSJR 003 4.0
END DESCRIPTION:
XS GIS Cut Line= 3
      3751139.59     10213832.73       3750899.1     10213794.53
      3749343.53     10213853.56
#Sta/Elev= 30
  4209.2  279.02  4271.7  277.32  4302.1  274.99  4378.6  272.05  4393.2  270.34
  4413.5  271.33  4471.8  269.54    4584  261.96  4676.9  257.08  4704.1  255.02
  4724.1  255.07  4794.2  251.28  4844.2  249.96  4974.3  247.71  4994.3  250.03
  5044.4  248.47  5224.6  247.84  5232.6  245.97  5236.8  246.47  5254.5  247.68
  5365.1  248.25  5384.6  248.58  5414.6  251.65  5524.7  258.89  5574.8  259.75
  5747.7  267.11  5760.8  267.33  5780.2  267.97    5915  272.86  6009.4  273.34
#Mann= 11 ,-1 , 0
  4209.2     .11       0  4471.8     .17       0  4676.9     .11       0
  4844.2     .06       0  4994.3     .15       0  5224.6     .15       0
  5236.8     .15       0  5365.1     .17       0  5747.7     .11       0
  5760.8     .17       0  5780.2     .11       0
Bank Sta=4844.2,4994.3
XS Rating Curve= 0 ,0
Exp/Cntr=0.3,0.1

Type RM Length L Ch R = 1 ,1847    ,602,602,602
BEGIN DESCRIPTION:
WFSJR 003 3.0
END DESCRIPTION:
XS GIS Cut Line= 3
      3751139.56     10213520.22      3750909.52     10213468.14
      3749191.79      10213461.2
#Sta/Elev= 30
  4282.8  278.43  4417.8  277.32  4516.9  269.55  4594.6  264.87  4730.3  258.51
  4788.3  254.59  4860.3   250.7  4940.3  248.18  4970.3   247.4  5010.3  248.06
  5040.3  246.95  5100.3  247.62    5223  246.28  5328.2  247.05  5368.3  244.29
  5372.6  244.79  5380.3  246.33  5450.3  248.87  5510.3     254  5580.3  256.76
  5590.3  257.93  5640.3  256.27  5770.3  255.31  5840.3  255.84  5880.3  258.46
  5950.3   258.8  5960.3   260.1  6030.3   261.3  6216.3  272.65  6236.4  274.32
#Mann= 9 ,-1 , 0
  4282.8     .11       0  4594.6     .17       0  4788.3     .11       0
  4940.3     .06       0  5010.3     .17       0    5223     .15       0
  5328.2     .17       0  5372.6     .17       0  6216.3     .11       0
Bank Sta=4940.3,5010.3
XS Rating Curve= 0 ,0
Exp/Cntr=0.3,0.1

Type RM Length L Ch R = 1 ,1245    ,566,566,566
BEGIN DESCRIPTION:
WFSJR 003 2.0
END DESCRIPTION:
XS GIS Cut Line= 3
      3751287.96     10213103.54      3750767.16       10212798.
      3748980.89     10213203.82
#Sta/Elev= 30
  4033.9  270.13  4173.2  267.08  4219.5  267.99  4393.4  260.28  4466.2  258.44
  4509.4  255.28  4729.8  249.92  4883.1  248.08  4934.4  245.54  4985.3  244.77
  5004.2  238.68  5008.2  238.68  5016.4  243.75  5026.7  245.44  5067.7  243.39
  5081.7  245.34    5173  243.03  5192.3  244.23  5221.5  243.29  5231.8  245.05
  5293.3  245.59  5403.3  250.44  5484.8  254.57    5724  256.09  5744.5  257.79
  5801.8   256.5  5941.3  257.44  6113.6  253.66    6288  260.23  6469.5   271.5
#Mann= 6 ,-1 , 0
  4033.9     .11       0  4729.8     .15       0  4934.4     .09       0
  5026.7     .15       0  5192.3     .11       0  5403.3     .17       0
Bank Sta=4934.4,5026.7
XS Rating Curve= 0 ,0
Exp/Cntr=0.3,0.1

Type RM Length L Ch R = 1 ,679     ,0,0,0
BEGIN DESCRIPTION:
WFSJR 003 1.0
END DESCRIPTION:
XS GIS Cut Line= 3
      3751326.15     10213006.31      3750077.67     10212185.87
      3748802.35     10213231.64
#Sta/Elev= 30
  3901.4  269.39  4105.5   268.4  4250.1  262.51  4337.5  256.46  4358.6  256.79
    4461  251.35  4619.6  246.06  4828.6  241.16  4958.2  240.21 4978.99242.6235
  4988.3   240.7  4992.3  234.91  5000.3  235.98  5009.4  241.46  5024.2  242.78
  5138.9  241.39  5226.3  245.29  5268.6  249.55  5334.8  252.72  5420.8  254.13
  5775.4  251.33    5967  255.01  6195.2  256.99  6279.9  257.18  6432.1  254.56
  6592.8  253.19  6749.2  257.77  6856.2  264.11  6926.5  270.55  7044.6  274.71
#Mann= 6 ,-1 , 0
  3901.4     .11       0  4619.6     .15       0 4978.99     .09       0
  5024.2     .15       0  5268.6     .11       0  6432.1     .17       0
Bank Sta=4978.99,5024.2
XS Rating Curve= 0 ,0
Exp/Cntr=0.3,0.1

Chan Stop Cuts=-1
Use User Specified Reach Order=0
Composite Channel Slope=5