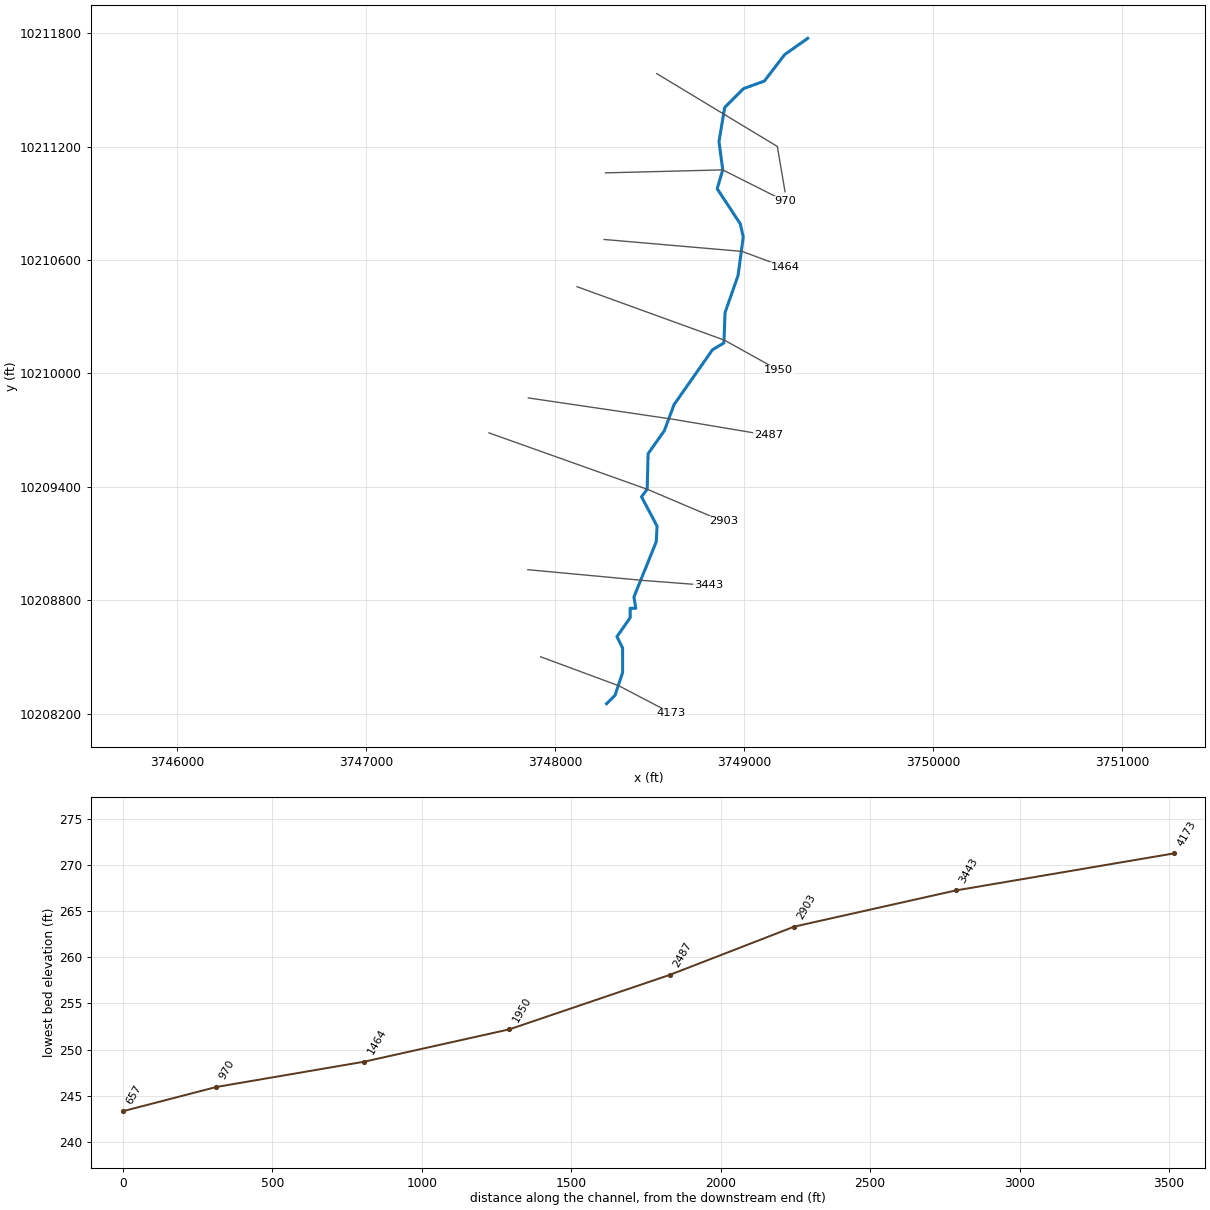
--- WFSJR 004.prj (project) ---

Proj Title=WFSJR 004 Base Level Engineering
Current Plan=p01
Default Exp/Contr=0.3,0.1
English Units
Geom File=g01
Flow File=f01
Plan File=p01
Y Axis Title=Elevation
X Axis Title(PF)=Main Channel Distance
X Axis Title(XS)=Station
BEGIN DESCRIPTION:
WFSJR 004
END DESCRIPTION:
DSS Export Rating Curves= 0
DSS Export Rating Curve Sorted= 0
DSS Export Volume Flow Curves= 0
DXF OffsetX= 0
DXF OffsetY= 0
DXF ScaleX= 1
DXF ScaleY= 10

--- WFSJR 004.p01 (plan) ---

Plan Title=Multiple Run
Program Version=4.10
Short Identifier=Multiple
Geom File=g01
Flow File=f01
Subcritical Flow
K Sum by GR= 0
Std Step Tol= 0.01
Critical Tol= 0.01
Num of Std Step Trials= 20
Max Error Tol= 0.3
Flow Tol Ratio= 0.001
Split Flow NTrial= 30
Split Flow Tol= 0.02
Split Flow Ratio= 0.02
Log Output Level= 0
Friction Slope Method= 1
Unsteady Friction Slope Method= 2
Unsteady Bridges Friction Slope Method= 1
Parabolic Critical Depth
Global Vel Dist= 1 , 1 , 1
Global Log Level= 0
CheckData=True
Encroach Param=-1 ,0,0, 0
BEGIN DESCRIPTION:
Multiple Run
END DESCRIPTION:
Computation Interval=1HOUR
Output Interval=1HOUR
Run HTab= 0
Run UNet= 0
Run PostProcess= 0
Run WQNet= 0
UNET Theta= 1
UNET Theta Warmup= 1
UNET ZTol= 0.02
UNET ZSATol= 0.05
UNET MxIter= 20
UNET MaxInSteps= 0
UNET DtIC= 0
UNET DtMin= 0
UNET MaxCRTS= 20
UNET WFStab= 2
UNET SFStab= 1
UNET WFX= 1
UNET SFX= 1
UNET DSS MLevel= 4
UNET DZMax Abort= 100
UNET Convert EG Bridges= 0
UNET Use Existing IB Tables=-1
UNET Froude Reduction=False
UNET Froude Limit= 1
UNET Froude Power= 10
UNET Time Slicing=0,0, 5
UNET Junction Losses=0
Instantaneous Interval=1HOUR
Write IC File= 0
Write IC File at Sim End=0
Echo Input=False
Echo Parameters=False
Echo Output=False
Write Detailed= 0
WQ AD Non Conservative
WQ ULTIMATE=-1
WQ Max Comp Step=1HOUR
WQ Output Interval=15MIN
WQ Output Selected Increments= 0
WQ Output face flow=0
WQ Output face velocity=0
WQ Output face area=0
WQ Output face dispersion=0
WQ Output cell volume=0
WQ Output cell surface area=0
WQ Output cell continuity=0
WQ Output cumulative cell continuity=0
WQ Output face conc=0
WQ Output face dconc_dx=0
WQ Output face courant=0
WQ Output face peclet=0
WQ Output face adv mass=0
WQ Output face disp mass=0
WQ Output cell mass=0
WQ Output cell source sink temp=0
WQ Output cell source sink nsm=0
WQ Output MaxMinRange=-1
WQ Daily Max Min Mean=-1
WQ Daily Range=0
WQ Daily Time=0
WQ Create Restart=0
WQ Fixed Restart=0
WQ System Summary=0
WQ Use Fixed Temperature=0
Sorting and Armoring Iterations= 10
XS Update Threshold= 0.02
Hydraulics Update Threshold= 0.02
Energy Slope Method= 1
Volume Change Method= 0
XS Weighting Method= 0
Number of US Weighted Cross Sections= 1
Number of DS Weighted Cross Sections= 1
Upstream XS Weight=0.25
Main XS Weight=0.5
Downstream XS Weight=0.25
Number of DS XS's Weighted with US Boundary= 1
Upstream Boundary Weight= 1
Weight of XSs Associated with US Boundary= 0
Number of US XS's Weighted with DS Boundary= 1
Downstream Boundary Weight= 0.5
Weight of XSs Associated with DS Boundary= 0.5
Sediment Output Level= 4
Mass or Volume Output= 0
Output Increment Type= 1
Profile and TS Output Increment= 10
XS Output Flag= 0
XS Output Increment= 10
Disregard all LS=0
Disregard all Conn=0
Disregard all Breaches=0
Disregard all Pumps=0

--- WFSJR 004.f01 (steady flow) ---

Flow Title=Multiple
Program Version=4.10
Number of Profiles= 7
Profile Names=10-year,25-year,50-year,1pct_min,100-year,1pct_plu,500-year
River Rch & RM=WFSJR 004,Reach-1         ,4173
     651     888    1208     540    1632    4929    3081
Boundary for River Rch & Prof#=WFSJR 004,Reach-1         , 1
Up Type= 0
Dn Type= 3
Dn Slope=0.008
Boundary for River Rch & Prof#=WFSJR 004,Reach-1         , 2
Up Type= 0
Dn Type= 3
Dn Slope=0.008
Boundary for River Rch & Prof#=WFSJR 004,Reach-1         , 3
Up Type= 0
Dn Type= 3
Dn Slope=0.008
Boundary for River Rch & Prof#=WFSJR 004,Reach-1         , 4
Up Type= 0
Dn Type= 3
Dn Slope=0.008
Boundary for River Rch & Prof#=WFSJR 004,Reach-1         , 5
Up Type= 0
Dn Type= 3
Dn Slope=0.008
Boundary for River Rch & Prof#=WFSJR 004,Reach-1         , 6
Up Type= 0
Dn Type= 3
Dn Slope=0.008
Boundary for River Rch & Prof#=WFSJR 004,Reach-1         , 7
Up Type= 0
Dn Type= 3
Dn Slope=0.008
DSS Import GetInterval= 0
DSS Import GetPeak= 0
DSS Import FillOption= 0

--- WFSJR 004.g01 (geometry) ---

Geom Title=Existing Conditions
Program Version=4.10

River Reach=WFSJR 004       ,Reach-1
Reach XY= 30
      3748273.23     10208251.84      3748318.23     10208296.84
      3748358.23     10208416.84      3748358.23     10208546.84
      3748328.23     10208606.84      3748398.23     10208706.84
      3748398.23     10208756.84      3748428.23     10208756.84
      3748418.23     10208816.84      3748536.25     10209109.09
      3748540.58      10209192.1      3748458.23     10209346.84
      3748488.23     10209386.84      3748493.27     10209575.16
       3748579.2     10209696.69      3748630.42     10209834.71
      3748834.41     10210125.51      3748894.31      10210161.1
      3748900.38     10210321.69      3748968.96       10210517.
      3748996.74     10210721.86      3748981.11     10210791.31
      3748858.72     10210977.07      3748888.23     10211076.84
      3748868.23     10211226.84      3748898.23     10211406.84
      3748998.23     10211506.84      3749108.23     10211546.84
      3749215.67     10211686.75       3749337.9     10211773.01

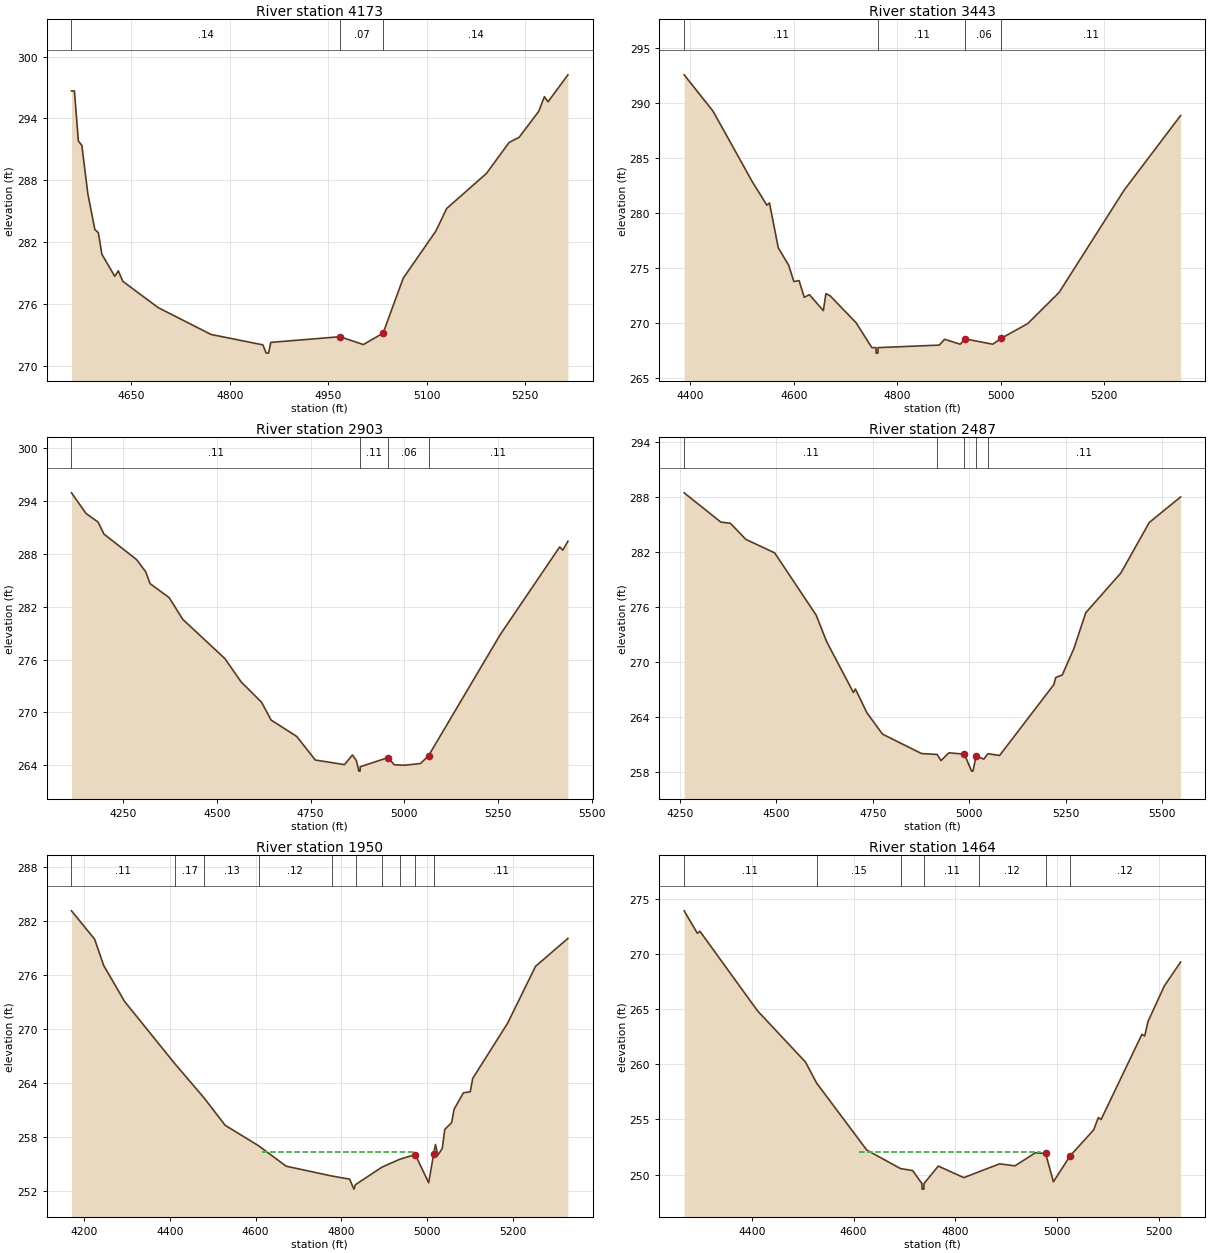
Type RM Length L Ch R = 1 ,4173    ,730,730,730
BEGIN DESCRIPTION:
WFSJR 004 8.0
END DESCRIPTION:
XS GIS Cut Line= 3
      3747924.46     10208500.27      3748338.23     10208346.84
       3748617.2     10208200.78
#Sta/Elev= 30
  4558.7  296.67  4563.2  296.67  4569.2  291.81  4574.5   291.4  4583.6  286.71
  4594.3  283.24  4599.6  282.94    4605  280.85  4624.6  278.71    4630  279.24
    4637  278.22  4690.7  275.68  4771.2  273.08  4850.3  272.07  4855.3  271.27
  4858.8  271.27  4862.3  272.31  4967.6  272.86  5003.4   272.1  5033.4  273.21
    5064  278.53  5113.8   283.1  5130.2  285.28  5190.8  288.68  5225.3  291.68
  5240.5  292.17  5270.5   294.7    5279  296.11  5284.7  295.62  5314.9  298.23
#Mann= 3 , 0 , 0
  4558.7     .14       0  4967.6     .07       0  5033.4     .14       0
Bank Sta=4967.6,5033.4
XS Rating Curve= 0 ,0
Exp/Cntr=0.3,0.1

Type RM Length L Ch R = 1 ,3443    ,540,540,540
BEGIN DESCRIPTION:
WFSJR 004 7.0
END DESCRIPTION:
XS GIS Cut Line= 3
      3747856.75      10208961.2      3748471.37      10208903.9
      3748812.49     10208877.86
#Sta/Elev= 30
  4388.2  292.53    4444  289.23  4519.9  282.82  4548.1  280.69  4553.1  280.89
  4570.1  276.82  4590.2  275.23  4600.2  273.75  4610.3  273.84  4620.3  272.32
  4630.3  272.56  4657.2  271.11  4662.2  272.66  4670.5  272.45  4720.7     270
  4750.9  267.75  4758.9  267.75  4759.2  267.25  4762.7  267.25  4762.9  267.75
  4881.4  267.98  4891.5  268.51  4921.6  268.06  4931.6  268.54  4984.5  268.06
  5001.2   268.6  5052.1  269.93  5112.8  272.76  5238.7  282.07  5347.6  288.83
#Mann= 4 ,-1 , 0
  4388.2     .11       0  4762.9     .11       0  4931.6     .06       0
  5001.2     .11       0
Bank Sta=4931.6,5001.2
XS Rating Curve= 0 ,0
Exp/Cntr=0.3,0.1

Type RM Length L Ch R = 1 ,2903    ,416,416,416
BEGIN DESCRIPTION:
WFSJR 004 6.0
END DESCRIPTION:
XS GIS Cut Line= 3
      3747651.09     10209685.14      3748488.23     10209386.84
      3748890.62     10209216.41
#Sta/Elev= 30
  4111.3  294.92  4150.3  292.57  4182.2  291.61    4198  290.24  4285.2  287.34
  4309.6  285.95  4321.3  284.61  4372.3  283.02  4408.4  280.56  4521.1   276.1
  4564.3  273.46  4618.9  271.15  4644.4  269.13    4713  267.26  4762.4  264.59
  4840.4  264.07  4861.6  265.17  4872.2  264.52  4878.6  263.33  4882.1  263.33
  4882.3  263.83  4957.1  264.87  4972.8  264.06    5000     264    5043  264.19
  5064.7  265.07  5256.6  278.85    5415  288.78  5423.1  288.41    5437  289.43
#Mann= 4 ,-1 , 0
  4111.3     .11       0  4882.3     .11       0  4957.1     .06       0
  5064.7     .11       0
Bank Sta=4957.1,5064.7
XS Rating Curve= 0 ,0
Exp/Cntr=0.3,0.1

Type RM Length L Ch R = 1 ,2487    ,537,537,537
BEGIN DESCRIPTION:
WFSJR 004 5.0
END DESCRIPTION:
XS GIS Cut Line= 3
       3747859.4     10209870.05      3748619.81     10209758.07
      3749130.21     10209672.14
#Sta/Elev= 30
  4261.3  288.49  4356.5  285.29    4381  285.17  4421.1  283.41  4495.9  281.93
  4603.4  275.13  4630.2  272.26  4699.9  266.68    4705  267.07  4734.8  264.47
  4775.2  262.14  4876.3  260.02  4916.8  259.92  4926.9  259.25  4947.1   260.1
  4987.5  259.95    5006   258.1  5009.5   258.1  5017.8  259.76  5037.5  259.41
  5048.2     260  5078.6  259.81  5219.1  267.55  5224.2  268.33  5240.9   268.6
  5271.3  271.51  5301.7  275.39    5393  279.75  5466.3  285.25  5547.5  288.04
#Mann= 5 ,-1 , 0
  4261.3     .11       0  4916.8     .11       0  4987.5     .06       0
  5017.8     .11       0  5048.2     .11       0
Bank Sta=4987.5,5017.8
XS Rating Curve= 0 ,0
Exp/Cntr=0.3,0.1

Type RM Length L Ch R = 1 ,1950    ,486,486,486
BEGIN DESCRIPTION:
WFSJR 004 4.0
END DESCRIPTION:
XS GIS Cut Line= 3
      3748117.19      10210458.6      3748896.91     10210175.86
      3749183.74     10210016.54
#Sta/Elev= 30
  4170.6  283.16  4224.5  280.01  4245.8  277.07  4294.5  273.07  4411.4  266.16
  4479.8  262.34  4528.8   259.3  4607.4     257  4671.2  254.74  4777.6  253.65
  4819.1   253.3  4829.1  252.19  4832.8  252.69  4894.6  254.64  4936.3  255.52
  4972.2  256.03  5003.4   252.9    5015 256.088  5019.2  257.16  5024.9  255.98
  5035.2  256.73  5040.9  258.83  5056.9  259.59  5062.7  261.08  5084.4  262.91
  5100.4  263.03  5106.1  264.51  5187.4  270.65  5252.7  276.99  5328.1  280.09
#Mann= 10 ,-1 , 0
  4170.6     .11       0  4411.4     .17       0  4479.8     .13       0
  4607.4     .12       0  4777.6     .11       0  4832.8     .11       0
  4894.6     .11       0  4936.3     .11       0  4972.2     .07       0
    5015     .11       0
#XS Ineff= 2 ,-1
    4615  4966.9  256.35  5019.2    5040  257.16
Permanent Ineff=
       T       F
Bank Sta=4972.2,5015
XS Rating Curve= 0 ,0
Exp/Cntr=0.3,0.1

Type RM Length L Ch R = 1 ,1464    ,494,494,494
BEGIN DESCRIPTION:
WFSJR 004 3.0
END DESCRIPTION:
XS GIS Cut Line= 3
      3748260.39      10210708.6      3748990.66     10210645.47
      3749217.89     10210561.06
#Sta/Elev= 30
    4267  273.89  4292.9  271.86    4298  272.04  4411.2  264.83  4505.4  260.19
  4527.4  258.28  4625.8  252.22  4692.2  250.54  4716.1  250.36  4734.2  249.18
  4734.5  248.68    4738  248.68  4738.2  249.18  4766.3  250.77  4816.5  249.72
  4846.6  250.26  4886.8  250.97  4916.9  250.79    4957  251.97  4977.1  251.91
  4992.6  249.35  5025.3  251.69  5071.7  254.05  5080.7  255.16  5086.1  254.98
  5166.5  262.71  5171.8  262.54  5178.4  263.87  5210.4  267.08  5242.4  269.25
#Mann= 7 ,-1 , 0
    4267     .11       0  4527.4     .15       0  4692.2     .13       0
  4738.2     .11       0  4846.6     .12       0  4977.1     .07       0
  5025.3     .12       0
#XS Ineff= 1 ,-1
    4610  4967.1  252.06
Permanent Ineff=
       T
Bank Sta=4977.1,5025.3
XS Rating Curve= 0 ,0
Exp/Cntr=0.3,0.1

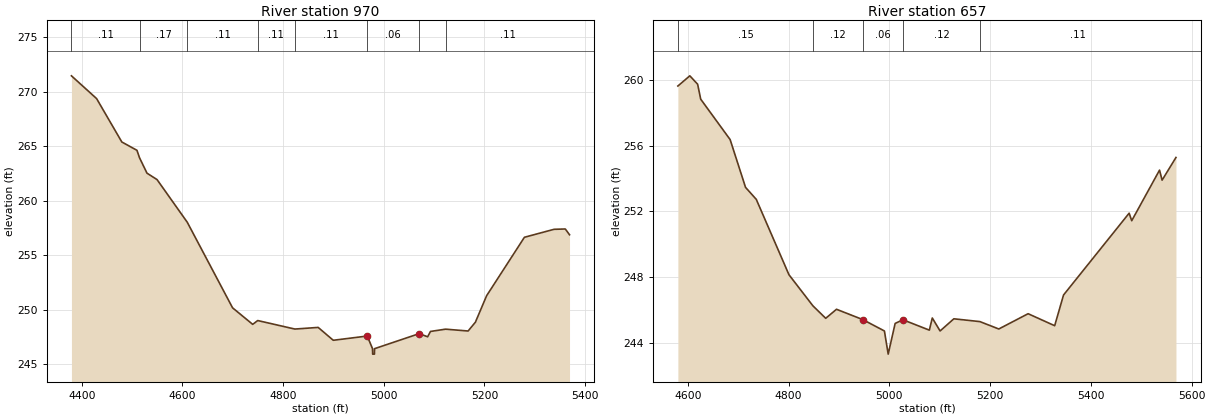
Type RM Length L Ch R = 1 ,970     ,313,313,313
BEGIN DESCRIPTION:
WFSJR 004 2.0
END DESCRIPTION:
XS GIS Cut Line= 3
      3748267.83     10211061.07      3748888.23     10211076.84
      3749217.89     10210911.05
#Sta/Elev= 30
  4379.4  271.47  4429.4  269.38  4479.5   265.4  4509.5  264.64  4514.7  263.95
  4529.5  262.54  4549.5  261.95  4609.5  258.04  4699.5  250.19  4739.5  248.67
  4749.5  249.02  4823.3  248.24  4869.6  248.39  4899.6  247.21  4967.1   247.6
  4977.6  246.44  4977.9  245.94  4981.4  245.94  4981.6  246.44  5070.4  247.82
  5087.1  247.53  5092.7  248.02  5122.7  248.23  5167.5  248.06    5182  248.87
  5204.3   251.3  5279.4  256.66  5338.3  257.39  5360.6  257.42    5369  256.89
#Mann= 8 ,-1 , 0
  4379.4     .11       0  4514.7     .17       0  4609.5     .11       0
  4749.5     .11       0  4823.3     .11       0  4967.1     .06       0
  5070.4     .11       0  5122.7     .11       0
Bank Sta=4967.1,5070.4
XS Rating Curve= 0 ,0
Exp/Cntr=0.3,0.1

Type RM Length L Ch R = 1 ,657     ,0,0,0
BEGIN DESCRIPTION:
WFSJR 004 1.0
END DESCRIPTION:
XS GIS Cut Line= 3
      3748539.07      10211586.2       3749177.1     10211200.78
      3749217.84     10210961.12
#Sta/Elev= 30
  4580.4  259.63  4604.1  260.25  4619.6  259.74  4625.7  258.83  4684.1  256.37
  4714.7  253.46    4736  252.73  4800.9  248.14  4848.4  246.25  4873.8  245.49
  4895.2  246.04  4947.5  245.41  4990.3  244.72  4997.8  243.31  5011.6  245.18
  5027.1   245.4  5079.5  244.77  5085.3  245.51  5100.8  244.72  5128.1  245.46
  5179.8  245.29  5217.3  244.84  5275.5  245.77  5328.2  245.04  5345.8  246.91
    5476  251.89  5481.1  251.43  5536.3  254.51  5541.4   253.9  5568.9  255.28
#Mann= 5 ,-1 , 0
  4580.4     .15       0  4848.4     .12       0  4947.5     .06       0
  5027.1     .12       0  5179.8     .11       0
Bank Sta=4947.5,5027.1
XS Rating Curve= 0 ,0
Exp/Cntr=0.3,0.1

Chan Stop Cuts=-1
Use User Specified Reach Order=0
Composite Channel Slope=5