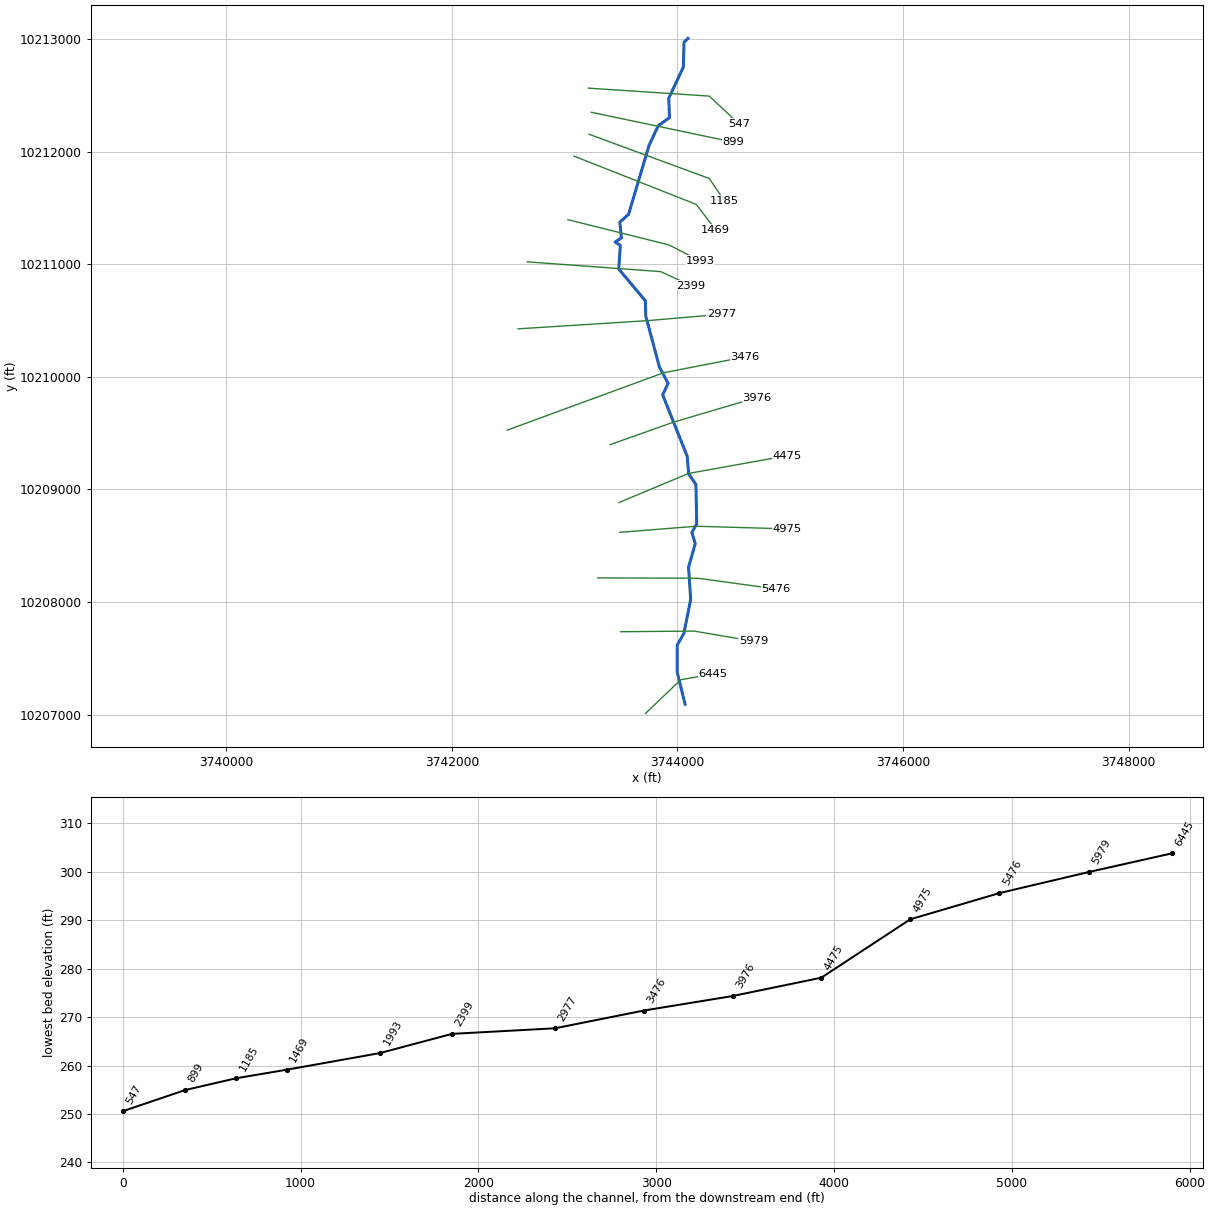
--- WFSJR 005.prj (project) ---

Proj Title=WFSJR 005 Base Level Engineering
Current Plan=p01
Default Exp/Contr=0.3,0.1
English Units
Geom File=g01
Flow File=f01
Plan File=p01
Y Axis Title=Elevation
X Axis Title(PF)=Main Channel Distance
X Axis Title(XS)=Station
BEGIN DESCRIPTION:
WFSJR 005
END DESCRIPTION:
DSS Export Rating Curves= 0
DSS Export Rating Curve Sorted= 0
DSS Export Volume Flow Curves= 0
DXF OffsetX= 0
DXF OffsetY= 0
DXF ScaleX= 1
DXF ScaleY= 10

--- WFSJR 005.p01 (plan) ---

Plan Title=Multiple Run
Program Version=4.10
Short Identifier=Multiple
Geom File=g01
Flow File=f01
Subcritical Flow
K Sum by GR= 0
Std Step Tol= 0.01
Critical Tol= 0.01
Num of Std Step Trials= 20
Max Error Tol= 0.3
Flow Tol Ratio= 0.001
Split Flow NTrial= 30
Split Flow Tol= 0.02
Split Flow Ratio= 0.02
Log Output Level= 0
Friction Slope Method= 1
Unsteady Friction Slope Method= 2
Unsteady Bridges Friction Slope Method= 1
Parabolic Critical Depth
Global Vel Dist= 1 , 1 , 1
Global Log Level= 0
CheckData=True
Encroach Param=-1 ,0,0, 0
BEGIN DESCRIPTION:
Multiple Run
END DESCRIPTION:
Computation Interval=1HOUR
Output Interval=1HOUR
Run HTab= 0
Run UNet= 0
Run PostProcess= 0
Run WQNet= 0
UNET Theta= 1
UNET Theta Warmup= 1
UNET ZTol= 0.02
UNET ZSATol= 0.05
UNET MxIter= 20
UNET MaxInSteps= 0
UNET DtIC= 0
UNET DtMin= 0
UNET MaxCRTS= 20
UNET WFStab= 2
UNET SFStab= 1
UNET WFX= 1
UNET SFX= 1
UNET DSS MLevel= 4
UNET DZMax Abort= 100
UNET Convert EG Bridges= 0
UNET Use Existing IB Tables=-1
UNET Froude Reduction=False
UNET Froude Limit= 1
UNET Froude Power= 10
UNET Time Slicing=0,0, 5
UNET Junction Losses=0
Instantaneous Interval=1HOUR
Write IC File= 0
Write IC File at Sim End=0
Echo Input=False
Echo Parameters=False
Echo Output=False
Write Detailed= 0
WQ AD Non Conservative
WQ ULTIMATE=-1
WQ Max Comp Step=1HOUR
WQ Output Interval=15MIN
WQ Output Selected Increments= 0
WQ Output face flow=0
WQ Output face velocity=0
WQ Output face area=0
WQ Output face dispersion=0
WQ Output cell volume=0
WQ Output cell surface area=0
WQ Output cell continuity=0
WQ Output cumulative cell continuity=0
WQ Output face conc=0
WQ Output face dconc_dx=0
WQ Output face courant=0
WQ Output face peclet=0
WQ Output face adv mass=0
WQ Output face disp mass=0
WQ Output cell mass=0
WQ Output cell source sink temp=0
WQ Output cell source sink nsm=0
WQ Output MaxMinRange=-1
WQ Daily Max Min Mean=-1
WQ Daily Range=0
WQ Daily Time=0
WQ Create Restart=0
WQ Fixed Restart=0
WQ System Summary=0
WQ Use Fixed Temperature=0
Sorting and Armoring Iterations= 10
XS Update Threshold= 0.02
Hydraulics Update Threshold= 0.02
Energy Slope Method= 1
Volume Change Method= 0
XS Weighting Method= 0
Number of US Weighted Cross Sections= 1
Number of DS Weighted Cross Sections= 1
Upstream XS Weight=0.25
Main XS Weight=0.5
Downstream XS Weight=0.25
Number of DS XS's Weighted with US Boundary= 1
Upstream Boundary Weight= 1
Weight of XSs Associated with US Boundary= 0
Number of US XS's Weighted with DS Boundary= 1
Downstream Boundary Weight= 0.5
Weight of XSs Associated with DS Boundary= 0.5
Sediment Output Level= 4
Mass or Volume Output= 0
Output Increment Type= 1
Profile and TS Output Increment= 10
XS Output Flag= 0
XS Output Increment= 10
Disregard all LS=0
Disregard all Conn=0
Disregard all Breaches=0
Disregard all Pumps=0

--- WFSJR 005.f01 (steady flow) ---

Flow Title=Multiple
Program Version=4.10
Number of Profiles= 7
Profile Names=10-year,25-year,50-year,1pct_min,100-year,1pct_plu,500-year
River Rch & RM=WFSJR 005,Reach-1         ,6445
     948    1353    1896     877    2649    8000    5341
Boundary for River Rch & Prof#=WFSJR 005,Reach-1         , 1
Up Type= 0
Dn Type= 3
Dn Slope=0.013
Boundary for River Rch & Prof#=WFSJR 005,Reach-1         , 2
Up Type= 0
Dn Type= 3
Dn Slope=0.013
Boundary for River Rch & Prof#=WFSJR 005,Reach-1         , 3
Up Type= 0
Dn Type= 3
Dn Slope=0.013
Boundary for River Rch & Prof#=WFSJR 005,Reach-1         , 4
Up Type= 0
Dn Type= 3
Dn Slope=0.013
Boundary for River Rch & Prof#=WFSJR 005,Reach-1         , 5
Up Type= 0
Dn Type= 3
Dn Slope=0.013
Boundary for River Rch & Prof#=WFSJR 005,Reach-1         , 6
Up Type= 0
Dn Type= 3
Dn Slope=0.013
Boundary for River Rch & Prof#=WFSJR 005,Reach-1         , 7
Up Type= 0
Dn Type= 3
Dn Slope=0.013
DSS Import GetInterval= 0
DSS Import GetPeak= 0
DSS Import FillOption= 0

--- WFSJR 005.g01 (geometry) ---

Geom Title=Existing Conditions
Program Version=4.10

River Reach=WFSJR 005       ,Reach-1
Reach XY= 30
      3744068.23     10207091.84      3743998.53     10207374.84
      3743998.46     10207618.36      3744057.02     10207720.25
       3744117.7     10208024.05      3744098.72     10208308.79
      3744158.13     10208516.83      3744128.58       10208619.
       3744171.3      10208693.3      3744163.87     10209045.25
      3744100.12      10209137.6      3744086.72     10209294.36
      3743869.13     10209840.29      3743917.62     10209941.72
      3743839.71     10210089.29      3743719.22     10210541.11
      3743716.81     10210674.34      3743479.87     10210957.57
      3743494.06     10211167.03      3743448.17     10211196.83
      3743503.42     10211234.46      3743489.57     10211374.31
      3743566.87     10211442.74       3743748.7     10212055.41
      3743830.29     10212230.43      3743929.19     10212301.61
      3743923.71     10212475.22      3744052.69     10212750.95
      3744058.43      10212970.9      3744093.64     10213006.14

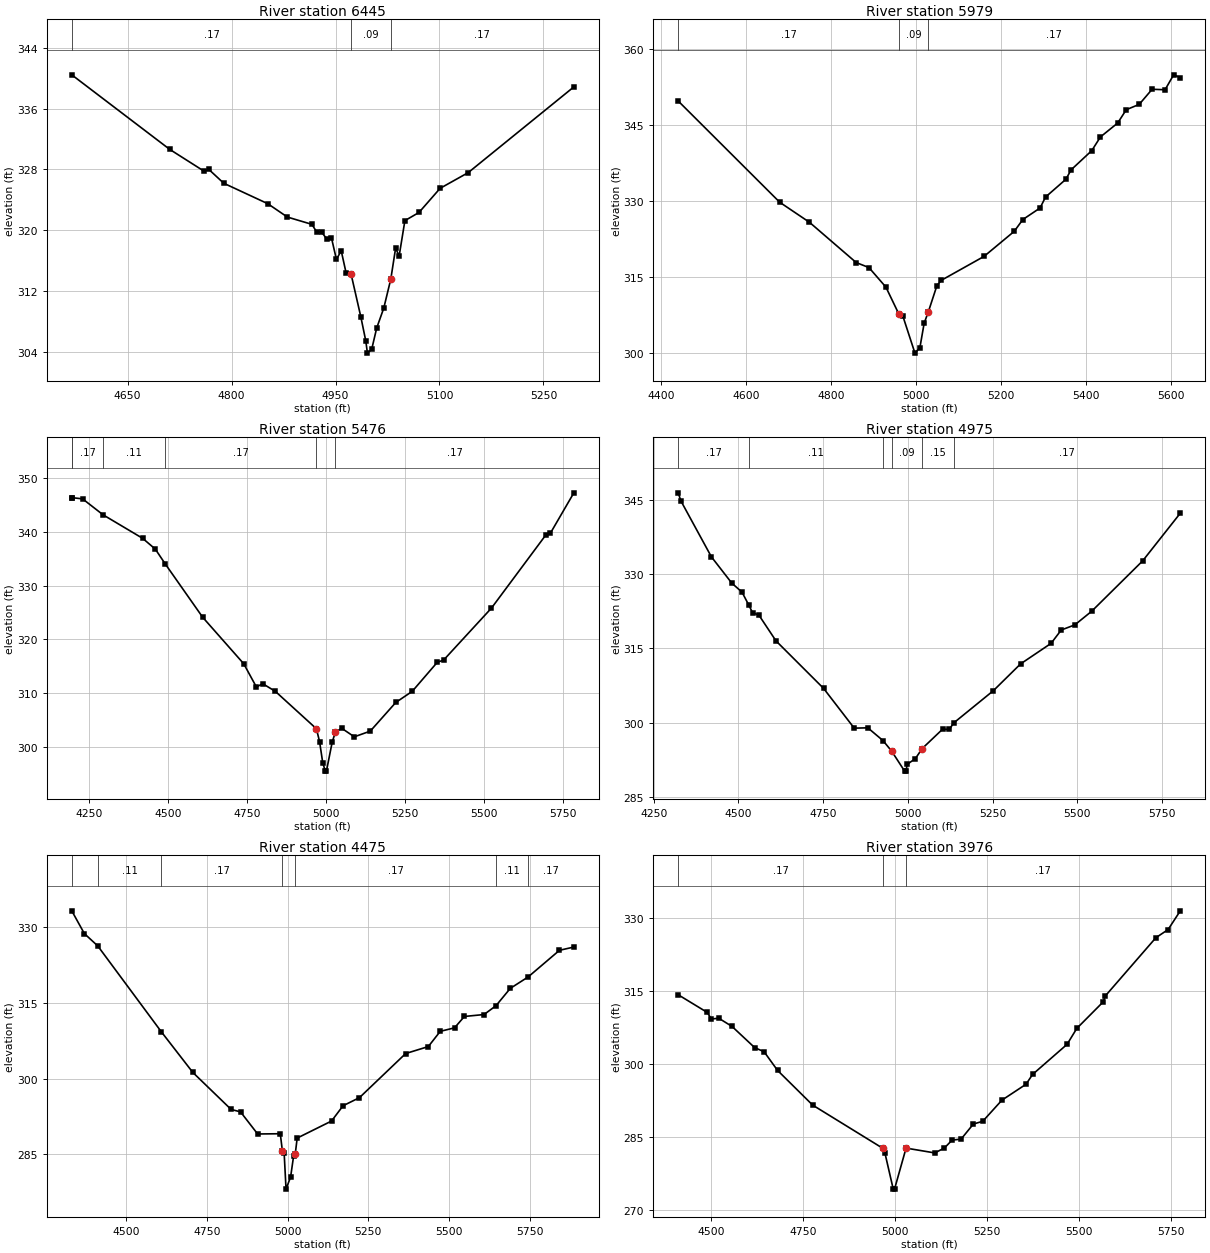
Type RM Length L Ch R = 1 ,6445    ,466,466,466
BEGIN DESCRIPTION:
WFSJR 005 13.0
END DESCRIPTION:
XS GIS Cut Line= 3
      3743717.88      10207011.1      3744028.56     10207309.26
      3744317.86     10207361.07
#Sta/Elev= 30
  4569.4  340.44  4710.7  330.63  4760.4  327.75  4767.3  327.98  4788.7  326.17
  4852.2  323.48  4880.5  321.72  4915.9  320.76    4923  319.73  4929.9  319.75
  4937.1  318.86  4944.1     319  4951.3  316.14  4958.2  317.29  4965.4  314.31
  4972.4  314.23  4986.5  308.59  4993.7   305.4    4996  303.81  5002.2  304.31
  5009.4  307.11  5019.6  309.73  5029.8  313.57  5036.7  317.63  5041.8  316.59
  5050.1  321.25  5070.4  322.32  5100.9   325.5  5141.5  327.57  5293.9  338.85
#Mann= 3 , 0 , 0
  4569.4     .17       0  4972.4     .09       0  5029.8     .17       0
Bank Sta=4972.4,5029.8
XS Rating Curve= 0 ,0
Exp/Cntr=0.3,0.1

Type RM Length L Ch R = 1 ,5979    ,503,503,503
BEGIN DESCRIPTION:
WFSJR 005 12.0
END DESCRIPTION:
XS GIS Cut Line= 3
      3743498.84     10207736.37      3744148.12     10207741.99
      3744673.28     10207652.13
#Sta/Elev= 30
  4440.4  349.68  4679.4  329.72  4749.4  325.77  4859.4  317.83  4889.4  316.84
  4929.4  312.98  4959.4  307.75  4969.4  307.24  4997.7  299.97  5009.4  301.07
  5019.4  305.87  5029.4  308.15  5049.4  313.27  5059.4  314.31  5160.5  319.05
  5231.5  323.99  5251.8  326.32  5292.3  328.59  5305.1  330.74  5353.2  334.26
  5365.2   336.1  5414.1  339.91  5434.4   342.6    5475  345.34  5495.2  347.97
  5525.7  349.02  5556.1     352  5586.6  351.91  5606.8  354.85  5622.5  354.31
#Mann= 3 , 0 , 0
  4440.4     .17       0  4959.4     .09       0  5029.4     .17       0
Bank Sta=4959.4,5029.4
XS Rating Curve= 0 ,0
Exp/Cntr=0.3,0.1

Type RM Length L Ch R = 1 ,5476    ,501,501,501
BEGIN DESCRIPTION:
WFSJR 005 11.0
END DESCRIPTION:
XS GIS Cut Line= 3
      3743293.59     10208214.22      3744181.85      10208211.4
      3744876.14     10208115.83
#Sta/Elev= 30
  4195.5  346.28  4195.7  346.28  4229.8  346.05  4294.5   343.1  4419.8  338.74
  4459.8  336.75  4491.9  333.95  4609.8  324.12  4739.8   315.5  4779.8   311.2
  4799.8  311.81  4839.8  310.39  4969.8  303.46  4979.8  301.08  4989.8  297.17
    4998  295.61  5001.5  295.61  5019.8  300.99  5029.8  302.82  5049.8  303.55
  5089.8  301.97  5140.3  303.02    5221  308.33  5273.1  310.39  5352.3  315.77
  5372.5  316.19  5523.9  325.82  5695.5  339.33  5710.1  339.66  5784.6  347.17
#Mann= 6 ,-1 , 0
  4195.5     .11       0  4195.7     .17       0  4294.5     .11       0
  4491.9     .17       0  4969.8     .09       0  5029.8     .17       0
Bank Sta=4969.8,5029.8
XS Rating Curve= 0 ,0
Exp/Cntr=0.3,0.1

Type RM Length L Ch R = 1 ,4975    ,500,500,500
BEGIN DESCRIPTION:
WFSJR 005 10.0
END DESCRIPTION:
XS GIS Cut Line= 3
      3743490.38     10208618.98      3744165.73     10208672.87
       3744968.9      10208649.9
#Sta/Elev= 30
  4322.5  346.42    4330  344.83  4420.3  333.49  4480.5  328.18  4510.6  326.36
    4531  323.69  4541.6  322.23  4560.7  321.69  4610.9  316.51  4751.3  306.91
  4841.6  298.88  4881.7  298.95  4926.5  296.37    4952  294.24  4990.3   290.2
  4993.8   290.2  4998.6   291.6  5022.1  292.74  5042.1  294.76  5102.2  298.67
  5122.2  298.62  5134.8  299.92  5252.2  306.46  5332.3  311.86  5422.3  316.01
  5452.3  318.71  5492.3  319.74  5542.3  322.51  5692.4  332.67  5803.5  342.31
#Mann= 6 ,-1 , 0
  4322.5     .17       0    4531     .11       0  4926.5     .15       0
    4952     .09       0  5042.1     .15       0  5134.8     .17       0
Bank Sta=4952,5042.1
XS Rating Curve= 0 ,0
Exp/Cntr=0.3,0.1

Type RM Length L Ch R = 1 ,4475    ,499,499,499
BEGIN DESCRIPTION:
WFSJR 005 9.0
END DESCRIPTION:
XS GIS Cut Line= 3
      3743481.93     10208883.19      3744098.94     10209142.01
       3744971.7      10209299.2
#Sta/Elev= 30
  4330.9  333.15  4369.9  328.65  4411.3  326.22  4608.8  309.21    4706  301.21
  4824.7  293.89  4853.9  293.41  4906.9  289.04  4977.1  289.09  4983.6  285.67
    4989  285.35  4994.9  278.14  5009.1  280.55  5018.5  284.76  5023.6  285.16
  5029.4  288.23  5135.9   291.6  5171.6  294.62  5222.4  296.22  5365.6  304.94
  5435.8  306.32  5472.8  309.33  5517.1  310.02  5547.6  312.27  5608.5  312.65
  5645.6   314.4  5689.8  317.82  5745.2  320.08  5842.3  325.35  5886.8  325.99
#Mann= 7 ,-1 , 0
  4330.9     .17       0  4411.3     .11       0  4608.8     .17       0
  4983.6     .09       0  5023.6     .17       0  5645.6     .11       0
  5745.2     .17       0
Bank Sta=4983.6,5023.6
XS Rating Curve= 0 ,0
Exp/Cntr=0.3,0.1

Type RM Length L Ch R = 1 ,3976    ,500,500,500
BEGIN DESCRIPTION:
WFSJR 005 8.0
END DESCRIPTION:
XS GIS Cut Line= 3
      3743403.29      10209397.6      3743959.25     10209595.42
      3744703.24     10209815.98
#Sta/Elev= 30
  4409.9  314.24    4489  310.61  4499.9  309.26  4520.1  309.43  4556.3  307.74
  4617.9  303.39  4643.5  302.55  4680.1  298.72  4775.6   291.6  4966.7  282.72
  4972.1  281.82  4994.9  274.35  4998.4  274.35  5029.8  282.77    5108  281.78
  5134.1  282.79    5155  284.41  5179.6  284.62  5212.9  287.71  5238.4  288.27
  5290.6  292.61  5356.3  295.88    5374  297.89  5467.9  304.07  5494.4  307.34
  5566.1  312.78  5572.2  314.02  5709.5  325.95  5742.7  327.62    5776  331.47
#Mann= 3 , 0 , 0
  4409.9     .17       0  4966.7     .09       0  5029.8     .17       0
Bank Sta=4966.7,5029.8
XS Rating Curve= 0 ,0
Exp/Cntr=0.3,0.1

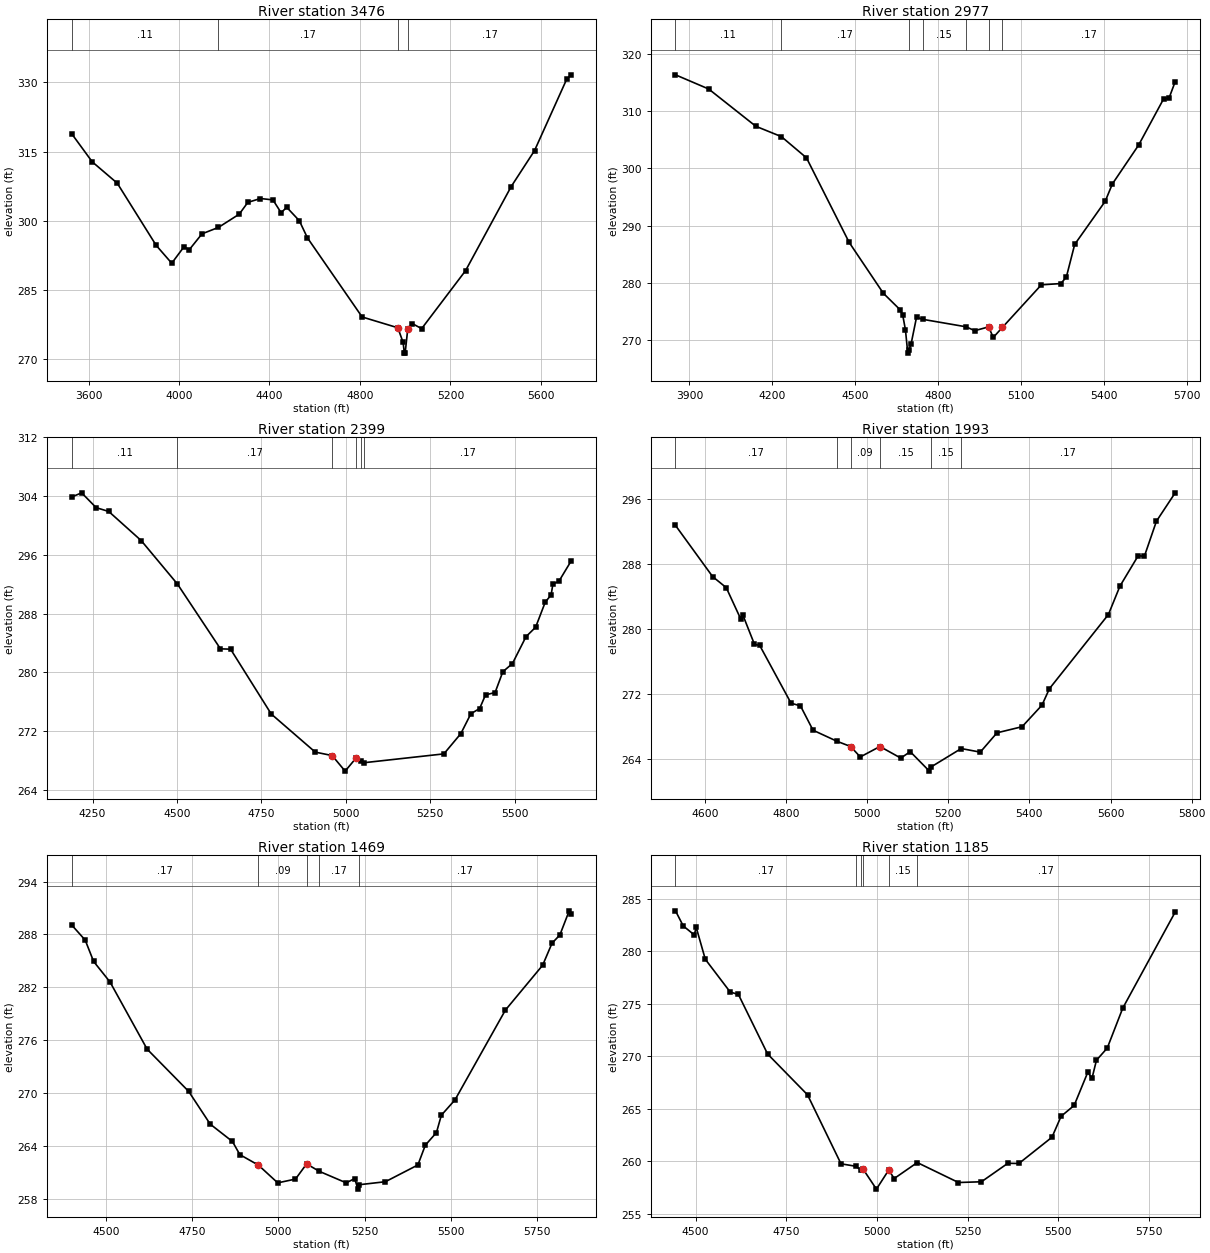
Type RM Length L Ch R = 1 ,3476    ,499,499,499
BEGIN DESCRIPTION:
WFSJR 005 7.0
END DESCRIPTION:
XS GIS Cut Line= 3
      3742492.56     10209526.89      3743876.37     10210036.02
      3744597.59     10210176.13
#Sta/Elev= 30
  3525.5  318.88  3616.4  312.79  3727.1  308.16  3899.2  294.69    3968  290.82
  4021.3  294.33  4046.2  293.79  4101.8  297.19  4174.5  298.58  4266.4  301.45
  4304.4     304    4360  304.84  4415.5  304.54  4451.4  301.77  4476.5  302.93
  4532.1  300.03  4567.9  296.32  4809.8  279.18  4967.7  276.84  4990.9  273.66
  4996.4  271.35  4999.9  271.35  5011.7  276.68  5032.1  277.74  5072.8  276.65
    5267  289.21  5468.6  307.42    5572  315.22  5714.6  330.73  5734.7  331.63
#Mann= 4 ,-1 , 0
  3525.5     .11       0  4174.5     .17       0  4967.7     .09       0
  5011.7     .17       0
Bank Sta=4967.7,5011.7
XS Rating Curve= 0 ,0
Exp/Cntr=0.3,0.1

Type RM Length L Ch R = 1 ,2977    ,578,578,578
BEGIN DESCRIPTION:
WFSJR 005 6.0
END DESCRIPTION:
XS GIS Cut Line= 3
      3742588.08     10210426.35      3743736.39     10210498.92
      3744389.83     10210555.65
#Sta/Elev= 30
  3849.4  316.38  3969.4   313.9  4139.8  307.38  4232.2  305.57  4322.9  301.86
  4477.3  287.06  4600.7  278.17  4660.8  275.31  4670.8  274.37  4680.8  271.74
  4689.1  267.69  4692.8  268.19  4700.9  269.24  4720.9  273.99  4742.4  273.61
  4899.6   272.3  4931.3  271.62  4981.4  272.28  4998.2  270.43  5031.6  272.21
  5172.1  279.64  5242.4  279.86  5262.4  280.99  5292.6  286.71    5403  294.26
  5428.8  297.29  5523.4  304.06  5613.8  312.15  5633.8  312.32  5655.9  315.18
#Mann= 7 ,-1 , 0
  3849.4     .11       0  4232.2     .17       0  4692.8     .17       0
  4742.4     .15       0  4899.6     .17       0  4981.4     .09       0
  5031.6     .17       0
Bank Sta=4981.4,5031.6
XS Rating Curve= 0 ,0
Exp/Cntr=0.3,0.1

Type RM Length L Ch R = 1 ,2399    ,406,406,406
BEGIN DESCRIPTION:
WFSJR 005 5.0
END DESCRIPTION:
XS GIS Cut Line= 3
      3742668.28     10211021.22      3743852.32     10210934.41
      3744117.86     10210811.07
#Sta/Elev= 30
  4188.2  303.88  4217.8  304.45  4260.8  302.43  4298.1  301.91  4394.3  297.94
  4501.6  292.02  4628.9   283.2    4659  283.15  4779.4  274.32  4909.7  269.13
  4959.8  268.66  4998.2  266.54    5030  268.29  5044.8  267.94  5054.9  267.69
  5290.7  268.89  5340.9  271.65  5370.7  274.36  5396.6  275.07    5414  276.92
  5442.4  277.25  5465.3  280.08  5493.7  281.19    5534  284.86  5562.4  286.14
    5591  289.57  5608.2  290.53  5613.7  292.04  5631.1  292.38  5668.2  295.21
#Mann= 6 ,-1 , 0
  4188.2     .11       0  4501.6     .17       0  4959.8     .09       0
    5030     .17       0  5044.8     .15       0  5054.9     .17       0
Bank Sta=4959.8,5030
XS Rating Curve= 0 ,0
Exp/Cntr=0.3,0.1

Type RM Length L Ch R = 1 ,1993    ,524,524,524
BEGIN DESCRIPTION:
WFSJR 005 4.0
END DESCRIPTION:
XS GIS Cut Line= 3
        3743029.     10211395.79      3743923.64     10211172.13
      3744198.94     10211030.66
#Sta/Elev= 30
  4527.7  292.71  4619.3  286.43  4652.8  285.08  4688.9  281.19    4694  281.69
  4722.4  278.12  4735.3  277.99  4812.6   270.9  4835.7  270.58  4866.7  267.59
  4925.9  266.23  4959.4  265.59  4983.2  264.31  5031.6  265.59  5083.1  264.17
  5106.3  264.96  5153.5  262.57  5157.3  263.07    5232  265.34    5279   264.9
  5320.2  267.27  5382.1  268.02    5431  270.66  5449.5  272.69  5594.8  281.78
  5623.3  285.27  5668.2  288.99  5683.5  288.93  5713.2  293.23  5759.4  296.71
#Mann= 6 ,-1 , 0
  4527.7     .17       0  4925.9     .15       0  4959.4     .09       0
  5031.6     .15       0  5157.3     .15       0    5232     .17       0
Bank Sta=4959.4,5031.6
XS Rating Curve= 0 ,0
Exp/Cntr=0.3,0.1

Type RM Length L Ch R = 1 ,1469    ,284,284,284
BEGIN DESCRIPTION:
WFSJR 005 3.0
END DESCRIPTION:
XS GIS Cut Line= 3
      3743084.36     10211959.77      3744166.43     10211531.53
       3744339.6     10211305.09
#Sta/Elev= 30
  4400.7  289.08    4440  287.36  4464.4  284.94    4512  282.61  4619.5     275
    4740  270.21  4802.4   266.5  4866.9  264.53  4888.4  263.04  4942.2  261.85
  4998.2  259.84  5049.7  260.27    5082  261.99  5118.6  261.15  5196.9  259.84
  5221.2  260.33  5230.8  259.13  5234.6  259.63  5310.4  259.97  5404.6  261.87
  5426.1  264.11  5458.4  265.54  5472.6  267.51  5512.2  269.25  5658.4  279.43
  5766.3  284.51  5793.5  287.01  5816.2  287.94  5843.3  290.68  5849.5  290.34
#Mann= 5 ,-1 , 0
  4400.7     .17       0  4942.2     .09       0    5082     .17       0
  5118.6     .17       0  5234.6     .17       0
Bank Sta=4942.2,5082
XS Rating Curve= 0 ,0
Exp/Cntr=0.3,0.1

Type RM Length L Ch R = 1 ,1185    ,286,286,286
BEGIN DESCRIPTION:
WFSJR 005 2.0
END DESCRIPTION:
XS GIS Cut Line= 3
      3743216.27     10212154.77      3744283.04     10211760.94
      3744417.83      10211561.1
#Sta/Elev= 30
  4444.4  283.86  4465.8  282.42  4496.2  281.57  4501.5  282.29  4526.6  279.25
  4595.3  276.13  4617.9   275.9  4698.5  270.23  4808.5  266.35  4900.9  259.78
  4941.1  259.55  4956.4  259.18  4961.7  259.28  4998.6  257.37  5032.4  259.18
  5047.7  258.38  5111.2   259.9  5224.9     258  5288.2  258.07  5361.1  259.83
  5391.5  259.81  5482.8  262.31  5507.9   264.3    5544  265.34  5581.4  268.48
  5593.3  267.94  5605.5  269.64  5635.3   270.8  5677.9  274.59  5822.6  283.74
#Mann= 6 ,-1 , 0
  4444.4     .17       0  4941.1     .15       0  4956.4     .12       0
  4961.7     .09       0  5032.4     .15       0  5111.2     .17       0
Bank Sta=4961.7,5032.4
XS Rating Curve= 0 ,0
Exp/Cntr=0.3,0.1

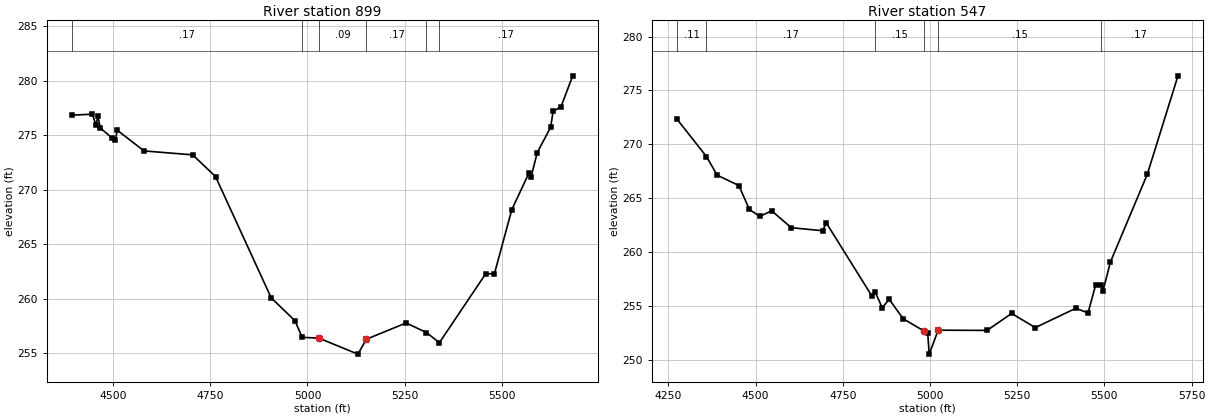
Type RM Length L Ch R = 1 ,899     ,352,352,352
BEGIN DESCRIPTION:
Mapping XS 0d7644a7
END DESCRIPTION:
XS GIS Cut Line= 2
      3743235.39     10212349.76      3744497.11     10212084.03
#Sta/Elev= 30
    4393  276.86  4446.6  276.95  4455.6  275.95  4460.7  276.75    4467  275.68
  4497.7  274.75  4505.4  274.55  4510.5  275.48  4579.5  273.58  4704.6  273.22
  4763.4  271.23  4906.5  260.11  4967.8     258  4986.2  256.48  5029.1  256.41
  5129.6  254.94  5151.7  256.31  5253.9   257.8    5306  256.92  5339.4  255.99
  5458.3   262.3  5481.1  262.33  5525.8   268.2  5570.5   271.6  5575.6  271.23
  5591.2  273.43  5625.5  275.74  5632.1  277.21  5652.5  277.65  5682.4  280.47
#Mann= 6 ,-1 , 0
    4393     .17       0  4986.2     .15       0  5029.1     .09       0
  5151.7     .17       0    5306     .15       0  5339.4     .17       0
Bank Sta=5029.1,5151.7
XS Rating Curve= 0 ,0
Exp/Cntr=0.3,0.1

Type RM Length L Ch R = 1 ,547     ,0,0,0
BEGIN DESCRIPTION:
WFSJR 005 1.0
END DESCRIPTION:
XS GIS Cut Line= 3
      3743210.55     10212563.86      3744283.04     10212493.13
      3744546.08     10212245.34
#Sta/Elev= 30
  4274.6  272.36  4359.3  268.88  4390.1  267.15  4452.3  266.19  4482.4  263.97
  4512.4  263.33  4546.2  263.85  4602.6  262.28  4692.4     262  4702.8  262.73
  4833.1  255.97  4842.5  256.35  4863.2  254.86  4883.2  255.64  4923.3  253.84
  4983.4  252.69  4993.5   252.5  4997.9  250.56  5023.5  252.78  5163.8  252.76
    5234  254.33  5301.9  253.02    5418  254.81  5453.1  254.38  5474.6  256.94
  5489.3  256.99  5495.6  256.37  5517.1  259.09  5623.1  267.25  5710.8  276.36
#Mann= 6 ,-1 , 0
  4274.6     .11       0  4359.3     .17       0  4842.5     .15       0
  4983.4     .09       0  5023.5     .15       0  5489.3     .17       0
#XS Ineff= 1 ,-1
    4845  4883.2  255.64
Permanent Ineff=
       F
Bank Sta=4983.4,5023.5
XS Rating Curve= 0 ,0
Exp/Cntr=0.3,0.1

Chan Stop Cuts=-1
Use User Specified Reach Order=0
Composite Channel Slope=5