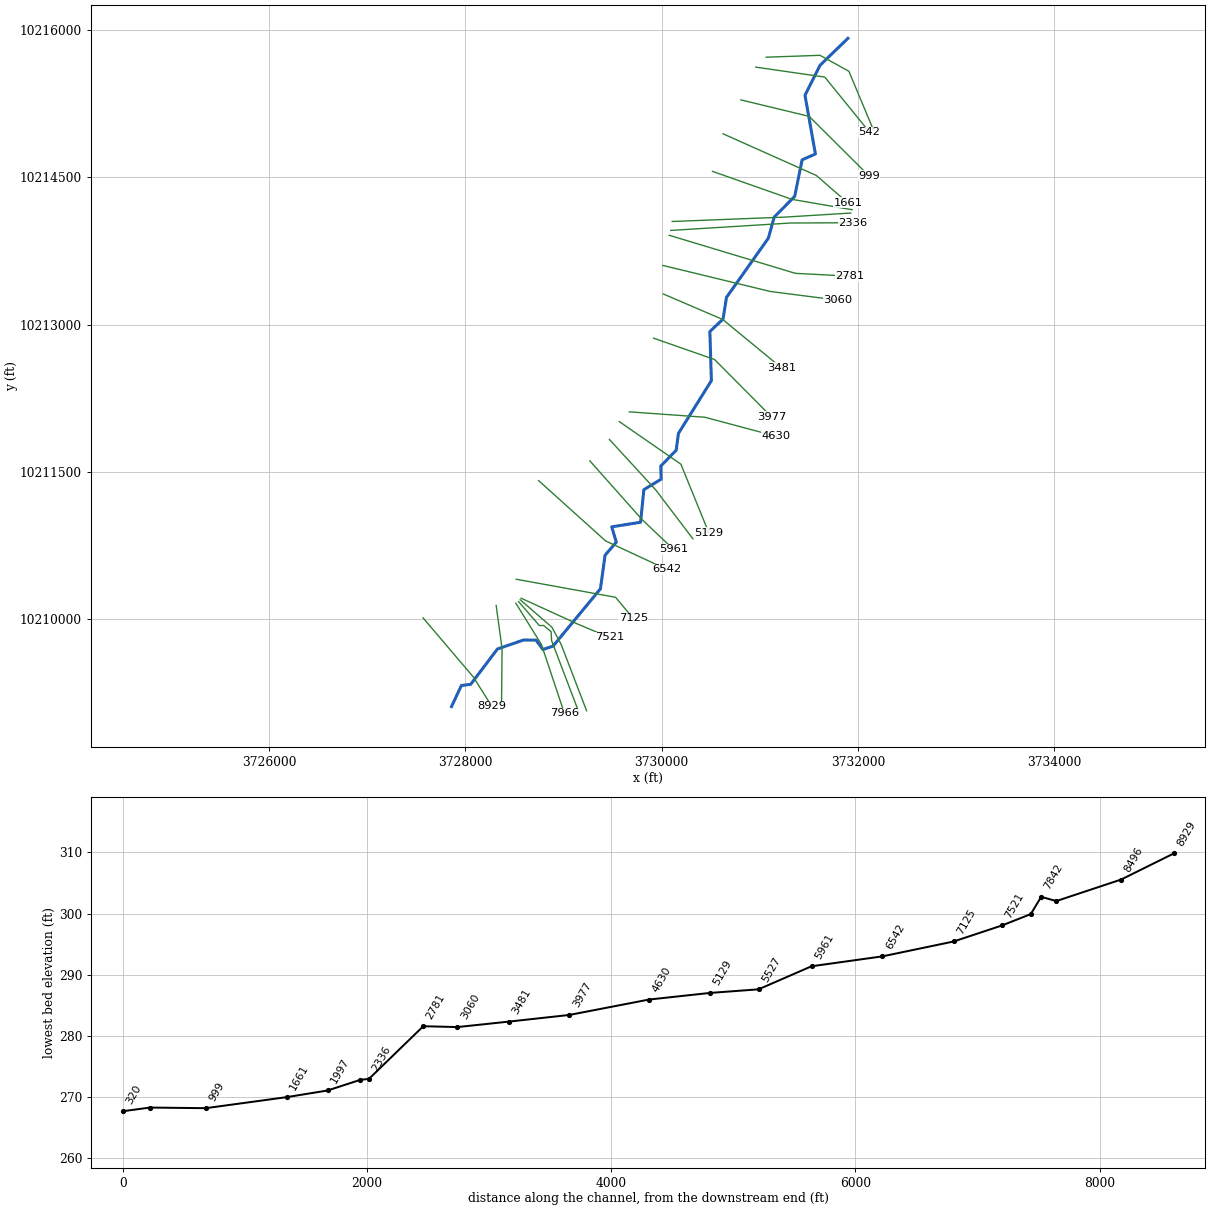
--- WFSJR 006.prj (project) ---

Proj Title=WFSJR 006 Base Level Engineering
Current Plan=p01
Default Exp/Contr=0.3,0.1
English Units
Geom File=g01
Flow File=f01
Plan File=p01
Y Axis Title=Elevation
X Axis Title(PF)=Main Channel Distance
X Axis Title(XS)=Station
BEGIN DESCRIPTION:
WFSJR 006
END DESCRIPTION:
DSS Export Rating Curves= 0
DSS Export Rating Curve Sorted= 0
DSS Export Volume Flow Curves= 0
DXF OffsetX= 0
DXF OffsetY= 0
DXF ScaleX= 1
DXF ScaleY= 10

--- WFSJR 006.p01 (plan) ---

Plan Title=Multiple Run
Program Version=4.10
Short Identifier=Multiple
Geom File=g01
Flow File=f01
Subcritical Flow
K Sum by GR= 0
Std Step Tol= 0.01
Critical Tol= 0.01
Num of Std Step Trials= 20
Max Error Tol= 0.3
Flow Tol Ratio= 0.001
Split Flow NTrial= 30
Split Flow Tol= 0.02
Split Flow Ratio= 0.02
Log Output Level= 0
Friction Slope Method= 1
Unsteady Friction Slope Method= 2
Unsteady Bridges Friction Slope Method= 1
Parabolic Critical Depth
Global Vel Dist= 1 , 1 , 1
Global Log Level= 0
CheckData=True
Encroach Param=-1 ,0,0, 0
BEGIN DESCRIPTION:
Multiple Run
END DESCRIPTION:
Computation Interval=1HOUR
Output Interval=1HOUR
Run HTab= 0
Run UNet= 0
Run PostProcess= 0
Run WQNet= 0
UNET Theta= 1
UNET Theta Warmup= 1
UNET ZTol= 0.02
UNET ZSATol= 0.05
UNET MxIter= 20
UNET MaxInSteps= 0
UNET DtIC= 0
UNET DtMin= 0
UNET MaxCRTS= 20
UNET WFStab= 2
UNET SFStab= 1
UNET WFX= 1
UNET SFX= 1
UNET DSS MLevel= 4
UNET DZMax Abort= 100
UNET Convert EG Bridges= 0
UNET Use Existing IB Tables=-1
UNET Froude Reduction=False
UNET Froude Limit= 1
UNET Froude Power= 10
UNET Time Slicing=0,0, 5
UNET Junction Losses=0
Instantaneous Interval=1HOUR
Write IC File= 0
Write IC File at Sim End=0
Echo Input=False
Echo Parameters=False
Echo Output=False
Write Detailed= 0
WQ AD Non Conservative
WQ ULTIMATE=-1
WQ Max Comp Step=1HOUR
WQ Output Interval=15MIN
WQ Output Selected Increments= 0
WQ Output face flow=0
WQ Output face velocity=0
WQ Output face area=0
WQ Output face dispersion=0
WQ Output cell volume=0
WQ Output cell surface area=0
WQ Output cell continuity=0
WQ Output cumulative cell continuity=0
WQ Output face conc=0
WQ Output face dconc_dx=0
WQ Output face courant=0
WQ Output face peclet=0
WQ Output face adv mass=0
WQ Output face disp mass=0
WQ Output cell mass=0
WQ Output cell source sink temp=0
WQ Output cell source sink nsm=0
WQ Output MaxMinRange=-1
WQ Daily Max Min Mean=-1
WQ Daily Range=0
WQ Daily Time=0
WQ Create Restart=0
WQ Fixed Restart=0
WQ System Summary=0
WQ Use Fixed Temperature=0
Sorting and Armoring Iterations= 10
XS Update Threshold= 0.02
Hydraulics Update Threshold= 0.02
Energy Slope Method= 1
Volume Change Method= 0
XS Weighting Method= 0
Number of US Weighted Cross Sections= 1
Number of DS Weighted Cross Sections= 1
Upstream XS Weight=0.25
Main XS Weight=0.5
Downstream XS Weight=0.25
Number of DS XS's Weighted with US Boundary= 1
Upstream Boundary Weight= 1
Weight of XSs Associated with US Boundary= 0
Number of US XS's Weighted with DS Boundary= 1
Downstream Boundary Weight= 0.5
Weight of XSs Associated with DS Boundary= 0.5
Sediment Output Level= 4
Mass or Volume Output= 0
Output Increment Type= 1
Profile and TS Output Increment= 10
XS Output Flag= 0
XS Output Increment= 10
Disregard all LS=0
Disregard all Conn=0
Disregard all Breaches=0
Disregard all Pumps=0

--- WFSJR 006.f01 (steady flow) ---

Flow Title=Multiple
Program Version=4.10
Number of Profiles= 7
Profile Names=10-year,25-year,50-year,1pct_min,100-year,1pct_plu,500-year
River Rch & RM=WFSJR 006,Reach-1         ,8929
    1260    1780    2473    1128    3406   10286    6691
Boundary for River Rch & Prof#=WFSJR 006,Reach-1         , 1
Up Type= 0
Dn Type= 3
Dn Slope=0.006
Boundary for River Rch & Prof#=WFSJR 006,Reach-1         , 2
Up Type= 0
Dn Type= 3
Dn Slope=0.006
Boundary for River Rch & Prof#=WFSJR 006,Reach-1         , 3
Up Type= 0
Dn Type= 3
Dn Slope=0.006
Boundary for River Rch & Prof#=WFSJR 006,Reach-1         , 4
Up Type= 0
Dn Type= 3
Dn Slope=0.006
Boundary for River Rch & Prof#=WFSJR 006,Reach-1         , 5
Up Type= 0
Dn Type= 3
Dn Slope=0.006
Boundary for River Rch & Prof#=WFSJR 006,Reach-1         , 6
Up Type= 0
Dn Type= 3
Dn Slope=0.006
Boundary for River Rch & Prof#=WFSJR 006,Reach-1         , 7
Up Type= 0
Dn Type= 3
Dn Slope=0.006
DSS Import GetInterval= 0
DSS Import GetPeak= 0
DSS Import FillOption= 0

--- WFSJR 006.g01 (geometry) ---

Geom Title=Existing Conditions
Program Version=4.10

River Reach=WFSJR 006       ,Reach-1
Reach XY= 30
      3727858.23     10209106.84      3727959.14     10209321.82
      3728053.49     10209333.06      3728325.83     10209693.28
      3728592.35     10209785.12      3728719.31     10209784.24
      3728789.69     10209688.72      3728892.75     10209722.74
      3729375.96     10210306.84      3729423.03     10210649.41
      3729537.49     10210782.04      3729491.12     10210938.28
      3729785.23     10210985.18      3729818.23     10211316.84
      3729994.79     10211424.46      3729990.89     10211557.65
      3730147.66     10211718.94      3730171.23     10211891.17
       3730506.6     10212428.46      3730491.11     10212928.44
      3730625.59     10213056.05      3730660.49     10213276.86
      3731087.61      10213880.7      3731146.56     10214095.18
      3731355.47     10214306.06      3731431.25     10214678.43
      3731566.76     10214738.48      3731460.41     10215336.85
      3731614.02     10215642.31      3731898.23     10215916.84

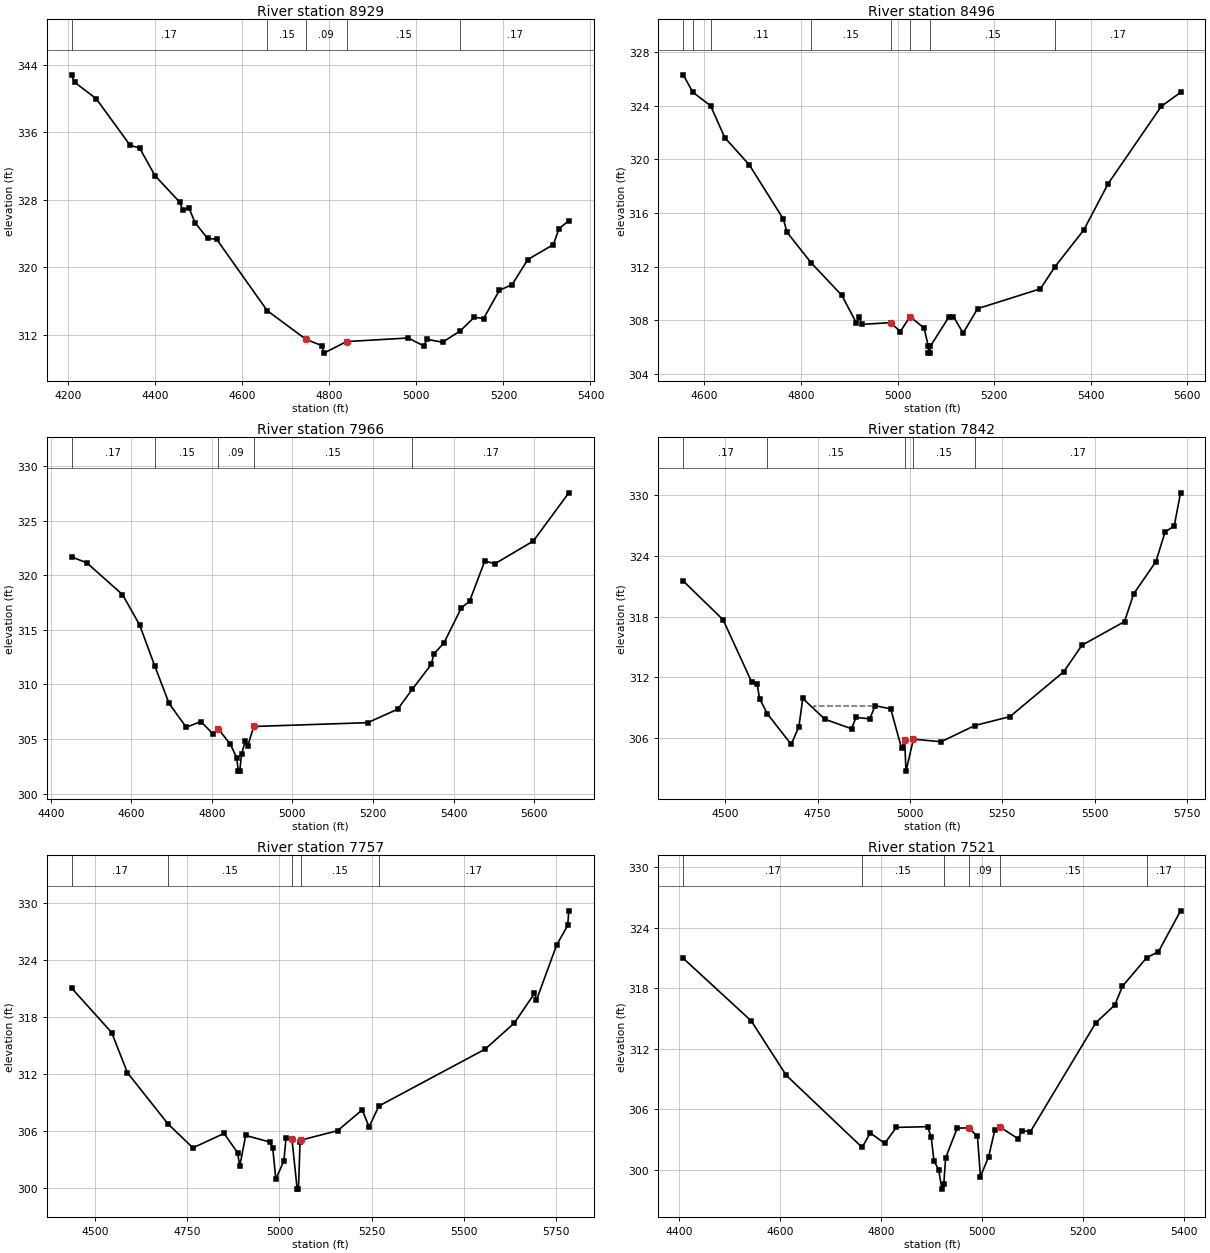
Type RM Length L Ch R = 1 ,8929    ,433,433,433
BEGIN DESCRIPTION:
WFSJR 006 18.0
END DESCRIPTION:
XS GIS Cut Line= 3
      3727567.85     10210011.08       3728081.1      10209407.5
      3728267.83     10209111.11
#Sta/Elev= 30
  4207.7  342.79  4214.8  341.91  4264.3  339.97  4342.2  334.46  4364.2  334.12
  4399.4  330.86  4456.5  327.71    4463  326.76  4477.3  327.05  4491.6  325.29
  4520.2  323.43    4541  323.33  4657.3  314.88  4746.4  311.48  4782.7  310.74
  4787.5  309.85 4839.55311.2191  4981.4  311.64  5017.8  310.68  5023.7  311.49
  5060.2  311.14  5101.3   312.5  5133.2  314.11  5154.3  313.93  5190.8  317.29
  5220.3  317.97  5255.8  320.92  5314.9   322.7  5327.4  324.56  5350.3  325.54
#Mann= 5 ,-1 , 0
  4207.7     .17       0  4657.3     .15       0  4746.4     .09       0
 4839.55     .15       0  5101.3     .17       0
Bank Sta=4746.4,4839.55
XS Rating Curve= 0 ,0
Exp/Cntr=0.3,0.1

Type RM Length L Ch R = 1 ,8496    ,530,530,530
BEGIN DESCRIPTION:
WFSJR 006 17.0
END DESCRIPTION:
XS GIS Cut Line= 3
       3728313.4     10210136.32      3728373.42      10209696.9
      3728367.85     10209111.03
#Sta/Elev= 30
  4556.5  326.29  4576.2     325  4613.2  323.98  4642.5  321.61    4693   319.6
  4763.7  315.55  4771.4  314.56  4821.6  312.28  4884.8  309.87  4915.1   307.8
    4921  308.26  4926.1  307.71  4985.7  307.84  5005.8  307.17  5025.8  308.29
  5055.2  307.43  5063.8  306.07  5064.1  305.57  5067.6  305.57  5067.8  306.07
  5105.8  308.23  5115.8  308.29  5135.8  307.06  5165.8  308.88  5295.8  310.36
  5325.9     312  5385.8  314.75  5435.9  318.18  5545.9  323.94  5585.9  324.98
#Mann= 8 ,-1 , 0
  4556.5     .11       0  4576.2     .17       0  4613.2     .11       0
  4821.6     .15       0  4985.7     .09       0  5025.8     .15       0
  5067.8     .15       0  5325.9     .17       0
Bank Sta=4985.7,5025.8
XS Rating Curve= 0 ,0
Exp/Cntr=0.3,0.1

Type RM Length L Ch R = 1 ,7966    ,124,124,124
BEGIN DESCRIPTION:
WFSJR 006 16.0
END DESCRIPTION:
XS GIS Cut Line= 3
       3728513.9     10210159.82      3728774.59     10209739.23
      3729008.71     10209037.37
#Sta/Elev= 30
  4451.6  321.69  4489.4  321.15  4578.1  318.24  4620.6  315.46  4658.2   311.7
  4693.8  308.26  4736.3  306.08    4773   306.6  4803.1  305.45  4815.5  305.95
  4846.2  304.51  4861.6  303.29  4865.7  302.06  4869.2  302.06  4873.7   303.6
  4882.9  304.84  4888.7  304.33  4904.1  306.15  5186.9   306.5  5261.5  307.74
    5298  309.58  5345.1  311.86    5351  312.78  5376.7  313.84  5419.5  317.02
  5439.9  317.63  5477.5   321.3  5503.2  321.07  5598.1  323.14  5686.3  327.56
#Mann= 5 ,-1 , 0
  4451.6     .17       0  4658.2     .15       0  4815.5     .09       0
  4904.1     .15       0    5298     .17       0
Bank Sta=4815.5,4904.1
XS Rating Curve= 0 ,0
Exp/Cntr=0.3,0.1

Type RM Length L Ch R = 1 ,7842    ,85,85,85
BEGIN DESCRIPTION:
Mapping XS 8478a26a
END DESCRIPTION:
XS GIS Cut Line= 6
      3728541.54      10210176.7      3728753.75     10209931.94
      3728796.72     10209933.24      3728873.55     10209869.44
      3728877.45      10209780.9      3729157.25     10209045.61
#Sta/Elev= 30
  4386.7   321.5  4494.5  317.68  4572.3   311.5  4586.6  311.33  4593.2  309.89
  4614.6  308.39  4678.7  305.39  4699.6  307.14    4710  309.92  4769.9  307.87
    4842  306.93  4854.1  308.05    4891  307.91  4906.3   309.2    4948  308.89
  4977.3  305.01  4985.7  305.78  4989.3  302.75  5009.4   305.9  5084.3  305.65
  5175.9  307.25  5270.7  308.13    5416  312.55  5465.4  315.17  5580.5   317.5
  5605.2  320.23  5665.5  323.42  5690.2  326.34    5715  326.93  5732.1   330.2
#Mann= 5 ,-1 , 0
  4386.7     .17       0  4614.6     .15       0  4985.7     .09       0
  5009.4     .15       0  5175.9     .17       0
#XS Ineff= 2 ,-1
    4590    4710  309.92    4740  4901.2   309.2
Permanent Ineff=
       F       F
Bank Sta=4985.7,5009.4
XS Rating Curve= 0 ,0
Exp/Cntr=0.3,0.1

Type RM Length L Ch R = 1 ,7757    ,236,236,236
BEGIN DESCRIPTION:
Mapping XS 135fd3a3
END DESCRIPTION:
XS GIS Cut Line= 4
      3728558.02     10210195.39      3728880.92     10209915.88
      3728974.67     10209742.27      3729234.58     10209064.79
#Sta/Elev= 30
  4435.6  321.07  4544.7  316.38  4587.4  312.16  4697.6  306.78  4765.1  304.27
  4849.6  305.78  4886.5  303.76  4892.2  302.34  4908.4  305.57    4974  304.88
  4981.8  304.26  4990.2  300.98  5012.1   302.9  5017.8  305.28    5034  305.16
  5048.2  299.93  5051.7  299.93  5055.9  304.87  5058.1  305.08  5157.7  306.07
  5224.8  308.26  5243.3  306.47  5270.1  308.67  5558.4  314.64  5637.7  317.39
  5692.4   320.5  5697.8   319.8  5752.5  325.58  5782.5  327.65  5785.6  329.18
#Mann= 5 ,-1 , 0
  4435.6     .17       0  4697.6     .15       0    5034     .09       0
  5058.1     .15       0  5270.1     .17       0
Bank Sta=5034,5058.1
XS Rating Curve= 0 ,0
Exp/Cntr=0.3,0.1

Type RM Length L Ch R = 1 ,7521    ,396,396,396
BEGIN DESCRIPTION:
WFSJR 006 15.0
END DESCRIPTION:
XS GIS Cut Line= 3
      3728567.86     10210211.07      3729146.72     10209946.26
      3729467.87     10209811.06
#Sta/Elev= 30
  4408.1  320.95  4542.9  314.74    4612  309.36  4762.4  302.21  4778.6  303.64
  4807.1   302.6  4830.1  304.19  4891.9  304.26  4899.2  303.24  4904.7  300.87
  4913.9  300.01  4920.4  298.07  4924.2  298.57  4927.7  301.15  4950.7  304.12
  4973.7  304.14  4990.9  303.29  4996.7  299.31  5012.9  301.27  5025.2  303.93
  5034.9  304.24    5072  303.05  5078.4  303.86  5095.7  303.77  5225.2  314.56
  5262.9  316.32  5278.1  318.19  5326.3  321.03  5349.3   321.6  5393.1  325.66
#Mann= 6 ,-1 , 0
  4408.1     .17       0  4762.4     .15       0  4924.2     .15       0
  4973.7     .09       0  5034.9     .15       0  5326.3     .17       0
Bank Sta=4973.7,5034.9
XS Rating Curve= 0 ,0
Exp/Cntr=0.3,0.1

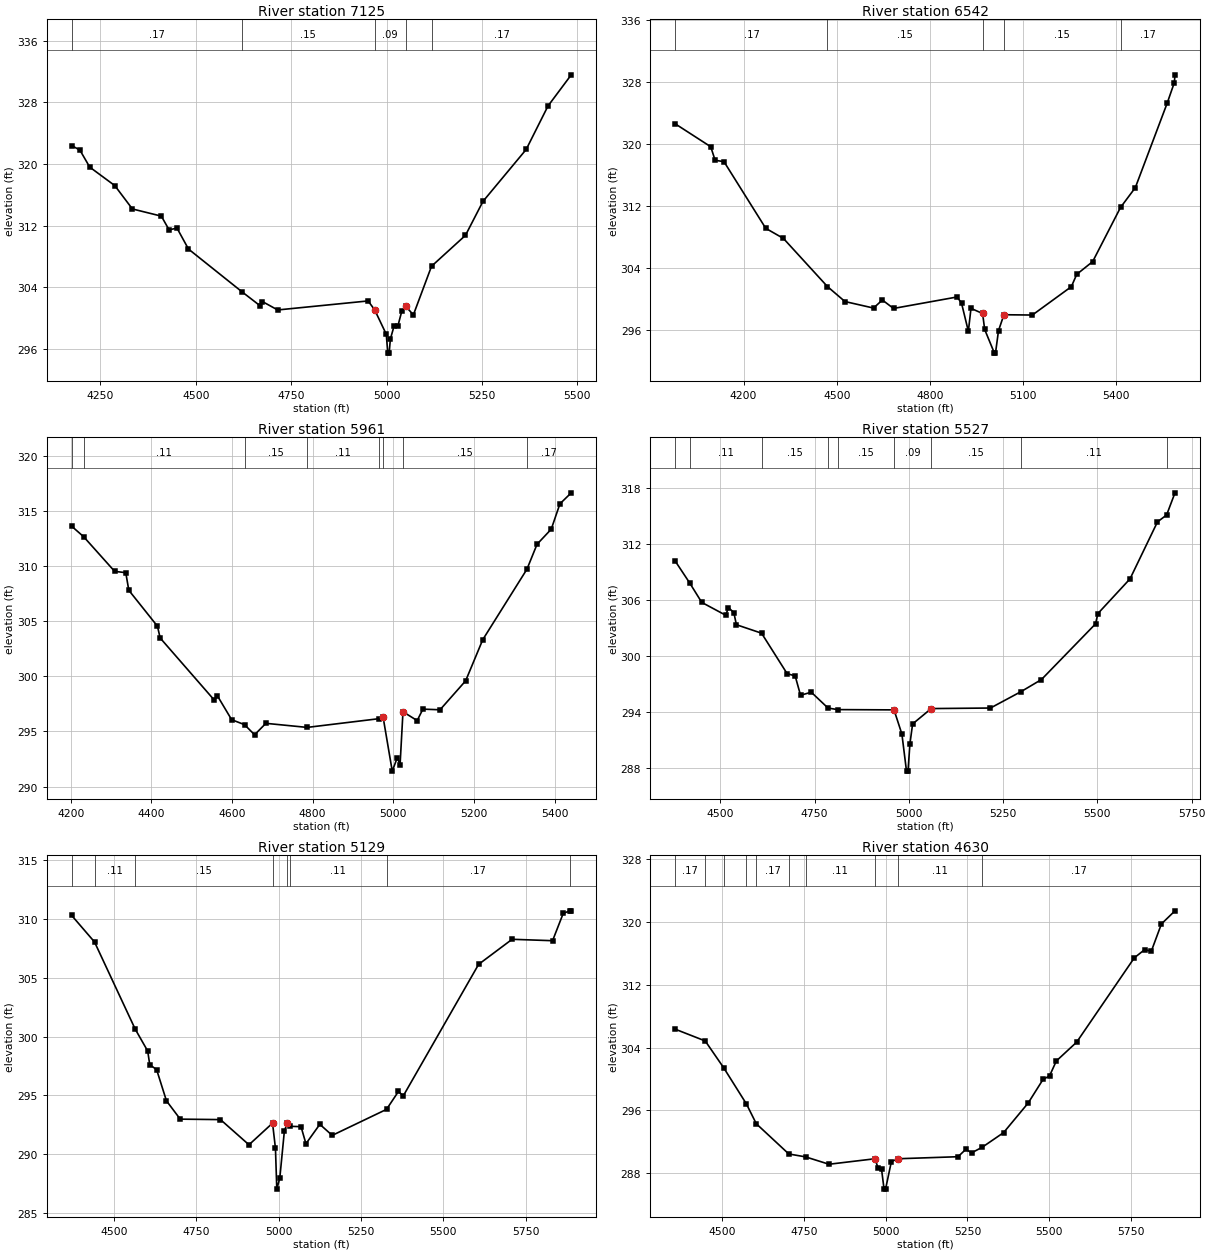
Type RM Length L Ch R = 1 ,7125    ,583,583,583
BEGIN DESCRIPTION:
WFSJR 006 14.0
END DESCRIPTION:
XS GIS Cut Line= 3
      3728516.56     10210404.59      3729529.74     10210220.56
      3729709.24     10210006.14
#Sta/Elev= 30
  4174.7  322.37  4196.3  321.79  4222.1  319.58  4287.8  317.18  4333.9  314.15
  4409.8  313.22  4430.1  311.44  4450.8  311.67  4480.9  308.95  4621.3   303.4
  4669.5  301.56  4674.6  302.14  4714.7  301.05  4951.7  302.22  4968.8  301.07
  4999.3   297.9  5003.3  295.45  5006.8  295.45  5010.1  297.29  5019.6  298.93
  5029.8  298.99  5039.9  300.88  5050.1  301.52  5070.4  300.42  5117.9  306.72
  5206.9  310.73  5252.7  315.13    5366  321.87  5423.2  327.51  5484.1  331.55
#Mann= 5 ,-1 , 0
  4174.7     .17       0  4621.3     .15       0  4968.8     .09       0
  5050.1     .15       0  5117.9     .17       0
Bank Sta=4968.8,5050.1
XS Rating Curve= 0 ,0
Exp/Cntr=0.3,0.1

Type RM Length L Ch R = 1 ,6542    ,581,581,581
BEGIN DESCRIPTION:
WFSJR 006 13.0
END DESCRIPTION:
XS GIS Cut Line= 3
      3728745.71     10211409.78      3729427.97     10210795.22
       3730053.1     10210504.39
#Sta/Elev= 30
  3980.8  322.57  4094.5  319.63  4108.7  317.88  4137.1  317.71  4271.6  309.11
  4328.4  307.81  4470.2   301.6  4526.5  299.67  4618.4  298.83  4646.8  299.87
  4682.7  298.78  4887.5  300.26  4901.7  299.45  4923.6  295.83    4932  298.79
  4969.4  298.13  4976.1  296.07  5007.4  293.02  5010.9  293.02  5020.6  295.92
    5038  297.97  5129.5  297.93    5255  301.59  5272.4  303.18  5323.6  304.82
  5413.2   311.8  5460.9  314.36  5563.5  325.26  5586.4   327.9  5588.5   328.9
#Mann= 5 ,-1 , 0
  3980.8     .17       0  4470.2     .15       0  4969.4     .09       0
    5038     .15       0  5413.2     .17       0
Bank Sta=4969.4,5038
XS Rating Curve= 0 ,0
Exp/Cntr=0.3,0.1

Type RM Length L Ch R = 1 ,5961    ,434,434,434
BEGIN DESCRIPTION:
WFSJR 006 12.0
END DESCRIPTION:
XS GIS Cut Line= 3
      3729267.84     10211611.09      3729797.74     10211014.96
      3730117.87     10210711.06
#Sta/Elev= 30
  4202.4  313.64    4232  312.69    4309  309.54  4336.6  309.42  4344.2  307.82
  4415.2  304.56  4421.9  303.49  4556.6  297.83  4563.7  298.25  4599.2  296.07
  4631.1  295.62  4656.1   294.7  4684.1  295.74  4786.4  295.37  4964.1  296.16
  4974.7  296.33  4997.5   291.4    5010  292.62  5016.9  291.99  5024.1  296.79
  5059.3  295.99  5073.5  297.03    5116  296.97  5179.5   299.6    5222  303.34
  5331.6  309.74  5356.6     312  5391.8  313.37  5413.3  315.67  5441.4  316.67
#Mann= 8 ,-1 , 0
  4202.4     .17       0    4232     .11       0  4631.1     .15       0
  4786.4     .11       0  4964.1     .15       0  4974.7     .09       0
  5024.1     .15       0  5331.6     .17       0
Bank Sta=4974.7,5024.1
XS Rating Curve= 0 ,0
Exp/Cntr=0.3,0.1

Type RM Length L Ch R = 1 ,5527    ,398,398,398
BEGIN DESCRIPTION:
WFSJR 006 11.0
END DESCRIPTION:
XS GIS Cut Line= 3
      3729467.01     10211829.11      3729938.39     10211316.05
      3730318.62     10210816.02
#Sta/Elev= 30
  4380.9  310.17  4418.6  307.86  4450.8  305.76  4514.3  304.38  4521.7   305.2
  4535.9  304.66  4542.7  303.36  4609.4  302.45  4677.1  298.11  4698.6  297.85
  4712.8  295.78  4741.2  296.11  4785.6  294.41  4811.2  294.24  4960.7  294.21
  4981.6  291.61  4993.8  287.63  4997.8  287.63  5002.9  290.57    5010   292.7
  5059.3  294.35  5216.5  294.41  5297.9  296.18  5351.7  297.47  5495.1  303.45
  5501.4  304.56  5586.6  308.29  5659.4  314.41  5683.6  315.15  5705.8  317.53
#Mann= 9 ,-1 , 0
  4380.9     .17       0  4418.6     .11       0  4609.4     .15       0
  4785.6     .11       0  4811.2     .15       0  4960.7     .09       0
  5059.3     .15       0  5297.9     .11       0  5683.6     .17       0
Bank Sta=4960.7,5059.3
XS Rating Curve= 0 ,0
Exp/Cntr=0.3,0.1

Type RM Length L Ch R = 1 ,5129    ,499,499,499
BEGIN DESCRIPTION:
WFSJR 006 10.0
END DESCRIPTION:
XS GIS Cut Line= 3
      3729567.88     10212011.05       3730196.2     10211576.47
      3730480.06     10210878.55
#Sta/Elev= 30
  4371.4  310.31  4440.9  308.05  4564.3  300.65  4602.4  298.78  4608.6  297.62
  4629.5   297.2  4659.3  294.55  4701.2  292.99  4823.5  292.95    4910  290.81
  4981.6  292.65  4990.4  290.51  4994.5  287.04  5003.6  287.98  5017.4  291.95
  5026.2  292.67    5034  292.38  5068.1  292.35    5083   290.9  5125.2  292.55
  5162.8  291.61  5327.7  293.82  5363.9  295.34  5378.7  294.97  5607.5  306.15
  5709.2  308.28  5832.1  308.16  5864.4  310.48  5884.3   310.7  5888.8   310.7
#Mann= 8 ,-1 , 0
  4371.4     .17       0  4440.9     .11       0  4564.3     .15       0
  4981.6     .09       0  5026.2     .15       0    5034     .11       0
  5327.7     .17       0  5884.3     .15       0
Bank Sta=4981.6,5026.2
XS Rating Curve= 0 ,0
Exp/Cntr=0.3,0.1

Type RM Length L Ch R = 1 ,4630    ,653,653,653
BEGIN DESCRIPTION:
WFSJR 006 9.0
END DESCRIPTION:
XS GIS Cut Line= 3
      3729670.17     10212110.32      3730438.39     10212055.64
      3731167.82     10211861.08
#Sta/Elev= 30
  4358.3  306.33  4449.4  304.84  4506.1   301.4  4575.2  296.81  4605.3  294.29
  4704.5  290.44  4755.7  290.07  4827.2  289.13  4967.5  289.83    4977  288.66
  4987.6   288.5  4995.3  285.96  4999.9  285.96  5017.6  289.47  5037.7  289.83
  5221.1  290.09  5245.1  291.04  5262.5  290.58  5295.4  291.31  5360.2  293.16
  5435.2  296.93  5480.5  299.93  5500.5  300.39  5521.2  302.29  5583.3  304.69
  5759.2  315.43  5790.9  316.48    5811  316.26    5842  319.75  5883.4  321.42
#Mann= 10 ,-1 , 0
  4358.3     .17       0  4449.4     .11       0  4506.1     .17       0
  4575.2     .11       0  4605.3     .17       0  4704.5     .15       0
  4755.7     .11       0  4967.5     .06       0  5037.7     .11       0
  5295.4     .17       0
Bank Sta=4967.5,5037.7
XS Rating Curve= 0 ,0
Exp/Cntr=0.3,0.1

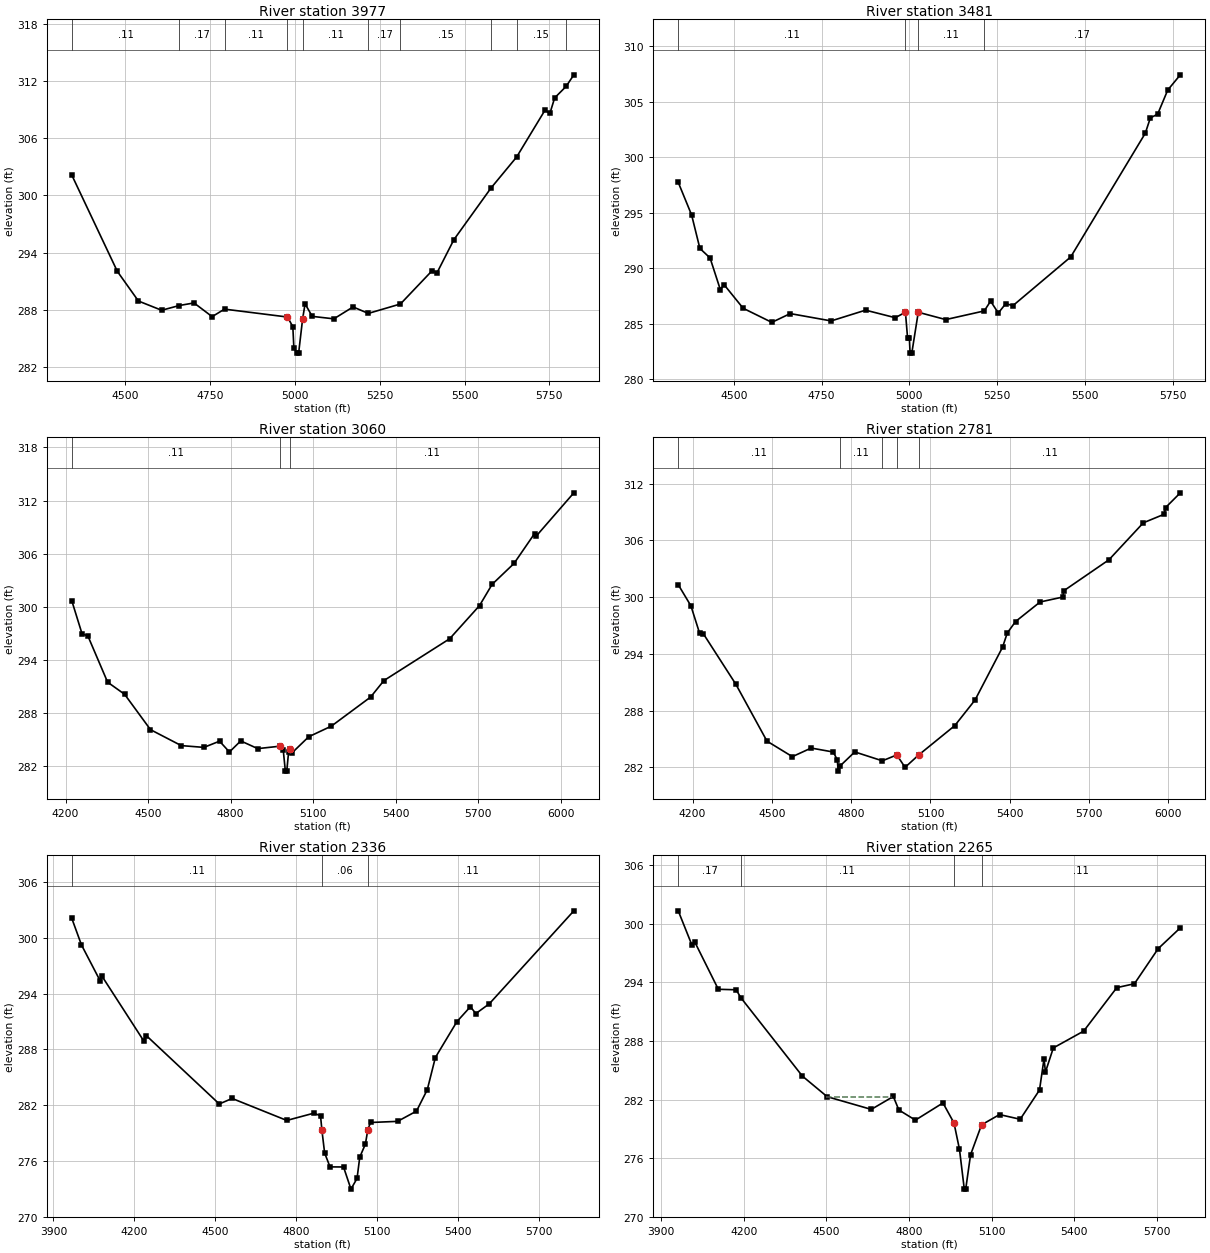
Type RM Length L Ch R = 1 ,3977    ,496,496,496
BEGIN DESCRIPTION:
WFSJR 006 8.0
END DESCRIPTION:
XS GIS Cut Line= 3
      3729917.89     10212861.06      3730538.33     10212644.03
      3731117.85     10212061.08
#Sta/Elev= 30
  4342.7  302.14    4477  292.02  4539.1  288.91  4607.5  287.94  4659.7  288.44
  4702.9  288.71  4756.3  287.27  4792.7  288.06  4978.3  287.23    4994  286.22
  4997.1     284  5006.5  283.44  5011.1  283.44    5023  287.07  5030.1  288.61
  5051.2   287.3  5114.9  287.04  5171.5  288.29  5216.4  287.61  5311.1   288.6
  5404.8  292.11  5418.9  291.88  5468.5  295.35    5578  300.78  5653.4  304.03
  5737.2  308.96  5751.3   308.6  5765.5  310.24  5799.1  311.44    5822  312.66
#Mann= 10 ,-1 , 0
  4342.7     .11       0  4659.7     .17       0  4792.7     .11       0
  4978.3     .06       0    5023     .11       0  5216.4     .17       0
  5311.1     .15       0    5578     .17       0  5653.4     .15       0
  5799.1     .17       0
Bank Sta=4978.3,5023
XS Rating Curve= 0 ,0
Exp/Cntr=0.3,0.1

Type RM Length L Ch R = 1 ,3481    ,421,421,421
BEGIN DESCRIPTION:
WFSJR 006 7.0
END DESCRIPTION:
XS GIS Cut Line= 3
      3730017.82     10213311.09       3730622.3      10213051.4
      3731217.83     10212561.09
#Sta/Elev= 30
  4342.1  297.73  4380.2  294.79  4403.7  291.78  4432.7  290.92  4461.9  288.07
  4472.7  288.51  4526.9  286.39  4608.5  285.12    4661  285.91  4777.5  285.25
  4875.4  286.22  4959.9  285.54  4988.9  286.03  4994.9  283.74    5000  283.74
  5002.1  282.35    5007  282.35  5025.4  286.03  5103.6  285.37  5213.3  286.15
  5231.3  287.03  5253.3  285.96  5274.3   286.8  5295.1  286.63  5459.4  291.01
  5671.7  302.15  5686.1  303.53  5706.9  303.87  5735.6  306.04  5771.4  307.41
#Mann= 4 ,-1 , 0
  4342.1     .11       0  4988.9     .06       0  5025.4     .11       0
  5213.3     .17       0
Bank Sta=4988.9,5025.4
XS Rating Curve= 0 ,0
Exp/Cntr=0.3,0.1

Type RM Length L Ch R = 1 ,3060    ,279,279,279
BEGIN DESCRIPTION:
Mapping XS 2c6489b6
END DESCRIPTION:
XS GIS Cut Line= 3
      3730011.27     10213602.52      3731107.66     10213336.89
      3731797.79     10213248.34
#Sta/Elev= 30
  4222.7   300.7  4260.3  296.93  4280.9  296.74  4352.9   291.5  4414.7  290.13
  4508.7  286.14  4620.5  284.34  4702.8  284.14  4759.5  284.84  4795.4  283.62
  4836.5  284.87  4898.3     284  4980.6  284.28  4990.9  283.84  4998.6  281.46
  5003.7  281.46  5010.4  283.63  5015.6  283.97  5021.7  283.49  5083.5  285.34
  5165.8  286.54  5308.3  289.82  5356.6  291.68  5595.5   296.4  5703.9  300.14
  5749.7  302.54  5829.3   304.9  5903.9  308.27  5908.9  307.95  6046.6  312.87
#Mann= 3 , 0 , 0
  4222.7     .11       0  4980.6     .06       0  5015.6     .11       0
Bank Sta=4980.6,5015.6
XS Rating Curve= 0 ,0
Exp/Cntr=0.3,0.1

Type RM Length L Ch R = 1 ,2781    ,445,445,445
BEGIN DESCRIPTION:
WFSJR 006 6.0
END DESCRIPTION:
XS GIS Cut Line= 3
      3730076.41      10213909.8      3731362.87     10213521.78
      3731917.52     10213493.14
#Sta/Elev= 30
  4145.9  301.31  4193.9  299.07  4226.9  296.16  4241.4   296.1  4364.1  290.77
  4481.6  284.77  4577.6  283.13  4648.8  284.04  4732.3  283.62  4747.8  282.78
  4750.7   281.6  4756.3   282.1  4813.7  283.63  4917.9  282.69  4972.6  283.31
  5003.9     282    5055   283.3  5191.9  286.41  5268.6  289.12  5372.8  294.71
  5390.4   296.2  5421.7  297.41  5514.6  299.48    5600     300    5605  300.68
    5775  303.94  5905.1  307.85  5984.2  308.76  5989.2  309.46    6045  311.02
#Mann= 5 ,-1 , 0
  4145.9     .11       0  4756.3     .11       0  4917.9     .11       0
  4972.6     .06       0    5055     .11       0
Bank Sta=4972.6,5055
XS Rating Curve= 0 ,0
Exp/Cntr=0.3,0.1

Type RM Length L Ch R = 1 ,2336    ,71,71,71
BEGIN DESCRIPTION:
WFSJR 006 5.0
END DESCRIPTION:
XS GIS Cut Line= 3
      3730092.03     10213959.28      3731315.99      10214034.8
       3731951.4     10214037.41
#Sta/Elev= 30
    3968  302.09  4003.9  299.23  4073.6  295.35  4078.6  295.93  4234.3  288.94
    4245  289.47  4514.9  282.14  4562.7  282.73  4765.3  280.37  4865.5  281.15
  4890.4  280.87  4895.6   279.3  4905.6  276.87  4925.6  275.38  4975.7  275.37
  5003.2  272.99  5025.8  274.14  5035.9  276.43  5056.7  277.82  5065.9  279.39
  5075.9  280.15  5176.1  280.27  5246.2  281.37  5286.2  283.67  5316.2  287.13
  5396.2  290.99  5446.2  292.59  5466.2  291.85  5516.2   292.9  5829.7  302.89
#Mann= 3 , 0 , 0
    3968     .11       0  4895.6     .06       0  5065.9     .11       0
Bank Sta=4895.6,5065.9
XS Rating Curve= 0 ,0
Exp/Cntr=0.3,0.1

Type RM Length L Ch R = 1 ,2265    ,268,268,268
BEGIN DESCRIPTION:
Mapping XS d7f93754
END DESCRIPTION:
XS GIS Cut Line= 3
      3730107.69     10214050.43      3731250.89      10214094.7
      3731927.95     10214136.36
#Sta/Elev= 30
  3961.9  301.31  4012.1  297.77  4022.1  298.11  4107.4  293.28  4172.2  293.23
  4188.6  292.44  4412.4   284.4  4502.5  282.29  4662.6  280.99  4742.6  282.31
  4762.7  280.93  4822.7  279.89  4922.8  281.65  4962.8   279.6  4982.8  276.89
  5000.2  272.83  5005.4  272.83  5022.9  276.34  5062.9  279.41  5128.1  280.46
  5203.1  279.98  5273.2  282.97  5289.7  286.19  5294.7   284.8  5323.3  287.28
  5433.5     289  5553.8  293.45  5617.8  293.85    5704  297.44  5784.3  299.57
#Mann= 4 ,-1 , 0
  3961.9     .17       0  4188.6     .11       0  4962.8     .06       0
  5062.9     .11       0
#XS Ineff= 2 ,-1
    4500  4732.6  282.27    4740  4922.8  281.65
Permanent Ineff=
       F       F
Bank Sta=4962.8,5062.9
XS Rating Curve= 0 ,0
Exp/Cntr=0.3,0.1

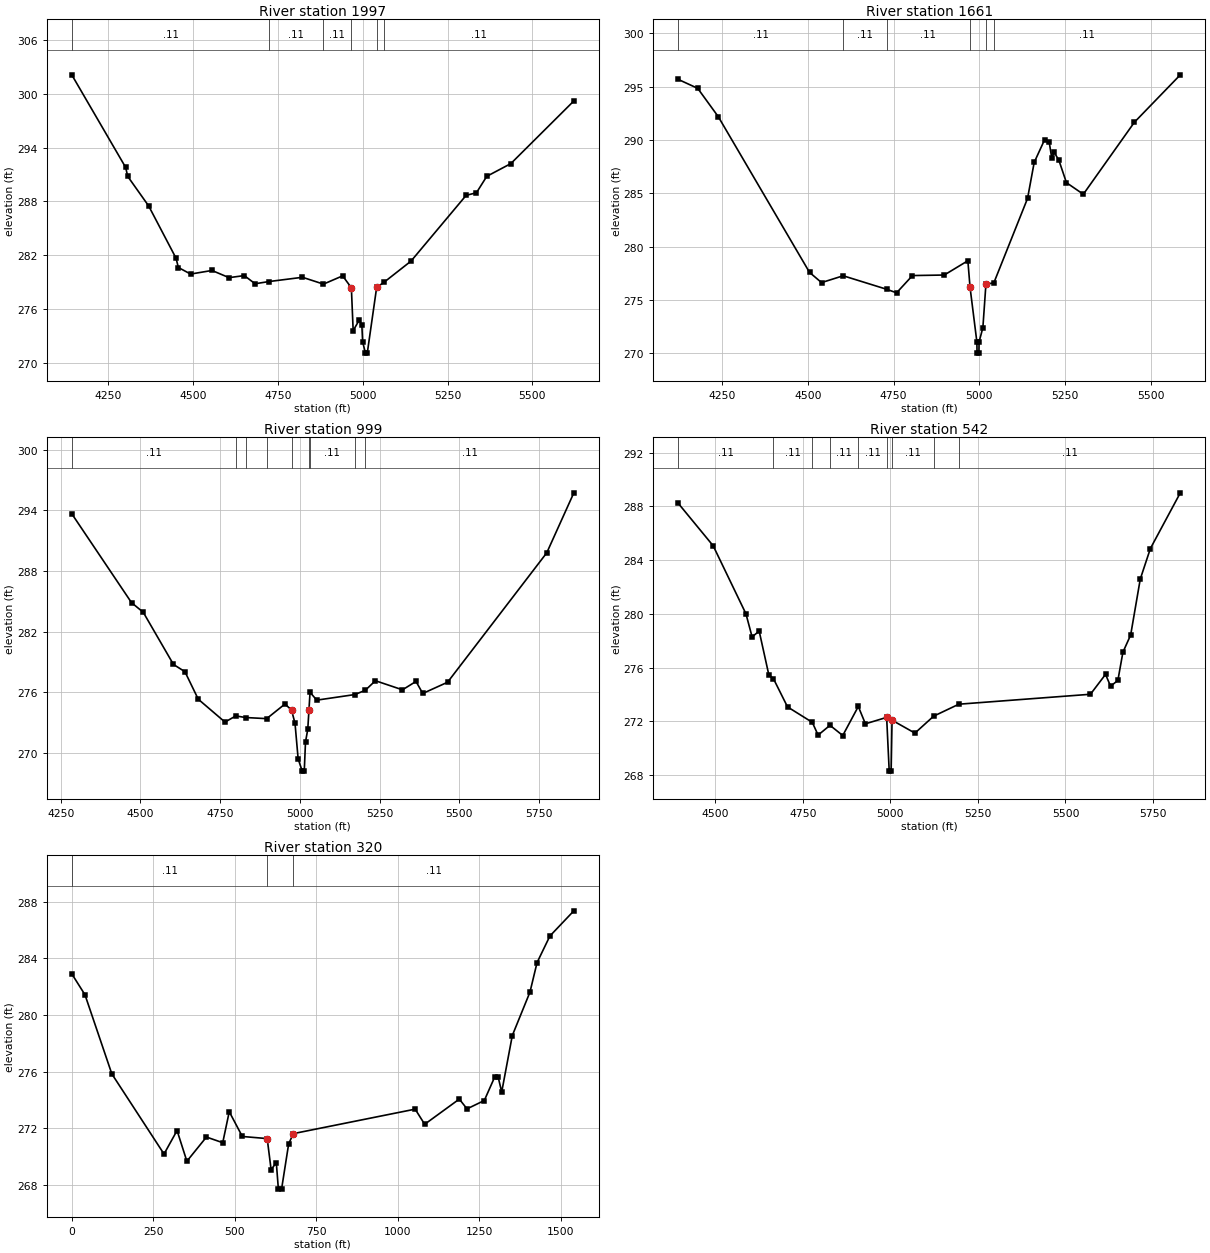
Type RM Length L Ch R = 1 ,1997    ,336,336,336
BEGIN DESCRIPTION:
WFSJR 006 4.0
END DESCRIPTION:
XS GIS Cut Line= 3
      3730517.86     10214561.07      3731327.41      10214275.9
      3731940.97     10214170.22
#Sta/Elev= 30
  4141.7   302.1  4300.7  291.78  4306.6  290.79  4368.5  287.49  4449.2  281.67
  4456.1  280.63  4492.3   279.9  4555.2   280.3  4605.6   279.5  4650.6  279.73
  4682.4  278.82  4724.1  279.07  4822.2  279.54  4884.1  278.78  4940.7   279.7
  4966.4  278.37  4971.7  273.59  4989.9   274.8  4997.3  274.19  4999.7  272.34
  5007.9  271.09  5013.3  271.09    5041  278.42  5062.2  278.97  5142.5  281.35
  5304.9  288.67  5335.3  288.96  5365.8  290.79  5436.8  292.21  5622.6  299.19
#Mann= 6 ,-1 , 0
  4141.7     .11       0  4724.1     .11       0  4884.1     .11       0
  4966.4     .06       0    5041     .11       0  5062.2     .11       0
Bank Sta=4966.4,5041
XS Rating Curve= 0 ,0
Exp/Cntr=0.3,0.1

Type RM Length L Ch R = 1 ,1661    ,662,662,662
BEGIN DESCRIPTION:
WFSJR 006 3.0
END DESCRIPTION:
XS GIS Cut Line= 3
      3730625.91     10214943.65      3731576.41     10214519.18
       3731896.7     10214240.55
#Sta/Elev= 30
  4121.3  295.69  4178.2  294.85  4238.2  292.19  4504.5  277.58  4539.6  276.62
  4602.8  277.26  4729.9  275.99  4758.6  275.66    4805  277.28  4897.8  277.33
  4966.7  278.67    4973  276.19    4993  271.05  4993.5     270  4998.9     270
  4999.4  271.05  5010.5  272.39  5019.4  276.47  5042.6   276.6  5140.9  284.52
  5160.3   287.9  5190.7  290.03    5204  289.83  5211.6   288.3  5218.3  288.87
  5232.5  288.09  5254.4     286  5303.7  284.91  5452.8  291.67  5586.8  296.12
#Mann= 6 ,-1 , 0
  4121.3     .11       0  4602.8     .11       0  4729.9     .11       0
    4973     .06       0  5019.4     .11       0  5042.6     .11       0
Bank Sta=4973,5019.4
XS Rating Curve= 0 ,0
Exp/Cntr=0.3,0.1

Type RM Length L Ch R = 1 ,999     ,457,457,457
BEGIN DESCRIPTION:
WFSJR 006 2.0
END DESCRIPTION:
XS GIS Cut Line= 3
      3730807.82     10215289.35      3731503.03     10215121.46
      3732112.41     10214515.61
#Sta/Elev= 30
  4284.8  293.65  4472.2  284.86  4508.9  283.91  4603.7  278.75  4639.7  278.03
  4681.5  275.31  4765.3  273.05  4799.2  273.66  4830.1   273.5  4896.1  273.39
  4953.5  274.84  4974.1  274.23  4984.9  272.92  4994.7  269.41  5007.5   268.2
  5013.9   268.2  5017.8  271.09  5024.9  272.34  5028.7 274.294    5032  275.99
  5053.2  275.22  5172.2  275.77  5205.1  276.19    5237  277.14  5321.9  276.24
  5364.3  277.07  5385.5  275.88  5463.3  276.99  5774.4  289.79  5859.3  295.72
#Mann= 9 ,-1 , 0
  4284.8     .11       0  4799.2     .11       0  4830.1     .11       0
  4896.1     .11       0  4974.1     .06       0  5028.7     .09       0
    5032     .11       0  5172.2     .17       0  5205.1     .11       0
#XS Ineff= 1 ,-1
    5032    5195  275.99
Permanent Ineff=
       F
Bank Sta=4974.1,5028.7
XS Rating Curve= 0 ,0
Exp/Cntr=0.3,0.1

Type RM Length L Ch R = 1 ,542     ,222,222,222
BEGIN DESCRIPTION:
WFSJR 006 1.0
END DESCRIPTION:
XS GIS Cut Line= 3
      3730959.18     10215623.35      3731662.35     10215521.78
      3732117.87     10214961.05
#Sta/Elev= 30
  4394.8  288.23  4494.5  285.07    4588  280.01  4605.6  278.29  4625.8  278.72
  4653.3  275.47  4666.3  275.19  4706.7  273.08  4777.4  271.93    4794  270.98
  4827.9  271.71  4864.3  270.95  4908.7  273.11    4929  271.82  4989.6   272.3
  4996.9   268.3  5002.4   268.3    5005  272.09  5070.3  271.13  5123.7  272.39
  5195.6  273.28  5571.2  274.02  5614.3   275.5  5628.7  274.62  5649.5  275.05
  5663.9  277.15    5686  278.43  5713.4  282.59  5742.2  284.86  5827.7  289.01
#Mann= 9 ,-1 , 0
  4394.8     .11       0  4666.3     .11       0  4777.4     .11       0
  4827.9     .11       0  4908.7     .11       0  4989.6     .06       0
    5005     .11       0  5123.7     .11       0  5195.6     .11       0
Bank Sta=4989.6,5005
XS Rating Curve= 0 ,0
Exp/Cntr=0.3,0.1

Type RM Length L Ch R = 1 ,320     ,0,0,0
XS GIS Cut Line= 4
        3731065.     10215724.56      3731613.74      10215743.8
      3731908.01     10215581.04      3732160.61     10214976.87
#Sta/Elev= 30
       0  282.91    40.5  281.43   122.9  275.84     283  270.18     323  271.84
   353.1  269.67   413.1  271.38   463.1  270.98   483.1  273.17   523.2  271.42
   599.5  271.27   611.5  269.08   627.5  269.57   633.8   267.7   643.6   267.7
   665.3  270.89   679.5  271.62  1053.4  273.35  1082.6  272.28  1188.8  274.06
  1212.5  273.37  1265.5  273.96  1297.2  275.61  1307.7  275.65  1318.9  274.56
  1351.4  278.55  1405.6  281.62  1427.3   283.7  1466.7  285.58  1540.2  287.36
#Mann= 3 , 0 , 0
       0     .11       0   599.5     .06       0   679.5     .11       0
Bank Sta=599.5,679.5
XS Rating Curve= 0 ,0
Exp/Cntr=0.3,0.1

Chan Stop Cuts=-1
Use User Specified Reach Order=0
Composite Channel Slope=5