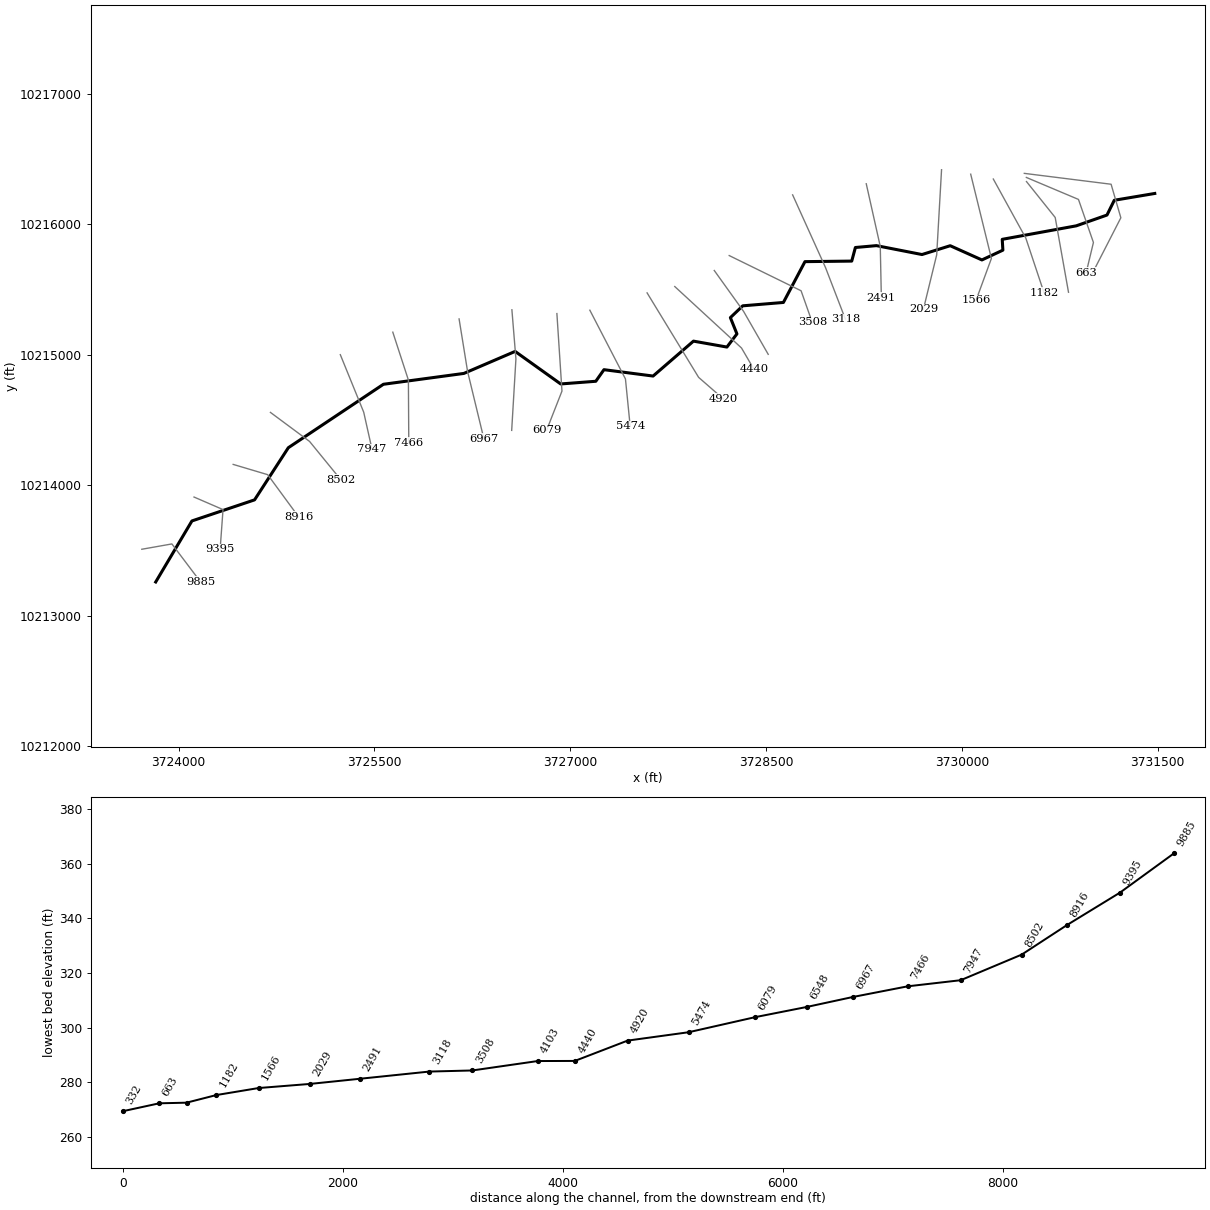
--- WFSJR 007.prj (project) ---

Proj Title=WFSJR 007 Base Level Engineering
Current Plan=p01
Default Exp/Contr=0.3,0.1
English Units
Geom File=g01
Flow File=f01
Flow File=f02
Plan File=p01
Y Axis Title=Elevation
X Axis Title(PF)=Main Channel Distance
X Axis Title(XS)=Station
BEGIN DESCRIPTION:
WFSJR 007
END DESCRIPTION:
DSS Export Rating Curves= 0
DSS Export Rating Curve Sorted= 0
DSS Export Volume Flow Curves= 0
DXF OffsetX= 0
DXF OffsetY= 0
DXF ScaleX= 1
DXF ScaleY= 10

--- WFSJR 007.p01 (plan) ---

Plan Title=Multiple Run
Program Version=4.10
Short Identifier=Multiple
Geom File=g01
Flow File=f01
Subcritical Flow
K Sum by GR= 0
Std Step Tol= 0.01
Critical Tol= 0.01
Num of Std Step Trials= 20
Max Error Tol= 0.3
Flow Tol Ratio= 0.001
Split Flow NTrial= 30
Split Flow Tol= 0.02
Split Flow Ratio= 0.02
Log Output Level= 0
Friction Slope Method= 1
Unsteady Friction Slope Method= 2
Unsteady Bridges Friction Slope Method= 1
Parabolic Critical Depth
Global Vel Dist= 1 , 1 , 1
Global Log Level= 0
CheckData=True
Encroach Param=-1 ,0,0, 0
BEGIN DESCRIPTION:
Multiple Run
END DESCRIPTION:
Computation Interval=1HOUR
Output Interval=1HOUR
Run HTab= 0
Run UNet= 0
Run PostProcess= 0
Run WQNet= 0
UNET Theta= 1
UNET Theta Warmup= 1
UNET ZTol= 0.02
UNET ZSATol= 0.05
UNET MxIter= 20
UNET MaxInSteps= 0
UNET DtIC= 0
UNET DtMin= 0
UNET MaxCRTS= 20
UNET WFStab= 2
UNET SFStab= 1
UNET WFX= 1
UNET SFX= 1
UNET DSS MLevel= 4
UNET DZMax Abort= 100
UNET Convert EG Bridges= 0
UNET Use Existing IB Tables=-1
UNET Froude Reduction=False
UNET Froude Limit= 1
UNET Froude Power= 10
UNET Time Slicing=0,0, 5
UNET Junction Losses=0
Instantaneous Interval=1HOUR
Write IC File= 0
Write IC File at Sim End=0
Echo Input=False
Echo Parameters=False
Echo Output=False
Write Detailed= 0
WQ AD Non Conservative
WQ ULTIMATE=-1
WQ Max Comp Step=1HOUR
WQ Output Interval=15MIN
WQ Output Selected Increments= 0
WQ Output face flow=0
WQ Output face velocity=0
WQ Output face area=0
WQ Output face dispersion=0
WQ Output cell volume=0
WQ Output cell surface area=0
WQ Output cell continuity=0
WQ Output cumulative cell continuity=0
WQ Output face conc=0
WQ Output face dconc_dx=0
WQ Output face courant=0
WQ Output face peclet=0
WQ Output face adv mass=0
WQ Output face disp mass=0
WQ Output cell mass=0
WQ Output cell source sink temp=0
WQ Output cell source sink nsm=0
WQ Output MaxMinRange=-1
WQ Daily Max Min Mean=-1
WQ Daily Range=0
WQ Daily Time=0
WQ Create Restart=0
WQ Fixed Restart=0
WQ System Summary=0
WQ Use Fixed Temperature=0
Sorting and Armoring Iterations= 10
XS Update Threshold= 0.02
Hydraulics Update Threshold= 0.02
Energy Slope Method= 1
Volume Change Method= 0
XS Weighting Method= 0
Number of US Weighted Cross Sections= 1
Number of DS Weighted Cross Sections= 1
Upstream XS Weight=0.25
Main XS Weight=0.5
Downstream XS Weight=0.25
Number of DS XS's Weighted with US Boundary= 1
Upstream Boundary Weight= 1
Weight of XSs Associated with US Boundary= 0
Number of US XS's Weighted with DS Boundary= 1
Downstream Boundary Weight= 0.5
Weight of XSs Associated with DS Boundary= 0.5
Sediment Output Level= 4
Mass or Volume Output= 0
Output Increment Type= 1
Profile and TS Output Increment= 10
XS Output Flag= 0
XS Output Increment= 10
Disregard all LS=0
Disregard all Conn=0
Disregard all Breaches=0
Disregard all Pumps=0

--- WFSJR 007.f01 (steady flow) ---

Flow Title=Multiple
Program Version=4.10
Number of Profiles= 7
Profile Names=10-year,25-year,50-year,1pct_min,100-year,1pct_plu,500-year
River Rch & RM=WFSJR 007,Reach-1         ,9885
     807    1135    1576     721    2178    6577    4298
Boundary for River Rch & Prof#=WFSJR 007,Reach-1         , 1
Up Type= 0
Dn Type= 3
Dn Slope=0.008
Boundary for River Rch & Prof#=WFSJR 007,Reach-1         , 2
Up Type= 0
Dn Type= 3
Dn Slope=0.008
Boundary for River Rch & Prof#=WFSJR 007,Reach-1         , 3
Up Type= 0
Dn Type= 3
Dn Slope=0.008
Boundary for River Rch & Prof#=WFSJR 007,Reach-1         , 4
Up Type= 0
Dn Type= 3
Dn Slope=0.008
Boundary for River Rch & Prof#=WFSJR 007,Reach-1         , 5
Up Type= 0
Dn Type= 3
Dn Slope=0.008
Boundary for River Rch & Prof#=WFSJR 007,Reach-1         , 6
Up Type= 0
Dn Type= 3
Dn Slope=0.008
Boundary for River Rch & Prof#=WFSJR 007,Reach-1         , 7
Up Type= 0
Dn Type= 3
Dn Slope=0.008
DSS Import GetInterval= 0
DSS Import GetPeak= 0
DSS Import FillOption= 0

--- WFSJR 007.f02 (steady flow) ---

Flow Title=Orig_BLE_Flow
Program Version=4.10
Number of Profiles= 7
Profile Names=10-year,25-year,50-year,1pct_min,100-year,1pct_plu,500-year
River Rch & RM=WFSJR 007,Reach-1         ,9885
     807    1113    1370     555    1675    5058    2499
Boundary for River Rch & Prof#=WFSJR 007,Reach-1         , 1
Up Type= 0
Dn Type= 3
Dn Slope=0.008
Boundary for River Rch & Prof#=WFSJR 007,Reach-1         , 2
Up Type= 0
Dn Type= 3
Dn Slope=0.008
Boundary for River Rch & Prof#=WFSJR 007,Reach-1         , 3
Up Type= 0
Dn Type= 3
Dn Slope=0.008
Boundary for River Rch & Prof#=WFSJR 007,Reach-1         , 4
Up Type= 0
Dn Type= 3
Dn Slope=0.008
Boundary for River Rch & Prof#=WFSJR 007,Reach-1         , 5
Up Type= 0
Dn Type= 3
Dn Slope=0.008
Boundary for River Rch & Prof#=WFSJR 007,Reach-1         , 6
Up Type= 0
Dn Type= 3
Dn Slope=0.008
Boundary for River Rch & Prof#=WFSJR 007,Reach-1         , 7
Up Type= 0
Dn Type= 3
Dn Slope=0.008
DSS Import GetInterval= 0
DSS Import GetPeak= 0
DSS Import FillOption= 0

--- WFSJR 007.g01 (geometry) ---

Geom Title=Existing Conditions
Program Version=4.10

River Reach=WFSJR 007       ,Reach-1
Reach XY= 30
      3723824.22     10213260.28      3724101.79     10213727.96
      3724581.61     10213889.41      3724840.29     10214288.91
      3725568.93     10214775.01      3726184.86     10214858.02
      3726577.85     10215026.76      3726926.72     10214777.45
      3727195.85     10214797.98      3727258.38     10214886.84
       3727634.8     10214837.99      3727944.14      10215105.5
      3728200.41     10215060.12      3728277.09     10215160.95
      3728226.91     10215285.67      3728321.67     10215376.05
      3728633.11     10215401.82      3728798.29     10215714.51
      3729156.68      10215718.7      3729184.64     10215822.86
      3729345.79     10215837.16      3729694.91     10215768.92
      3729911.08     10215836.51      3730154.04     10215727.53
       3730314.6      10215802.5      3730309.59     10215885.37
      3730876.73     10215988.81      3731112.18     10216071.49
      3731168.02      10216184.7      3731478.23     10216236.84

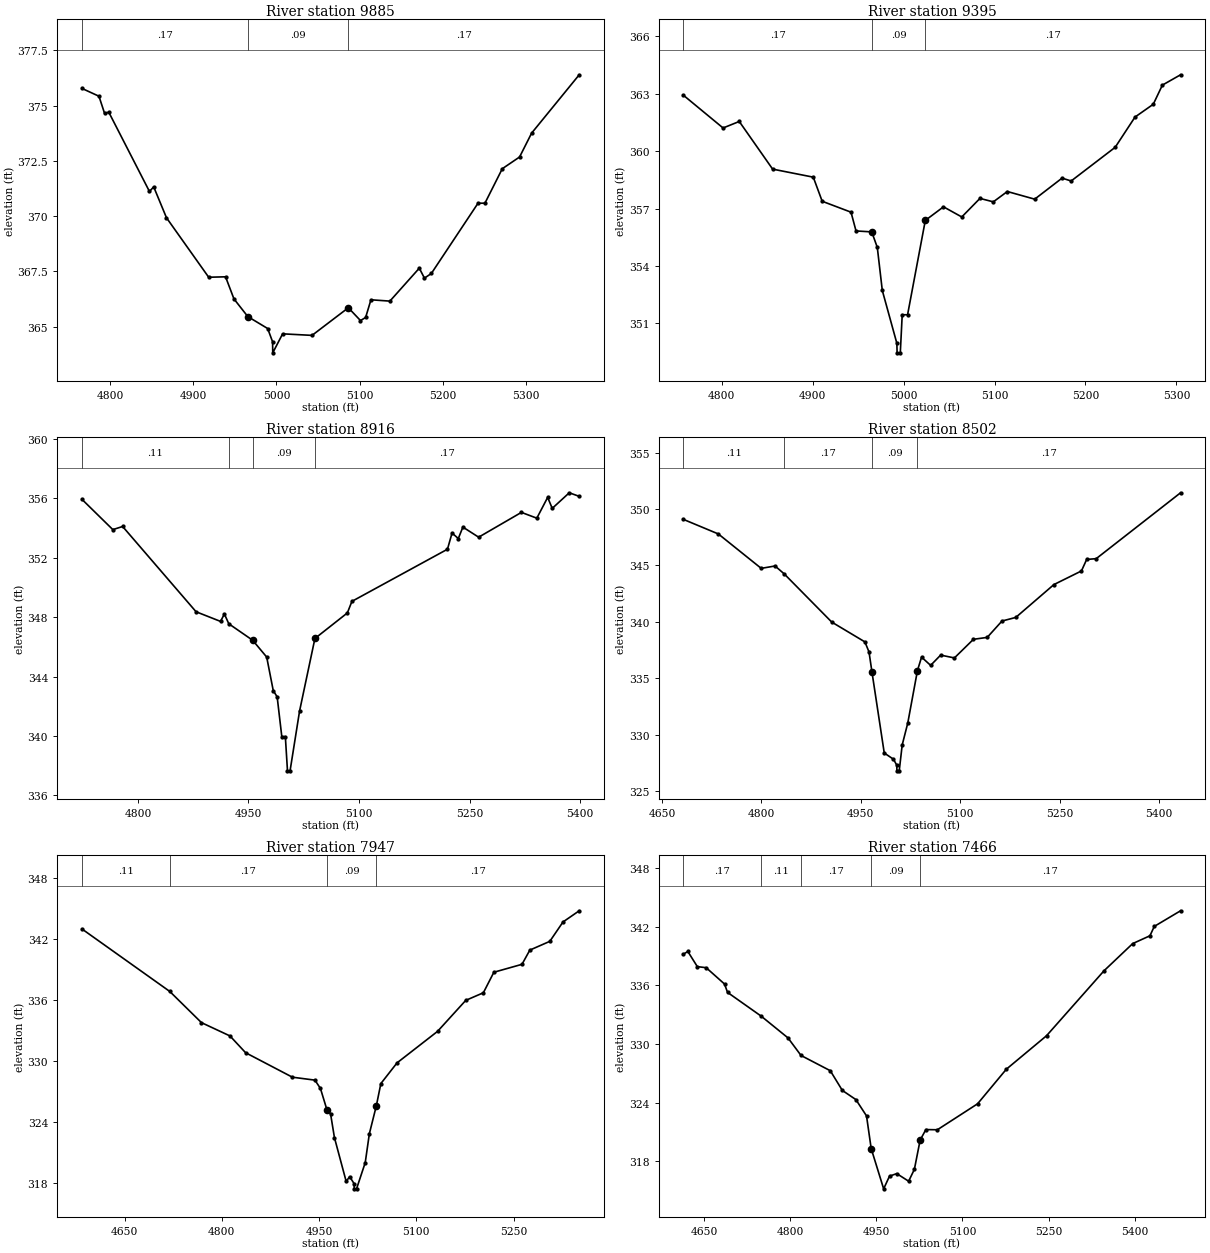
Type RM Length L Ch R = 1 ,9885    ,490,490,490
BEGIN DESCRIPTION:
WFSJR 007 19.0
END DESCRIPTION:
XS GIS Cut Line= 3
      3723717.83     10213511.07      3723948.25     10213551.84
      3724167.86     10213261.05
#Sta/Elev= 30
    4766  375.77  4786.3  375.42  4793.1  374.64  4798.1   374.7  4847.1  371.11
  4852.2  371.32  4867.6  369.92  4918.4  367.23  4938.7  367.25  4948.8  366.25
  4965.5  365.45  4989.4  364.91  4995.3  364.31  4995.5  363.81  5007.4  364.67
  5042.8   364.6  5086.5  365.85  5101.1  365.27  5107.3  365.41  5113.7  366.21
  5136.5  366.15  5171.9  367.64  5178.1  367.19  5186.4   367.4  5242.6  370.58
  5250.9  370.58  5271.8  372.14  5292.6  372.67  5307.1  373.75  5364.4  376.39
#Mann= 3 , 0 , 0
    4766     .17       0  4965.5     .09       0  5086.5     .17       0
Bank Sta=4965.5,5086.5
XS Rating Curve= 0 ,0
Exp/Cntr=0.3,0.1

Type RM Length L Ch R = 1 ,9395    ,479,479,479
BEGIN DESCRIPTION:
WFSJR 007 18.0
END DESCRIPTION:
XS GIS Cut Line= 3
      3724117.84     10213911.08      3724340.01      10213814.9
      3724317.85      10213511.1
#Sta/Elev= 30
  4757.9  362.92  4801.5  361.21  4819.3  361.55    4856  359.06  4900.7  358.64
  4910.5  357.38  4942.2  356.81  4947.7  355.83    4965  355.78  4971.1  354.97
  4976.6  352.72  4992.6  349.96  4992.9  349.46  4996.4  349.46  4998.5  351.45
  5004.4  351.45  5023.9  356.38  5043.9  357.09    5064  356.56    5084  357.53
  5098.7  357.35  5114.1  357.89  5144.2  357.49  5174.3  358.59  5184.3  358.44
  5232.7   360.2  5254.5  361.78  5274.6  362.45  5284.6  363.45  5304.6  363.99
#Mann= 3 , 0 , 0
  4757.9     .17       0    4965     .09       0  5023.9     .17       0
Bank Sta=4965,5023.9
XS Rating Curve= 0 ,0
Exp/Cntr=0.3,0.1

Type RM Length L Ch R = 1 ,8916    ,414,414,414
BEGIN DESCRIPTION:
WFSJR 007 17.0
END DESCRIPTION:
XS GIS Cut Line= 3
      3724417.84     10214161.08      3724682.09     10214082.47
      3724917.86     10213761.07
#Sta/Elev= 30
  4724.3  355.93    4766   353.9  4779.3  354.11  4878.9  348.37  4912.1  347.72
  4917.3  348.22  4923.3  347.56  4955.7  346.45  4974.7  345.32  4983.6  343.06
  4988.9  342.64  4995.2  339.96    5000  339.96  5002.9  337.66  5006.4  337.66
  5019.3  341.69  5040.1  346.57  5084.1  348.29  5090.3  349.07  5219.9  352.58
  5226.1  353.67  5234.6   353.3  5240.8  354.07  5262.2  353.39  5320.2  355.06
  5341.1  354.67  5355.8  356.07    5362  355.33  5385.1  356.38  5398.6  356.14
#Mann= 4 ,-1 , 0
  4724.3     .11       0  4923.3     .17       0  4955.7     .09       0
  5040.1     .17       0
Bank Sta=4955.7,5040.1
XS Rating Curve= 0 ,0
Exp/Cntr=0.3,0.1

Type RM Length L Ch R = 1 ,8502    ,555,555,555
BEGIN DESCRIPTION:
WFSJR 007 16.0
END DESCRIPTION:
XS GIS Cut Line= 3
      3724703.22     10214559.49      3725003.01     10214337.14
      3725241.36     10214044.99
#Sta/Elev= 30
  4682.4  349.07  4735.1  347.78  4799.8  344.73  4820.7  344.94  4834.5  344.24
  4906.2  339.97  4956.3  338.21  4962.5  337.32    4967  335.52  4985.5  328.36
  4999.4  327.81  5004.4  327.28  5004.6  326.78  5008.1  326.78  5012.6  329.08
    5021  331.02  5035.6  335.67  5041.8  336.86  5055.5  336.13  5070.6  337.04
  5091.4  336.79  5120.1  338.44  5140.9  338.61  5163.2  340.06    5184  340.38
  5241.5  343.29  5283.1   344.5    5291  345.52  5305.4  345.59  5432.7  351.43
#Mann= 4 ,-1 , 0
  4682.4     .11       0  4834.5     .17       0    4967     .09       0
  5035.6     .17       0
Bank Sta=4967,5035.6
XS Rating Curve= 0 ,0
Exp/Cntr=0.3,0.1

Type RM Length L Ch R = 1 ,7947    ,481,481,481
BEGIN DESCRIPTION:
WFSJR 007 15.0
END DESCRIPTION:
XS GIS Cut Line= 3
      3725238.59     10215001.73      3725417.85     10214561.07
      3725481.41     10214276.72
#Sta/Elev= 30
  4584.3  342.97  4719.6  336.83  4768.5  333.76  4812.5  332.45  4836.6   330.8
  4908.8  328.39  4943.6   328.1  4952.1  327.28  4962.3  325.14  4967.7  324.79
  4973.7  322.44  4991.8  318.13  4997.2   318.6  5004.1   317.9  5004.3   317.4
  5007.8   317.4  5021.2  319.98  5027.6  322.83  5038.4  325.59  5045.3  327.76
  5070.3   329.8  5132.8   332.9  5176.3  335.95  5203.5   336.7  5219.7  338.72
  5263.1   339.5  5275.2   340.9    5306  341.76  5326.4  343.67  5351.4  344.77
#Mann= 4 ,-1 , 0
  4584.3     .11       0  4719.6     .17       0  4962.3     .09       0
  5038.4     .17       0
Bank Sta=4962.3,5038.4
XS Rating Curve= 0 ,0
Exp/Cntr=0.3,0.1

Type RM Length L Ch R = 1 ,7466    ,499,499,499
BEGIN DESCRIPTION:
WFSJR 007 14.0
END DESCRIPTION:
XS GIS Cut Line= 3
      3725640.72     10215174.08      3725760.17     10214807.45
      3725763.12     10214327.75
#Sta/Elev= 30
  4614.4  339.21  4622.1  339.48  4638.6  337.93    4654  337.82  4685.9  336.15
  4691.2  335.29  4749.7  332.86  4796.4  330.63  4819.1  328.83    4870  327.27
    4891  325.25  4914.6  324.31  4933.1  322.64  4941.2   319.3  4962.9  315.17
  4973.1  316.47  4985.7  316.73  5006.4  315.95  5016.4  317.17  5026.4  320.16
  5036.4  321.24  5056.4  321.22  5126.4  323.88  5176.4  327.42  5246.4  330.85
  5346.4   337.5  5396.4  340.29  5426.4  341.09    5434  342.05  5479.7  343.65
#Mann= 5 ,-1 , 0
  4614.4     .17       0  4749.7     .11       0  4819.1     .17       0
  4941.2     .09       0  5026.4     .17       0
Bank Sta=4941.2,5026.4
XS Rating Curve= 0 ,0
Exp/Cntr=0.3,0.1

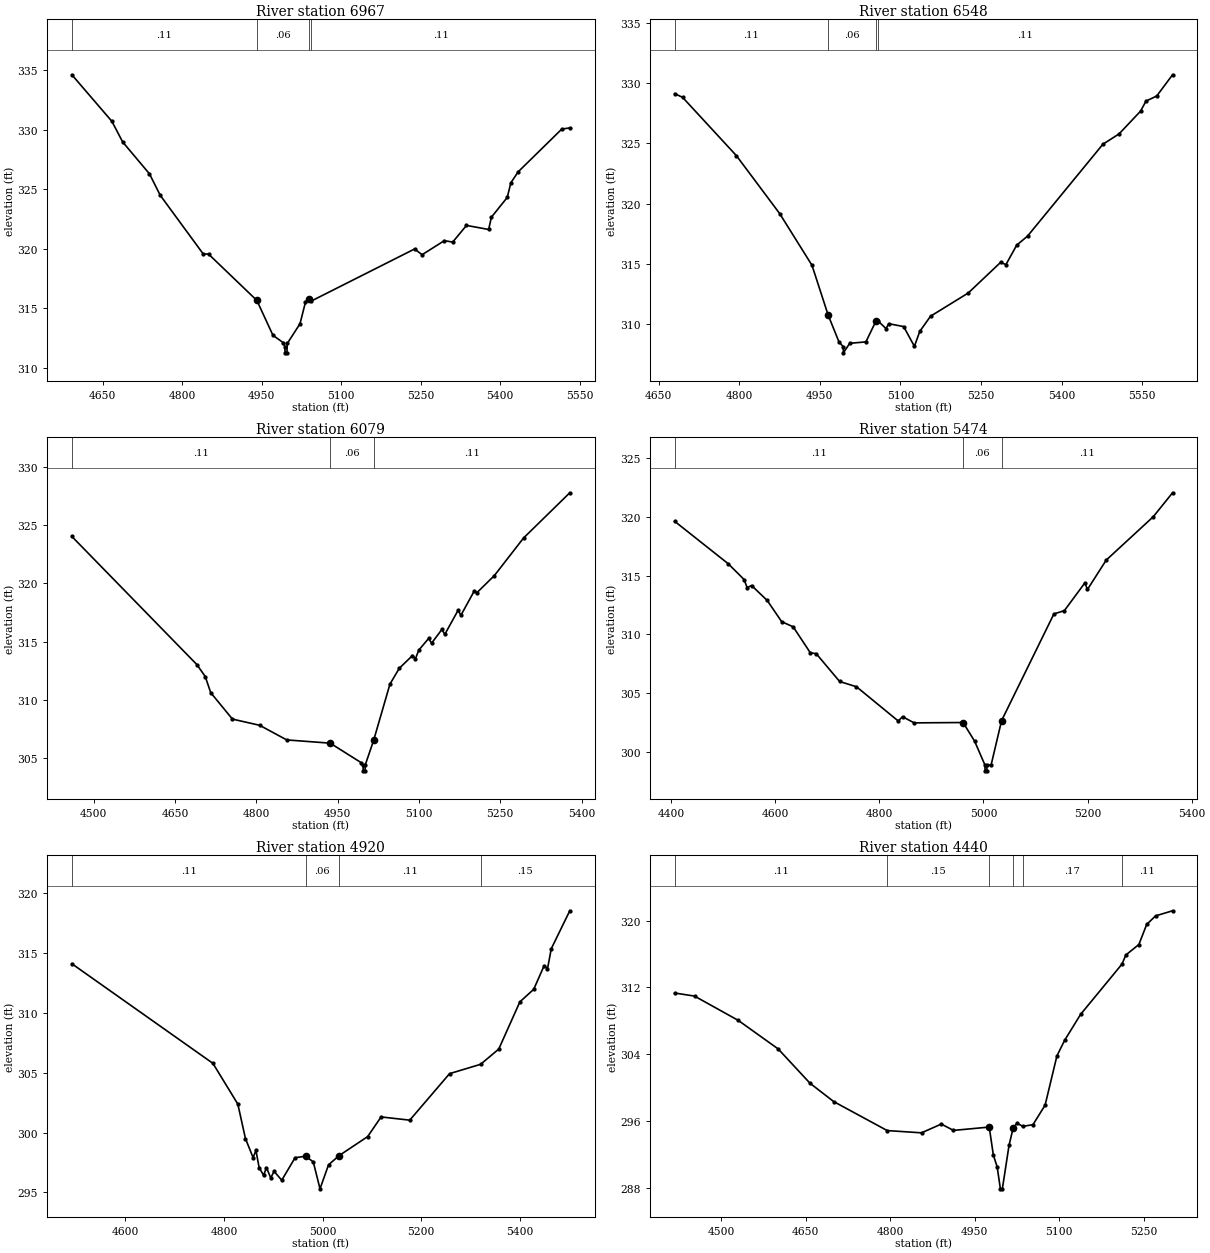
Type RM Length L Ch R = 1 ,6967    ,419,419,419
BEGIN DESCRIPTION:
WFSJR 007 13.0
END DESCRIPTION:
XS GIS Cut Line= 3
      3726148.53     10215275.63      3726213.65     10214872.76
      3726338.64     10214356.37
#Sta/Elev= 30
  4591.9  334.61  4667.4   330.7  4687.7  328.97  4738.3  326.29  4758.6  324.49
  4839.6  319.57  4849.8  319.55  4940.9  315.66  4971.3  312.73  4990.8  312.11
  4993.8  311.76  4994.1  311.26  4997.6  311.26  4998.3  312.05  5022.3   313.7
  5032.6  315.52  5038.4   315.8  5043.6  315.61  5238.4  319.98  5252.7   319.5
  5294.6  320.68  5310.4  320.56  5336.4  321.96  5378.2  321.62  5383.4  322.65
  5413.3  324.31  5420.1  325.54  5433.9  326.46  5516.2  330.05  5531.3  330.15
#Mann= 4 ,-1 , 0
  4591.9     .11       0  4940.9     .06       0  5038.4     .11       0
  5043.6     .11       0
Bank Sta=4940.9,5038.4
XS Rating Curve= 0 ,0
Exp/Cntr=0.3,0.1

Type RM Length L Ch R = 1 ,6548    ,469,469,469
BEGIN DESCRIPTION:
WFSJR 007 12.0
END DESCRIPTION:
XS GIS Cut Line= 3
      3726553.13     10215345.69      3726583.88     10214968.65
      3726551.51      10214421.7
#Sta/Elev= 30
    4680  329.13  4694.7  328.83  4794.8  323.99  4875.3  319.18  4935.5  314.88
  4965.6  310.74  4985.6  308.53  4993.7  308.11  4993.9  307.61  5005.7   308.4
  5035.8  308.52  5054.6  310.26  5058.3  310.26  5073.3  309.62  5078.3  310.03
    5106  309.79    5126  308.15    5136  309.39    5156  310.65  5226.2  312.58
  5286.3  315.12  5296.3  314.94  5316.3  316.55  5336.4   317.3  5476.6  324.93
  5506.7  325.79  5546.7  327.68  5556.7  328.51  5576.8  328.94  5606.2   330.7
#Mann= 4 ,-1 , 0
    4680     .11       0  4965.6     .06       0  5054.6     .11       0
  5058.3     .11       0
Bank Sta=4965.6,5054.6
XS Rating Curve= 0 ,0
Exp/Cntr=0.3,0.1

Type RM Length L Ch R = 1 ,6079    ,605,605,605
BEGIN DESCRIPTION:
WFSJR 007 11.0
END DESCRIPTION:
XS GIS Cut Line= 3
      3726897.83     10215316.61      3726936.67     10214722.67
      3726818.51     10214421.63
#Sta/Elev= 30
  4459.8  324.04  4690.4  313.02  4705.9  311.99  4715.9  310.61    4756  308.33
  4806.1   307.8  4856.2  306.54  4936.4  306.26    4994  304.57    4997  304.38
  4997.3  303.88  5000.8  303.88    5001  304.38  5016.5   306.5  5046.6  311.34
  5063.8   312.7  5088.2   313.8  5093.6  313.51  5099.7  314.26    5118  315.27
  5123.4  314.86  5142.4  316.04  5147.8  315.62  5172.2  317.68  5177.6  317.27
    5202  319.34  5207.4  319.22  5239.3  320.68  5293.1  323.91  5378.4   327.8
#Mann= 3 , 0 , 0
  4459.8     .11       0  4936.4     .06       0  5016.5     .11       0
Bank Sta=4936.4,5016.5
XS Rating Curve= 0 ,0
Exp/Cntr=0.3,0.1

Type RM Length L Ch R = 1 ,5474    ,554,554,554
BEGIN DESCRIPTION:
WFSJR 007 10.0
END DESCRIPTION:
XS GIS Cut Line= 3
       3727150.3     10215342.45      3727423.07     10214815.69
      3727459.19     10214454.29
#Sta/Elev= 30
  4406.8  319.64  4509.7  316.02  4540.3  314.67    4546  313.99  4554.7  314.16
  4584.6  312.89  4612.4  311.08  4634.5  310.64  4667.4  308.43  4678.8  308.35
  4723.7  305.98  4756.1  305.53  4836.3  302.61  4844.6  302.98  4866.7  302.45
  4960.9  302.48    4983  300.89  5002.8  298.86  5003.1  298.36  5006.6  298.36
  5006.8  298.86  5014.7  298.86  5034.8  302.64  5135.3  311.74  5155.4  312.02
  5194.7  314.38  5199.8  313.83  5235.8  316.33  5326.2  320.03  5363.2  322.07
#Mann= 3 , 0 , 0
  4406.8     .11       0  4960.9     .06       0  5034.8     .11       0
Bank Sta=4960.9,5034.8
XS Rating Curve= 0 ,0
Exp/Cntr=0.3,0.1

Type RM Length L Ch R = 1 ,4920    ,480,480,480
BEGIN DESCRIPTION:
WFSJR 007 9.0
END DESCRIPTION:
XS GIS Cut Line= 3
      3727588.86     10215475.16      3727983.71     10214827.86
      3728172.96     10214662.87
#Sta/Elev= 30
  4491.8  314.08  4777.7  305.77  4828.2  302.37  4843.6   299.5  4859.1  297.91
  4864.9   298.5  4871.4  297.07  4880.4  296.43  4886.3  297.07  4894.9  296.21
  4901.7  296.76  4917.2  296.02  4944.3   297.9  4965.7  298.02  4981.1  297.55
  4994.8   295.3    5012   297.3  5033.4  298.07  5091.4  299.66  5118.6   301.3
  5176.7  301.03  5257.4  304.91  5320.3  305.69  5357.1  306.96  5399.9   310.9
    5428  311.95  5449.2  313.93  5455.9  313.65  5463.5  315.33  5501.1   318.5
#Mann= 4 ,-1 , 0
  4491.8     .11       0  4965.7     .06       0  5033.4     .11       0
  5320.3     .15       0
Bank Sta=4965.7,5033.4
XS Rating Curve= 0 ,0
Exp/Cntr=0.3,0.1

Type RM Length L Ch R = 1 ,4440    ,337,337,337
BEGIN DESCRIPTION:
WFSJR 007 8.0
END DESCRIPTION:
XS GIS Cut Line= 3
      3727800.87     10215523.71      3728312.22     10215052.81
      3728407.68     10214889.39
#Sta/Elev= 30
    4417  311.32  4452.3  310.95    4530  308.04  4600.9  304.62  4657.6   300.5
  4699.6  298.31  4794.6  294.84  4855.5  294.57  4890.7  295.62  4912.3  294.86
  4975.8  295.26  4983.1  291.91  4989.9  290.49  4995.6  287.86  4999.1  287.86
    5011  293.08  5018.3  295.16  5025.1  295.73  5035.4  295.34  5053.5  295.55
    5075  297.88    5096  303.78  5109.7  305.65  5138.2  308.77  5211.7  314.79
  5218.4  315.87  5241.6  317.13  5255.5  319.54  5271.3  320.56  5301.4  321.17
#Mann= 6 ,-1 , 0
    4417     .11       0  4794.6     .15       0  4975.8     .09       0
  5018.3     .15       0  5035.4     .17       0  5211.7     .11       0
Bank Sta=4975.8,5018.3
XS Rating Curve= 0 ,0
Exp/Cntr=0.3,0.1

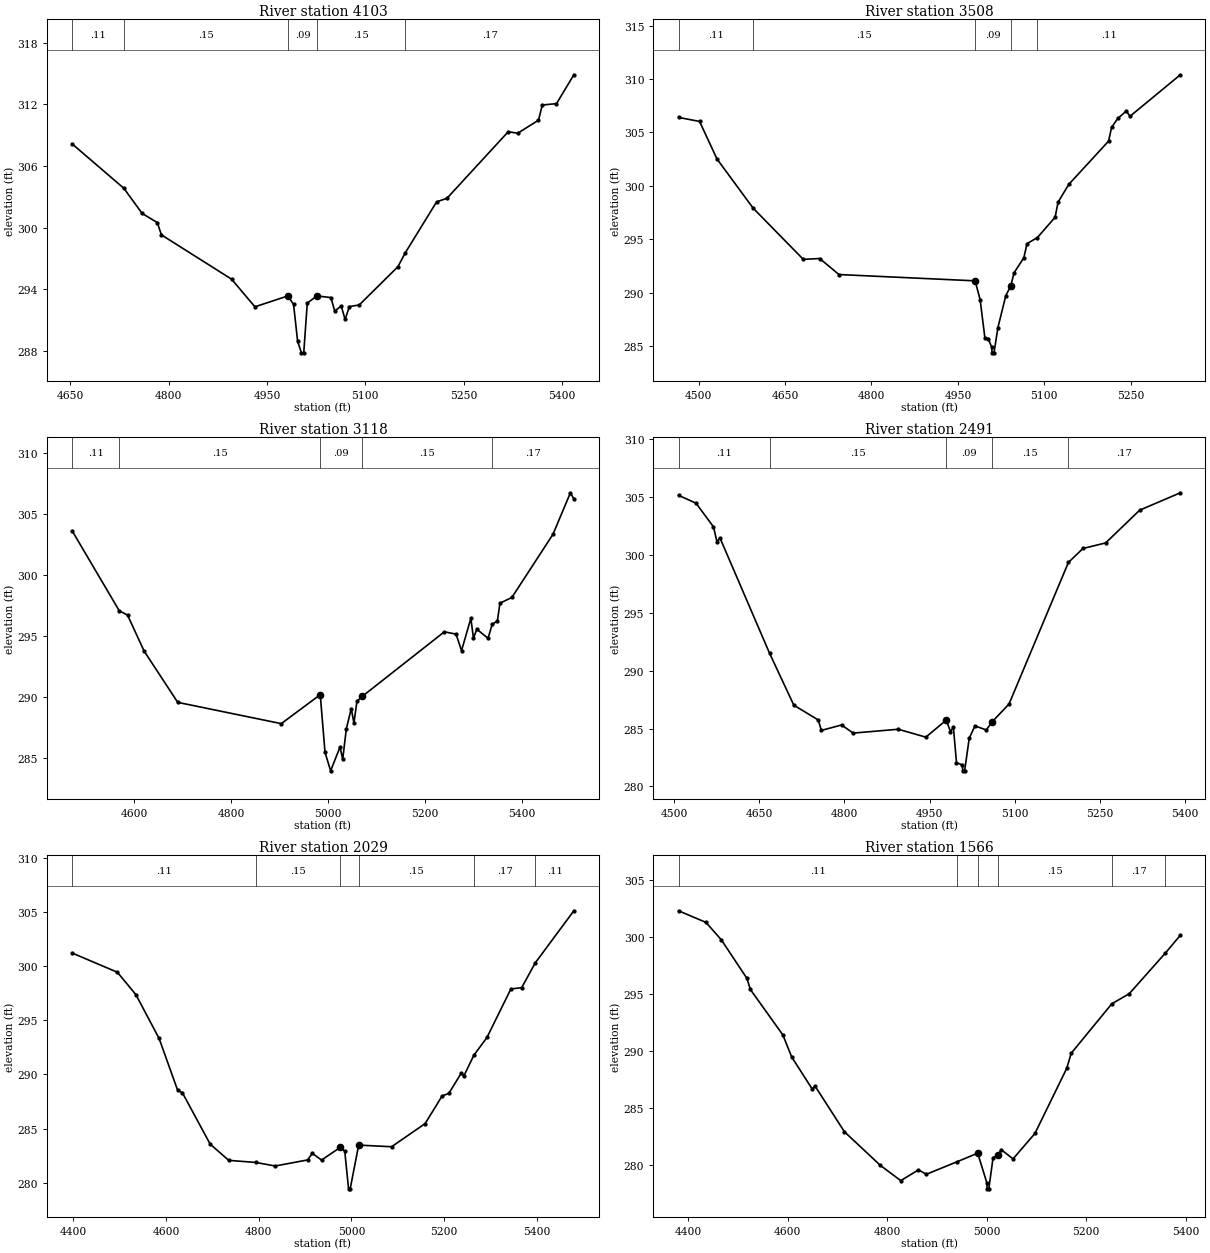
Type RM Length L Ch R = 1 ,4103    ,595,595,595
BEGIN DESCRIPTION:
WFSJR 007 7.0
END DESCRIPTION:
XS GIS Cut Line= 3
      3728103.48      10215646.7      3728328.41     10215332.77
      3728516.77     10215004.35
#Sta/Elev= 30
    4653  308.16    4732  303.83  4759.7  301.39  4782.9   300.5  4789.2   299.3
  4896.1  294.99  4931.7   292.3    4982  293.36  4990.6  292.53  4996.8  288.93
  5002.6  287.82  5006.1  287.82  5011.5  292.66  5026.2  293.36  5047.5   293.2
  5053.3  291.89  5063.3  292.38  5069.1  291.07  5075.7  292.32  5090.7  292.48
  5149.6   296.2  5161.1  297.58  5208.6  302.51  5224.4  302.86  5317.8  309.34
  5332.3  309.19  5363.9  310.46  5369.7  311.94  5391.3  312.07  5417.8  314.88
#Mann= 5 ,-1 , 0
    4653     .11       0    4732     .15       0    4982     .09       0
  5026.2     .15       0  5161.1     .17       0
Bank Sta=4982,5026.2
XS Rating Curve= 0 ,0
Exp/Cntr=0.3,0.1

Type RM Length L Ch R = 1 ,3508    ,390,390,390
BEGIN DESCRIPTION:
WFSJR 007 6.0
END DESCRIPTION:
XS GIS Cut Line= 3
      3728217.89     10215761.05      3728768.59     10215491.37
      3728854.34     10215248.66
#Sta/Elev= 30
  4465.3  306.41  4501.8  306.03  4532.1  302.51  4594.8  297.91  4681.8  293.12
  4710.2   293.2  4743.6   291.7  4979.9  291.11  4988.6  289.34  4996.9  285.73
  5002.4  285.71  5008.9  284.87  5009.1  284.37  5012.6  284.37  5019.4  286.73
  5033.1  289.72  5041.9  290.66  5047.4  291.86  5064.4  293.27  5069.9  294.59
  5087.9  295.16  5118.6  297.06  5123.9  298.49  5142.4  300.14  5211.4  304.19
  5216.7  305.48  5227.3  306.31  5242.3  307.01  5248.5  306.51  5335.9   310.4
#Mann= 5 ,-1 , 0
  4465.3     .11       0  4594.8     .15       0  4979.9     .09       0
  5041.9     .15       0  5087.9     .11       0
Bank Sta=4979.9,5041.9
XS Rating Curve= 0 ,0
Exp/Cntr=0.3,0.1

Type RM Length L Ch R = 1 ,3118    ,627,627,627
BEGIN DESCRIPTION:
WFSJR 007 5.0
END DESCRIPTION:
XS GIS Cut Line= 3
      3728703.85     10216226.08      3728956.31     10215667.76
      3729107.82     10215274.48
#Sta/Elev= 30
  4472.5  303.61  4569.9  297.05  4586.8  296.71  4620.9  293.77  4690.3  289.57
  4903.7  287.83    4984   290.2  4993.8  285.49  5005.4  283.97  5024.8  285.92
  5030.3  284.91  5037.7  287.39  5047.9  289.06  5053.4  287.88  5059.7  289.67
  5070.6  290.06  5239.8  295.34  5263.9  295.15  5275.2   293.8  5294.4  296.44
  5299.8  294.82  5306.7  295.55  5329.8  294.81  5338.5  295.96    5349  296.22
  5354.4  297.68    5379  298.15  5463.6  303.31  5499.6  306.71  5506.7   306.2
#Mann= 5 ,-1 , 0
  4472.5     .11       0  4569.9     .15       0    4984     .09       0
  5070.6     .15       0  5338.5     .17       0
Bank Sta=4984,5070.6
XS Rating Curve= 0 ,0
Exp/Cntr=0.3,0.1

Type RM Length L Ch R = 1 ,2491    ,462,462,462
BEGIN DESCRIPTION:
WFSJR 007 4.0
END DESCRIPTION:
XS GIS Cut Line= 3
      3729267.84     10216311.11      3729375.25     10215830.98
      3729383.54     10215439.57
#Sta/Elev= 30
    4508  305.14  4538.8  304.46  4569.5  302.42  4575.7  301.12  4580.8  301.48
  4668.2  291.51    4711  287.02    4754  285.74  4759.5  284.84    4795  285.31
  4815.5  284.61  4894.9  284.94  4943.4  284.26  4979.4  285.73  4986.8  284.73
  4991.9  285.13  4997.4  282.06  5007.9  281.85  5008.2  281.35  5011.7  281.35
  5019.9  284.18  5029.9  285.23  5049.9  284.88  5059.9  285.57  5089.9  287.12
  5194.4  299.34    5220  300.55    5260  301.03    5320  303.86  5391.5  305.36
#Mann= 5 ,-1 , 0
    4508     .11       0  4668.2     .15       0  4979.4     .09       0
  5059.9     .15       0  5194.4     .17       0
Bank Sta=4979.4,5059.9
XS Rating Curve= 0 ,0
Exp/Cntr=0.3,0.1

Type RM Length L Ch R = 1 ,2029    ,463,463,463
BEGIN DESCRIPTION:
WFSJR 007 3.0
END DESCRIPTION:
XS GIS Cut Line= 3
      3729844.76      10216418.7      3729807.54     10215766.48
      3729705.58     10215348.93
#Sta/Elev= 30
  4397.1  301.22  4494.9  299.44  4534.9  297.37    4585  293.32  4625.1  288.52
  4635.1  288.32  4695.2  283.56  4735.3  282.06  4793.5  281.87  4835.4  281.54
  4905.6   282.1  4915.6  282.71  4935.6  282.09  4975.7  283.25  4985.7  282.91
  4993.9  279.43  4997.4  279.43  5015.7  283.47  5086.8  283.32  5159.2  285.46
  5195.8  288.01  5210.4  288.25  5237.4  290.14  5242.6  289.84  5264.2  291.76
  5292.7  293.42  5344.2  297.89  5367.6  298.02  5397.1  300.32  5480.2  305.12
#Mann= 6 ,-1 , 0
  4397.1     .11       0  4793.5     .15       0  4975.7     .09       0
  5015.7     .15       0  5264.2     .17       0  5397.1     .11       0
Bank Sta=4975.7,5015.7
XS Rating Curve= 0 ,0
Exp/Cntr=0.3,0.1

Type RM Length L Ch R = 1 ,1566    ,384,384,384
BEGIN DESCRIPTION:
WFSJR 007 2.0
END DESCRIPTION:
XS GIS Cut Line= 3
      3730068.09     10216384.63      3730226.68     10215738.97
      3730108.53      10215416.9
#Sta/Elev= 30
  4381.1  302.34  4436.2  301.32  4467.1  299.79  4518.6   296.4  4525.3  295.44
  4590.7  291.44  4608.4  289.51    4650  286.67  4655.1  286.97  4714.3  282.95
  4786.4     280  4827.5  278.66  4862.9   279.6    4879  279.22  4940.8  280.32
    4982  281.07  5000.6  278.44  5000.8  277.94  5004.3  277.94  5012.9  280.68
  5023.2  280.91  5029.1  281.38    5053  280.57    5097   282.8  5160.9  288.52
  5169.7  289.83  5251.4  294.18  5286.4  295.06  5359.2  298.64    5389  300.19
#Mann= 6 ,-1 , 0
  4381.1     .11       0  4940.8     .15       0    4982     .09       0
  5023.2     .15       0  5251.4     .17       0  5359.2     .11       0
Bank Sta=4982,5023.2
XS Rating Curve= 0 ,0
Exp/Cntr=0.3,0.1

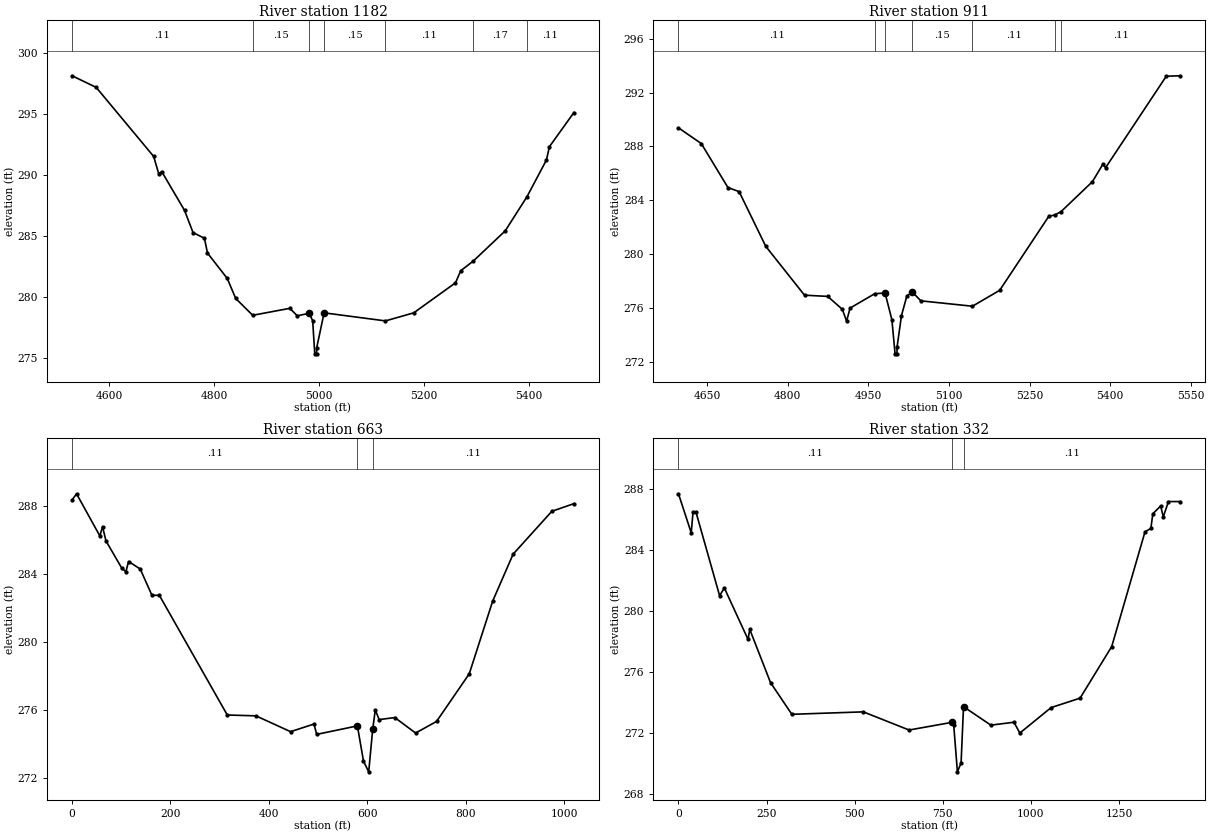
Type RM Length L Ch R = 1 ,1182    ,271,271,271
BEGIN DESCRIPTION:
Mapping XS 1e87b6d0
END DESCRIPTION:
XS GIS Cut Line= 3
      3730241.26     10216347.41      3730490.46     10215894.32
      3730629.63     10215476.81
#Sta/Elev= 30
  4528.9  298.16  4574.9  297.21  4684.5  291.55  4694.2  290.13  4699.9  290.31
  4743.5  287.12  4759.6  285.31  4781.4  284.84  4787.2  283.63  4824.9  281.55
    4841  279.91  4873.4  278.53  4944.2   279.1  4958.4  278.49  4981.2  278.69
  4987.8  278.09  4991.8  275.37  4995.3  275.37  4995.5  275.87  5009.6  278.73
  5126.6  278.07  5180.6  278.73  5260.2  281.19  5270.2  282.18  5294.3  282.98
  5355.1  285.45  5396.6  288.25  5433.6  291.25  5439.4  292.35  5486.1  295.15
#Mann= 7 ,-1 , 0
  4528.9     .11       0  4873.4     .15       0  4981.2     .09       0
  5009.6     .15       0  5126.6     .11       0  5294.3     .17       0
  5396.6     .11       0
Bank Sta=4981.2,5009.6
XS Rating Curve= 0 ,0
Exp/Cntr=0.3,0.1

Type RM Length L Ch R = 1 ,911     ,248,248,248
BEGIN DESCRIPTION:
WFSJR 007 1.0
END DESCRIPTION:
XS GIS Cut Line= 3
      3730495.34       10216328.       3730715.4     10216052.92
      3730817.37     10215479.99
#Sta/Elev= 30
  4596.5  289.38    4639  288.21  4688.6  284.94  4709.4  284.64    4759  280.57
  4831.1  276.94  4874.3  276.85  4901.5  275.89  4909.5  275.01  4915.9  275.98
  4961.8  277.05  4981.1   277.1  4993.8  275.11  4999.7  272.58  5003.2  272.58
  5003.4  273.08  5011.6  275.42  5021.7  276.89  5031.9  277.17  5047.7  276.52
  5143.7  276.12  5194.4   277.3  5285.8   282.8  5297.6  282.91  5308.9  283.16
  5367.1  285.38  5386.6  286.68  5391.6  286.42  5504.6  293.22  5530.7  293.25
#Mann= 7 ,-1 , 0
  4596.5     .11       0  4961.8     .15       0  4981.1     .09       0
  5031.9     .15       0  5143.7     .11       0  5297.6     .17       0
  5308.9     .11       0
Bank Sta=4981.1,5031.9
XS Rating Curve= 0 ,0
Exp/Cntr=0.3,0.1

Type RM Length L Ch R = 1 ,663     ,332,332,332
XS GIS Cut Line= 4
       3730494.4     10216359.56       3730893.7     10216191.16
      3731008.29      10215861.3      3730952.73     10215630.39
#Sta/Elev= 30
       0  288.33     9.1  288.69    56.5  286.21    61.9  286.76    68.9  285.92
   101.4   284.3   109.4  284.11   114.8  284.71   138.5  284.27   162.2  282.73
   177.4  282.72   315.4  275.69   373.7  275.64     444  274.71   491.7  275.16
     497  274.55   579.8  275.05   592.2  272.98   602.8  272.35   610.9  274.86
   616.2  275.99     624  275.42   655.8  275.54   698.1  274.63   740.6  275.31
   807.1  278.11   854.8  282.39   896.2  285.14   974.9  287.66  1019.8  288.11
#Mann= 3 , 0 , 0
       0     .11       0   579.8     .09       0   610.9     .11       0
Bank Sta=579.8,610.9
XS Rating Curve= 0 ,0
Exp/Cntr=0.3,0.1

Type RM Length L Ch R = 1 ,332     ,0,0,0
XS GIS Cut Line= 4
      3730478.77     10216390.81       3731143.7     10216307.48
      3731218.36     10216050.53      3730996.57     10215617.95
#Sta/Elev= 30
       0  287.67    36.2  285.11    41.3  286.47    49.5  286.48   116.7  280.99
   130.1   281.5   197.3  278.13   202.3  278.78   261.1   275.3   321.6  273.22
   524.4  273.38   654.2  272.19   775.2  272.69   780.9  272.51   791.4  269.45
   801.8  270.03   808.7  273.72   886.2  272.51   951.9   272.7   968.4  271.99
  1057.2  273.66  1139.4  274.28  1229.2  277.66  1323.6  285.18  1340.2   285.4
  1345.8  286.36    1368  286.87  1375.4  286.16  1390.2  287.16  1423.8  287.16
#Mann= 3 , 0 , 0
       0     .11       0   775.2     .09       0   808.7     .11       0
Bank Sta=775.2,808.7
XS Rating Curve= 0 ,0
Exp/Cntr=0.3,0.1
Stream Node=WFSJR 007       ,Reach-1         , 0 , 0 ,Upstream end
Stream Node=WFSJR 007       ,Reach-1         , 0 , 1 ,Downstream end

Chan Stop Cuts=-1
Use User Specified Reach Order=0
Composite Channel Slope=5