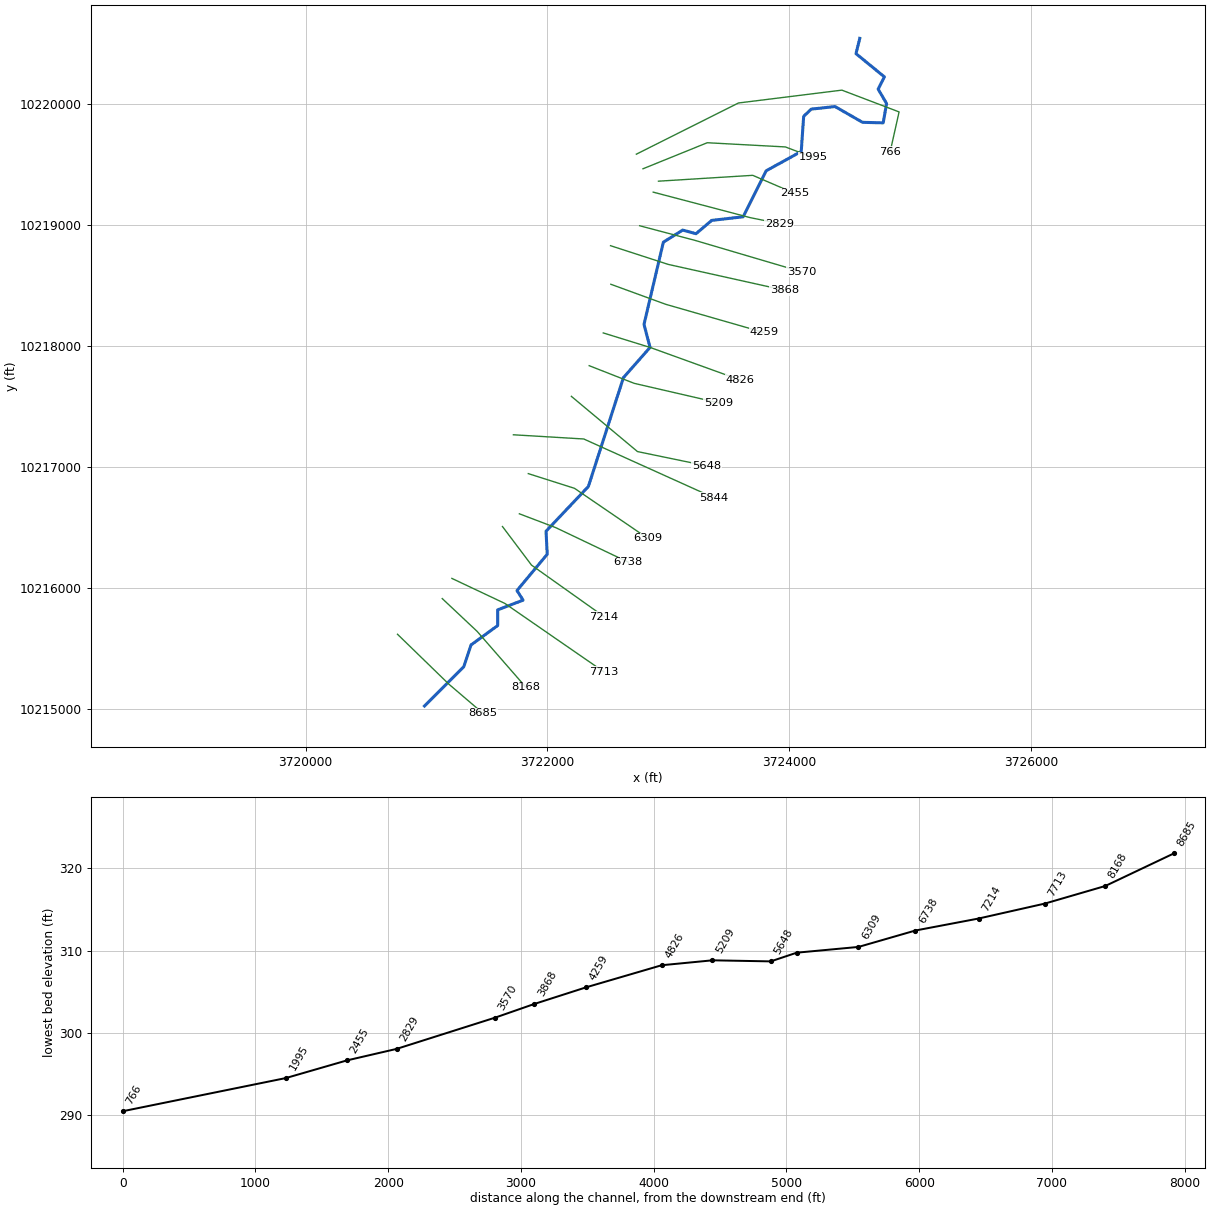
--- WFSJR 009.prj (project) ---

Proj Title=WFSJR 009 Base Level Engineering
Current Plan=p01
Default Exp/Contr=0.3,0.1
English Units
Geom File=g01
Flow File=f01
Flow File=f02
Plan File=p01
Y Axis Title=Elevation
X Axis Title(PF)=Main Channel Distance
X Axis Title(XS)=Station
BEGIN DESCRIPTION:
WFSJR 009
END DESCRIPTION:
DSS Export Rating Curves= 0
DSS Export Rating Curve Sorted= 0
DSS Export Volume Flow Curves= 0
DXF OffsetX= 0
DXF OffsetY= 0
DXF ScaleX= 1
DXF ScaleY= 10

--- WFSJR 009.p01 (plan) ---

Plan Title=Multiple Run
Program Version=4.10
Short Identifier=Multiple
Geom File=g01
Flow File=f01
Subcritical Flow
K Sum by GR= 0
Std Step Tol= 0.01
Critical Tol= 0.01
Num of Std Step Trials= 20
Max Error Tol= 0.3
Flow Tol Ratio= 0.001
Split Flow NTrial= 30
Split Flow Tol= 0.02
Split Flow Ratio= 0.02
Log Output Level= 0
Friction Slope Method= 1
Unsteady Friction Slope Method= 2
Unsteady Bridges Friction Slope Method= 1
Parabolic Critical Depth
Global Vel Dist= 1 , 1 , 1
Global Log Level= 0
CheckData=True
Encroach Param=-1 ,0,0, 0
BEGIN DESCRIPTION:
Multiple Run
END DESCRIPTION:
Computation Interval=1HOUR
Output Interval=1HOUR
Run HTab= 0
Run UNet= 0
Run PostProcess= 0
Run WQNet= 0
UNET Theta= 1
UNET Theta Warmup= 1
UNET ZTol= 0.02
UNET ZSATol= 0.05
UNET MxIter= 20
UNET MaxInSteps= 0
UNET DtIC= 0
UNET DtMin= 0
UNET MaxCRTS= 20
UNET WFStab= 2
UNET SFStab= 1
UNET WFX= 1
UNET SFX= 1
UNET DSS MLevel= 4
UNET DZMax Abort= 100
UNET Convert EG Bridges= 0
UNET Use Existing IB Tables=-1
UNET Froude Reduction=False
UNET Froude Limit= 1
UNET Froude Power= 10
UNET Time Slicing=0,0, 5
UNET Junction Losses=0
Instantaneous Interval=1HOUR
Write IC File= 0
Write IC File at Sim End=0
Echo Input=False
Echo Parameters=False
Echo Output=False
Write Detailed= 0
WQ AD Non Conservative
WQ ULTIMATE=-1
WQ Max Comp Step=1HOUR
WQ Output Interval=15MIN
WQ Output Selected Increments= 0
WQ Output face flow=0
WQ Output face velocity=0
WQ Output face area=0
WQ Output face dispersion=0
WQ Output cell volume=0
WQ Output cell surface area=0
WQ Output cell continuity=0
WQ Output cumulative cell continuity=0
WQ Output face conc=0
WQ Output face dconc_dx=0
WQ Output face courant=0
WQ Output face peclet=0
WQ Output face adv mass=0
WQ Output face disp mass=0
WQ Output cell mass=0
WQ Output cell source sink temp=0
WQ Output cell source sink nsm=0
WQ Output MaxMinRange=-1
WQ Daily Max Min Mean=-1
WQ Daily Range=0
WQ Daily Time=0
WQ Create Restart=0
WQ Fixed Restart=0
WQ System Summary=0
WQ Use Fixed Temperature=0
Sorting and Armoring Iterations= 10
XS Update Threshold= 0.02
Hydraulics Update Threshold= 0.02
Energy Slope Method= 1
Volume Change Method= 0
XS Weighting Method= 0
Number of US Weighted Cross Sections= 1
Number of DS Weighted Cross Sections= 1
Upstream XS Weight=0.25
Main XS Weight=0.5
Downstream XS Weight=0.25
Number of DS XS's Weighted with US Boundary= 1
Upstream Boundary Weight= 1
Weight of XSs Associated with US Boundary= 0
Number of US XS's Weighted with DS Boundary= 1
Downstream Boundary Weight= 0.5
Weight of XSs Associated with DS Boundary= 0.5
Sediment Output Level= 4
Mass or Volume Output= 0
Output Increment Type= 1
Profile and TS Output Increment= 10
XS Output Flag= 0
XS Output Increment= 10
Disregard all LS=0
Disregard all Conn=0
Disregard all Breaches=0
Disregard all Pumps=0

--- WFSJR 009.f01 (steady flow) ---

Flow Title=Multiple
Program Version=4.10
Number of Profiles= 7
Profile Names=10-year,25-year,50-year,1pct_min,100-year,1pct_plu,500-year
River Rch & RM=WFSJR 009,Reach-1         ,8685
     840    1160    1587     714    2155    6508    4116
Boundary for River Rch & Prof#=WFSJR 009,Reach-1         , 1
Up Type= 0
Dn Type= 3
Dn Slope=0.003
Boundary for River Rch & Prof#=WFSJR 009,Reach-1         , 2
Up Type= 0
Dn Type= 3
Dn Slope=0.003
Boundary for River Rch & Prof#=WFSJR 009,Reach-1         , 3
Up Type= 0
Dn Type= 3
Dn Slope=0.003
Boundary for River Rch & Prof#=WFSJR 009,Reach-1         , 4
Up Type= 0
Dn Type= 3
Dn Slope=0.003
Boundary for River Rch & Prof#=WFSJR 009,Reach-1         , 5
Up Type= 0
Dn Type= 3
Dn Slope=0.003
Boundary for River Rch & Prof#=WFSJR 009,Reach-1         , 6
Up Type= 0
Dn Type= 3
Dn Slope=0.003
Boundary for River Rch & Prof#=WFSJR 009,Reach-1         , 7
Up Type= 0
Dn Type= 3
Dn Slope=0.003
DSS Import GetInterval= 0
DSS Import GetPeak= 0
DSS Import FillOption= 0

--- WFSJR 009.f02 (steady flow) ---

Flow Title=Orig_BLE_Flow
Program Version=4.10
Number of Profiles= 7
Profile Names=10-year,25-year,50-year,1pct_min,100-year,1pct_plu,500-year
River Rch & RM=WFSJR 009,Reach-1         ,8685
     840    1137    1380     549    1658    5008    2393
Boundary for River Rch & Prof#=WFSJR 009,Reach-1         , 1
Up Type= 0
Dn Type= 3
Dn Slope=0.003
Boundary for River Rch & Prof#=WFSJR 009,Reach-1         , 2
Up Type= 0
Dn Type= 3
Dn Slope=0.003
Boundary for River Rch & Prof#=WFSJR 009,Reach-1         , 3
Up Type= 0
Dn Type= 3
Dn Slope=0.003
Boundary for River Rch & Prof#=WFSJR 009,Reach-1         , 4
Up Type= 0
Dn Type= 3
Dn Slope=0.003
Boundary for River Rch & Prof#=WFSJR 009,Reach-1         , 5
Up Type= 0
Dn Type= 3
Dn Slope=0.003
Boundary for River Rch & Prof#=WFSJR 009,Reach-1         , 6
Up Type= 0
Dn Type= 3
Dn Slope=0.003
Boundary for River Rch & Prof#=WFSJR 009,Reach-1         , 7
Up Type= 0
Dn Type= 3
Dn Slope=0.003
DSS Import GetInterval= 0
DSS Import GetPeak= 0
DSS Import FillOption= 0

--- WFSJR 009.g01 (geometry) ---

Geom Title=Existing Conditions
Program Version=4.10

River Reach=WFSJR 009       ,Reach-1
Reach XY= 30
      3720983.23     10215021.84      3721308.23     10215346.84
      3721368.23     10215526.84      3721588.23     10215686.84
      3721588.23     10215816.84      3721798.23     10215896.84
      3721748.23     10215976.84      3721998.23     10216276.84
      3721988.23     10216466.84      3722338.23     10216836.84
      3722628.23     10217736.84      3722848.23     10217986.84
      3722798.23     10218176.84      3722958.23     10218856.84
      3723118.23     10218956.84      3723228.23     10218926.84
      3723358.23     10219036.84      3723618.23     10219066.84
      3723808.23     10219446.84      3724098.23     10219606.84
      3724118.23     10219896.84      3724180.79     10219956.85
      3724377.62     10219978.22      3724604.82     10219847.74
      3724775.78     10219843.25       3724803.9     10220002.96
      3724734.16     10220122.18       3724785.9     10220223.41
      3724550.83     10220415.74       3724582.5     10220542.15

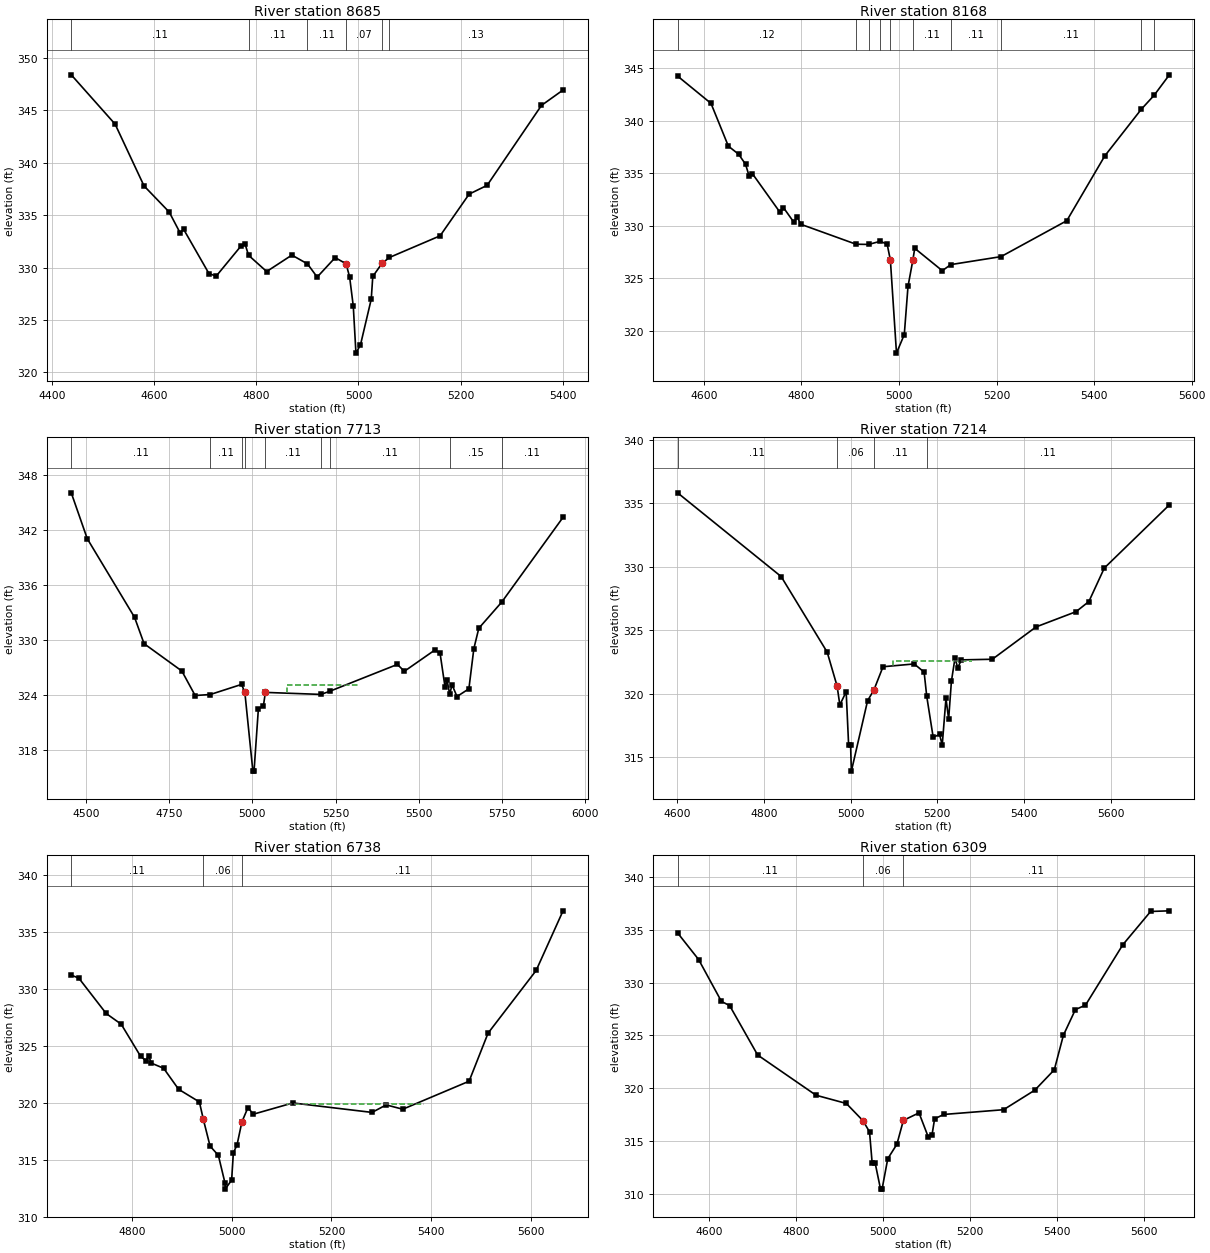
Type RM Length L Ch R = 1 ,8685    ,517,517,517
BEGIN DESCRIPTION:
WFSJR 009 14.0
END DESCRIPTION:
XS GIS Cut Line= 3
      3720760.24     10215615.12       3721185.6     10215201.91
      3721467.89     10214961.04
#Sta/Elev= 30
  4436.9   348.4  4522.9  343.69  4579.5   337.8  4628.9   335.3  4650.2  333.32
  4657.2  333.65  4706.8  329.43    4721  329.18  4770.4   332.1  4777.6  332.25
  4784.5  331.17    4820  329.62  4869.4  331.19    4900  330.35    4919  329.09
  4954.3  330.95  4975.6  330.36  4982.6  329.11  4989.8  326.31    4995  321.83
  5003.9  322.62    5025  326.98    5028  329.15    5046  330.39  5060.5  330.96
    5160  333.03  5216.9  337.01  5252.2  337.85  5358.7  345.48    5401  346.95
#Mann= 6 ,-1 , 0
  4436.9     .11       0  4784.5     .11       0    4900     .11       0
  4975.6     .07       0    5046     .11       0  5060.5     .13       0
#XS Ineff= 2 ,-1
    4630  4777.6  332.25    4780  4954.3  330.95
Permanent Ineff=
       F       F
Bank Sta=4975.6,5046
XS Rating Curve= 0 ,0
Exp/Cntr=0.3,0.1

Type RM Length L Ch R = 1 ,8168    ,455,455,455
BEGIN DESCRIPTION:
WFSJR 009 13.0
END DESCRIPTION:
XS GIS Cut Line= 3
      3721130.04     10215910.25      3721418.24     10215639.41
      3721821.04     10215177.58
#Sta/Elev= 30
    4546  344.24  4614.5  341.64  4650.1  337.57  4671.1   336.8  4685.3  335.85
  4692.6  334.73  4699.5  334.94  4756.1  331.26    4763  331.72  4784.4  330.32
  4791.3  330.81  4798.6  330.13  4911.9  328.23  4937.8  328.21  4961.5  328.51
  4975.7  328.23  4982.3  326.71  4994.8  317.86  5010.8  319.63  5018.4  324.21
  5028.3 326.697  5032.2  327.84  5088.7  325.71  5106.2  326.29  5209.2  327.05
    5344  330.47  5421.9  336.64  5496.9  341.09    5523  342.41  5554.3  344.36
#Mann= 10 ,-1 , 0
    4546     .12       0  4911.9     .12       0  4937.8     .11       0
  4961.5     .11       0  4982.3     .06       0  5028.3     .11       0
  5106.2     .11       0  5209.2     .11       0  5496.9     .17       0
    5523     .11       0
#XS Ineff= 1 ,-1
  5032.2    5245  327.84
Permanent Ineff=
       F
Bank Sta=4982.3,5028.3
XS Rating Curve= 0 ,0
Exp/Cntr=0.3,0.1

Type RM Length L Ch R = 1 ,7713    ,499,499,499
BEGIN DESCRIPTION:
WFSJR 009 12.0
END DESCRIPTION:
XS GIS Cut Line= 3
      3721209.92      10216076.9      3721647.41     10215870.31
      3722465.61      10215305.2
#Sta/Elev= 30
  4455.6  346.05  4503.7  341.05  4645.9  332.48  4674.5  329.61    4788  326.63
    4828  323.96  4873.5  324.07  4967.4  325.17  4977.3 324.328  5001.5  315.72
    5005  315.72  5018.1  322.54    5033  322.79  5039.1   324.3    5206  324.08
  5233.1  324.43  5435.9  327.35  5456.8   326.6  5549.4  328.94  5564.3  328.54
  5579.2  324.86  5585.2  325.62  5593.2  324.09  5600.1  325.14    5615  323.85
  5650.8  324.69  5665.7  329.07  5680.6  331.29  5749.7  334.15  5933.8  343.38
#Mann= 9 ,-1 , 0
  4455.6     .11       0  4873.5     .11       0  4967.4     .11       0
  4977.3     .06       0  5039.1     .11       0    5206     .11       0
  5233.1     .11       0  5593.2     .15       0  5749.7     .11       0
#XS Ineff= 3 ,-1
  5104.6    5320  325.09  5549.4    5670  328.94    4800  4967.4  325.17
Permanent Ineff=
       F       F       F
Bank Sta=4977.3,5039.1
XS Rating Curve= 0 ,0
Exp/Cntr=0.3,0.1

Type RM Length L Ch R = 1 ,7214    ,476,476,476
BEGIN DESCRIPTION:
WFSJR 009 11.0
END DESCRIPTION:
XS GIS Cut Line= 3
      3721628.29     10216505.76      3721868.23     10216186.84
      3722467.84     10215761.08
#Sta/Elev= 30
  4600.9  335.84  4839.8  329.24    4946  323.28  4968.9   320.6  4975.2  319.12
  4989.8  320.16  4995.5  315.93    5000  315.93  5001.8   313.9  5039.2  319.45
  5053.9  320.31  5074.8  322.13  5146.7  322.35  5169.6  321.71  5175.7  319.79
  5190.5  316.57  5205.3  316.79  5211.4  315.95    5220  319.63  5226.2     318
  5232.6  320.99  5240.9  322.82  5247.1  322.05  5255.7  322.67    5327  322.72
  5427.9  325.27  5520.1  326.47  5549.7  327.27  5585.3  329.91  5735.4  334.89
#Mann= 4 ,-1 , 0
  4600.9     .11       0  4968.9     .06       0  5053.9     .11       0
  5175.7     .11       0
#XS Ineff= 1 ,-1
  5097.7    5280  322.55
Permanent Ineff=
       F
Bank Sta=4968.9,5053.9
XS Rating Curve= 0 ,0
Exp/Cntr=0.3,0.1

Type RM Length L Ch R = 1 ,6738    ,429,429,429
BEGIN DESCRIPTION:
WFSJR 009 10.0
END DESCRIPTION:
XS GIS Cut Line= 3
      3721767.82     10216611.08      3722068.23     10216496.84
      3722667.82     10216211.09
#Sta/Elev= 30
  4678.6  331.24  4693.7  330.98  4748.6  327.87  4778.7  326.93  4817.7   324.1
  4828.2  323.73  4833.6  324.16  4839.1  323.51  4863.7  323.06  4893.8  321.21
  4935.4   320.1  4943.3  318.57  4956.8  316.22  4973.4  315.41  4986.9  312.94
  4987.1  312.44    5000  313.23  5003.5  315.65  5010.7   316.3  5020.6  318.35
  5032.8  319.61  5043.3  319.02  5122.5  320.01  5281.4  319.18  5309.8  319.84
    5343  319.46  5475.9  321.92  5513.9  326.14  5610.3  331.65  5664.2  336.89
#Mann= 3 ,-1 , 0
  4678.6     .11       0  4943.3     .06       0  5020.6     .11       0
#XS Ineff= 1 ,-1
  5110.4    5385  319.96
Permanent Ineff=
       F
Bank Sta=4943.3,5020.6
XS Rating Curve= 0 ,0
Exp/Cntr=0.3,0.1

Type RM Length L Ch R = 1 ,6309    ,465,465,465
BEGIN DESCRIPTION:
WFSJR 009 9.0
END DESCRIPTION:
XS GIS Cut Line= 3
      3721841.81     10216943.24       3722223.8      10216821.7
      3722826.23     10216410.24
#Sta/Elev= 30
  4527.7   334.7    4576  332.18  4628.5  328.21  4647.3  327.82  4711.7  323.14
  4845.9  319.33  4915.6  318.55    4954  316.91  4968.9  315.86  4974.9  312.92
  4981.9  312.89  4994.2  310.44  4997.7  310.44  5010.8  313.32  5031.8  314.69
  5046.7  316.95  5082.6  317.66  5103.6  315.41  5112.5  315.57  5118.5   317.1
  5139.5  317.51    5277  317.96  5348.8  319.81  5393.6  321.74  5414.5  325.01
  5442.1  327.44  5465.3  327.86  5551.1  333.58    5615  336.73  5658.1  336.79
#Mann= 3 ,-1 , 0
  4527.7     .11       0    4954     .06       0  5046.7     .11       0
Bank Sta=4954,5046.7
XS Rating Curve= 0 ,0
Exp/Cntr=0.3,0.1

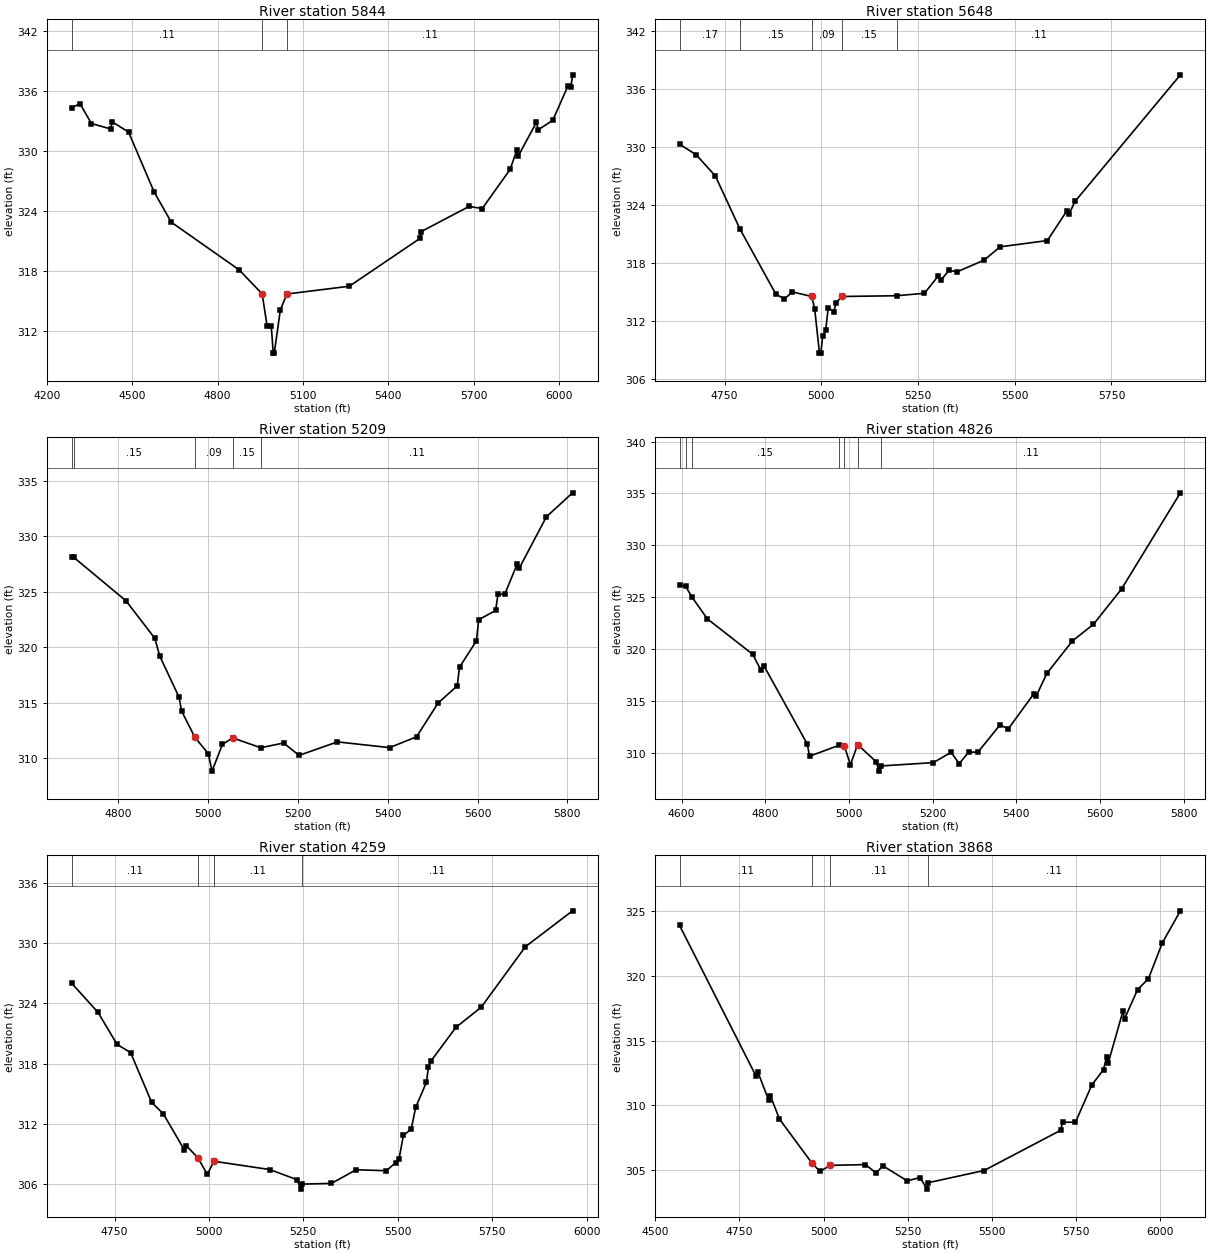
Type RM Length L Ch R = 1 ,5844    ,196,196,196
BEGIN DESCRIPTION:
Mapping XS 487cc341
END DESCRIPTION:
XS GIS Cut Line= 3
      3721718.64      10217264.4      3722300.19     10217229.69
      3723372.13     10216745.75
#Sta/Elev= 30
  4287.9  334.33  4317.2  334.71  4357.2  332.73    4425  332.19    4430   332.9
  4487.5  331.88  4577.6  325.86  4637.7  322.85  4876.3  318.07  4956.7  315.67
  4974.3  312.42  4988.6  312.45  4995.7  309.74  4999.2  309.74  5020.6  314.07
  5043.5  315.66  5262.8  316.44  5510.5  321.22  5515.9  321.92  5683.3  324.43
  5729.5  324.22  5827.5  328.14  5850.6  330.04  5856.1  329.49    5920  332.86
  5925.5   332.1  5977.2  333.05  6030.9  336.52  6041.1  336.43  6046.6  337.61
#Mann= 3 ,-1 , 0
  4287.9     .11       0  4956.7     .06       0  5043.5     .11       0
Bank Sta=4956.7,5043.5
XS Rating Curve= 0 ,0
Exp/Cntr=0.3,0.1

Type RM Length L Ch R = 1 ,5648    ,439,439,439
BEGIN DESCRIPTION:
WFSJR 009 8.0
END DESCRIPTION:
XS GIS Cut Line= 3
      3722197.73     10217582.14      3722744.63     10217125.52
      3723314.32     10217007.77
#Sta/Elev= 30
  4633.8  330.26    4677  329.17  4726.5  326.97  4789.9   321.5  4882.7  314.77
  4904.8  314.28  4925.6     315  4975.1  314.54  4982.9  313.29  4995.4  308.68
  4998.9  308.68  5003.7  310.41  5011.5  311.08    5018  313.36  5032.3  312.96
  5038.8   313.9  5053.1  314.53  5194.5  314.61  5266.6  314.86  5301.7  316.62
  5309.5  316.23  5330.4  317.24  5350.5  317.07    5421  318.29  5461.9  319.66
  5584.4  320.31  5635.2  323.41  5640.3  323.05  5655.9  324.36    5928  337.43
#Mann= 5 ,-1 , 0
  4633.8     .17       0  4789.9     .15       0  4975.1     .09       0
  5053.1     .15       0  5194.5     .11       0
Bank Sta=4975.1,5053.1
XS Rating Curve= 0 ,0
Exp/Cntr=0.3,0.1

Type RM Length L Ch R = 1 ,5209    ,383,383,383
BEGIN DESCRIPTION:
WFSJR 009 7.0
END DESCRIPTION:
XS GIS Cut Line= 3
      3722345.34     10217835.58      3722716.85     10217689.75
      3723414.71     10217528.71
#Sta/Elev= 30
  4696.1  328.13  4700.6  328.11    4817  324.18  4881.2   320.8  4892.2  319.19
  4935.1  315.49  4940.8  314.23  4970.6  311.85  5000.4  310.38  5008.5  308.81
  5031.8  311.22  5054.6  311.81  5117.2  310.92  5168.1  311.35  5202.3  310.23
  5287.8  311.45  5404.1  310.93    5464  311.91  5511.9  314.95  5554.6  316.51
  5559.7  318.19  5597.4  320.57  5602.5  322.48  5640.1  323.31  5645.3  324.76
  5660.7   324.8    5688  327.49  5693.2  327.16  5753.1  331.76  5811.4  333.93
#Mann= 5 ,-1 , 0
  4696.1     .17       0  4700.6     .15       0  4970.6     .09       0
  5054.6     .15       0  5117.2     .11       0
Bank Sta=4970.6,5054.6
XS Rating Curve= 0 ,0
Exp/Cntr=0.3,0.1

Type RM Length L Ch R = 1 ,4826    ,567,567,567
BEGIN DESCRIPTION:
WFSJR 009 6.0
END DESCRIPTION:
XS GIS Cut Line= 3
       3722461.6     10218106.43      3722848.23     10217986.84
      3723593.19     10217717.68
#Sta/Elev= 30
  4595.3  326.14    4610  326.04  4624.6  325.02  4661.8   322.9  4770.1  319.48
  4790.3  317.92  4797.5  318.33  4900.6  310.82  4905.9  309.65  4975.7  310.69
  4989.1  310.63  5003.6  308.83  5020.9  310.77  5064.9  309.12  5072.2  308.21
  5076.1  308.71  5201.6  309.03  5244.2  310.02  5263.6  308.93  5286.7  310.07
  5307.9  310.02  5361.1  312.67  5380.9  312.29  5442.3  315.69  5447.6  315.45
  5472.9  317.63  5534.3  320.78  5584.4  322.37  5651.6  325.79  5792.1  335.06
#Mann= 7 ,-1 , 0
  4595.3     .17       0    4610     .11       0  4624.6     .15       0
  4975.7     .11       0  4989.1     .06       0  5020.9     .11       0
  5076.1     .11       0
Bank Sta=4989.1,5020.9
XS Rating Curve= 0 ,0
Exp/Cntr=0.3,0.1

Type RM Length L Ch R = 1 ,4259    ,391,391,391
BEGIN DESCRIPTION:
WFSJR 009 5.0
END DESCRIPTION:
XS GIS Cut Line= 3
      3722524.18     10218508.75      3722977.27      10218343.4
      3723788.43     10218110.34
#Sta/Elev= 30
  4636.6  326.01  4706.2  323.12  4756.7  319.93  4792.6  319.11  4848.3  314.16
  4878.9  313.04  4934.7  309.45    4940  309.86  4970.6  308.65  4995.8     307
  5013.1   308.3  5161.1  307.48    5234  306.46  5242.5  305.53  5246.5  306.03
  5324.5   306.1    5390  307.46  5469.7  307.36  5494.1  308.15  5503.4  308.52
  5514.9  310.87  5535.7  311.51  5547.6  313.67  5576.1  316.18  5581.3  317.71
  5587.7  318.26  5653.9  321.62  5721.3  323.64  5838.1  329.65  5962.9  333.22
#Mann= 4 ,-1 , 0
  4636.6     .11       0  4970.6     .06       0  5013.1     .11       0
  5246.5     .11       0
Bank Sta=4970.6,5013.1
XS Rating Curve= 0 ,0
Exp/Cntr=0.3,0.1

Type RM Length L Ch R = 1 ,3868    ,298,298,298
BEGIN DESCRIPTION:
WFSJR 009 4.0
END DESCRIPTION:
XS GIS Cut Line= 3
      3722521.57     10218827.76      3722999.41     10218672.83
      3723960.34     10218459.29
#Sta/Elev= 30
  4572.5  323.92  4799.8  312.24    4805  312.57    4837  310.39  4842.3  310.72
    4869  308.93  4964.9  305.54  4989.1  304.87  5020.6  305.34  5124.5   305.4
  5156.2  304.74  5175.7  305.31  5248.4  304.14  5286.8   304.4    5307   303.5
    5311     304  5476.3  304.94  5704.2  308.06  5709.4  308.68  5747.8  308.68
  5796.4  311.57  5831.3  312.76    5840  313.74  5845.1  313.27  5888.6  317.27
  5893.7   316.7  5932.2  318.95  5964.5   319.8  6005.4  322.56  6059.2  325.05
#Mann= 4 ,-1 , 0
  4572.5     .11       0  4964.9     .06       0  5020.6     .11       0
    5311     .11       0
Bank Sta=4964.9,5020.6
XS Rating Curve= 0 ,0
Exp/Cntr=0.3,0.1

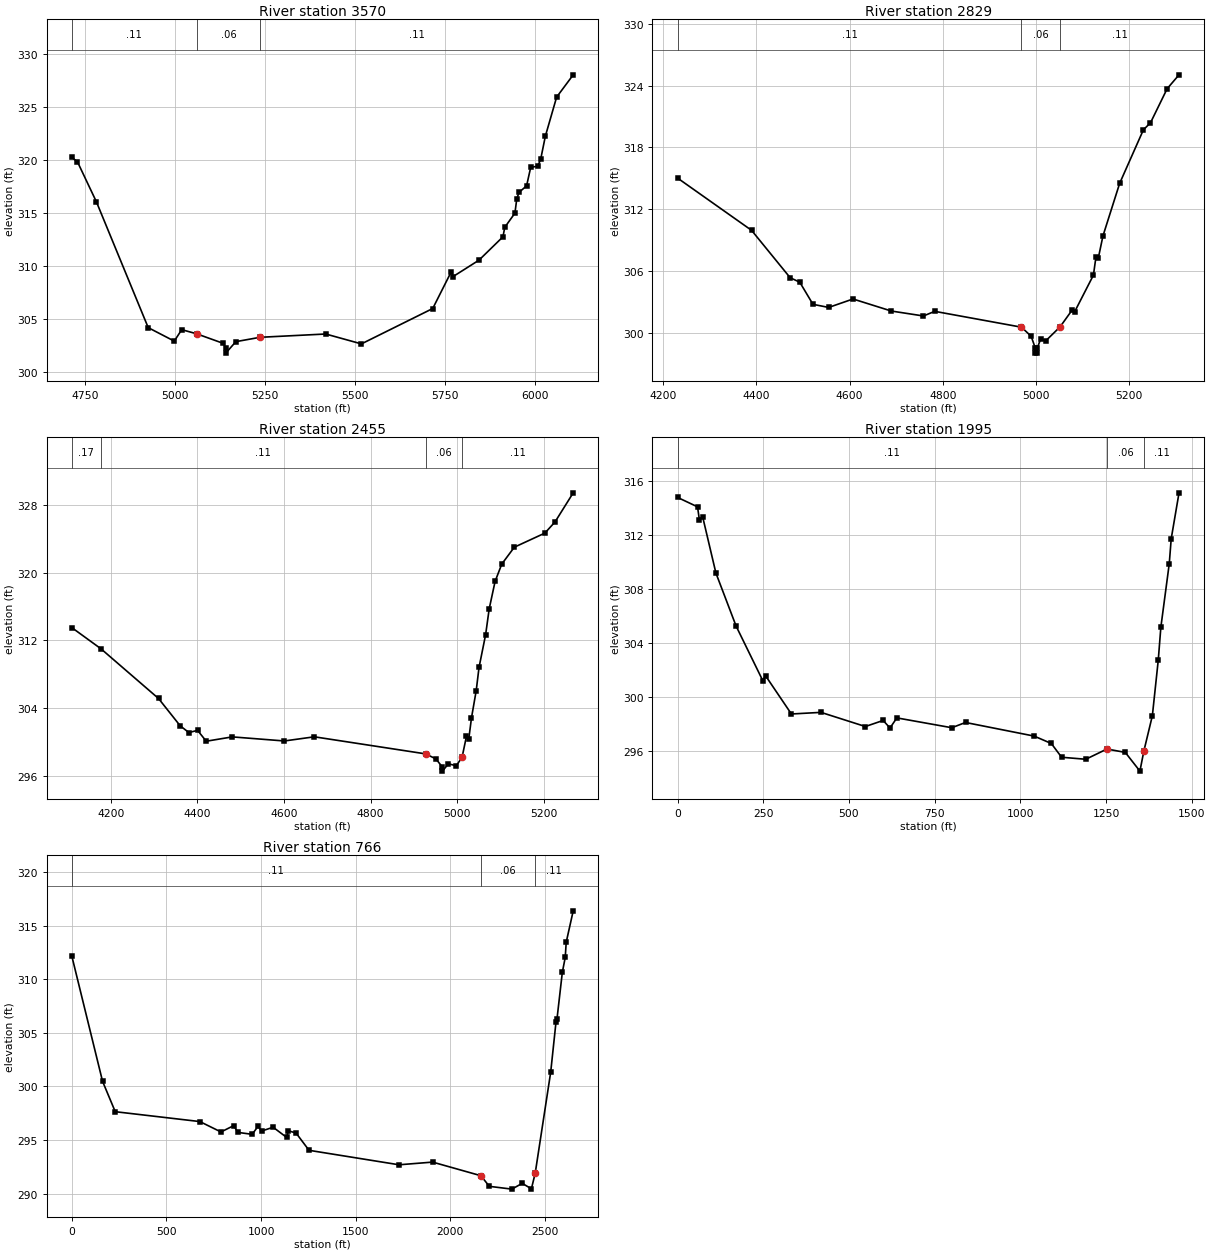
Type RM Length L Ch R = 1 ,3570    ,741,741,741
BEGIN DESCRIPTION:
WFSJR 009 3.0
END DESCRIPTION:
XS GIS Cut Line= 3
      3722762.45     10218992.58      3723220.07      10218871.7
      3724102.05     10218611.42
#Sta/Elev= 30
  4712.4  320.25  4728.3  319.83  4781.1  316.05  4924.8  304.22  4997.2  302.95
  5017.9  304.03  5059.3  303.64  5133.2  302.74  5139.9  302.32  5140.2  301.82
  5168.2   302.9  5235.5  303.31  5417.8  303.62    5517  302.69  5715.1  306.02
  5766.5  309.48  5771.7  309.03  5843.5  310.57  5910.1  312.77  5915.3  313.67
  5943.4     315  5948.6  316.36    5955  316.96  5975.8  317.57  5987.2  319.31
  6007.1  319.42  6015.2  320.12  6027.9  322.24  6059.2  325.92  6105.3  328.02
#Mann= 3 ,-1 , 0
  4712.4     .11       0  5059.3     .06       0  5235.5     .11       0
Bank Sta=5059.3,5235.5
XS Rating Curve= 0 ,0
Exp/Cntr=0.3,0.1

Type RM Length L Ch R = 1 ,2829    ,374,374,374
BEGIN DESCRIPTION:
WFSJR 009 2.0
END DESCRIPTION:
XS GIS Cut Line= 3
      3722874.31      10219270.6      3723679.86      10219058.8
       3723917.9     10219011.06
#Sta/Elev= 30
  4230.8  315.03  4389.6  309.95  4472.3  305.35    4493  304.91  4521.3  302.76
    4555  302.46  4607.2  303.28  4689.4  302.11  4758.2  301.63  4782.5  302.08
  4968.6  300.54  4989.3  299.66  4998.1  298.52  4998.4  298.02  5002.2  298.02
  5002.5  298.52  5009.9  299.42  5020.3   299.2  5051.3  300.57  5077.3  302.21
  5082.4  302.02  5122.9   305.6  5128.2  307.33  5133.3  307.24  5143.3   309.4
  5179.1  314.51  5230.1  319.72  5245.3   320.4    5281  323.71  5306.5  325.06
#Mann= 3 ,-1 , 0
  4230.8     .11       0  4968.6     .06       0  5051.3     .11       0
#XS Ineff= 1 ,-1
    4510  4607.2  303.28
Permanent Ineff=
       F
Bank Sta=4968.6,5051.3
XS Rating Curve= 0 ,0
Exp/Cntr=0.3,0.1

Type RM Length L Ch R = 1 ,2455    ,460,460,460
BEGIN DESCRIPTION:
WFSJR 009 1.0
END DESCRIPTION:
XS GIS Cut Line= 3
      3722917.88     10219361.07      3723697.22     10219409.49
      3724043.61     10219260.55
#Sta/Elev= 30
  4109.8  313.52  4177.3  311.02  4310.2  305.17  4360.3  301.95  4380.3  301.16
  4400.3  301.42  4420.4  300.14  4480.5  300.65  4600.7  300.17    4670  300.66
    4927  298.65  4950.6  298.06  4965.3  297.12  4965.6  296.62  4979.6  297.48
  4997.7  297.25  5011.1  298.26  5021.2  300.72  5026.6  300.42  5032.8  302.89
  5043.7  306.09  5050.2  308.82  5065.5   312.7  5073.7  315.72  5087.3  318.95
  5102.7  320.99  5131.7  322.98  5202.3  324.64  5225.9  325.97  5267.7  329.38
#Mann= 4 ,-1 , 0
  4109.8     .17       0  4177.3     .11       0    4927     .06       0
  5011.1     .11       0
Bank Sta=4927,5011.1
XS Rating Curve= 0 ,0
Exp/Cntr=0.3,0.1

Type RM Length L Ch R = 1 ,1995    ,1229,1229,1229
XS GIS Cut Line= 4
      3722789.98     10219463.72      3723321.23       10219679.
      3723967.07     10219644.28      3724196.23     10219557.47
#Sta/Elev= 30
       0  314.78    58.3  314.08    63.7  313.12    73.2  313.35   111.9  309.17
   170.9  305.23   248.6  301.19   256.7  301.55   332.2  298.71   418.5  298.83
     548  297.78   599.9  298.23   619.9  297.67   639.9  298.42   800.2  297.69
   840.2  298.08  1040.5  297.07  1090.6  296.52  1120.6   295.5  1191.1  295.35
  1252.9  296.11  1306.4  295.86  1349.1  294.47  1360.6  295.96  1385.4  298.58
  1402.6   302.7  1410.2  305.15  1434.7  309.86  1440.4  311.71  1463.2  315.12
#Mann= 3 ,-1 , 0
       0     .11       0  1252.9     .06       0  1360.6     .11       0
Bank Sta=1252.9,1360.6
XS Rating Curve= 0 ,0
Exp/Cntr=0.3,0.1

Type RM Length L Ch R = 1 ,766     ,0,0,0
XS GIS Cut Line= 5
      3722734.86     10219584.38      3723579.05     10220007.56
      3724434.08      10220113.9      3724907.17     10219933.77
      3724833.39     10219603.91
#Sta/Elev= 30
       0  312.19   162.8  300.48   229.8  297.65   676.7  296.73   788.4  295.76
   855.4  296.35   877.8  295.72   953.2  295.54   983.4  296.27  1003.6  295.85
    1064   296.2  1134.6  295.26  1144.6  295.87    1185  295.66  1253.4  294.05
  1729.1   292.7  1906.3  292.95  2161.5  291.68  2205.9  290.69  2325.2  290.43
  2379.6  290.97  2428.2  290.46  2448.1  291.89  2530.1  301.33  2558.4  306.05
  2563.5  306.31  2591.6  310.65  2606.9  312.03  2612.1  313.45  2649.1  316.38
#Mann= 3 , 0 , 0
       0     .11       0  2161.5     .06       0  2448.1     .11       0
Bank Sta=2161.5,2448.1
XS Rating Curve= 0 ,0
Exp/Cntr=0.3,0.1

Chan Stop Cuts=-1
Use User Specified Reach Order=0
Composite Channel Slope=5