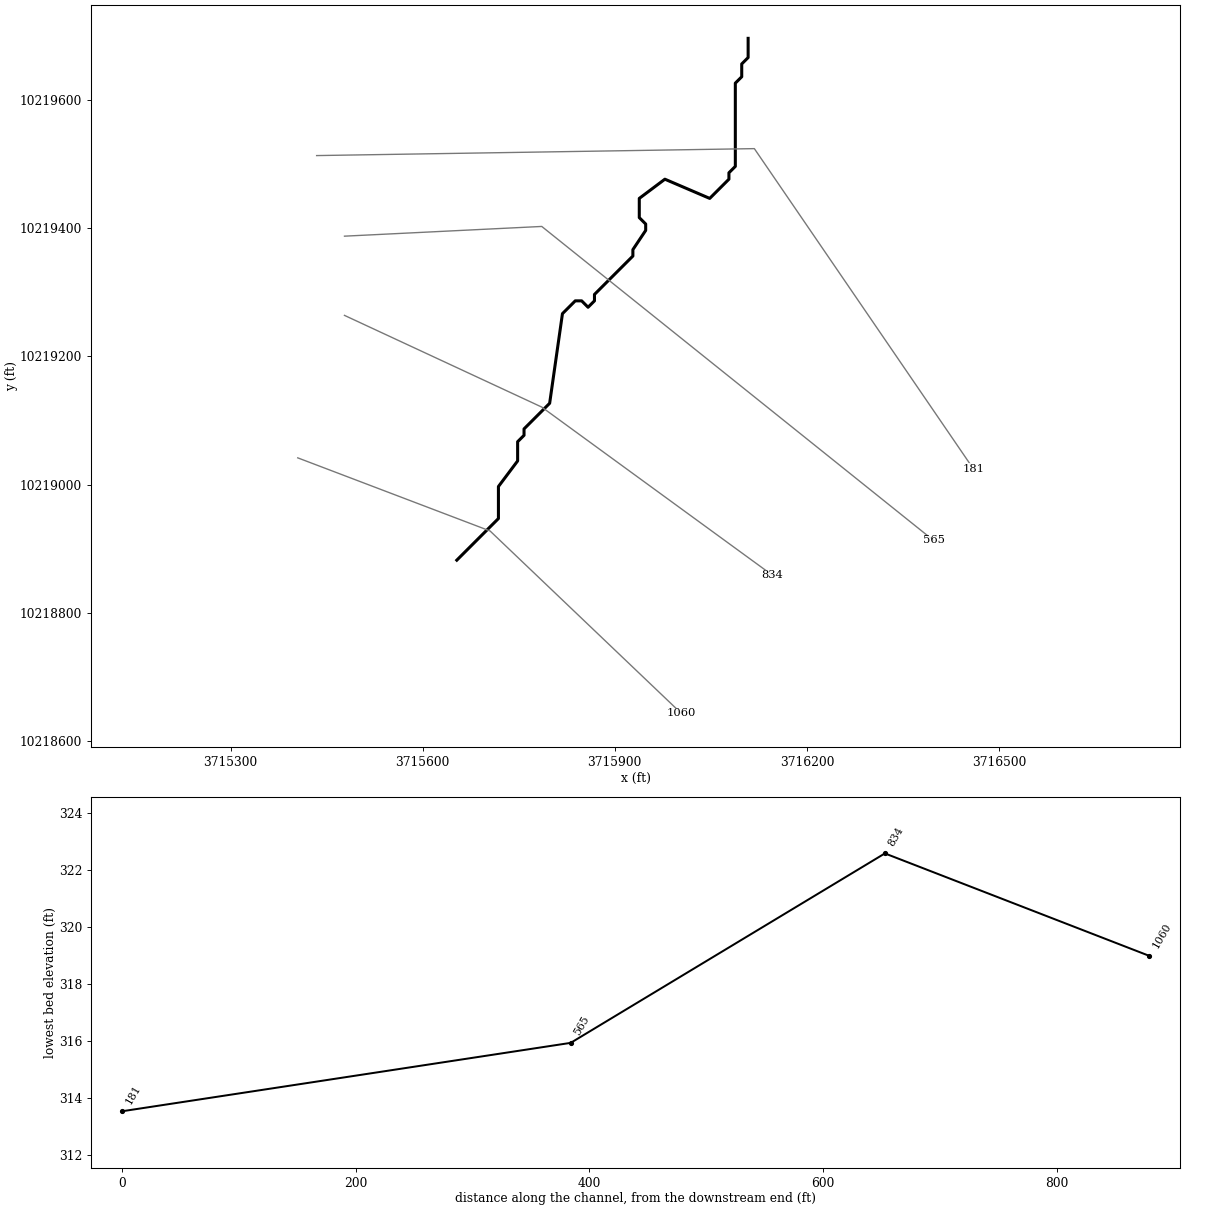
--- WFSJR 012.prj (project) ---

Proj Title=WFSJR 012 Base Level Engineering
Current Plan=p01
Default Exp/Contr=0.3,0.1
English Units
Geom File=g01
Flow File=f01
Flow File=f02
Plan File=p01
Y Axis Title=Elevation
X Axis Title(PF)=Main Channel Distance
X Axis Title(XS)=Station
BEGIN DESCRIPTION:
WFSJR 012
END DESCRIPTION:
DSS Export Rating Curves= 0
DSS Export Rating Curve Sorted= 0
DSS Export Volume Flow Curves= 0
DXF OffsetX= 0
DXF OffsetY= 0
DXF ScaleX= 1
DXF ScaleY= 10

--- WFSJR 012.p01 (plan) ---

Plan Title=Multiple Run
Program Version=4.10
Short Identifier=Multiple
Geom File=g01
Flow File=f01
Subcritical Flow
K Sum by GR= 0
Std Step Tol= 0.01
Critical Tol= 0.01
Num of Std Step Trials= 20
Max Error Tol= 0.3
Flow Tol Ratio= 0.001
Split Flow NTrial= 30
Split Flow Tol= 0.02
Split Flow Ratio= 0.02
Log Output Level= 0
Friction Slope Method= 1
Unsteady Friction Slope Method= 2
Unsteady Bridges Friction Slope Method= 1
Parabolic Critical Depth
Global Vel Dist= 1 , 1 , 1
Global Log Level= 0
CheckData=True
Encroach Param=-1 ,0,0, 0
BEGIN DESCRIPTION:
Multiple Run
END DESCRIPTION:
Computation Interval=1HOUR
Output Interval=1HOUR
Run HTab= 0
Run UNet= 0
Run PostProcess= 0
Run WQNet= 0
UNET Theta= 1
UNET Theta Warmup= 1
UNET ZTol= 0.02
UNET ZSATol= 0.05
UNET MxIter= 20
UNET MaxInSteps= 0
UNET DtIC= 0
UNET DtMin= 0
UNET MaxCRTS= 20
UNET WFStab= 2
UNET SFStab= 1
UNET WFX= 1
UNET SFX= 1
UNET DSS MLevel= 4
UNET DZMax Abort= 100
UNET Convert EG Bridges= 0
UNET Use Existing IB Tables=-1
UNET Froude Reduction=False
UNET Froude Limit= 1
UNET Froude Power= 10
UNET Time Slicing=0,0, 5
UNET Junction Losses=0
Instantaneous Interval=1HOUR
Write IC File= 0
Write IC File at Sim End=0
Echo Input=False
Echo Parameters=False
Echo Output=False
Write Detailed= 0
WQ AD Non Conservative
WQ ULTIMATE=-1
WQ Max Comp Step=1HOUR
WQ Output Interval=15MIN
WQ Output Selected Increments= 0
WQ Output face flow=0
WQ Output face velocity=0
WQ Output face area=0
WQ Output face dispersion=0
WQ Output cell volume=0
WQ Output cell surface area=0
WQ Output cell continuity=0
WQ Output cumulative cell continuity=0
WQ Output face conc=0
WQ Output face dconc_dx=0
WQ Output face courant=0
WQ Output face peclet=0
WQ Output face adv mass=0
WQ Output face disp mass=0
WQ Output cell mass=0
WQ Output cell source sink temp=0
WQ Output cell source sink nsm=0
WQ Output MaxMinRange=-1
WQ Daily Max Min Mean=-1
WQ Daily Range=0
WQ Daily Time=0
WQ Create Restart=0
WQ Fixed Restart=0
WQ System Summary=0
WQ Use Fixed Temperature=0
Sorting and Armoring Iterations= 10
XS Update Threshold= 0.02
Hydraulics Update Threshold= 0.02
Energy Slope Method= 1
Volume Change Method= 0
XS Weighting Method= 0
Number of US Weighted Cross Sections= 1
Number of DS Weighted Cross Sections= 1
Upstream XS Weight=0.25
Main XS Weight=0.5
Downstream XS Weight=0.25
Number of DS XS's Weighted with US Boundary= 1
Upstream Boundary Weight= 1
Weight of XSs Associated with US Boundary= 0
Number of US XS's Weighted with DS Boundary= 1
Downstream Boundary Weight= 0.5
Weight of XSs Associated with DS Boundary= 0.5
Sediment Output Level= 4
Mass or Volume Output= 0
Output Increment Type= 1
Profile and TS Output Increment= 10
XS Output Flag= 0
XS Output Increment= 10
Disregard all LS=0
Disregard all Conn=0
Disregard all Breaches=0
Disregard all Pumps=0

--- WFSJR 012.f01 (steady flow) ---

Flow Title=Multiple
Program Version=4.10
Number of Profiles= 7
Profile Names=10-year,25-year,50-year,1pct_min,100-year,1pct_plu,500-year
River Rch & RM=WFSJR 012,Reach-1         ,1060
     671     923    1262     567    1713    5173    3271
Boundary for River Rch & Prof#=WFSJR 012,Reach-1         , 1
Up Type= 0
Dn Type= 3
Dn Slope=0.01
Boundary for River Rch & Prof#=WFSJR 012,Reach-1         , 2
Up Type= 0
Dn Type= 3
Dn Slope=0.01
Boundary for River Rch & Prof#=WFSJR 012,Reach-1         , 3
Up Type= 0
Dn Type= 3
Dn Slope=0.01
Boundary for River Rch & Prof#=WFSJR 012,Reach-1         , 4
Up Type= 0
Dn Type= 3
Dn Slope=0.01
Boundary for River Rch & Prof#=WFSJR 012,Reach-1         , 5
Up Type= 0
Dn Type= 3
Dn Slope=0.01
Boundary for River Rch & Prof#=WFSJR 012,Reach-1         , 6
Up Type= 0
Dn Type= 3
Dn Slope=0.01
Boundary for River Rch & Prof#=WFSJR 012,Reach-1         , 7
Up Type= 0
Dn Type= 3
Dn Slope=0.01
DSS Import GetInterval= 0
DSS Import GetPeak= 0
DSS Import FillOption= 0

--- WFSJR 012.f02 (steady flow) ---

Flow Title=Orig_BLE_Flow
Program Version=4.10
Number of Profiles= 7
Profile Names=10-year,25-year,50-year,1pct_min,100-year,1pct_plu,500-year
River Rch & RM=WFSJR 012,Reach-1         ,1060
     671     905    1097     437    1318    3982    1902
Boundary for River Rch & Prof#=WFSJR 012,Reach-1         , 1
Up Type= 0
Dn Type= 3
Dn Slope=0.01
Boundary for River Rch & Prof#=WFSJR 012,Reach-1         , 2
Up Type= 0
Dn Type= 3
Dn Slope=0.01
Boundary for River Rch & Prof#=WFSJR 012,Reach-1         , 3
Up Type= 0
Dn Type= 3
Dn Slope=0.01
Boundary for River Rch & Prof#=WFSJR 012,Reach-1         , 4
Up Type= 0
Dn Type= 3
Dn Slope=0.01
Boundary for River Rch & Prof#=WFSJR 012,Reach-1         , 5
Up Type= 0
Dn Type= 3
Dn Slope=0.01
Boundary for River Rch & Prof#=WFSJR 012,Reach-1         , 6
Up Type= 0
Dn Type= 3
Dn Slope=0.01
Boundary for River Rch & Prof#=WFSJR 012,Reach-1         , 7
Up Type= 0
Dn Type= 3
Dn Slope=0.01
DSS Import GetInterval= 0
DSS Import GetPeak= 0
DSS Import FillOption= 0

--- WFSJR 012.g01 (geometry) ---

Geom Title=Existing Conditions
Program Version=4.10

River Reach=WFSJR 012       ,Reach-1
Reach XY= 30
      3715653.23     10218881.84      3715718.23     10218946.84
      3715718.23     10218996.84      3715748.23     10219036.84
      3715748.23     10219066.84      3715758.23     10219076.84
      3715758.23     10219086.84      3715798.23     10219126.84
      3715818.23     10219266.84      3715838.23     10219286.84
      3715848.23     10219286.84      3715858.23     10219276.84
      3715868.23     10219286.84      3715868.23     10219296.84
      3715928.23     10219356.84      3715928.23     10219366.84
      3715948.23     10219396.84      3715948.23     10219406.84
      3715938.23     10219416.84      3715938.23     10219446.84
      3715978.23     10219476.84      3716048.23     10219446.84
      3716078.23     10219476.84      3716078.23     10219486.84
      3716088.23     10219496.84      3716088.23     10219626.84
      3716098.23     10219636.84      3716098.23     10219656.84
      3716108.23     10219666.84      3716108.23     10219696.84

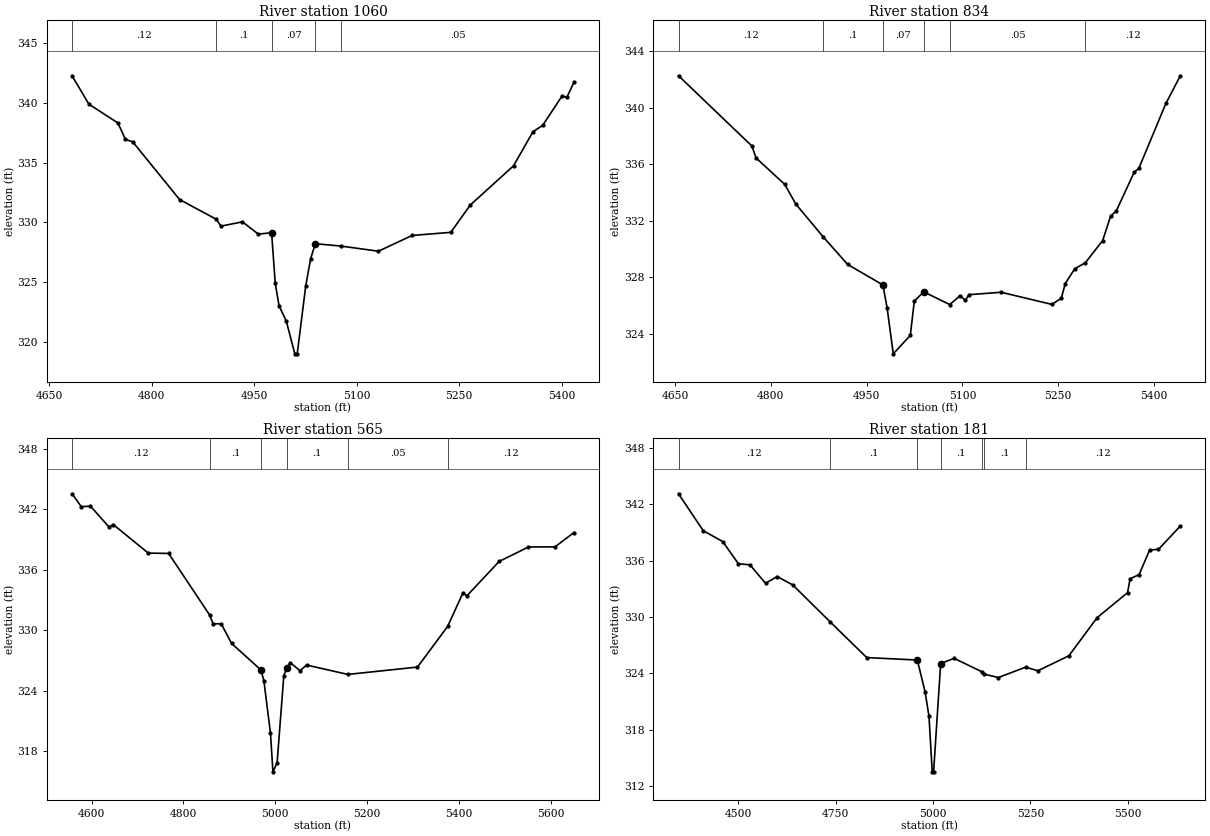
Type RM Length L Ch R = 1 ,1060    ,226,226,226
BEGIN DESCRIPTION:
WFSJR 012 2.0
END DESCRIPTION:
XS GIS Cut Line= 3
      3715404.82     10219041.63      3715705.21      10218927.4
      3716003.87     10218642.55
#Sta/Elev= 30
  4683.6  342.29  4708.2  339.91  4750.6  338.34  4761.7  336.96  4772.4  336.75
  4840.9  331.92  4894.8  330.26  4901.2  329.69  4932.9  330.05  4956.1  329.02
  4975.5  329.14  4980.8  324.92  4986.4  323.02  4997.1  321.71  5009.5  318.99
    5013  318.99  5025.4  324.67  5032.6  326.96  5039.5  328.22  5077.2  328.02
  5131.7  327.59  5181.1  328.91  5237.7  329.17    5266  331.45  5329.5  334.75
  5357.8   337.6    5372  338.13  5400.3  340.58  5407.5  340.49  5417.7  341.73
#Mann= 5 ,-1 , 0
  4683.6     .12       0  4894.8      .1       0  4975.5     .07       0
  5039.5      .1       0  5077.2     .05       0
Bank Sta=4975.5,5039.5
XS Rating Curve= 0 ,0
Exp/Cntr=0.3,0.1

Type RM Length L Ch R = 1 ,834     ,269,269,269
BEGIN DESCRIPTION:
Mapping XS d754e009
END DESCRIPTION:
XS GIS Cut Line= 3
      3715477.76     10219264.16      3715785.91     10219120.93
      3716146.15     10218858.35
#Sta/Elev= 30
  4655.6  342.27  4770.6  337.29    4777  336.45  4821.9  334.58  4839.3  333.18
  4882.3  330.85  4920.4  328.91  4975.5  327.46  4982.1  325.85  4991.8  322.58
  5018.5  323.89  5024.7  326.31  5039.4  326.97  5080.2  326.07  5096.8  326.71
  5104.3  326.36  5110.5  326.77  5160.7  326.94  5240.2  326.08  5254.9  326.52
  5261.1  327.56  5275.8   328.6  5292.5  329.03  5319.6   330.6  5332.2  332.35
  5340.7  332.68  5369.1  335.45  5376.2  335.71  5418.6  340.31  5441.2  342.27
#Mann= 6 ,-1 , 0
  4655.6     .12       0  4882.3      .1       0  4975.5     .07       0
  5039.4      .1       0  5080.2     .05       0  5292.5     .12       0
Bank Sta=4975.5,5039.4
XS Rating Curve= 0 ,0
Exp/Cntr=0.3,0.1

Type RM Length L Ch R = 1 ,565     ,384,384,384
BEGIN DESCRIPTION:
Mapping XS 8a6895e8
END DESCRIPTION:
XS GIS Cut Line= 3
       3715477.8     10219387.86      3715785.91     10219403.05
      3716397.86     10218912.63
#Sta/Elev= 30
  4557.4  343.53  4577.5  342.25  4597.5   342.3  4637.5  340.25  4647.6  340.46
  4723.4  337.64  4767.7  337.61  4857.2  331.48  4864.4  330.63  4882.3  330.62
  4904.7  328.68  4968.7  326.04  4975.1  324.97  4989.5  319.74  4994.8  315.93
  5003.9  316.82  5018.4  325.43  5024.8  326.28  5032.8  326.76  5053.6  325.97
    5068  326.53    5158   325.6  5309.6  326.33  5375.2  330.36  5408.9  333.72
  5416.9  333.39  5487.3  336.81  5551.3  338.25  5608.9  338.26  5650.1  339.67
#Mann= 6 ,-1 , 0
  4557.4     .12       0  4857.2      .1       0  4968.7     .07       0
  5024.8      .1       0    5158     .05       0  5375.2     .12       0
#XS Ineff= 1 ,-1
  5032.8    5325  326.76
Permanent Ineff=
       F
Bank Sta=4968.7,5024.8
XS Rating Curve= 0 ,0
Exp/Cntr=0.3,0.1

Type RM Length L Ch R = 1 ,181     ,0,0,0
BEGIN DESCRIPTION:
WFSJR 012 1.0
END DESCRIPTION:
XS GIS Cut Line= 3
      3715434.31     10219513.73      3716117.94     10219524.58
      3716459.89     10219024.65
#Sta/Elev= 30
    4346   343.1  4409.5  339.17  4459.6  338.02  4499.6  335.67  4529.6  335.54
  4569.6  333.58  4599.6   334.3  4639.6   333.4    4736  329.46  4829.6  325.68
  4959.6  325.42  4979.6  322.03  4989.6  319.42  4997.9  313.53  5001.4  313.53
  5019.6  325.05  5054.1   325.6  5125.1  324.18  5130.4  323.93  5167.8  323.56
  5237.9  324.66  5269.4  324.28    5349  325.87  5421.7  329.93  5499.7  332.58
  5506.5  334.07  5529.5   334.5  5556.5  337.12  5579.2  337.19  5635.4  339.67
#Mann= 7 ,-1 , 0
    4346     .12       0    4736      .1       0  4959.6     .07       0
  5019.6      .1       0  5125.1     .12       0  5130.4      .1       0
  5237.9     .12       0
#XS Ineff= 1 ,-1
  5054.1    5345   325.6
Permanent Ineff=
       F
Bank Sta=4959.6,5019.6
XS Rating Curve= 0 ,0
Exp/Cntr=0.3,0.1

Chan Stop Cuts=-1
Use User Specified Reach Order=0
Composite Channel Slope=5