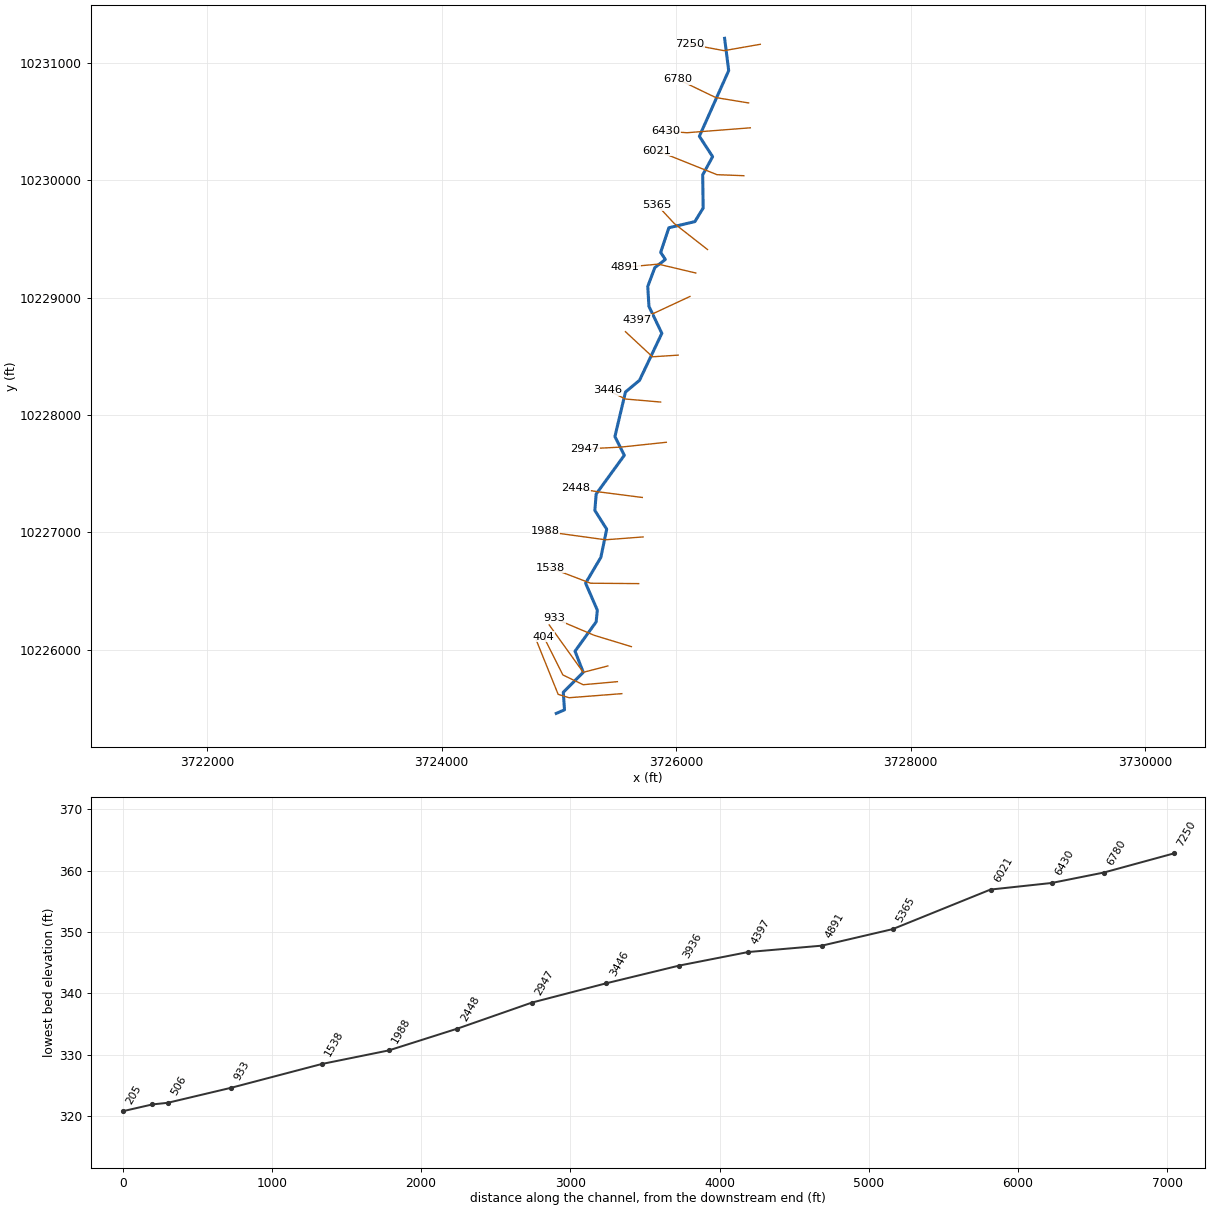
--- WFSJR 016.prj (project) ---

Proj Title=WFSJR 016 Base Level Engineering
Current Plan=p01
Default Exp/Contr=0.3,0.1
English Units
Geom File=g01
Flow File=f01
Plan File=p01
Y Axis Title=Elevation
X Axis Title(PF)=Main Channel Distance
X Axis Title(XS)=Station
BEGIN DESCRIPTION:
WFSJR 016
END DESCRIPTION:
DSS Export Rating Curves= 0
DSS Export Rating Curve Sorted= 0
DSS Export Volume Flow Curves= 0
DXF OffsetX= 0
DXF OffsetY= 0
DXF ScaleX= 1
DXF ScaleY= 10

--- WFSJR 016.p01 (plan) ---

Plan Title=Multiple Run
Program Version=4.10
Short Identifier=Multiple
Geom File=g01
Flow File=f01
Subcritical Flow
K Sum by GR= 0
Std Step Tol= 0.01
Critical Tol= 0.01
Num of Std Step Trials= 20
Max Error Tol= 0.3
Flow Tol Ratio= 0.001
Split Flow NTrial= 30
Split Flow Tol= 0.02
Split Flow Ratio= 0.02
Log Output Level= 0
Friction Slope Method= 1
Unsteady Friction Slope Method= 2
Unsteady Bridges Friction Slope Method= 1
Parabolic Critical Depth
Global Vel Dist= 1 , 1 , 1
Global Log Level= 0
CheckData=True
Encroach Param=-1 ,0,0, 0
BEGIN DESCRIPTION:
Multiple Run
END DESCRIPTION:
Computation Interval=1HOUR
Output Interval=1HOUR
Run HTab= 0
Run UNet= 0
Run PostProcess= 0
Run WQNet= 0
UNET Theta= 1
UNET Theta Warmup= 1
UNET ZTol= 0.02
UNET ZSATol= 0.05
UNET MxIter= 20
UNET MaxInSteps= 0
UNET DtIC= 0
UNET DtMin= 0
UNET MaxCRTS= 20
UNET WFStab= 2
UNET SFStab= 1
UNET WFX= 1
UNET SFX= 1
UNET DSS MLevel= 4
UNET DZMax Abort= 100
UNET Convert EG Bridges= 0
UNET Use Existing IB Tables=-1
UNET Froude Reduction=False
UNET Froude Limit= 1
UNET Froude Power= 10
UNET Time Slicing=0,0, 5
UNET Junction Losses=0
Instantaneous Interval=1HOUR
Write IC File= 0
Write IC File at Sim End=0
Echo Input=False
Echo Parameters=False
Echo Output=False
Write Detailed= 0
WQ AD Non Conservative
WQ ULTIMATE=-1
WQ Max Comp Step=1HOUR
WQ Output Interval=15MIN
WQ Output Selected Increments= 0
WQ Output face flow=0
WQ Output face velocity=0
WQ Output face area=0
WQ Output face dispersion=0
WQ Output cell volume=0
WQ Output cell surface area=0
WQ Output cell continuity=0
WQ Output cumulative cell continuity=0
WQ Output face conc=0
WQ Output face dconc_dx=0
WQ Output face courant=0
WQ Output face peclet=0
WQ Output face adv mass=0
WQ Output face disp mass=0
WQ Output cell mass=0
WQ Output cell source sink temp=0
WQ Output cell source sink nsm=0
WQ Output MaxMinRange=-1
WQ Daily Max Min Mean=-1
WQ Daily Range=0
WQ Daily Time=0
WQ Create Restart=0
WQ Fixed Restart=0
WQ System Summary=0
WQ Use Fixed Temperature=0
Sorting and Armoring Iterations= 10
XS Update Threshold= 0.02
Hydraulics Update Threshold= 0.02
Energy Slope Method= 1
Volume Change Method= 0
XS Weighting Method= 0
Number of US Weighted Cross Sections= 1
Number of DS Weighted Cross Sections= 1
Upstream XS Weight=0.25
Main XS Weight=0.5
Downstream XS Weight=0.25
Number of DS XS's Weighted with US Boundary= 1
Upstream Boundary Weight= 1
Weight of XSs Associated with US Boundary= 0
Number of US XS's Weighted with DS Boundary= 1
Downstream Boundary Weight= 0.5
Weight of XSs Associated with DS Boundary= 0.5
Sediment Output Level= 4
Mass or Volume Output= 0
Output Increment Type= 1
Profile and TS Output Increment= 10
XS Output Flag= 0
XS Output Increment= 10
Disregard all LS=0
Disregard all Conn=0
Disregard all Breaches=0
Disregard all Pumps=0

--- WFSJR 016.f01 (steady flow) ---

Flow Title=Multiple
Program Version=4.10
Number of Profiles= 7
Profile Names=10-year,25-year,50-year,1pct_min,100-year,1pct_plu,500-year
River Rch & RM=WFSJR 016,Reach-1         ,7250
     603     826    1126     505    1526    4608    2900
River Rch & RM=WFSJR 016,Reach-1         ,6780
     813    1125    1542     695    2100    6342    4028
Boundary for River Rch & Prof#=WFSJR 016,Reach-1         , 1
Up Type= 0
Dn Type= 3
Dn Slope=0.005
Boundary for River Rch & Prof#=WFSJR 016,Reach-1         , 2
Up Type= 0
Dn Type= 3
Dn Slope=0.005
Boundary for River Rch & Prof#=WFSJR 016,Reach-1         , 3
Up Type= 0
Dn Type= 3
Dn Slope=0.005
Boundary for River Rch & Prof#=WFSJR 016,Reach-1         , 4
Up Type= 0
Dn Type= 3
Dn Slope=0.005
Boundary for River Rch & Prof#=WFSJR 016,Reach-1         , 5
Up Type= 0
Dn Type= 3
Dn Slope=0.005
Boundary for River Rch & Prof#=WFSJR 016,Reach-1         , 6
Up Type= 0
Dn Type= 3
Dn Slope=0.005
Boundary for River Rch & Prof#=WFSJR 016,Reach-1         , 7
Up Type= 0
Dn Type= 3
Dn Slope=0.005
DSS Import GetInterval= 0
DSS Import GetPeak= 0
DSS Import FillOption= 0

--- WFSJR 016.g01 (geometry) ---

Geom Title=Existing Conditions
Program Version=4.10

River Reach=WFSJR 016       ,Reach-1
Reach XY= 30
      3726413.23     10231211.84      3726448.23     10230936.84
      3726198.23     10230376.84      3726311.17     10230203.15
       3726226.5     10230047.77      3726230.48     10229764.89
      3726159.76     10229649.34      3725938.23     10229596.84
      3725868.23     10229386.84      3725908.23     10229326.84
      3725818.23     10229256.84      3725758.23     10229096.84
      3725768.23     10228926.84      3725878.23     10228696.84
      3725688.23     10228296.84      3725568.23     10228196.84
      3725478.23     10227816.84      3725558.23     10227656.84
      3725318.23     10227326.84      3725307.14     10227187.08
      3725408.23     10227026.84      3725358.23     10226786.84
      3725228.23     10226566.84      3725328.23     10226336.84
      3725318.23     10226236.84      3725138.23     10225986.84
      3725208.23     10225806.84      3725038.23     10225636.84
      3725048.23     10225486.84      3724978.23     10225456.84

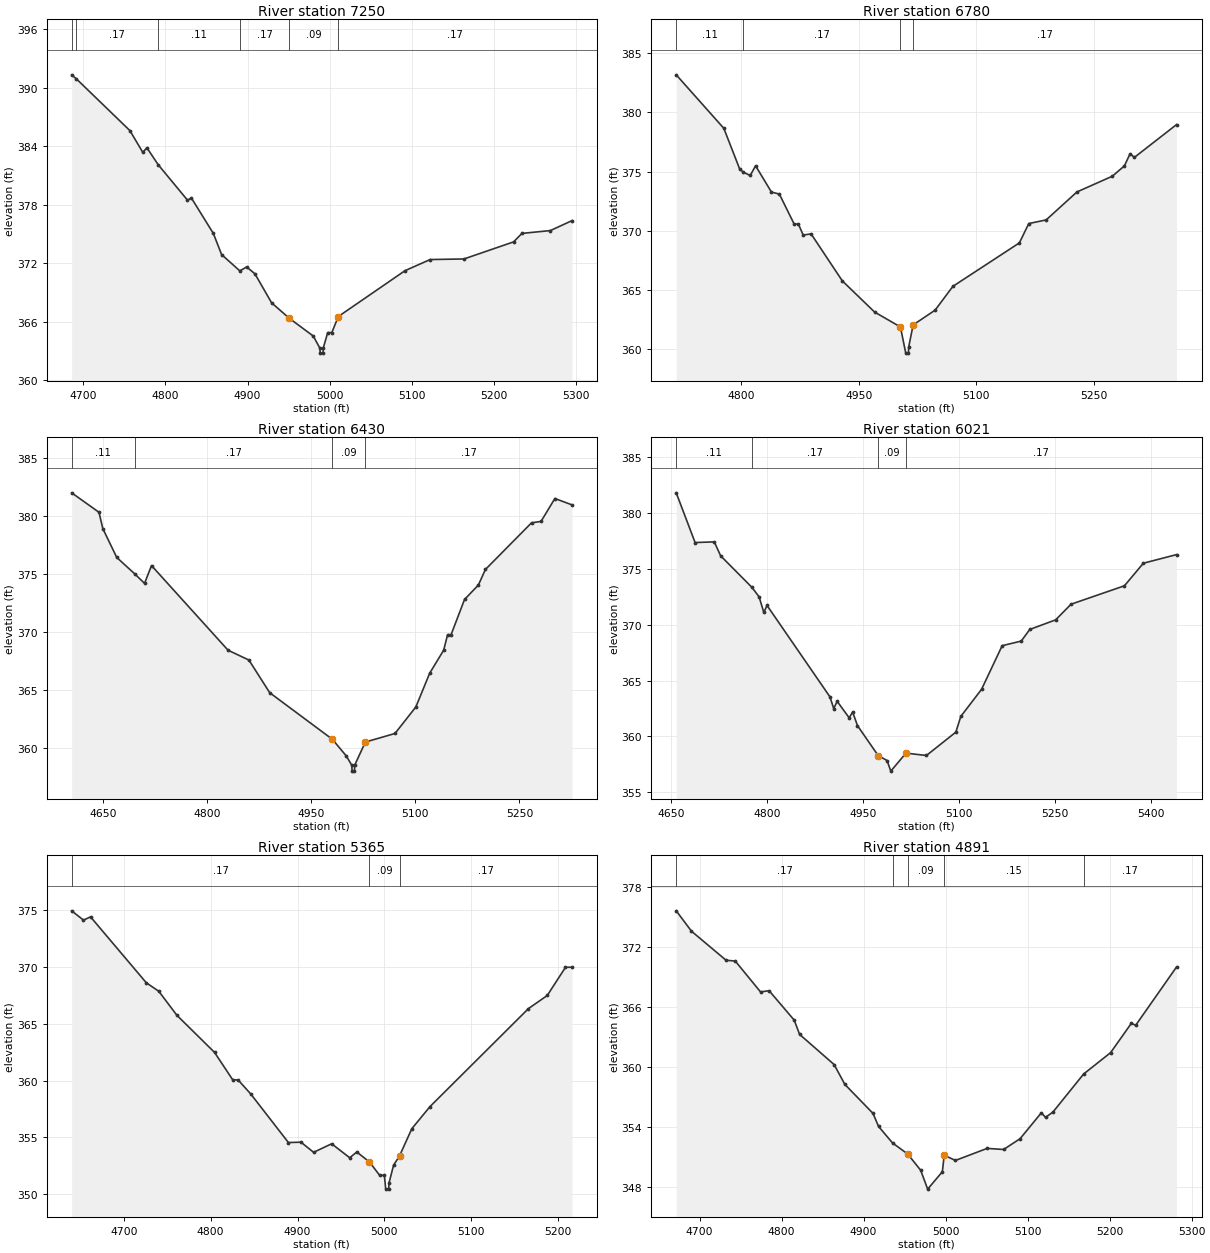
Type RM Length L Ch R = 1 ,7250    ,470,470,470
BEGIN DESCRIPTION:
WFSJR 016 15.0
END DESCRIPTION:
XS GIS Cut Line= 3
      3726717.82     10231161.07      3726408.23     10231106.84
      3726117.85     10231161.07
#Sta/Elev= 30
  4685.7  391.31  4691.5  390.89  4756.7  385.59  4772.3  383.37  4777.4  383.83
  4791.1   382.1  4826.7  378.48  4831.7  378.67  4858.3  375.06  4868.4  372.89
  4890.6  371.22  4898.9  371.62    4909  370.92  4929.3  367.95  4950.6  366.38
  4980.1  364.54  4988.2  363.29  4988.5  362.79    4992  362.79  4992.2  363.29
  4997.7  364.89  5002.7  364.89  5010.6  366.54  5091.9  371.24  5122.5  372.38
  5163.7  372.44  5224.2  374.19  5234.4  375.06  5269.1  375.35  5295.4  376.37
#Mann= 6 ,-1 , 0
  4685.7     .11       0  4691.5     .17       0  4791.1     .11       0
  4890.6     .17       0  4950.6     .09       0  5010.6     .17       0
Bank Sta=4950.6,5010.6
XS Rating Curve= 0 ,0
Exp/Cntr=0.3,0.1

Type RM Length L Ch R = 1 ,6780    ,350,350,350
BEGIN DESCRIPTION:
WFSJR 016 14.0
END DESCRIPTION:
XS GIS Cut Line= 3
      3726617.81     10230661.08      3726338.23     10230706.84
      3726017.82     10230861.09
#Sta/Elev= 30
  4716.7  383.17  4777.5  378.65  4797.7  375.22  4802.3  374.95  4811.2  374.67
    4818  375.49  4838.3  373.27  4848.4   373.1  4867.5  370.54  4872.6  370.59
  4878.8  369.64  4888.9  369.74  4928.8  365.77    4970  363.14    5003  361.88
  5009.8  359.67  5013.3  359.67  5013.5  360.17  5019.2  362.05  5047.3   363.3
    5070  365.31  5154.9  368.98  5166.9  370.61  5189.1  370.92  5228.4  373.28
  5273.6  374.61    5289  375.48  5296.2   376.5  5301.8   376.2  5355.6  378.97
#Mann= 4 ,-1 , 0
  4716.7     .11       0  4802.3     .17       0    5003     .09       0
  5019.2     .17       0
Bank Sta=5003,5019.2
XS Rating Curve= 0 ,0
Exp/Cntr=0.3,0.1

Type RM Length L Ch R = 1 ,6430    ,409,409,409
BEGIN DESCRIPTION:
WFSJR 016 13.0
END DESCRIPTION:
XS GIS Cut Line= 3
      3726632.64     10230449.08      3726091.48     10230407.02
      3725913.27     10230420.31
#Sta/Elev= 30
  4604.4     382  4643.8  380.32  4649.3  378.91  4669.4  376.42    4695  375.02
  4709.5  374.18  4719.5  375.72  4829.9  368.41    4860  367.56    4890  364.74
  4980.3  360.72  5000.4  359.28  5008.4  358.47  5008.7  357.97  5012.2  357.97
  5012.4  358.47  5027.9  360.48  5070.6  361.22  5100.7  363.51  5120.7  366.43
  5140.8  368.41  5146.5  369.75  5151.5  369.75  5170.9  372.79  5190.9  374.04
    5201  375.38  5267.5  379.41  5281.2  379.53  5301.2  381.51  5325.9  380.96
#Mann= 4 ,-1 , 0
  4604.4     .11       0    4695     .17       0  4980.3     .09       0
  5027.9     .17       0
Bank Sta=4980.3,5027.9
XS Rating Curve= 0 ,0
Exp/Cntr=0.3,0.1

Type RM Length L Ch R = 1 ,6021    ,656,656,656
BEGIN DESCRIPTION:
WFSJR 016 12.0
END DESCRIPTION:
XS GIS Cut Line= 3
      3726577.31     10230040.68      3726348.25     10230049.54
      3725834.71      10230255.4
#Sta/Elev= 30
  4657.7  381.81  4687.2  377.36  4717.2  377.42  4727.2  376.17  4776.1  373.35
  4787.3   372.5  4794.7   371.1  4799.7  371.73  4898.1  363.55    4904   362.5
  4909.4  363.15  4928.2  361.67  4933.6  362.19  4941.2  360.97  4973.6  358.29
  4987.4  357.85  4993.3   356.9    5017  358.51    5049   358.3    5095  360.39
  5102.8   361.8  5135.2  364.22  5167.5  368.13  5197.3  368.54  5210.6  369.58
  5251.1  370.44  5275.2  371.84  5358.7  373.49  5388.3  375.51  5440.2  376.28
#Mann= 4 ,-1 , 0
  4657.7     .11       0  4776.1     .17       0  4973.6     .09       0
    5017     .17       0
Bank Sta=4973.6,5017
XS Rating Curve= 0 ,0
Exp/Cntr=0.3,0.1

Type RM Length L Ch R = 1 ,5365    ,474,474,474
BEGIN DESCRIPTION:
WFSJR 016 11.0
END DESCRIPTION:
XS GIS Cut Line= 3
      3726267.84     10229411.08      3725984.32     10229632.93
      3725837.45     10229791.32
#Sta/Elev= 30
    4640  374.94  4653.6  374.12  4661.7  374.41  4725.9  368.61  4740.3  367.86
  4761.1  365.75  4804.5  362.48  4825.3  360.08  4831.7  360.05  4846.2  358.82
  4889.5  354.55    4904  354.58  4918.5  353.69  4939.3  354.44  4960.1  353.21
  4968.2  353.72  4982.7  352.85  4994.6  351.66    5000  351.66  5001.5  350.45
    5005  350.45  5005.2  350.95  5010.6  352.56  5017.4  353.37  5031.6  355.77
  5052.6  357.72  5165.9  366.34  5187.5  367.49  5208.5  369.97    5216  369.98
#Mann= 3 , 0 , 0
    4640     .17       0  4982.7     .09       0  5017.4     .17       0
Bank Sta=4982.7,5017.4
XS Rating Curve= 0 ,0
Exp/Cntr=0.3,0.1

Type RM Length L Ch R = 1 ,4891    ,494,494,494
BEGIN DESCRIPTION:
WFSJR 016 10.0
END DESCRIPTION:
XS GIS Cut Line= 3
      3726167.87     10229211.07      3725848.23     10229286.84
      3725567.81     10229261.07
#Sta/Elev= 30
  4671.5  375.63  4690.1  373.59  4732.3  370.68  4743.5   370.6  4774.3  367.51
  4784.8  367.63  4815.4  364.68  4821.9  363.26  4864.1  360.23  4877.1  358.25
  4911.5  355.34  4918.2  354.04  4935.3  352.38  4953.7  351.28  4969.6  349.65
  4978.1  347.76    4996   349.5  4998.3  351.16  5011.9  350.63  5050.6  351.84
  5070.7  351.73  5090.8  352.81  5116.8  355.41  5121.8  354.94  5130.9  355.48
  5168.3  359.29  5201.2  361.43  5226.6  364.38  5231.7  364.16  5281.6  370.01
#Mann= 5 ,-1 , 0
  4671.5     .17       0  4935.3     .15       0  4953.7     .09       0
  4998.3     .15       0  5168.3     .17       0
Bank Sta=4953.7,4998.3
XS Rating Curve= 0 ,0
Exp/Cntr=0.3,0.1

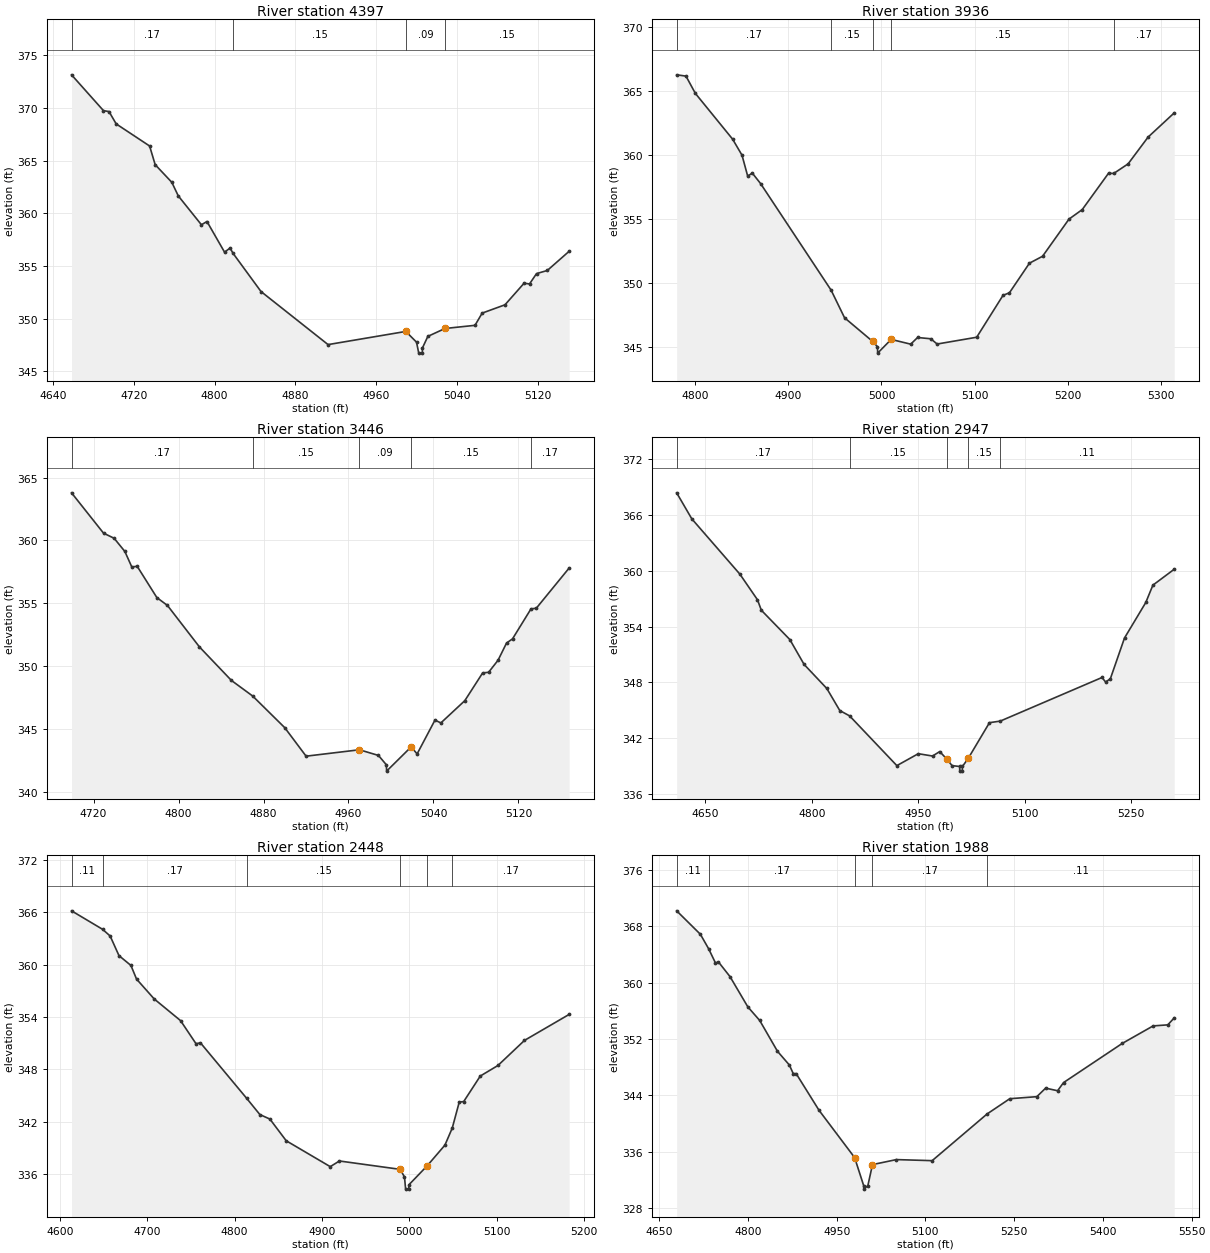
Type RM Length L Ch R = 1 ,4397    ,461,461,461
BEGIN DESCRIPTION:
WFSJR 016 9.0
END DESCRIPTION:
XS GIS Cut Line= 3
      3726117.88     10229011.09      3725808.23     10228866.84
      3725667.81     10228811.05
#Sta/Elev= 30
  4658.4  373.15    4690  369.75  4695.5  369.66  4702.6  368.49  4735.7  366.39
  4741.2  364.62  4757.7  362.94  4764.1  361.65    4787  358.91  4792.5  359.22
  4809.9  356.31  4815.4   356.7  4818.3   356.2    4846  352.57  4912.4  347.53
  4989.4  348.78    5000  347.76  5002.2  346.72  5005.7  346.72  5005.9  347.22
  5011.2  348.31  5028.2  349.06  5057.9  349.36    5065  350.52  5087.6  351.31
  5106.5  353.36  5111.9  353.29  5118.8  354.27  5129.5  354.57  5151.1  356.39
#Mann= 4 ,-1 , 0
  4658.4     .17       0  4818.3     .15       0  4989.4     .09       0
  5028.2     .15       0
Bank Sta=4989.4,5028.2
XS Rating Curve= 0 ,0
Exp/Cntr=0.3,0.1

Type RM Length L Ch R = 1 ,3936    ,490,490,490
BEGIN DESCRIPTION:
WFSJR 016 8.0
END DESCRIPTION:
XS GIS Cut Line= 3
      3726017.87     10228511.07      3725798.23     10228496.84
      3725567.84     10228711.08
#Sta/Elev= 30
  4779.9  366.24  4789.9  366.14    4800  364.79    4840  361.22  4850.1  359.97
  4856.2  358.34  4861.2  358.57  4870.1  357.75  4945.9  349.43  4960.3  347.28
  4990.4  345.44  4995.7  345.02  4995.9  344.52  5010.4  345.59  5031.4  345.22
  5038.8  345.74    5053  345.64  5059.8  345.23  5102.3  345.76  5130.6  349.03
  5137.5  349.23    5159  351.54  5173.1  352.08  5201.5  354.98  5215.7  355.72
    5244  358.56  5249.5  358.54    5265  359.29  5286.5  361.38  5314.6  363.27
#Mann= 5 ,-1 , 0
  4779.9     .17       0  4945.9     .15       0  4990.4     .09       0
  5010.4     .15       0  5249.5     .17       0
Bank Sta=4990.4,5010.4
XS Rating Curve= 0 ,0
Exp/Cntr=0.3,0.1

Type RM Length L Ch R = 1 ,3446    ,499,499,499
BEGIN DESCRIPTION:
WFSJR 016 7.0
END DESCRIPTION:
XS GIS Cut Line= 3
      3725867.82     10228111.07      3725568.23     10228136.84
      3725417.85     10228211.07
#Sta/Elev= 30
  4699.3  363.79  4729.4  360.58  4739.4  360.17  4749.5  359.12    4756  357.89
  4761.1  357.94  4779.6  355.45  4789.6  354.82  4819.7  351.52  4849.8  348.85
  4869.8  347.61    4900  345.09  4920.1  342.82  4970.3  343.33  4988.2  342.88
  4995.7  342.13  4995.9  341.63    5019  343.56  5024.6     343  5041.4  345.69
    5047  345.47  5069.5  347.24  5086.3  349.45  5091.9   349.5  5100.8  350.46
  5108.8  351.83  5114.4  352.16  5131.8  354.55  5136.8   354.6  5167.7   357.8
#Mann= 5 ,-1 , 0
  4699.3     .17       0  4869.8     .15       0  4970.3     .09       0
    5019     .15       0  5131.8     .17       0
Bank Sta=4970.3,5019
XS Rating Curve= 0 ,0
Exp/Cntr=0.3,0.1

Type RM Length L Ch R = 1 ,2947    ,499,499,499
BEGIN DESCRIPTION:
WFSJR 016 6.0
END DESCRIPTION:
XS GIS Cut Line= 3
      3725916.45     10227768.07      3725528.23     10227726.84
      3725217.83     10227711.07
#Sta/Elev= 30
  4609.6  368.35  4630.9  365.56  4698.7  359.62  4723.5  356.87  4728.9  355.75
  4769.1   352.6  4789.2  349.93  4821.2  347.35  4839.5  344.98  4853.3  344.41
  4919.9  339.07  4950.1  340.35  4970.2   340.1  4980.3  340.58  4990.3  339.77
  4997.7  339.07  5008.3  338.98  5008.6  338.48  5012.1  338.48  5012.3  338.98
  5020.4  339.84  5050.4  343.68  5065.6  343.85    5209  348.53    5214  348.05
  5220.7  348.38  5240.7  352.77  5270.7  356.58  5280.7  358.44  5310.8  360.15
#Mann= 5 ,-1 , 0
  4609.6     .17       0  4853.3     .15       0  4990.3     .09       0
  5020.4     .15       0  5065.6     .11       0
Bank Sta=4990.3,5020.4
XS Rating Curve= 0 ,0
Exp/Cntr=0.3,0.1

Type RM Length L Ch R = 1 ,2448    ,460,460,460
BEGIN DESCRIPTION:
WFSJR 016 5.0
END DESCRIPTION:
XS GIS Cut Line= 3
      3725711.68     10227297.58      3725328.23     10227346.84
      3725147.42     10227375.71
#Sta/Elev= 30
  4613.4  366.18  4648.9  364.06  4657.6  363.29  4667.7  361.04  4681.4  359.91
  4687.8  358.35    4708  356.07  4738.2  353.58  4755.9  350.93    4761  351.03
    4814  344.65    4829   342.8  4840.5  342.28  4859.2  339.79  4909.6  336.82
  4920.1  337.47  4989.6  336.51  4994.6  335.64  4995.9  334.24  4999.4  334.24
  4999.7  334.74  5020.6  336.92  5040.9  339.29  5049.3  341.25  5057.3  344.23
  5062.4  344.29  5081.4  347.22  5101.6  348.43    5132  351.31  5183.1  354.29
#Mann= 6 ,-1 , 0
  4613.4     .11       0  4648.9     .17       0    4814     .15       0
  4989.6     .09       0  5020.6     .15       0  5049.3     .17       0
Bank Sta=4989.6,5020.6
XS Rating Curve= 0 ,0
Exp/Cntr=0.3,0.1

Type RM Length L Ch R = 1 ,1988    ,450,450,450
BEGIN DESCRIPTION:
WFSJR 016 4.0
END DESCRIPTION:
XS GIS Cut Line= 3
      3725717.81     10226961.07      3725398.23     10226936.84
      3724882.46      10227007.6
#Sta/Elev= 30
  4679.5  370.18  4719.6  366.85  4733.5   364.8  4745.1  362.78  4750.1  362.93
  4769.7  360.84  4799.8  356.55  4819.9  354.62  4849.9  350.25    4870   348.3
  4876.5  347.09  4881.5  347.08  4920.2  341.87  4980.3  335.17  4995.6  331.19
  4995.9  330.69  5002.7  331.19  5010.5  334.17  5050.9  334.88  5111.4  334.73
  5204.3  341.36  5242.6  343.52  5288.3  343.81  5303.2  345.02  5323.4  344.65
  5333.5  345.81  5432.6  351.36  5484.9  353.85  5509.7     354  5520.6  354.99
#Mann= 5 ,-1 , 0
  4679.5     .11       0  4733.5     .17       0  4980.3     .09       0
  5010.5     .17       0  5204.3     .11       0
Bank Sta=4980.3,5010.5
XS Rating Curve= 0 ,0
Exp/Cntr=0.3,0.1

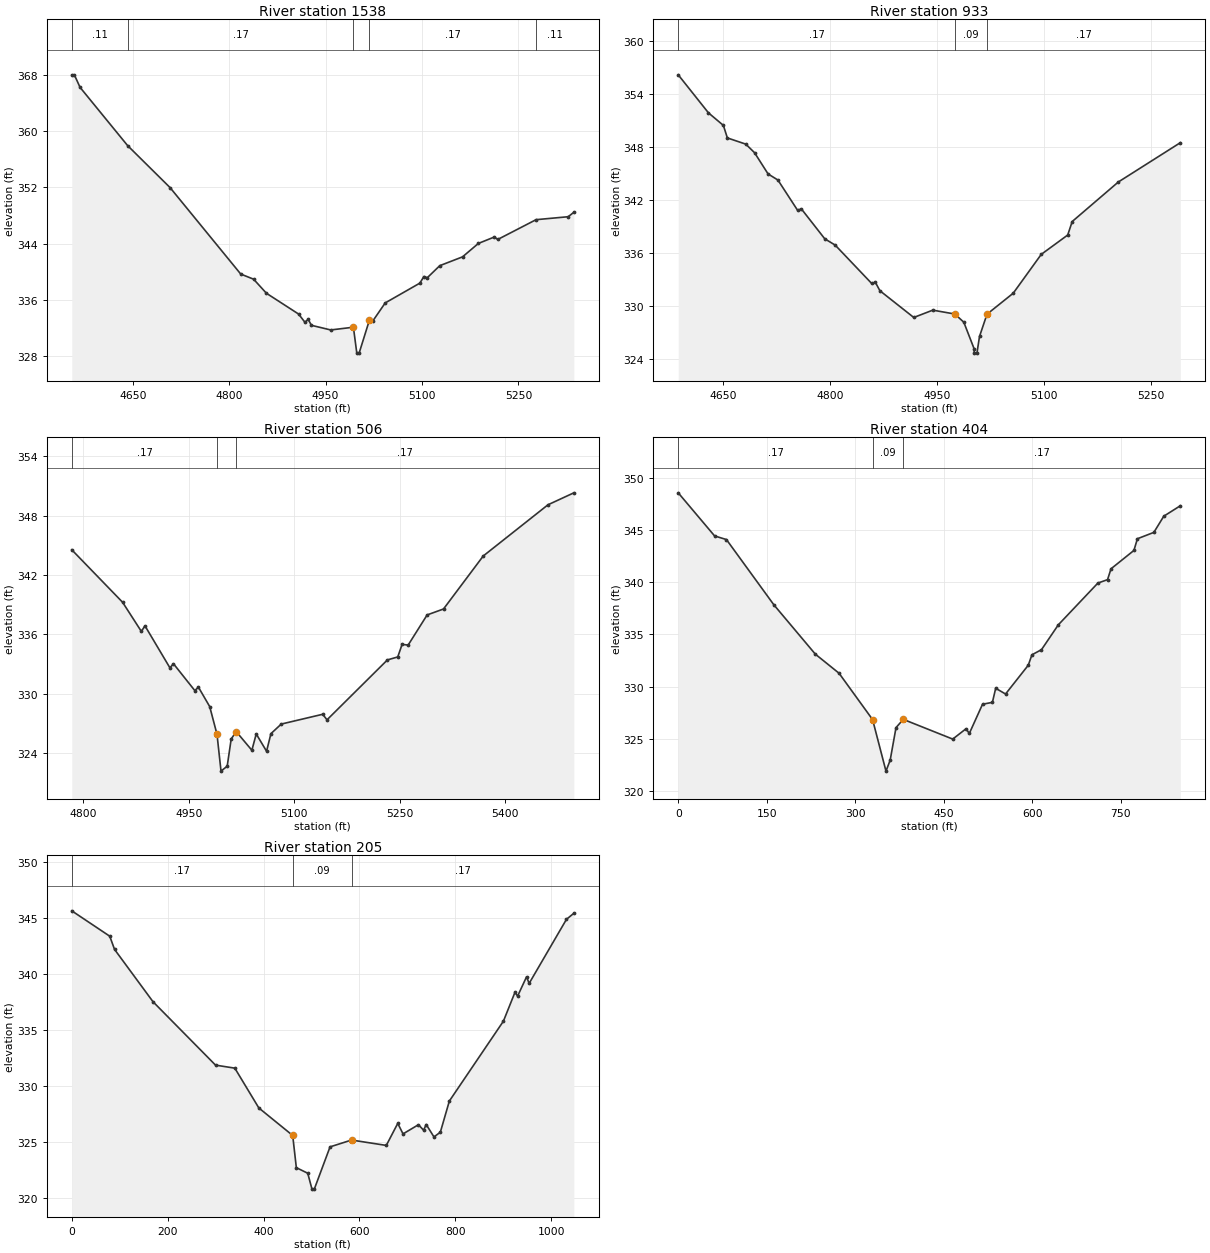
Type RM Length L Ch R = 1 ,1538    ,605,605,605
BEGIN DESCRIPTION:
WFSJR 016 3.0
END DESCRIPTION:
XS GIS Cut Line= 3
      3725680.79     10226563.14      3725271.39     10226566.41
      3724924.03     10226698.95
#Sta/Elev= 30
  4555.1  367.99  4559.1  367.99    4568  366.21    4642  357.94    4708  351.98
    4818   339.7    4838  338.97    4858  336.97    4908  334.02  4917.9  332.85
  4922.9  333.27    4928  332.42    4958  331.76  4993.3  332.15  4998.6  328.47
  5002.2  328.47  5018.1  333.12  5023.4  333.02  5042.8   335.6  5096.7  338.41
    5103  339.35  5108.3  339.18  5127.7  340.89  5163.1  342.14  5187.8  344.05
  5212.6  344.96  5217.9  344.61  5277.5  347.42  5327.5  347.84  5336.3  348.47
#Mann= 5 ,-1 , 0
  4555.1     .11       0    4642     .17       0  4993.3     .09       0
  5018.1     .17       0  5277.5     .11       0
Bank Sta=4993.3,5018.1
XS Rating Curve= 0 ,0
Exp/Cntr=0.3,0.1

Type RM Length L Ch R = 1 ,933     ,427,427,427
BEGIN DESCRIPTION:
WFSJR 016 2.0
END DESCRIPTION:
XS GIS Cut Line= 3
      3725618.41     10226025.86      3725301.97     10226122.28
      3724958.34     10226268.13
#Sta/Elev= 30
  4586.6  356.14    4629  351.83  4649.9  350.41  4655.5  348.99  4681.3  348.29
  4693.6  347.32  4712.6  344.91  4726.4  344.22    4754  340.79  4759.3  340.95
  4792.1  337.56  4806.7  336.85  4857.8  332.51    4863  332.64  4869.4  331.68
  4916.9  328.65  4943.6  329.48  4974.5  329.04  4987.1  328.11  5001.5  325.11
  5001.8  324.61  5005.5  324.61  5009.1   326.5  5019.6  329.02  5056.4   331.4
  5095.7   335.8  5132.8  337.99  5139.1  339.52  5203.8     344  5290.7  348.45
#Mann= 3 , 0 , 0
  4586.6     .17       0  4974.5     .09       0  5019.6     .17       0
Bank Sta=4974.5,5019.6
XS Rating Curve= 0 ,0
Exp/Cntr=0.3,0.1

Type RM Length L Ch R = 1 ,506     ,102,102,102
BEGIN DESCRIPTION:
WFSJR 016 1.0
END DESCRIPTION:
XS GIS Cut Line= 3
      3725417.83     10225861.07      3725208.23     10225806.84
      3724917.86     10226211.06
#Sta/Elev= 30
  4783.5  344.54  4855.8  339.23  4882.5  336.28  4887.6  336.85  4923.1   332.6
  4928.2  333.01  4958.5   330.3  4963.7  330.64  4979.7  328.68  4990.1  325.87
  4995.8  322.15  5004.6  322.65  5010.3  325.41  5017.5  326.14  5039.7  324.26
  5045.9  325.91  5060.6  324.16  5066.8  325.94  5081.5  326.91  5140.4   327.9
  5146.6  327.34  5232.5   333.4  5247.2   333.7  5253.4  334.97    5262   334.9
    5289  337.95  5312.3  338.55  5368.8  343.91  5460.9  349.09  5497.7   350.3
#Mann= 3 , 0 , 0
  4783.5     .17       0  4990.1     .09       0  5017.5     .17       0
Bank Sta=4990.1,5017.5
XS Rating Curve= 0 ,0
Exp/Cntr=0.3,0.1

Type RM Length L Ch R = 1 ,404     ,199,199,199
XS GIS Cut Line= 4
      3725499.25     10225727.18      3725207.59     10225701.13
      3725034.41     10225784.47      3724870.35     10226111.29
#Sta/Elev= 30
       0  348.56    61.6  344.43    81.7  344.08     162  337.83   232.3   333.1
   272.5  331.27   329.3  326.83     352  321.89   359.1  322.94     369  326.06
   381.3  326.85   465.1  324.96   487.6  325.95   493.2   325.5   515.6   328.3
   532.3  328.48   537.9  329.83   554.6  329.28   593.1  332.04   599.3  333.04
   615.5  333.53     644  335.91     711  339.91   727.4  340.24   733.3  341.28
   772.1  343.04     778  344.16   805.9  344.77   822.7  346.32   850.7  347.32
#Mann= 3 , 0 , 0
       0     .17       0   329.3     .09       0   381.3     .17       0
Bank Sta=329.3,381.3
XS Rating Curve= 0 ,0
Exp/Cntr=0.3,0.1

Type RM Length L Ch R = 1 ,205     ,0,0,0
XS GIS Cut Line= 4
       3725536.8     10225624.96      3725087.14     10225590.24
      3724994.26      10225619.1      3724807.63     10226081.56
#Sta/Elev= 30
       0  345.67    79.2   343.4    89.2  342.22   169.4  337.54   299.8  331.87
     340   331.6   390.1  328.04   460.7  325.58   468.3   322.7   492.1   322.2
   500.9  320.78   506.1  320.82   538.6  324.56   583.4  325.17   655.9  324.69
   679.8  326.66   690.8  325.72   722.9  326.54   733.7  326.05   739.1  326.56
   755.3  325.45   768.6  325.87   787.4  328.66   900.1   335.8   924.3  338.39
   929.7  338.04   948.4  339.77   953.8  339.18  1031.6  344.91    1047  345.45
#Mann= 3 , 0 , 0
       0     .17       0   460.7     .09       0   583.4     .17       0
Bank Sta=460.7,583.4
XS Rating Curve= 0 ,0
Exp/Cntr=0.3,0.1

Chan Stop Cuts=-1
Use User Specified Reach Order=0
Composite Channel Slope=5