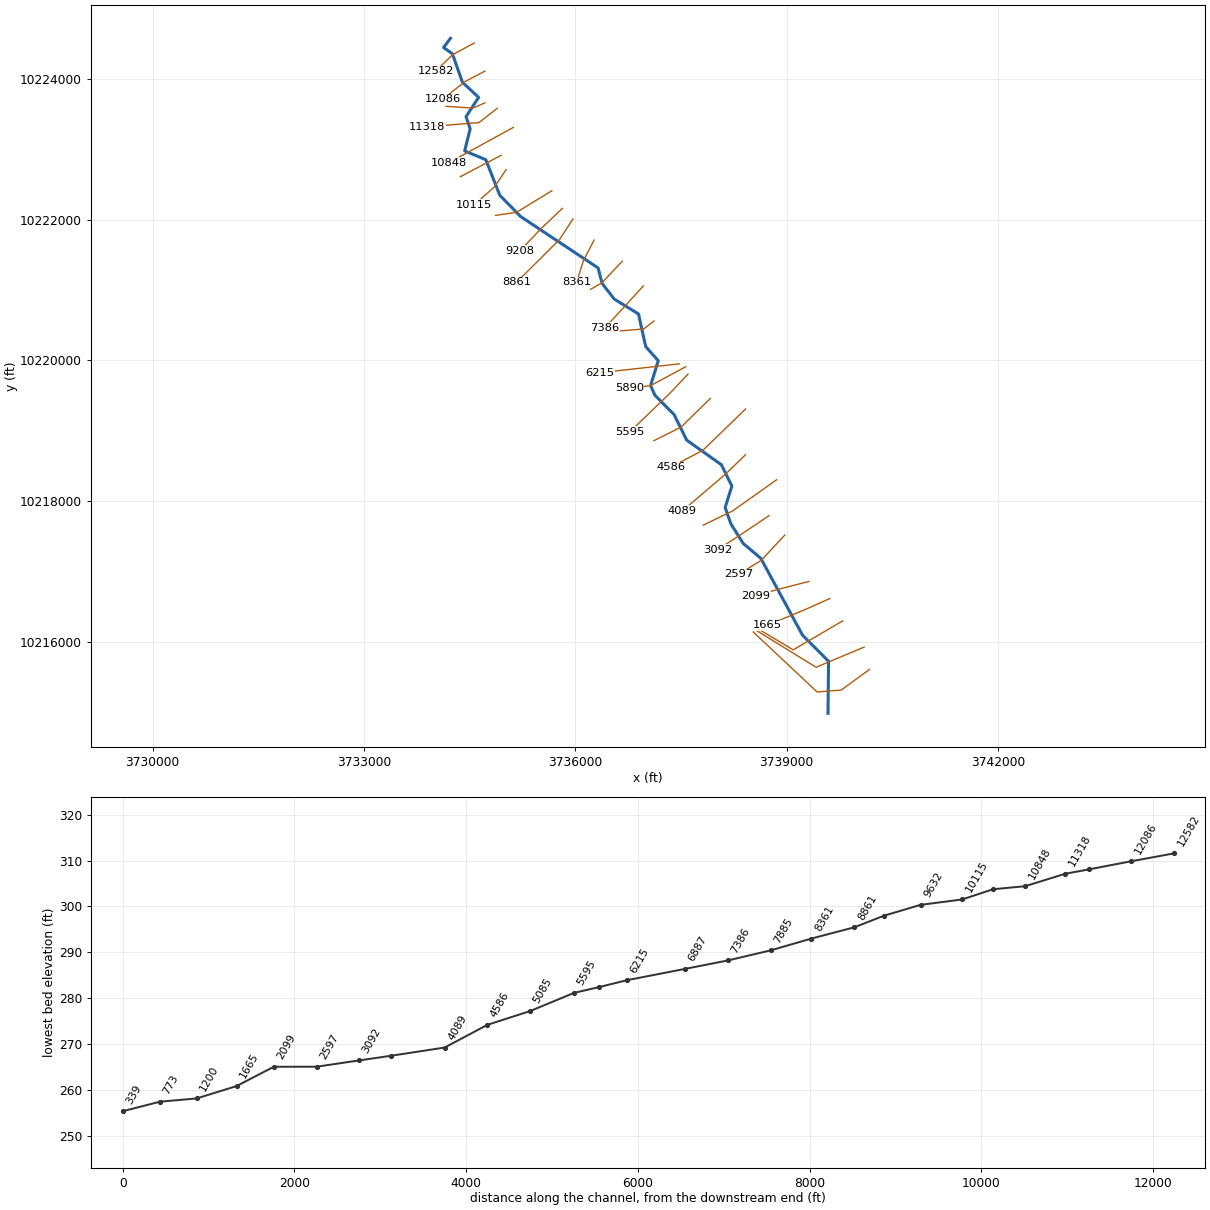
--- WFSJR 017.prj (project) ---

Proj Title=WFSJR 017 Base Level Engineering
Current Plan=p01
Default Exp/Contr=0.3,0.1
English Units
Geom File=g01
Flow File=f01
Flow File=f02
Plan File=p01
Y Axis Title=Elevation
X Axis Title(PF)=Main Channel Distance
X Axis Title(XS)=Station
BEGIN DESCRIPTION:
WFSJR 017
END DESCRIPTION:
DSS Export Rating Curves= 0
DSS Export Rating Curve Sorted= 0
DSS Export Volume Flow Curves= 0
DXF OffsetX= 0
DXF OffsetY= 0
DXF ScaleX= 1
DXF ScaleY= 10

--- WFSJR 017.p01 (plan) ---

Plan Title=Multiple Run
Program Version=4.10
Short Identifier=Multiple
Geom File=g01
Flow File=f01
Subcritical Flow
K Sum by GR= 0
Std Step Tol= 0.01
Critical Tol= 0.01
Num of Std Step Trials= 20
Max Error Tol= 0.3
Flow Tol Ratio= 0.001
Split Flow NTrial= 30
Split Flow Tol= 0.02
Split Flow Ratio= 0.02
Log Output Level= 0
Friction Slope Method= 1
Unsteady Friction Slope Method= 2
Unsteady Bridges Friction Slope Method= 1
Parabolic Critical Depth
Global Vel Dist= 1 , 1 , 1
Global Log Level= 0
CheckData=True
Encroach Param=-1 ,0,0, 0
BEGIN DESCRIPTION:
Multiple Run
END DESCRIPTION:
Computation Interval=1HOUR
Output Interval=1HOUR
Run HTab= 0
Run UNet= 0
Run PostProcess= 0
Run WQNet= 0
UNET Theta= 1
UNET Theta Warmup= 1
UNET ZTol= 0.02
UNET ZSATol= 0.05
UNET MxIter= 20
UNET MaxInSteps= 0
UNET DtIC= 0
UNET DtMin= 0
UNET MaxCRTS= 20
UNET WFStab= 2
UNET SFStab= 1
UNET WFX= 1
UNET SFX= 1
UNET DSS MLevel= 4
UNET DZMax Abort= 100
UNET Convert EG Bridges= 0
UNET Use Existing IB Tables=-1
UNET Froude Reduction=False
UNET Froude Limit= 1
UNET Froude Power= 10
UNET Time Slicing=0,0, 5
UNET Junction Losses=0
Instantaneous Interval=1HOUR
Write IC File= 0
Write IC File at Sim End=0
Echo Input=False
Echo Parameters=False
Echo Output=False
Write Detailed= 0
WQ AD Non Conservative
WQ ULTIMATE=-1
WQ Max Comp Step=1HOUR
WQ Output Interval=15MIN
WQ Output Selected Increments= 0
WQ Output face flow=0
WQ Output face velocity=0
WQ Output face area=0
WQ Output face dispersion=0
WQ Output cell volume=0
WQ Output cell surface area=0
WQ Output cell continuity=0
WQ Output cumulative cell continuity=0
WQ Output face conc=0
WQ Output face dconc_dx=0
WQ Output face courant=0
WQ Output face peclet=0
WQ Output face adv mass=0
WQ Output face disp mass=0
WQ Output cell mass=0
WQ Output cell source sink temp=0
WQ Output cell source sink nsm=0
WQ Output MaxMinRange=-1
WQ Daily Max Min Mean=-1
WQ Daily Range=0
WQ Daily Time=0
WQ Create Restart=0
WQ Fixed Restart=0
WQ System Summary=0
WQ Use Fixed Temperature=0
Sorting and Armoring Iterations= 10
XS Update Threshold= 0.02
Hydraulics Update Threshold= 0.02
Energy Slope Method= 1
Volume Change Method= 0
XS Weighting Method= 0
Number of US Weighted Cross Sections= 1
Number of DS Weighted Cross Sections= 1
Upstream XS Weight=0.25
Main XS Weight=0.5
Downstream XS Weight=0.25
Number of DS XS's Weighted with US Boundary= 1
Upstream Boundary Weight= 1
Weight of XSs Associated with US Boundary= 0
Number of US XS's Weighted with DS Boundary= 1
Downstream Boundary Weight= 0.5
Weight of XSs Associated with DS Boundary= 0.5
Sediment Output Level= 4
Mass or Volume Output= 0
Output Increment Type= 1
Profile and TS Output Increment= 10
XS Output Flag= 0
XS Output Increment= 10
Disregard all LS=0
Disregard all Conn=0
Disregard all Breaches=0
Disregard all Pumps=0

--- WFSJR 017.f01 (steady flow) ---

Flow Title=Multiple
Program Version=4.10
Number of Profiles= 7
Profile Names=10-year,25-year,50-year,1pct_min,100-year,1pct_plu,500-year
River Rch & RM=WFSJR 017,Reach-1         ,12582
    1123    1575    2177     988    2984    9012    5802
Boundary for River Rch & Prof#=WFSJR 017,Reach-1         , 1
Up Type= 0
Dn Type= 3
Dn Slope=0.005
Boundary for River Rch & Prof#=WFSJR 017,Reach-1         , 2
Up Type= 0
Dn Type= 3
Dn Slope=0.005
Boundary for River Rch & Prof#=WFSJR 017,Reach-1         , 3
Up Type= 0
Dn Type= 3
Dn Slope=0.005
Boundary for River Rch & Prof#=WFSJR 017,Reach-1         , 4
Up Type= 0
Dn Type= 3
Dn Slope=0.005
Boundary for River Rch & Prof#=WFSJR 017,Reach-1         , 5
Up Type= 0
Dn Type= 3
Dn Slope=0.005
Boundary for River Rch & Prof#=WFSJR 017,Reach-1         , 6
Up Type= 0
Dn Type= 3
Dn Slope=0.005
Boundary for River Rch & Prof#=WFSJR 017,Reach-1         , 7
Up Type= 0
Dn Type= 3
Dn Slope=0.005
DSS Import GetInterval= 0
DSS Import GetPeak= 0
DSS Import FillOption= 0

--- WFSJR 017.f02 (steady flow) ---

Flow Title=Orig_BLE_Flow
Program Version=4.10
Number of Profiles= 7
Profile Names=10-year,25-year,50-year,1pct_min,100-year,1pct_plu,500-year
River Rch & RM=WFSJR 017,Reach-1         ,12582
    1123    1544    1893     760    2295    6930    3373
Boundary for River Rch & Prof#=WFSJR 017,Reach-1         , 1
Up Type= 0
Dn Type= 3
Dn Slope=0.005
Boundary for River Rch & Prof#=WFSJR 017,Reach-1         , 2
Up Type= 0
Dn Type= 3
Dn Slope=0.005
Boundary for River Rch & Prof#=WFSJR 017,Reach-1         , 3
Up Type= 0
Dn Type= 3
Dn Slope=0.005
Boundary for River Rch & Prof#=WFSJR 017,Reach-1         , 4
Up Type= 0
Dn Type= 3
Dn Slope=0.005
Boundary for River Rch & Prof#=WFSJR 017,Reach-1         , 5
Up Type= 0
Dn Type= 3
Dn Slope=0.005
Boundary for River Rch & Prof#=WFSJR 017,Reach-1         , 6
Up Type= 0
Dn Type= 3
Dn Slope=0.005
Boundary for River Rch & Prof#=WFSJR 017,Reach-1         , 7
Up Type= 0
Dn Type= 3
Dn Slope=0.005
DSS Import GetInterval= 0
DSS Import GetPeak= 0
DSS Import FillOption= 0

--- WFSJR 017.g01 (geometry) ---

Geom Title=Existing Conditions
Program Version=4.10

River Reach=WFSJR 017       ,Reach-1
Reach XY= 30
      3734228.23     10224576.84      3734130.35     10224446.84
      3734255.41     10224357.62      3734398.34      10223952.7
      3734628.04     10223737.96      3734449.11     10223463.42
      3734508.41     10223290.86      3734429.89     10222977.55
      3734730.03     10222852.33       3734928.6     10222347.55
      3735222.68     10222045.89      3736324.43     10221314.98
      3736380.89     10221096.04      3736552.86     10220873.39
      3736897.92     10220660.88       3737000.3     10220197.69
      3737178.23     10219996.84      3737069.51     10219643.49
      3737131.33     10219505.24      3737403.84     10219230.71
      3737581.64      10218869.3      3738074.63     10218519.19
      3738223.63     10218217.38      3738127.95     10217911.13
      3738210.92     10217676.05      3738384.57     10217400.71
      3738634.05     10217189.99      3739225.72     10216099.79
      3739595.92     10215726.79      3739588.23     10214986.84

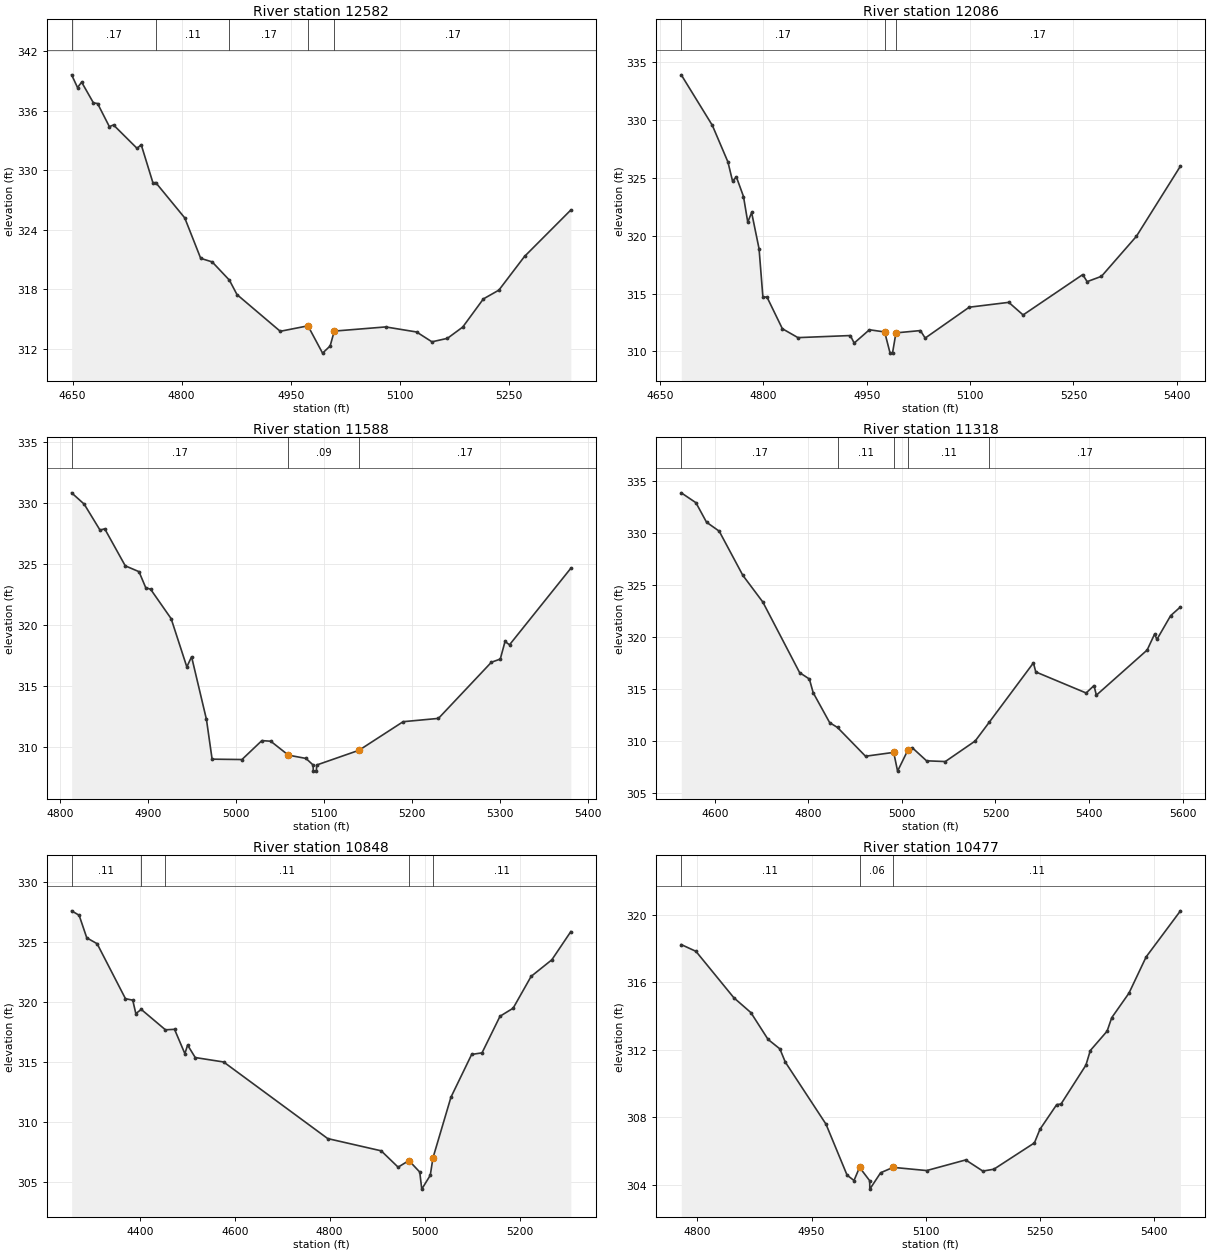
Type RM Length L Ch R = 1 ,12582   ,496,496,496
BEGIN DESCRIPTION:
WFSJR 017 25.0
END DESCRIPTION:
XS GIS Cut Line= 3
      3734567.89     10224511.09      3734258.84     10224344.05
      3734017.85     10224111.07
#Sta/Elev= 30
  4648.7   339.6  4656.8  338.32  4662.5  338.86  4678.7  336.77  4684.4  336.71
  4700.6  334.38  4706.3  334.55  4738.7  332.19  4744.4  332.56  4760.6   328.7
  4764.3  328.75  4804.3  325.18  4826.2  321.11    4842  320.75  4865.7  318.91
  4876.1  317.46  4935.6  313.76  4973.7  314.31  4993.8  311.56  5004.2  312.28
  5009.9  313.78  5080.6   314.2  5123.1  313.69  5144.2   312.7  5165.5  313.05
  5186.6  314.19  5214.9  317.02  5236.3  317.91  5271.5   321.3  5335.2  325.98
#Mann= 5 ,-1 , 0
  4648.7     .17       0  4764.3     .11       0  4865.7     .17       0
  4973.7     .09       0  5009.9     .17       0
Bank Sta=4973.7,5009.9
XS Rating Curve= 0 ,0
Exp/Cntr=0.3,0.1

Type RM Length L Ch R = 1 ,12086   ,498,498,498
BEGIN DESCRIPTION:
WFSJR 017 24.0
END DESCRIPTION:
XS GIS Cut Line= 3
      3734717.84     10224111.06      3734435.14     10223963.05
      3734117.83     10223711.06
#Sta/Elev= 30
  4680.9  333.91    4726  329.54  4748.6  326.38  4755.3  324.73  4760.9  325.08
  4771.2  323.39  4777.4  321.17    4783  322.01  4793.8  318.87  4799.4  314.66
  4805.1  314.72  4827.6  311.96  4850.2  311.19  4926.2  311.37  4931.8  310.72
  4953.9  311.87    4976  311.68  4983.9  309.85  4987.4  309.85  4992.4   311.6
  5027.9   311.8  5034.8  311.15  5098.7  313.82  5156.1  314.24  5176.9  313.15
  5263.4  316.64  5269.8  316.03  5290.6  316.49  5341.3  319.95  5405.2  326.02
#Mann= 3 , 0 , 0
  4680.9     .17       0    4976     .09       0  4992.4     .17       0
Bank Sta=4976,4992.4
XS Rating Curve= 0 ,0
Exp/Cntr=0.3,0.1

Type RM Length L Ch R = 1 ,11588   ,270,270,270
BEGIN DESCRIPTION:
WFSJR 017 23.0
END DESCRIPTION:
XS GIS Cut Line= 3
      3734717.83     10223661.06      3734547.12     10223585.45
      3734167.88     10223611.07
#Sta/Elev= 30
  4813.3  330.86  4827.6  329.93  4845.5  327.81  4850.9  327.91  4874.2  324.88
  4889.8   324.4  4897.5  323.08    4903  322.96  4926.3  320.55  4944.1   316.6
  4949.5  317.43  4966.4  312.29  4972.8  309.04  5006.7  309.01  5029.3  310.56
  5039.4  310.51  5059.4  309.37  5079.4   309.1  5087.5  308.56  5087.7  308.06
  5091.2  308.06  5091.5  308.56  5139.6  309.77  5189.7  312.11  5229.8  312.38
  5289.9  316.98    5300  317.24  5305.4  318.68  5310.5  318.41  5380.1  324.68
#Mann= 3 , 0 , 0
  4813.3     .17       0  5059.4     .09       0  5139.6     .17       0
Bank Sta=5059.4,5139.6
XS Rating Curve= 0 ,0
Exp/Cntr=0.3,0.1

Type RM Length L Ch R = 1 ,11318   ,470,470,470
BEGIN DESCRIPTION:
WFSJR 017 22.0
END DESCRIPTION:
XS GIS Cut Line= 3
      3734891.61     10223582.24      3734631.21     10223379.13
      3733896.88     10223321.84
#Sta/Elev= 30
  4528.5  333.84  4559.9  332.89  4582.5  331.02  4609.6  330.16  4660.1  325.92
  4702.8  323.36  4781.5  316.58  4802.3  315.97  4810.4  314.66  4845.7  311.78
  4862.4  311.32  4922.3  308.56  4982.5  308.93  4990.8  307.13  5012.6  309.13
  5022.1  309.38  5052.7  308.12  5092.8  308.05  5156.6  310.02  5186.8  311.83
  5281.1  317.52  5286.1  316.65  5393.7  314.63  5410.5  315.34  5415.6  314.42
  5524.1  318.75    5540  320.28    5545  319.77  5574.3  322.05  5595.3  322.89
#Mann= 5 ,-1 , 0
  4528.5     .17       0  4862.4     .11       0  4982.5     .06       0
  5012.6     .11       0  5186.8     .17       0
Bank Sta=4982.5,5012.6
XS Rating Curve= 0 ,0
Exp/Cntr=0.3,0.1

Type RM Length L Ch R = 1 ,10848   ,371,371,371
BEGIN DESCRIPTION:
Mapping XS 44c5fa61
END DESCRIPTION:
XS GIS Cut Line= 2
      3735120.76      10223311.4      3734198.91     10222806.21
#Sta/Elev= 30
  4256.6  327.58  4272.4  327.21  4288.5  325.33  4310.3  324.84    4370  320.26
  4385.3  320.14  4391.8  319.02  4403.2  319.37  4454.1  317.67  4473.3  317.71
  4495.1  315.68  4500.8   316.4  4516.9  315.36  4576.7  314.99  4795.9  308.61
  4908.5  307.59  4944.1  306.23  4966.9  306.78  4989.7  305.82  4993.9   304.4
  5011.8  305.55  5017.5     307  5055.4  312.06    5099  315.62  5120.8  315.75
  5158.7   318.8  5186.3  319.47  5224.2  322.12  5267.8   323.5  5307.8  325.85
#Mann= 5 ,-1 , 0
  4256.6     .11       0  4403.2     .17       0  4454.1     .11       0
  4966.9     .06       0  5017.5     .11       0
Bank Sta=4966.9,5017.5
XS Rating Curve= 0 ,0
Exp/Cntr=0.3,0.1

Type RM Length L Ch R = 1 ,10477   ,362,362,362
BEGIN DESCRIPTION:
WFSJR 017 21.0
END DESCRIPTION:
XS GIS Cut Line= 2
      3734948.91     10222915.58      3734367.86     10222611.08
#Sta/Elev= 30
  4778.8  318.24  4798.1  317.84  4847.9  315.09  4870.3  314.21  4892.9  312.62
  4908.4  312.06  4915.5  311.28    4969   307.6  4996.7  304.58  5005.8  304.26
  5013.1  305.04  5026.4  304.25  5026.6  303.75  5040.8  304.72  5057.2  305.04
  5101.3  304.85  5152.6  305.48  5175.1  304.82  5189.6  304.93  5242.9  306.49
  5250.1  307.29  5272.2  308.76  5277.8  308.79  5310.6   311.1  5316.3  311.96
  5338.4  313.11  5344.5  313.91  5367.1  315.36  5389.7  317.51  5434.8  320.24
#Mann= 3 , 0 , 0
  4778.8     .11       0  5013.1     .06       0  5057.2     .11       0
Bank Sta=5013.1,5057.2
XS Rating Curve= 0 ,0
Exp/Cntr=0.3,0.1

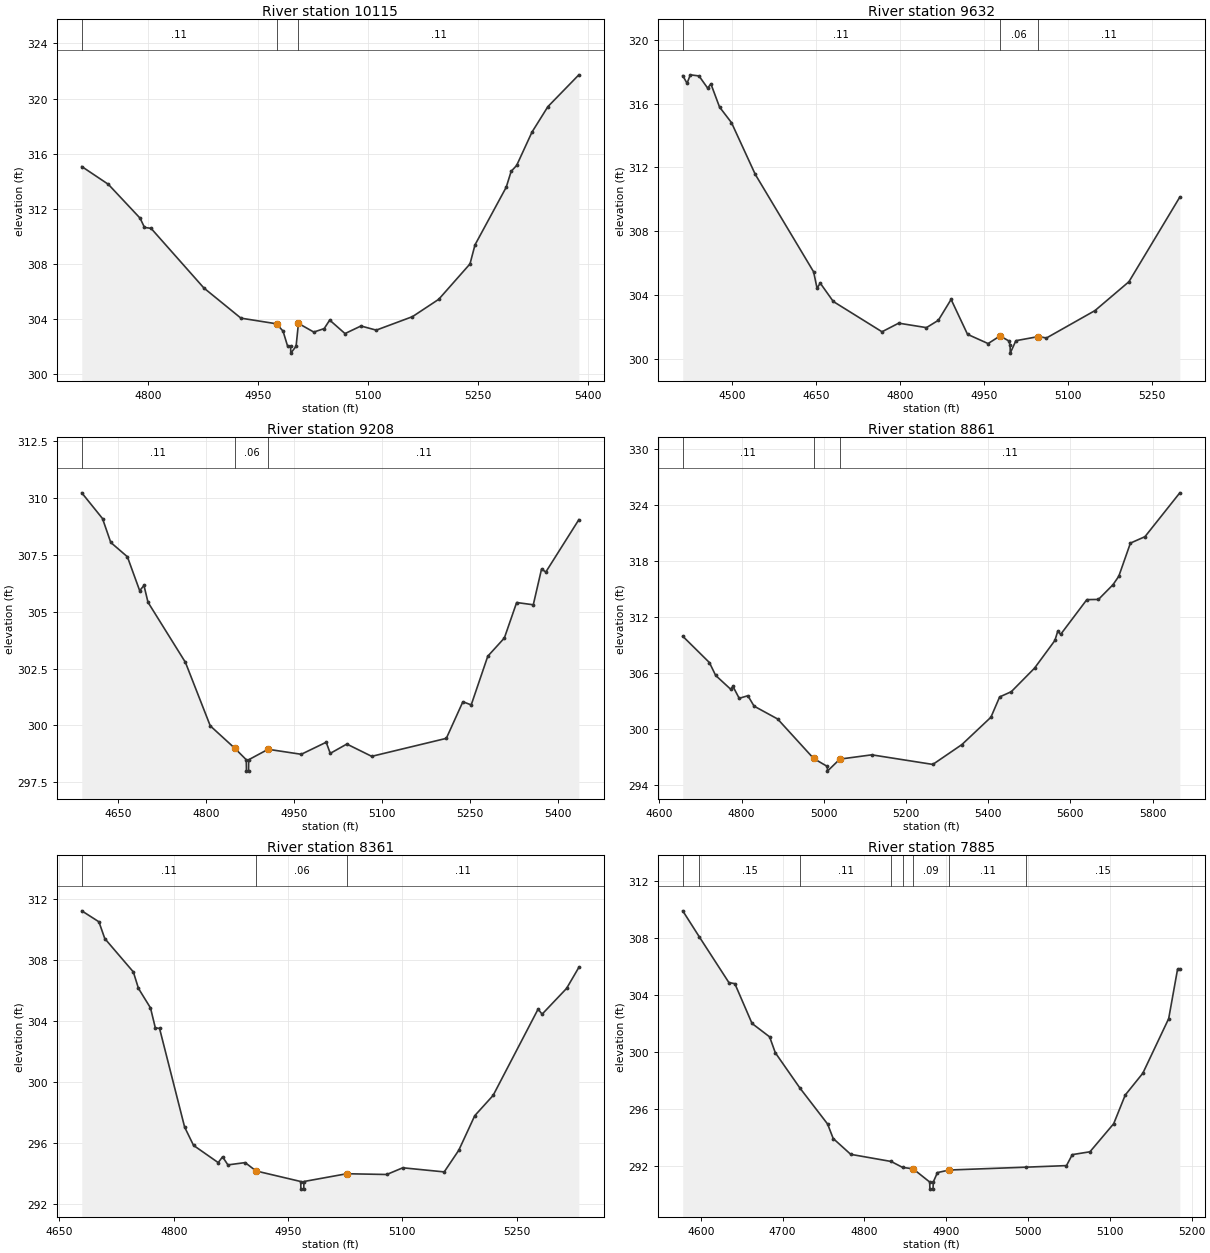
Type RM Length L Ch R = 1 ,10115   ,483,483,483
BEGIN DESCRIPTION:
WFSJR 017 20.0
END DESCRIPTION:
XS GIS Cut Line= 3
      3735017.87     10222711.09      3734855.84     10222470.33
      3734567.85     10222211.07
#Sta/Elev= 30
  4709.8  315.06    4746  313.77  4789.3  311.31  4795.3  310.64  4804.3  310.57
  4876.3  306.24  4926.8  304.05  4975.3  303.64  4984.2  303.11  4990.3  302.04
  4994.5  302.01  4994.8  301.51    5002  302.01  5005.2  303.67  5026.1  303.04
  5040.3  303.29  5047.8  303.91  5068.7  302.93  5090.4  303.48  5111.3  303.18
  5160.7  304.16  5196.5  305.42  5239.1  307.99  5245.9  309.37  5288.5  313.56
  5295.2  314.71  5302.7  315.14  5323.6  317.56  5345.3  319.41  5387.5  321.72
#Mann= 3 , 0 , 0
  4709.8     .11       0  4975.3     .06       0  5005.2     .11       0
Bank Sta=4975.3,5005.2
XS Rating Curve= 0 ,0
Exp/Cntr=0.3,0.1

Type RM Length L Ch R = 1 ,9632    ,424,424,424
BEGIN DESCRIPTION:
WFSJR 017 19.0
END DESCRIPTION:
XS GIS Cut Line= 3
      3735667.85     10222411.07      3735165.08     10222105.01
      3734867.81     10222061.07
#Sta/Elev= 30
  4411.4  317.75  4419.1  317.27    4425   317.8  4440.5  317.73  4455.9  316.97
  4461.8  317.23  4477.2  315.78  4498.6   314.8  4541.2  311.55  4645.5  305.44
  4651.6  304.42  4657.4  304.73  4680.7  303.58  4767.8  301.68  4797.7  302.22
  4847.3  301.94  4868.6   302.4  4891.4  303.71  4920.8  301.52  4957.6  300.94
    4979  301.42  4994.4  301.11    4997  300.84  4997.2  300.34  5007.3  301.12
  5047.7  301.38    5062  301.29  5148.8  303.01  5209.5  304.82  5300.5  310.13
#Mann= 3 , 0 , 0
  4411.4     .11       0    4979     .06       0  5047.7     .11       0
#XS Ineff= 1 ,-1
    4670  4891.4  303.71
Permanent Ineff=
       F
Bank Sta=4979,5047.7
XS Rating Curve= 0 ,0
Exp/Cntr=0.3,0.1

Type RM Length L Ch R = 1 ,9208    ,347,347,347
BEGIN DESCRIPTION:
WFSJR 017 18.0
END DESCRIPTION:
XS GIS Cut Line= 3
      3735817.84     10222161.06      3735518.27     10221877.63
      3735217.87     10221561.09
#Sta/Elev= 30
  4587.6  310.22    4623  309.09  4637.1  308.04  4665.5  307.41  4686.5  305.92
  4693.8  306.15  4700.7  305.41  4764.6  302.77    4807  299.98  4849.1  298.99
  4868.5  298.49  4868.8  297.99  4872.4  297.99  4872.6  298.49  4905.8  298.95
  4962.4  298.73    5005  299.26  5011.9  298.77  5040.2  299.18  5082.7  298.64
  5210.1  299.43  5238.4  301.04  5252.6   300.9  5280.9  303.04  5309.2  303.84
  5330.2   305.4  5358.6   305.3  5372.7  306.87    5380  306.74  5436.4  309.04
#Mann= 3 , 0 , 0
  4587.6     .11       0  4849.1     .06       0  4905.8     .11       0
Bank Sta=4849.1,4905.8
XS Rating Curve= 0 ,0
Exp/Cntr=0.3,0.1

Type RM Length L Ch R = 1 ,8861    ,500,500,500
BEGIN DESCRIPTION:
WFSJR 017 17.0
END DESCRIPTION:
XS GIS Cut Line= 3
      3735967.88     10222011.11      3735780.54     10221723.43
      3735167.88      10221111.1
#Sta/Elev= 30
  4656.7  309.94  4721.6  307.11  4736.8  305.73    4773  304.26    4779  304.54
  4794.1  303.27  4815.2  303.55  4830.3  302.43  4887.6  301.05  4975.2  296.81
  5008.6  295.95  5008.8  295.45  5038.9  296.74  5116.7   297.2  5265.2  296.17
  5335.9   298.3  5406.6  301.24  5427.8  303.42  5456.1  303.98  5512.7  306.51
  5562.2  309.48  5569.3  310.49  5576.3  310.14    5640  313.87  5668.2  313.89
  5703.6  315.47  5717.7  316.38    5746  319.94  5781.4  320.63  5866.2  325.34
#Mann= 3 , 0 , 0
  4656.7     .11       0  4975.2     .06       0  5038.9     .11       0
Bank Sta=4975.2,5038.9
XS Rating Curve= 0 ,0
Exp/Cntr=0.3,0.1

Type RM Length L Ch R = 1 ,8361    ,476,476,476
BEGIN DESCRIPTION:
WFSJR 017 16.0
END DESCRIPTION:
XS GIS Cut Line= 3
      3736267.83     10221711.04      3736119.17     10221426.88
      3736017.84     10221111.03
#Sta/Elev= 30
  4679.3  311.25  4701.8  310.53  4709.5  309.43    4747  307.24  4753.7  306.16
  4769.5  304.88  4775.8  303.58  4781.4  303.53  4814.3  297.06    4826  295.86
  4858.4  294.73  4864.1  295.11  4871.1  294.58  4893.7  294.73  4908.2  294.18
  4966.7  293.49  4966.9  292.99  4970.6  292.99  4970.9  293.49  5027.1     294
  5079.6  293.95  5100.6  294.39    5155  294.12  5174.1  295.54  5195.1  297.81
  5219.2  299.14  5278.2   304.8  5283.5  304.47  5315.6  306.16  5331.7  307.54
#Mann= 3 , 0 , 0
  4679.3     .11       0  4908.2     .06       0  5027.1     .11       0
Bank Sta=4908.2,5027.1
XS Rating Curve= 0 ,0
Exp/Cntr=0.3,0.1

Type RM Length L Ch R = 1 ,7885    ,499,499,499
BEGIN DESCRIPTION:
WFSJR 017 15.0
END DESCRIPTION:
XS GIS Cut Line= 3
      3736667.84     10221411.06      3736378.54     10221103.83
      3736217.89     10221011.09
#Sta/Elev= 30
    4578  309.93  4598.2  308.11  4634.4   304.9  4641.7  304.82  4662.7  302.03
  4684.2  301.09  4691.1  299.98  4721.1  297.51    4755  294.98  4761.9  293.96
  4783.3  292.85  4832.7  292.35  4846.8  291.93  4859.4  291.84  4879.8  290.91
  4880.1  290.41  4883.9  290.41  4884.2  290.91  4889.3  291.57  4903.5  291.75
  4997.7  291.95    5047  292.06  5054.1  292.83  5075.7  293.03  5104.7     295
  5118.8  297.01  5140.3  298.54  5171.9  302.37  5182.7  305.82  5185.5  305.82
#Mann= 8 ,-1 , 0
    4578     .11       0  4598.2     .15       0  4721.1     .11       0
  4832.7     .15       0  4846.8     .11       0  4859.4     .09       0
  4903.5     .11       0  4997.7     .15       0
Bank Sta=4859.4,4903.5
XS Rating Curve= 0 ,0
Exp/Cntr=0.3,0.1

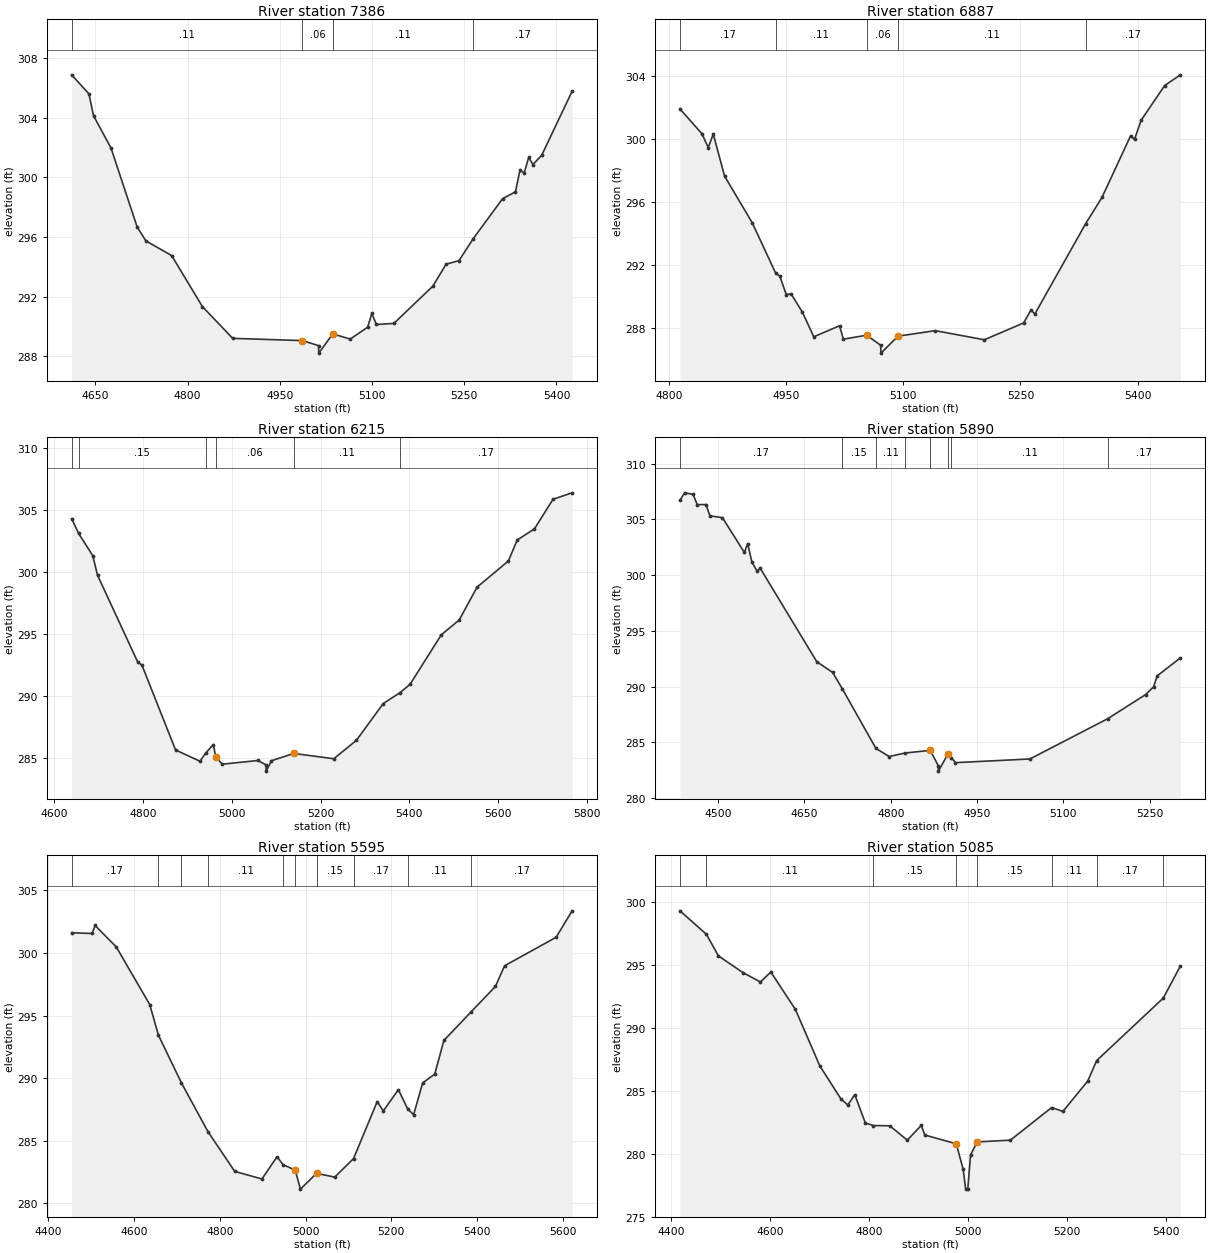
Type RM Length L Ch R = 1 ,7386    ,499,499,499
BEGIN DESCRIPTION:
WFSJR 017 14.0
END DESCRIPTION:
XS GIS Cut Line= 3
      3736967.87      10221061.1      3736706.73     10220773.46
      3736417.84     10220461.06
#Sta/Elev= 30
  4611.5  306.86  4639.6  305.58    4647  304.12  4675.4  301.96    4718  296.66
  4732.2  295.73  4774.1  294.75  4824.1  291.33  4873.4   289.2  4986.9  289.05
  5013.1  288.71  5013.4  288.21  5036.2   289.5  5064.6  289.15  5092.9  289.95
  5099.7  290.87  5107.1  290.13  5135.5   290.2    5199   292.7  5220.5  294.17
  5241.5  294.41  5264.8  295.89  5312.4  298.56  5333.3  299.02  5340.7  300.46
  5347.5  300.28  5354.9  301.33  5361.7  300.85  5375.9  301.46  5425.5  305.76
#Mann= 4 ,-1 , 0
  4611.5     .11       0  4986.9     .06       0  5036.2     .11       0
  5264.8     .17       0
Bank Sta=4986.9,5036.2
XS Rating Curve= 0 ,0
Exp/Cntr=0.3,0.1

Type RM Length L Ch R = 1 ,6887    ,672,672,672
BEGIN DESCRIPTION:
WFSJR 017 13.0
END DESCRIPTION:
XS GIS Cut Line= 3
      3737117.85     10220561.07      3736970.99     10220447.59
      3736517.85     10220411.07
#Sta/Elev= 30
  4814.4  301.91  4842.5  300.33  4850.6  299.45    4857  300.31  4871.5  297.63
  4906.8  294.67    4937  291.44  4942.1  291.28  4950.3   290.1  4956.6  290.14
  4971.1  288.97  4985.6  287.41  5018.5  288.11  5023.5  287.26  5053.3  287.51
  5071.1  286.87  5071.5  286.37  5093.4  287.45    5141   287.8  5203.8  287.22
    5254  288.29  5263.4  289.11  5268.4  288.86  5333.3   294.6  5354.3  296.28
  5390.9   300.2  5395.9  299.97  5404.4  301.19  5434.5   303.4  5454.6  304.08
#Mann= 5 ,-1 , 0
  4814.4     .17       0    4937     .11       0  5053.3     .06       0
  5093.4     .11       0  5333.3     .17       0
Bank Sta=5053.3,5093.4
XS Rating Curve= 0 ,0
Exp/Cntr=0.3,0.1

Type RM Length L Ch R = 1 ,6215    ,325,325,325
BEGIN DESCRIPTION:
WFSJR 017 12.0
END DESCRIPTION:
XS GIS Cut Line= 2
      3737474.99     10219952.05      3736355.15     10219827.04
#Sta/Elev= 30
  4639.7  304.32  4655.2  303.13  4687.1  301.34  4697.9  299.75  4788.2  292.75
  4797.8  292.49  4873.6  285.63  4928.6  284.72  4941.2  285.37  4958.8  286.07
  4963.9  285.07  4978.9  284.48  5059.4  284.78  5077.2  284.42  5077.6  283.92
  5089.6  284.76  5139.6  285.35  5229.9  284.92  5280.8  286.41  5341.2  289.38
  5378.1  290.24  5401.5  290.93    5472  294.94  5512.2  296.13  5552.5  298.79
  5622.9   300.9    5643   302.6  5681.7   303.5  5723.5  305.89  5766.5  306.41
#Mann= 6 ,-1 , 0
  4639.7     .17       0  4655.2     .15       0  4941.2     .11       0
  4963.9     .06       0  5139.6     .11       0  5378.1     .17       0
Bank Sta=4963.9,5139.6
XS Rating Curve= 0 ,0
Exp/Cntr=0.3,0.1

Type RM Length L Ch R = 1 ,5890    ,295,295,295
BEGIN DESCRIPTION:
WFSJR 017 11.0
END DESCRIPTION:
XS GIS Cut Line= 3
      3737567.85     10219911.07      3737069.43     10219642.64
      3736767.88     10219611.07
#Sta/Elev= 30
  4433.9  306.72    4442  307.38  4456.6  307.25  4463.9  306.32  4479.3  306.33
  4485.8  305.32  4507.7  305.15  4545.8  302.03  4551.5  302.83  4558.8  301.18
  4567.7  300.37  4573.4  300.61  4671.6  292.23  4699.2  291.27  4715.6  289.83
  4774.3  284.46  4797.3  283.73  4825.5  284.05  4868.7  284.28  4882.5  282.92
  4882.9  282.42  4899.6  283.98  4905.2  283.63  4912.5  283.18  5041.8  283.51
  5176.9  287.12  5242.9  289.29  5256.6  289.98    5263  290.97  5303.2  292.58
#Mann= 8 ,-1 , 0
  4433.9     .17       0  4715.6     .15       0  4774.3     .11       0
  4825.5     .15       0  4868.7     .06       0  4899.6     .15       0
  4905.2     .11       0  5176.9     .17       0
Bank Sta=4868.7,4899.6
XS Rating Curve= 0 ,0
Exp/Cntr=0.3,0.1

Type RM Length L Ch R = 1 ,5595    ,510,510,510
BEGIN DESCRIPTION:
WFSJR 017 10.0
END DESCRIPTION:
XS GIS Cut Line= 3
      3737599.93     10219806.17      3737349.96     10219540.59
      3736772.35     10218983.79
#Sta/Elev= 30
  4454.6  301.61  4502.3  301.55  4509.2  302.19  4558.5  300.48  4636.6  295.88
  4656.9  293.43  4710.4  289.63  4772.4  285.73  4834.7  282.56  4898.3  281.95
  4933.5  283.73  4947.6  283.09  4975.9  282.66    4988  281.14  5025.6   282.4
    5068   282.1  5111.9  283.58  5167.1  288.13  5181.2  287.38  5216.5  289.08
  5238.2  287.54    5252  287.08  5273.1  289.62  5301.4  290.33  5322.5  293.01
  5385.7  295.28  5442.9  297.33    5464  298.97  5584.4  301.25  5621.6  303.36
#Mann= 10 ,-1 , 0
  4454.6     .17       0  4656.9     .11       0  4710.4     .17       0
  4772.4     .11       0  4947.6     .15       0  4975.9     .09       0
  5025.6     .15       0  5111.9     .17       0  5238.2     .11       0
  5385.7     .17       0
Bank Sta=4975.9,5025.6
XS Rating Curve= 0 ,0
Exp/Cntr=0.3,0.1

Type RM Length L Ch R = 1 ,5085    ,499,499,499
BEGIN DESCRIPTION:
WFSJR 017 9.0
END DESCRIPTION:
XS GIS Cut Line= 3
      3737917.85     10219461.07      3737501.79     10219053.11
      3737117.84     10218861.07
#Sta/Elev= 30
  4417.3  299.28  4470.7  297.42  4495.1   295.7  4544.5  294.38    4580  293.63
  4601.1  294.42  4650.7  291.45  4700.1  286.97  4742.5  284.36  4756.7  283.87
  4770.8  284.68  4792.1  282.44  4808.2  282.23  4841.6  282.21    4877  281.07
  4905.3  282.24  4912.3  281.48    4976  280.78  4990.1  278.75    4995  277.18
  4999.3  277.18    5005  279.91  5018.5  280.93  5085.5  281.07    5169  283.66
  5191.7  283.35    5242  285.77    5260  287.39  5394.7  292.35  5429.3   294.9
#Mann= 8 ,-1 , 0
  4417.3     .17       0  4470.7     .11       0  4808.2     .15       0
    4976     .09       0  5018.5     .15       0    5169     .11       0
    5260     .17       0  5394.7     .15       0
Bank Sta=4976,5018.5
XS Rating Curve= 0 ,0
Exp/Cntr=0.3,0.1

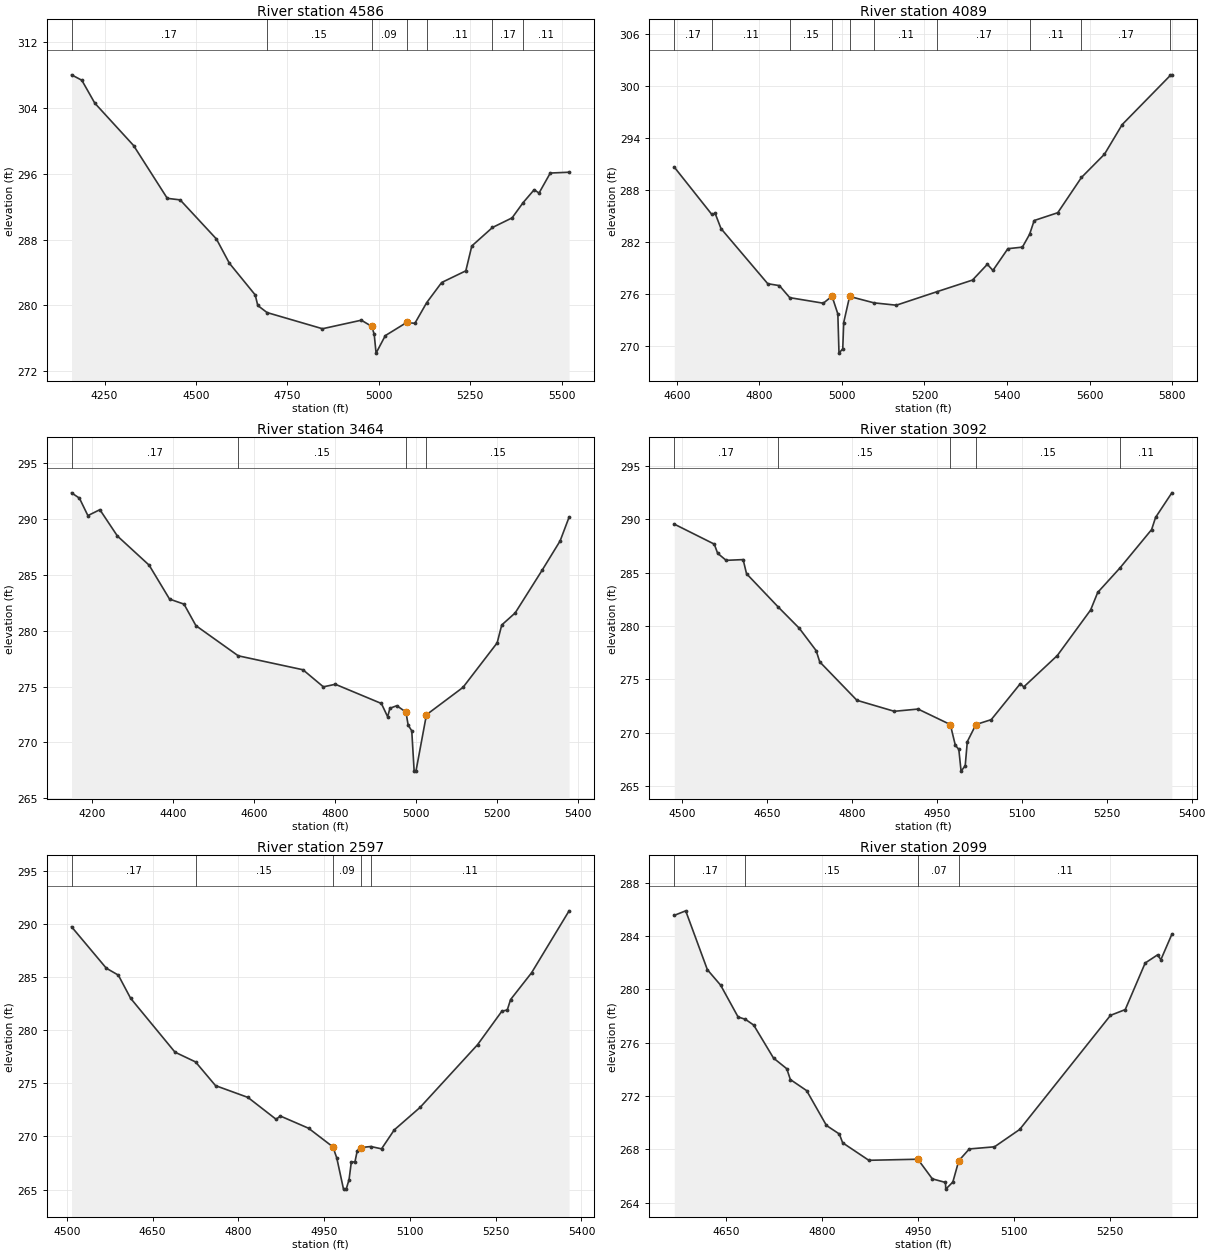
Type RM Length L Ch R = 1 ,4586    ,497,497,497
BEGIN DESCRIPTION:
WFSJR 017 8.0
END DESCRIPTION:
XS GIS Cut Line= 3
      3738417.82     10219311.04      3737814.89     10218726.03
      3737355.14     10218483.28
#Sta/Elev= 30
  4159.9  308.06    4188   307.4  4223.5  304.61  4329.5  299.45  4421.6  293.02
  4456.8  292.83  4555.9  288.07  4591.3  285.12  4661.9  281.26    4669  279.97
  4694.3  279.11  4845.8  277.14    4952  278.18  4980.3  277.43  4987.2  276.48
  4992.3  274.17  5017.5   276.3  5075.8   277.9  5098.4   277.8  5130.7  280.32
  5171.6  282.77  5237.6  284.19    5254  287.22  5310.5  289.47  5364.1  290.64
  5394.3   292.5  5424.5  294.07  5437.7  293.66  5468.5   296.1  5519.9   296.2
#Mann= 7 ,-1 , 0
  4159.9     .17       0  4694.3     .15       0  4980.3     .09       0
  5075.8     .15       0  5130.7     .11       0  5310.5     .17       0
  5394.3     .11       0
Bank Sta=4980.3,5075.8
XS Rating Curve= 0 ,0
Exp/Cntr=0.3,0.1

Type RM Length L Ch R = 1 ,4089    ,625,625,625
BEGIN DESCRIPTION:
WFSJR 017 7.0
END DESCRIPTION:
XS GIS Cut Line= 3
      3738417.85     10218661.07      3738125.99     10218379.13
      3737517.84     10217861.06
#Sta/Elev= 30
  4594.2  290.68  4685.1  285.22  4693.1  285.35  4707.3  283.59  4820.5  277.23
  4848.7  277.01  4873.8  275.62    4955  274.98  4976.1  275.79  4990.2  273.74
    4993  269.22  5002.1  269.72  5004.4  272.75  5018.7  275.76  5077.8  275.02
  5131.8  274.75    5231  276.32  5316.3  277.65  5352.2  279.47  5365.7  278.76
  5401.9  281.27  5437.1  281.45  5454.5  282.93  5465.6  284.52  5522.7  285.42
  5580.1  289.49  5635.8  292.17  5678.7  295.59  5795.2  301.26  5798.9  301.33
#Mann= 10 ,-1 , 0
  4594.2     .17       0  4685.1     .11       0  4873.8     .15       0
  4976.1     .09       0  5018.7     .15       0  5077.8     .11       0
    5231     .17       0  5454.5     .11       0  5580.1     .17       0
  5795.2     .11       0
Bank Sta=4976.1,5018.7
XS Rating Curve= 0 ,0
Exp/Cntr=0.3,0.1

Type RM Length L Ch R = 1 ,3464    ,372,372,372
BEGIN DESCRIPTION:
WFSJR 017 6.0
END DESCRIPTION:
XS GIS Cut Line= 3
       3738860.4     10218306.22      3738235.38      10217863.5
      3737817.89     10217661.09
#Sta/Elev= 30
    4149  292.36  4168.5  291.88  4189.4  290.32    4219  290.85  4262.4  288.49
  4340.8  285.88  4391.3  282.84    4427  282.39  4456.5  280.46  4561.1  277.76
  4721.1  276.51  4771.5  274.98  4801.1  275.21  4914.9  273.49  4930.4   272.3
    4936  273.06    4953  273.29  4975.6  272.72  4981.1  271.55    4990  271.04
  4995.9  267.43  5000.4  267.43  5026.3  272.48  5116.6  274.93  5201.1  278.92
  5212.4  280.52  5245.6   281.6  5312.3  285.43  5356.7  288.05  5378.9  290.18
#Mann= 4 ,-1 , 0
    4149     .17       0  4561.1     .15       0  4975.6     .09       0
  5026.3     .15       0
Bank Sta=4975.6,5026.3
XS Rating Curve= 0 ,0
Exp/Cntr=0.3,0.1

Type RM Length L Ch R = 1 ,3092    ,495,495,495
BEGIN DESCRIPTION:
WFSJR 017 5.0
END DESCRIPTION:
XS GIS Cut Line= 3
        3738751.     10217795.79      3738324.56     10217509.01
      3738017.88     10217311.09
#Sta/Elev= 30
  4486.1  289.53  4556.7  287.66  4562.7   286.8  4577.7  286.14  4607.7  286.21
  4613.7  284.89  4670.1  281.75  4706.8  279.79  4736.7  277.69    4743  276.64
  4808.7  273.04  4874.7  272.01  4916.7  272.22  4973.7  270.77  4982.6  268.82
  4988.7  268.45  4992.7  266.41    5000  266.91  5003.7  269.17  5018.9  270.77
    5046  271.23  5097.4   274.6  5103.4  274.29  5162.7  277.23  5221.5  281.49
  5234.1  283.14  5273.4  285.43  5329.3  289.02  5336.3  290.16    5365  292.46
#Mann= 5 ,-1 , 0
  4486.1     .17       0  4670.1     .15       0  4973.7     .09       0
  5018.9     .15       0  5273.4     .11       0
Bank Sta=4973.7,5018.9
XS Rating Curve= 0 ,0
Exp/Cntr=0.3,0.1

Type RM Length L Ch R = 1 ,2597    ,498,498,498
BEGIN DESCRIPTION:
WFSJR 017 4.0
END DESCRIPTION:
XS GIS Cut Line= 3
      3738974.99     10217519.78      3738639.54     10217160.28
      3738317.83     10216961.06
#Sta/Elev= 30
  4508.3  289.73  4569.1  285.83  4590.1  285.18  4611.6     283  4689.2  277.93
  4725.2  277.01  4760.1  274.78  4816.8  273.67  4866.1  271.61  4873.4  271.92
  4922.8  270.77  4965.3  269.02  4972.1  267.98  4983.9  265.04  4988.6  265.04
  4993.6  265.93  4997.6   267.6  5003.9   267.6  5007.9  268.64  5013.8  268.95
  5031.8  269.05  5050.4  268.83  5072.6  270.61  5117.8  272.73  5218.3  278.63
  5260.8  281.78  5270.3   281.9  5276.1  282.88  5312.8   285.4  5378.4  291.23
#Mann= 5 ,-1 , 0
  4508.3     .17       0  4725.2     .15       0  4965.3     .09       0
  5013.8     .15       0  5031.8     .11       0
Bank Sta=4965.3,5013.8
XS Rating Curve= 0 ,0
Exp/Cntr=0.3,0.1

Type RM Length L Ch R = 1 ,2099    ,434,434,434
BEGIN DESCRIPTION:
WFSJR 017 3.0
END DESCRIPTION:
XS GIS Cut Line= 3
      3739317.86     10216861.07       3738900.9     10216754.37
      3738567.82     10216661.06
#Sta/Elev= 30
  4569.6  285.54  4587.4  285.88  4621.2  281.47  4641.9  280.31  4669.1  277.93
  4680.6  277.75  4693.5  277.32  4724.4  274.85  4745.1  274.05  4750.7  273.24
  4776.1  272.41    4807   269.8  4827.1  269.16  4832.3   268.5  4873.1  267.19
  4949.6  267.27  4972.2   265.8  4992.7  265.53  4993.2  265.03  5004.2  265.56
  5013.5  267.16  5029.9  268.04  5069.2   268.2  5108.5   269.5  5250.2  278.05
  5273.2  278.48  5304.3  281.97  5323.6  282.58  5328.8  282.22  5345.9  284.12
#Mann= 4 ,-1 , 0
  4569.6     .17       0  4680.6     .15       0  4949.6     .07       0
  5013.5     .11       0
Bank Sta=4949.6,5013.5
XS Rating Curve= 0 ,0
Exp/Cntr=0.3,0.1

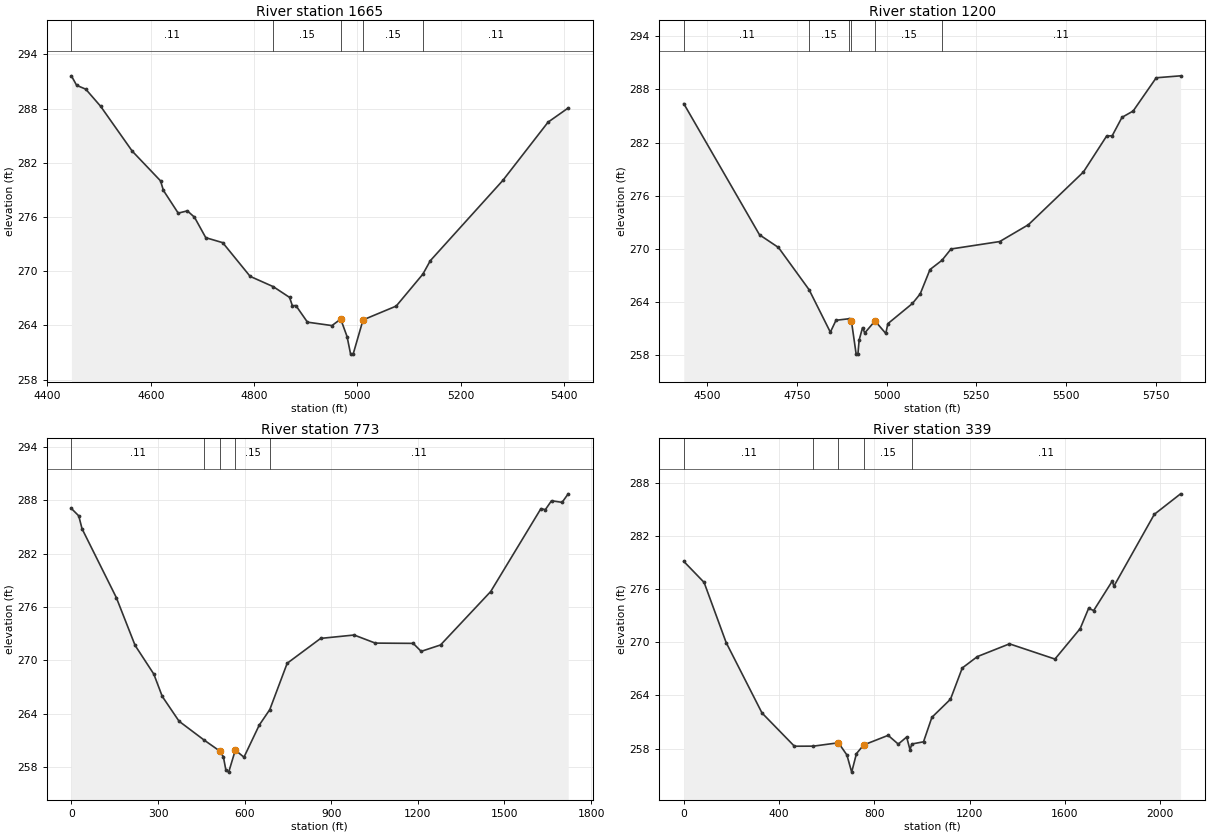
Type RM Length L Ch R = 1 ,1665    ,465,465,465
BEGIN DESCRIPTION:
WFSJR 017 2.0
END DESCRIPTION:
XS GIS Cut Line= 3
      3739615.54     10216618.69      3739277.04     10216467.67
      3738731.47     10216239.05
#Sta/Elev= 30
  4446.3  291.63  4456.5  290.58  4474.2  290.15  4502.9  288.26  4564.2  283.29
    4619     280  4624.5  278.95  4653.2  276.43  4670.9  276.68  4684.7  275.98
  4706.6  273.71  4739.4  273.16  4792.5  269.43  4837.3  268.29  4868.9   267.1
  4874.3  266.18  4881.1   266.2  4903.5  264.36    4951  263.98  4967.9   264.7
  4980.2  262.77  4987.1  260.82    4992  260.82  5011.2  264.61  5075.4  266.14
  5127.1  269.68  5141.4  271.16  5281.9  280.05  5369.5   286.5  5408.5  288.07
#Mann= 5 ,-1 , 0
  4446.3     .11       0  4837.3     .15       0  4967.9     .09       0
  5011.2     .15       0  5127.1     .11       0
Bank Sta=4967.9,5011.2
XS Rating Curve= 0 ,0
Exp/Cntr=0.3,0.1

Type RM Length L Ch R = 1 ,1200    ,427,427,427
BEGIN DESCRIPTION:
WFSJR 017 1.0
END DESCRIPTION:
XS GIS Cut Line= 3
      3739797.87       10216301.      3739094.75     10215889.54
       3738605.2     10216181.19
#Sta/Elev= 30
  4434.8   286.4  4645.9  271.59  4698.7  270.16  4784.1  265.39  4843.3   260.6
    4859  261.94  4896.2  262.12    4902  261.87  4915.2  258.12  4920.1  258.12
  4923.5   259.7    4933  261.11  4939.2  260.51  4967.8  261.87  4997.8  260.45
  5003.6  261.56  5072.1  263.84  5093.7  264.92    5121  267.67  5154.3  268.71
  5179.6  269.99  5315.3  270.83  5395.2  272.73  5548.5  278.68  5613.2  282.74
  5628.8  282.78    5656  284.85  5687.2  285.57  5751.4  289.32  5819.3  289.54
#Mann= 6 ,-1 , 0
  4434.8     .11       0  4784.1     .15       0  4896.2     .12       0
    4902     .09       0  4967.8     .15       0  5154.3     .11       0
Bank Sta=4902,4967.8
XS Rating Curve= 0 ,0
Exp/Cntr=0.3,0.1

Type RM Length L Ch R = 1 ,773     ,434,434,434
XS GIS Cut Line= 3
      3740101.37     10215928.55      3739419.07      10215642.1
      3738583.14     10216157.72
#Sta/Elev= 30
       0   287.1    25.5  286.27      37  284.81   155.6  277.07   220.7  271.68
   285.5  268.45   314.7  265.94     373  263.14   459.3  261.03   513.6  259.79
   526.4  259.14   535.2  257.62   544.8  257.41   567.8  259.89   597.7  259.09
   650.7  262.71   687.1  264.45   747.4  269.67   863.3  272.47   979.2  272.85
  1052.6  271.94  1183.8  271.91  1211.4  271.01  1278.5  271.73  1452.3  277.75
  1626.1  287.08  1641.5  286.97  1662.8  287.97  1699.5  287.79  1720.6  288.75
#Mann= 5 ,-1 , 0
       0     .11       0   459.3     .15       0   513.6     .09       0
   567.8     .15       0   687.1     .11       0
Bank Sta=513.6,567.8
XS Rating Curve= 0 ,0
Exp/Cntr=0.3,0.1

Type RM Length L Ch R = 1 ,339     ,0,0,0
XS GIS Cut Line= 4
      3740176.86     10215610.67      3739776.14     10215318.38
      3739433.85     10215290.75      3738525.85      10216144.7
#Sta/Elev= 30
       0  279.17    85.4  276.79   177.9  269.99   328.5  262.02   464.5  258.26
   544.4  258.27   649.4  258.65   684.9  257.27     705  255.33     725  257.42
   755.1   258.4   858.1  259.49   900.6   258.5   935.8   259.3     950  257.85
   957.3  258.51  1006.6  258.76  1041.8  261.53  1119.9  263.58  1169.3  267.11
  1232.8   268.4  1367.5  269.84  1558.5  268.12  1664.5  271.57  1699.7  273.85
  1721.1  273.61  1798.8  276.93  1806.1  276.37  1975.6  284.49  2085.9  286.81
#Mann= 5 ,-1 , 0
       0     .11       0   544.4     .15       0   649.4     .09       0
   755.1     .15       0   957.3     .11       0
Bank Sta=649.4,755.1
XS Rating Curve= 0 ,0
Exp/Cntr=0.3,0.1

Chan Stop Cuts=-1
Use User Specified Reach Order=0
Composite Channel Slope=5