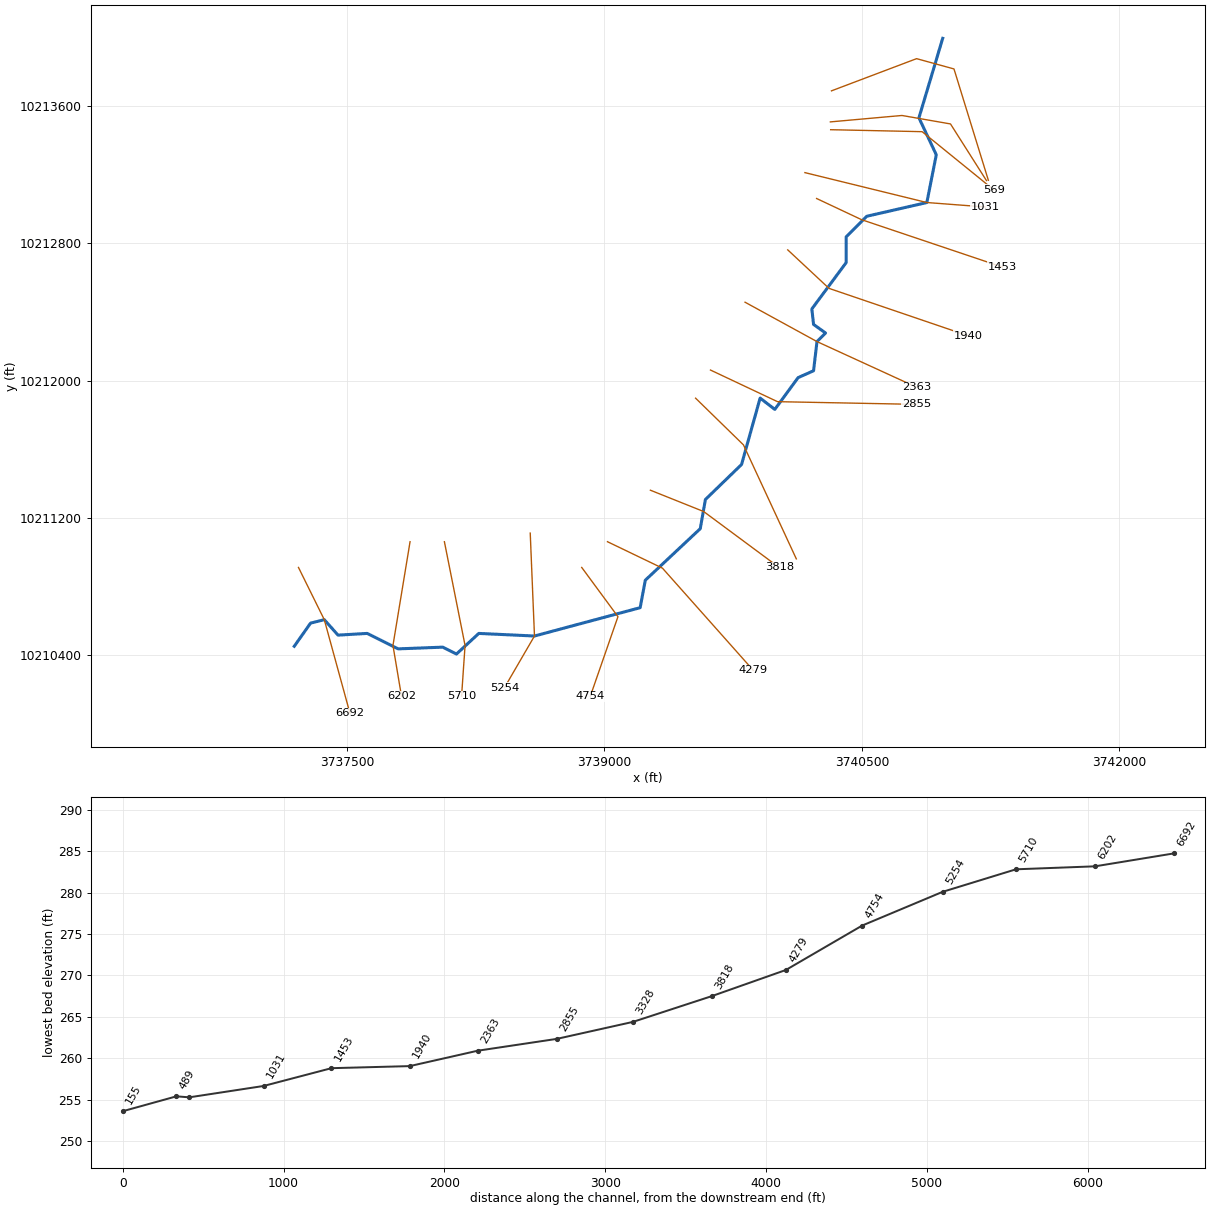
--- WFSJR 018.prj (project) ---

Proj Title=WFSJR 018 Base Level Engineering
Current Plan=p01
Default Exp/Contr=0.3,0.1
English Units
Geom File=g01
Flow File=f01
Plan File=p01
Y Axis Title=Elevation
X Axis Title(PF)=Main Channel Distance
X Axis Title(XS)=Station
BEGIN DESCRIPTION:
WFSJR 018
END DESCRIPTION:
DSS Export Rating Curves= 0
DSS Export Rating Curve Sorted= 0
DSS Export Volume Flow Curves= 0
DXF OffsetX= 0
DXF OffsetY= 0
DXF ScaleX= 1
DXF ScaleY= 10

--- WFSJR 018.p01 (plan) ---

Plan Title=Multiple Run
Program Version=4.10
Short Identifier=Multiple
Geom File=g01
Flow File=f01
Subcritical Flow
K Sum by GR= 0
Std Step Tol= 0.01
Critical Tol= 0.01
Num of Std Step Trials= 20
Max Error Tol= 0.3
Flow Tol Ratio= 0.001
Split Flow NTrial= 30
Split Flow Tol= 0.02
Split Flow Ratio= 0.02
Log Output Level= 0
Friction Slope Method= 1
Unsteady Friction Slope Method= 2
Unsteady Bridges Friction Slope Method= 1
Parabolic Critical Depth
Global Vel Dist= 1 , 1 , 1
Global Log Level= 0
CheckData=True
Encroach Param=-1 ,0,0, 0
BEGIN DESCRIPTION:
Multiple Run
END DESCRIPTION:
Computation Interval=1HOUR
Output Interval=1HOUR
Run HTab= 0
Run UNet= 0
Run PostProcess= 0
Run WQNet= 0
UNET Theta= 1
UNET Theta Warmup= 1
UNET ZTol= 0.02
UNET ZSATol= 0.05
UNET MxIter= 20
UNET MaxInSteps= 0
UNET DtIC= 0
UNET DtMin= 0
UNET MaxCRTS= 20
UNET WFStab= 2
UNET SFStab= 1
UNET WFX= 1
UNET SFX= 1
UNET DSS MLevel= 4
UNET DZMax Abort= 100
UNET Convert EG Bridges= 0
UNET Use Existing IB Tables=-1
UNET Froude Reduction=False
UNET Froude Limit= 1
UNET Froude Power= 10
UNET Time Slicing=0,0, 5
UNET Junction Losses=0
Instantaneous Interval=1HOUR
Write IC File= 0
Write IC File at Sim End=0
Echo Input=False
Echo Parameters=False
Echo Output=False
Write Detailed= 0
WQ AD Non Conservative
WQ ULTIMATE=-1
WQ Max Comp Step=1HOUR
WQ Output Interval=15MIN
WQ Output Selected Increments= 0
WQ Output face flow=0
WQ Output face velocity=0
WQ Output face area=0
WQ Output face dispersion=0
WQ Output cell volume=0
WQ Output cell surface area=0
WQ Output cell continuity=0
WQ Output cumulative cell continuity=0
WQ Output face conc=0
WQ Output face dconc_dx=0
WQ Output face courant=0
WQ Output face peclet=0
WQ Output face adv mass=0
WQ Output face disp mass=0
WQ Output cell mass=0
WQ Output cell source sink temp=0
WQ Output cell source sink nsm=0
WQ Output MaxMinRange=-1
WQ Daily Max Min Mean=-1
WQ Daily Range=0
WQ Daily Time=0
WQ Create Restart=0
WQ Fixed Restart=0
WQ System Summary=0
WQ Use Fixed Temperature=0
Sorting and Armoring Iterations= 10
XS Update Threshold= 0.02
Hydraulics Update Threshold= 0.02
Energy Slope Method= 1
Volume Change Method= 0
XS Weighting Method= 0
Number of US Weighted Cross Sections= 1
Number of DS Weighted Cross Sections= 1
Upstream XS Weight=0.25
Main XS Weight=0.5
Downstream XS Weight=0.25
Number of DS XS's Weighted with US Boundary= 1
Upstream Boundary Weight= 1
Weight of XSs Associated with US Boundary= 0
Number of US XS's Weighted with DS Boundary= 1
Downstream Boundary Weight= 0.5
Weight of XSs Associated with DS Boundary= 0.5
Sediment Output Level= 4
Mass or Volume Output= 0
Output Increment Type= 1
Profile and TS Output Increment= 10
XS Output Flag= 0
XS Output Increment= 10
Disregard all LS=0
Disregard all Conn=0
Disregard all Breaches=0
Disregard all Pumps=0

--- WFSJR 018.f01 (steady flow) ---

Flow Title=Multiple
Program Version=4.10
Number of Profiles= 7
Profile Names=10-year,25-year,50-year,1pct_min,100-year,1pct_plu,500-year
River Rch & RM=WFSJR 018,Reach-1         ,6692
     924    1295    1793     816    2465    7444    4818
River Rch & RM=WFSJR 018,Reach-1         ,2855
    1177    1665    2316    1059    3197    9655    6304
River Rch & RM=WFSJR 018,Reach-1         ,2363
    1177    1665    2316    1059    3197    9655    6304
Boundary for River Rch & Prof#=WFSJR 018,Reach-1         , 1
Up Type= 0
Dn Type= 3
Dn Slope=0.005
Boundary for River Rch & Prof#=WFSJR 018,Reach-1         , 2
Up Type= 0
Dn Type= 3
Dn Slope=0.005
Boundary for River Rch & Prof#=WFSJR 018,Reach-1         , 3
Up Type= 0
Dn Type= 3
Dn Slope=0.005
Boundary for River Rch & Prof#=WFSJR 018,Reach-1         , 4
Up Type= 0
Dn Type= 3
Dn Slope=0.005
Boundary for River Rch & Prof#=WFSJR 018,Reach-1         , 5
Up Type= 0
Dn Type= 3
Dn Slope=0.005
Boundary for River Rch & Prof#=WFSJR 018,Reach-1         , 6
Up Type= 0
Dn Type= 3
Dn Slope=0.005
Boundary for River Rch & Prof#=WFSJR 018,Reach-1         , 7
Up Type= 0
Dn Type= 3
Dn Slope=0.005
DSS Import GetInterval= 0
DSS Import GetPeak= 0
DSS Import FillOption= 0

--- WFSJR 018.g01 (geometry) ---

Geom Title=Existing Conditions
Program Version=4.10

River Reach=WFSJR 018       ,Reach-1
Reach XY= 30
      3737193.23     10210451.84      3737288.23     10210586.84
      3737368.23     10210606.84      3737448.23     10210516.84
      3737618.23     10210526.84      3737798.23     10210436.84
      3738058.23     10210446.84      3738138.23     10210406.84
      3738268.23     10210526.84      3738592.59     10210511.71
      3739208.23     10210676.84      3739238.23     10210836.84
      3739558.23     10211136.84      3739588.23     10211306.84
      3739798.87     10211510.87      3739906.95     10211897.55
      3739992.64     10211831.83      3740128.23     10212016.84
      3740218.23     10212056.84      3740238.23     10212226.84
      3740288.23     10212276.84      3740218.23     10212326.84
      3740208.23     10212416.84      3740408.23     10212686.84
      3740408.23     10212836.84      3740528.23     10212956.84
      3740878.23     10213036.84      3740933.12     10213314.96
      3740832.16     10213530.34      3740970.52      10213993.3

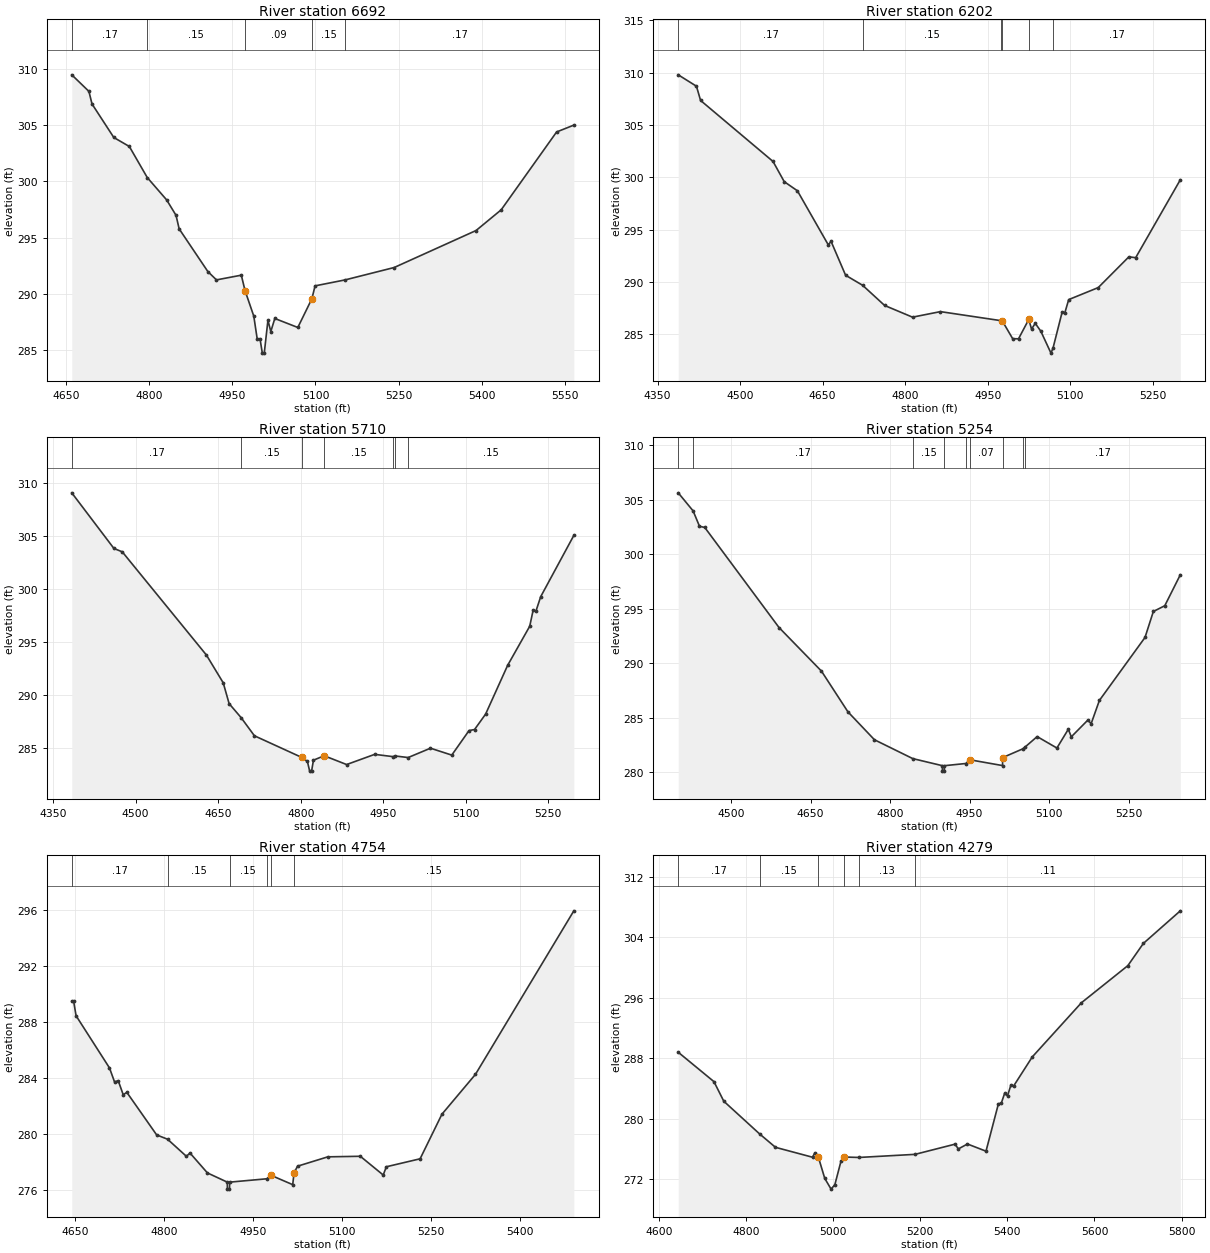
Type RM Length L Ch R = 1 ,6692    ,490,490,490
BEGIN DESCRIPTION:
WFSJR 018 14.0
END DESCRIPTION:
XS GIS Cut Line= 3
      3737217.84      10210911.1      3737368.23     10210606.84
      3737517.85     10210061.08
#Sta/Elev= 30
  4660.6  309.48  4691.5  308.01  4697.1  306.89  4736.4  303.91  4764.4  303.11
  4796.7  300.35  4831.7  298.36  4848.6  296.99  4854.2  295.79    4906  291.99
  4921.5  291.25  4966.3  291.67    4973   290.3  4988.8  288.03  4994.9  286.02
    5000  286.02  5004.2  284.74  5007.7  284.74  5014.3  287.66  5019.5  286.66
  5026.7  287.82  5068.2  287.02  5093.6  289.58  5099.3  290.72  5153.5  291.25
  5241.9  292.35  5389.6  295.64  5434.9  297.48  5534.8   304.4  5565.9  305.01
#Mann= 5 ,-1 , 0
  4660.6     .17       0  4796.7     .15       0    4973     .09       0
  5093.6     .15       0  5153.5     .17       0
Bank Sta=4973,5093.6
XS Rating Curve= 0 ,0
Exp/Cntr=0.3,0.1

Type RM Length L Ch R = 1 ,6202    ,492,492,492
BEGIN DESCRIPTION:
WFSJR 018 13.0
END DESCRIPTION:
XS GIS Cut Line= 3
      3737867.85     10211061.09      3737768.23     10210456.84
      3737817.85     10210161.08
#Sta/Elev= 30
  4387.6   309.8  4420.7  308.71  4428.2  307.35  4559.9  301.51  4580.2  299.58
  4604.1  298.71  4660.2  293.54  4665.3  293.87  4691.7  290.63  4722.6  289.67
  4762.6  287.74  4813.3  286.62    4864  287.15  4973.5  286.29  4976.1  286.29
  4995.3  284.56  5005.9  284.55  5024.5   286.4  5029.6  285.48  5036.3  286.03
  5046.4  285.28  5064.9  283.18  5068.7  283.68  5085.1  287.09  5090.2  287.06
  5097.1   288.3  5150.8  289.45  5206.4  292.39  5218.8  292.31  5299.9  299.76
#Mann= 6 ,-1 , 0
  4387.6     .17       0  4722.6     .15       0  4973.5     .17       0
  4976.1     .09       0  5024.5     .17       0  5068.7     .17       0
Bank Sta=4976.1,5024.5
XS Rating Curve= 0 ,0
Exp/Cntr=0.3,0.1

Type RM Length L Ch R = 1 ,5710    ,456,456,456
BEGIN DESCRIPTION:
WFSJR 018 12.0
END DESCRIPTION:
XS GIS Cut Line= 3
      3738067.85     10211061.07      3738188.23     10210456.84
      3738167.85     10210161.05
#Sta/Elev= 30
  4383.9  309.04  4460.5   303.8  4475.7  303.48  4628.6  293.76  4659.2  291.14
  4669.9  289.18  4691.7  287.86  4715.9  286.15    4802  284.11  4812.2  283.73
  4816.3  282.82  4819.8  282.82  4823.2  283.85  4842.7  284.27  4883.5  283.44
  4934.5   284.4  4968.6  284.18  4971.3  284.25  4995.3   284.1  5035.9  284.98
  5074.6  284.33    5106  286.64    5116  286.74  5136.1  288.19  5176.2  292.79
  5216.3  296.47  5222.5  297.98  5227.5  297.88  5236.3  299.26  5296.5  305.03
#Mann= 7 ,-1 , 0
  4383.9     .17       0  4691.7     .15       0    4802     .08       0
  4842.7     .15       0  4968.6     .15       0  4971.3     .11       0
  4995.3     .15       0
Bank Sta=4802,4842.7
XS Rating Curve= 0 ,0
Exp/Cntr=0.3,0.1

Type RM Length L Ch R = 1 ,5254    ,500,500,500
BEGIN DESCRIPTION:
WFSJR 018 11.0
END DESCRIPTION:
XS GIS Cut Line= 3
      3738567.85      10211111.1      3738592.59     10210511.71
      3738417.87      10210211.1
#Sta/Elev= 30
  4400.1  305.64  4428.2  303.98  4440.2  302.57  4450.2  302.46  4590.3  293.28
  4670.4  289.28  4720.4  285.54  4770.4  282.98  4842.7  281.25  4898.6   280.6
  4898.8   280.1  4902.3   280.1  4902.6   280.6    4943   280.8  4950.6  281.14
  5012.2  280.61  5012.3  281.34  5050.2  282.14    5054  282.28  5077.5  283.27
  5114.8  282.22  5136.3  283.94    5142  283.25  5173.5   284.8  5179.3  284.44
    5195  286.59  5281.1  292.37  5296.8  294.75  5318.4  295.28  5347.7  298.12
#Mann= 9 ,-1 , 0
  4400.1     .11       0  4428.2     .17       0  4842.7     .15       0
  4902.6     .15       0    4943     .15       0  4950.6     .07       0
  5012.3     .15       0  5050.2     .15       0    5054     .17       0
Bank Sta=4950.6,5012.3
XS Rating Curve= 0 ,0
Exp/Cntr=0.3,0.1

Type RM Length L Ch R = 1 ,4754    ,475,475,475
BEGIN DESCRIPTION:
WFSJR 018 10.0
END DESCRIPTION:
XS GIS Cut Line= 3
      3738867.86     10210911.06      3739078.87     10210624.45
      3738917.84     10210161.03
#Sta/Elev= 30
  4644.1  289.48  4647.2  289.48  4651.4  288.43  4707.7   284.7  4716.2   283.7
  4722.4  283.79  4730.8  282.79    4737  282.95  4787.2  279.91  4805.6   279.6
  4837.3  278.38  4843.5  278.61  4872.8  277.19  4906.3  276.53  4906.5  276.03
    4910  276.03  4910.3  276.53  4973.1  276.77  4979.4  277.03  5016.6  276.35
  5018.9  277.19  5024.7  277.67  5075.8  278.34  5130.6  278.38  5169.2  277.04
  5174.5  277.63  5231.4   278.2  5268.2  281.39  5324.7  284.24  5490.6  295.94
#Mann= 6 ,-1 , 0
  4644.1     .17       0  4805.6     .15       0  4910.3     .15       0
  4973.1     .15       0  4979.4     .08       0  5018.9     .15       0
Bank Sta=4979.4,5018.9
XS Rating Curve= 0 ,0
Exp/Cntr=0.3,0.1

Type RM Length L Ch R = 1 ,4279    ,461,461,461
BEGIN DESCRIPTION:
WFSJR 018 9.0
END DESCRIPTION:
XS GIS Cut Line= 3
      3739017.82     10211061.09      3739338.23     10210906.84
      3739867.82     10210311.11
#Sta/Elev= 30
  4644.4  288.77  4726.4  284.88    4749  282.29  4831.1  277.97  4867.7  276.19
  4952.7  274.88  4958.2  275.48  4966.3  274.86  4980.8  272.08  4995.3  270.66
    5004  271.25  5018.2  274.39  5024.9  274.91  5059.3  274.85    5188  275.26
  5279.9  276.61  5287.5  275.98  5308.4  276.63    5351  275.68  5379.5  281.95
  5386.1  282.03  5393.7  283.32  5400.4     283  5407.9  284.38  5414.6  284.32
  5457.2  288.15  5570.1  295.32  5676.7  300.23  5712.3  303.17  5797.1  307.48
#Mann= 6 ,-1 , 0
  4644.4     .17       0  4831.1     .15       0  4966.3     .09       0
  5024.9     .15       0  5059.3     .13       0    5188     .11       0
#XS Ineff= 1 ,-1
  5279.9    5360  276.61
Permanent Ineff=
       F
Bank Sta=4966.3,5024.9
XS Rating Curve= 0 ,0
Exp/Cntr=0.3,0.1

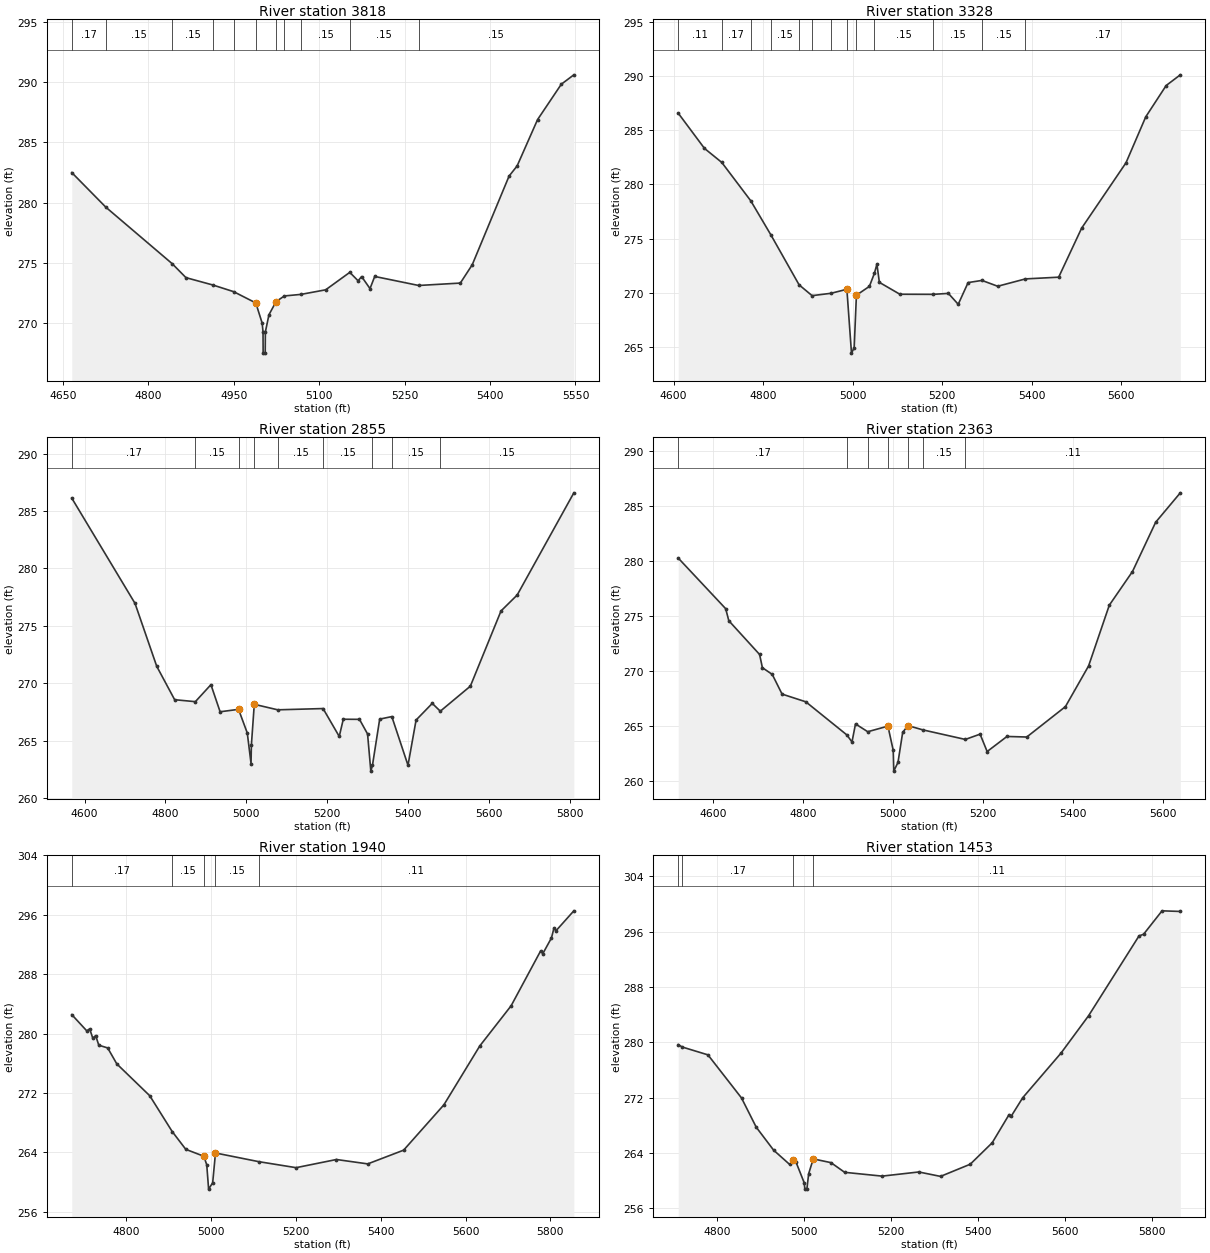
Type RM Length L Ch R = 1 ,3818    ,490,490,490
BEGIN DESCRIPTION:
WFSJR 018 8.0
END DESCRIPTION:
XS GIS Cut Line= 3
      3739267.87     10211361.07      3739578.23     10211236.84
      3740017.88     10210911.05
#Sta/Elev= 30
  4665.7   282.5  4725.6  279.62    4842  274.93  4866.2  273.77  4913.4  273.16
  4949.7  272.61  4988.8  271.67    5000  269.99  5001.5  269.26  5001.7   267.5
  5005.3   267.5  5005.6  269.26  5011.9  270.69  5024.4  271.78    5039  272.25
  5068.2  272.38  5111.5  272.76  5153.8  274.21  5168.4  273.51  5174.6  273.86
  5189.3  272.86  5197.6  273.87  5274.8  273.12  5347.9  273.32  5368.8  274.84
  5433.5  282.21  5447.6  283.05  5483.5   286.9  5525.2  289.84  5547.2  290.62
#Mann= 11 ,-1 , 0
  4665.7     .17       0  4725.6     .15       0    4842     .15       0
  4913.4     .15       0  4949.7     .15       0  4988.8     .09       0
  5024.4     .15       0    5039     .15       0  5068.2     .15       0
  5153.8     .15       0  5274.8     .15       0
Bank Sta=4988.8,5024.4
XS Rating Curve= 0 ,0
Exp/Cntr=0.3,0.1

Type RM Length L Ch R = 1 ,3328    ,473,473,473
BEGIN DESCRIPTION:
WFSJR 018 7.0
END DESCRIPTION:
XS GIS Cut Line= 3
      3739531.11     10211897.12      3739809.95     10211625.03
      3740117.86     10210961.05
#Sta/Elev= 30
  4610.4   286.6    4669  283.34  4707.7  282.04  4772.4  278.49  4817.4  275.33
  4880.4  270.71  4909.4  269.71  4951.9  269.93  4987.1   270.3  4997.4  264.39
  5003.4  264.89  5008.4  269.75  5037.4  270.57  5048.5  271.77  5054.2  272.62
  5059.7  270.94  5105.5  269.84  5179.9  269.83  5213.8  269.92  5235.8  268.91
  5257.9  270.92  5288.8  271.12    5324  270.58  5385.9  271.26  5460.2  271.42
  5511.5  275.96  5610.6  282.01  5654.7  286.26  5700.3  289.16  5731.9  290.15
#Mann= 13 ,-1 , 0
  4610.4     .11       0  4707.7     .17       0  4772.4     .17       0
  4817.4     .15       0  4880.4     .15       0  4909.4     .15       0
  4951.9     .15       0  4987.1     .09       0  5008.4     .15       0
  5048.5     .15       0  5179.9     .15       0  5288.8     .15       0
  5385.9     .17       0
Bank Sta=4987.1,5008.4
XS Rating Curve= 0 ,0
Exp/Cntr=0.3,0.1

Type RM Length L Ch R = 1 ,2855    ,492,492,492
BEGIN DESCRIPTION:
WFSJR 018 6.0
END DESCRIPTION:
XS GIS Cut Line= 3
      3739617.82     10212061.09      3740008.23     10211876.84
      3740817.88     10211861.07
#Sta/Elev= 30
  4568.3  286.12  4724.7  276.95  4778.4  271.47  4822.7  268.56  4873.9  268.39
  4912.4  269.87  4935.1  267.51  4980.7  267.72  5002.3  265.66  5011.6     263
  5012.4  264.59  5019.6  268.16  5077.6  267.68  5189.7  267.79  5229.7  265.36
  5239.7  266.86  5279.7  266.85  5299.7  265.58  5307.8  262.34  5311.8  262.84
  5329.7  266.87  5359.7  267.09  5399.7  262.85  5419.7  266.79  5459.7  268.24
  5479.6  267.56  5553.9  269.74  5629.7  276.29  5669.7  277.68  5809.8  286.58
#Mann= 9 ,-1 , 0
  4568.3     .17       0  4873.9     .15       0  4980.7     .09       0
  5019.6     .15       0  5077.6     .15       0  5189.7     .15       0
  5311.8     .15       0  5359.7     .15       0  5479.6     .15       0
#XS Ineff= 1 ,-1
    4790  4912.4  269.87
Permanent Ineff=
       F
Bank Sta=4980.7,5019.6
XS Rating Curve= 0 ,0
Exp/Cntr=0.3,0.1

Type RM Length L Ch R = 1 ,2363    ,423,423,423
BEGIN DESCRIPTION:
WFSJR 018 5.0
END DESCRIPTION:
XS GIS Cut Line= 3
      3739819.36      10212456.1      3740238.23     10212226.84
      3740817.81     10211961.09
#Sta/Elev= 30
  4522.5  280.27  4627.9  275.67  4634.8  274.58  4703.2  271.51  4709.4  270.31
  4731.3   269.7  4753.1  267.91  4805.8  267.21    4897   264.2  4908.4  263.56
  4916.2   265.2  4943.4  264.49  4988.2     265    5000   262.8  5001.2  260.91
  5010.6  261.71    5021  264.43  5032.6  265.05  5065.6  264.66  5160.1  263.79
  5192.9  264.27  5208.6  262.69  5252.6  264.06  5296.6  264.01  5382.4  266.77
  5433.9  270.47  5479.9  275.99  5531.4  279.05  5582.9  283.53  5637.6   286.2
#Mann= 7 ,-1 , 0
  4522.5     .17       0    4897     .15       0  4943.4     .17       0
  4988.2     .09       0  5032.6     .17       0  5065.6     .15       0
  5160.1     .11       0
Bank Sta=4988.2,5032.6
XS Rating Curve= 0 ,0
Exp/Cntr=0.3,0.1

Type RM Length L Ch R = 1 ,1940    ,487,487,487
BEGIN DESCRIPTION:
WFSJR 018 4.0
END DESCRIPTION:
XS GIS Cut Line= 3
      3740067.87     10212761.06      3740308.23     10212536.84
      3741117.85     10212261.07
#Sta/Elev= 30
  4671.3  282.56  4706.7  280.37  4713.5  280.64  4720.9  279.38  4727.7  279.73
    4735  278.44    4756  278.07  4777.5  275.92  4855.2  271.63  4908.1  266.81
  4940.2  264.41  4982.7  263.48  4989.6  262.33    4994  259.05  5003.6  259.91
  5010.2  263.92  5112.3  262.75  5200.3  261.94  5295.4  263.04  5369.3  262.45
  5453.9   264.3  5548.9  270.41  5633.5  278.34  5707.4  283.75  5776.9  291.13
  5782.2  290.78  5802.5  292.89  5808.3  294.19  5813.6  293.88  5855.3  296.54
#Mann= 5 ,-1 , 0
  4671.3     .17       0  4908.1     .15       0  4982.7     .09       0
  5010.2     .15       0  5112.3     .11       0
Bank Sta=4982.7,5010.2
XS Rating Curve= 0 ,0
Exp/Cntr=0.3,0.1

Type RM Length L Ch R = 1 ,1453    ,422,422,422
BEGIN DESCRIPTION:
WFSJR 018 3.0
END DESCRIPTION:
XS GIS Cut Line= 3
      3740236.03     10213060.27      3740498.23     10212936.84
      3741317.88     10212661.06
#Sta/Elev= 30
  4710.2  279.69  4719.5  279.34  4778.5  278.21  4855.7  271.98  4889.5  267.76
  4929.6  264.43  4966.4  262.37  4975.1  263.01  4980.7  262.76    5000   259.7
  5001.4   258.8    5006   258.8  5010.2  261.04  5020.7  263.17  5061.4  262.63
  5092.9  261.23    5179  260.68  5263.4  261.28  5313.4  260.64  5381.7   262.4
  5432.2   265.5    5471  269.57  5476.2  269.37  5502.5  272.02  5590.4  278.46
  5653.8  283.86  5769.8   295.4  5780.4  295.65  5822.8  299.03  5864.8  298.94
#Mann= 4 ,-1 , 0
  4710.2     .11       0  4719.5     .17       0  4975.1     .06       0
  5020.7     .11       0
Bank Sta=4975.1,5020.7
XS Rating Curve= 0 ,0
Exp/Cntr=0.3,0.1

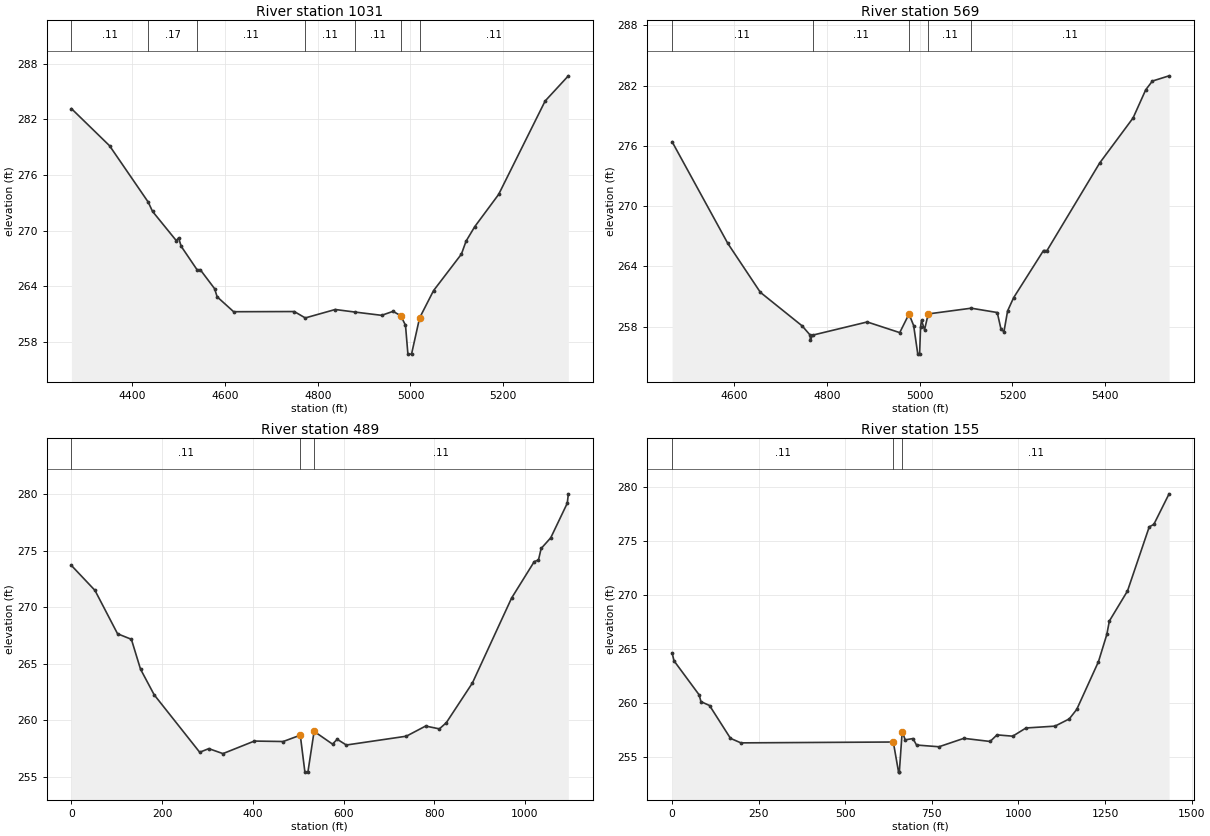
Type RM Length L Ch R = 1 ,1031    ,462,462,462
BEGIN DESCRIPTION:
WFSJR 018 2.0
END DESCRIPTION:
XS GIS Cut Line= 3
      3740167.88     10213211.06      3740878.23     10213036.84
      3741217.85     10213011.07
#Sta/Elev= 30
  4268.6  283.17  4350.9  279.16  4434.2  273.08  4443.6  272.07  4494.7  268.92
  4499.9   269.2  4505.4   268.3  4539.6  265.77  4546.6  265.77  4577.5  263.72
    4583  262.84  4618.6  261.23  4749.4  261.25  4773.1  260.56  4837.7  261.47
  4879.3   261.2  4937.8  260.84  4962.4  261.27    4979   260.8  4989.3  259.77
  4994.5  256.65  5002.3  256.65  5019.7  260.56  5049.8  263.51  5109.9  267.45
    5120  268.86  5138.7  270.42  5190.2   273.9  5290.5  283.99  5340.6  286.71
#Mann= 7 ,-1 , 0
  4268.6     .11       0  4434.2     .17       0  4539.6     .11       0
  4773.1     .11       0  4879.3     .11       0    4979     .06       0
  5019.7     .11       0
Bank Sta=4979,5019.7
XS Rating Curve= 0 ,0
Exp/Cntr=0.3,0.1

Type RM Length L Ch R = 1 ,569     ,80,80,80
BEGIN DESCRIPTION:
WFSJR 018 1.0
END DESCRIPTION:
XS GIS Cut Line= 3
      3740317.89     10213461.07      3740850.67     10213449.57
      3741267.82      10213111.1
#Sta/Elev= 30
  4467.1  276.41  4587.1  266.29  4657.1  261.43  4747.1  258.09  4764.4  257.17
  4764.8  256.67  4769.9  257.17  4887.2  258.48  4957.2  257.42  4977.2  259.27
  4987.2  258.12  4996.1  255.28    5000  255.28  5002.1  258.01  5004.2  258.64
  5010.6   257.7  5018.6  259.28  5111.2  259.85  5167.2  259.42  5175.2  257.78
  5181.6   257.5  5189.5  259.58  5202.4  260.89  5266.8  265.59  5274.3  265.58
  5387.8   274.3  5459.7  278.78  5486.9  281.58  5501.3  282.45  5537.2  282.97
#Mann= 5 ,-1 , 0
  4467.1     .11       0  4769.9     .11       0  4977.2     .06       0
  5018.6     .11       0  5111.2     .11       0
Bank Sta=4977.2,5018.6
XS Rating Curve= 0 ,0
Exp/Cntr=0.3,0.1

Type RM Length L Ch R = 1 ,489     ,334,334,334
XS GIS Cut Line= 4
      3740316.07     10213506.58      3740733.26     10213543.97
      3741015.94     10213494.64      3741225.36     10213164.78
#Sta/Elev= 30
       0   273.7      52  271.49   101.8  267.65   132.3  267.16   152.4  264.52
   182.5  262.25   282.9  257.16     303  257.48   334.2  257.04   403.4  258.15
     467  258.11   504.7  258.67   514.9   255.4   521.5   255.4   535.2  259.01
   575.8  257.88   586.1  258.31   606.2   257.8   738.5  258.58   781.1  259.48
   811.4  259.23   826.6  259.77   884.2  263.29   970.6  270.81  1020.6  274.04
  1029.9  274.18  1035.8   275.2    1057  276.15  1093.4  279.21  1095.8  280.04
#Mann= 3 , 0 , 0
       0     .11       0   504.7     .06       0   535.2     .11       0
Bank Sta=504.7,535.2
XS Rating Curve= 0 ,0
Exp/Cntr=0.3,0.1

Type RM Length L Ch R = 1 ,155     ,0,0,0
XS GIS Cut Line= 4
      3740322.72     10213687.44      3740818.38     10213874.94
      3741036.26     10213815.04      3741236.53     10213166.35
#Sta/Elev= 30
       0  264.64     5.5  263.91      78  260.76    83.3  260.13   108.1  259.77
   168.5  256.73   198.6  256.31   638.6  256.39   653.8   253.6     656   253.6
   664.2  257.35     673  256.59   695.3  256.71   705.7  256.11   770.5  255.95
   842.3  256.73   918.1  256.44     938  257.05   983.4  256.93  1021.7  257.69
  1105.4  257.86  1146.6  258.53  1168.2  259.41    1231  263.84    1255  266.35
  1262.4   267.6  1314.7  270.38  1377.5  276.32  1390.8  276.55  1434.8  279.38
#Mann= 3 , 0 , 0
       0     .11       0   638.6     .06       0   664.2     .11       0
Bank Sta=638.6,664.2
XS Rating Curve= 0 ,0
Exp/Cntr=0.3,0.1

Chan Stop Cuts=-1
Use User Specified Reach Order=0
Composite Channel Slope=5