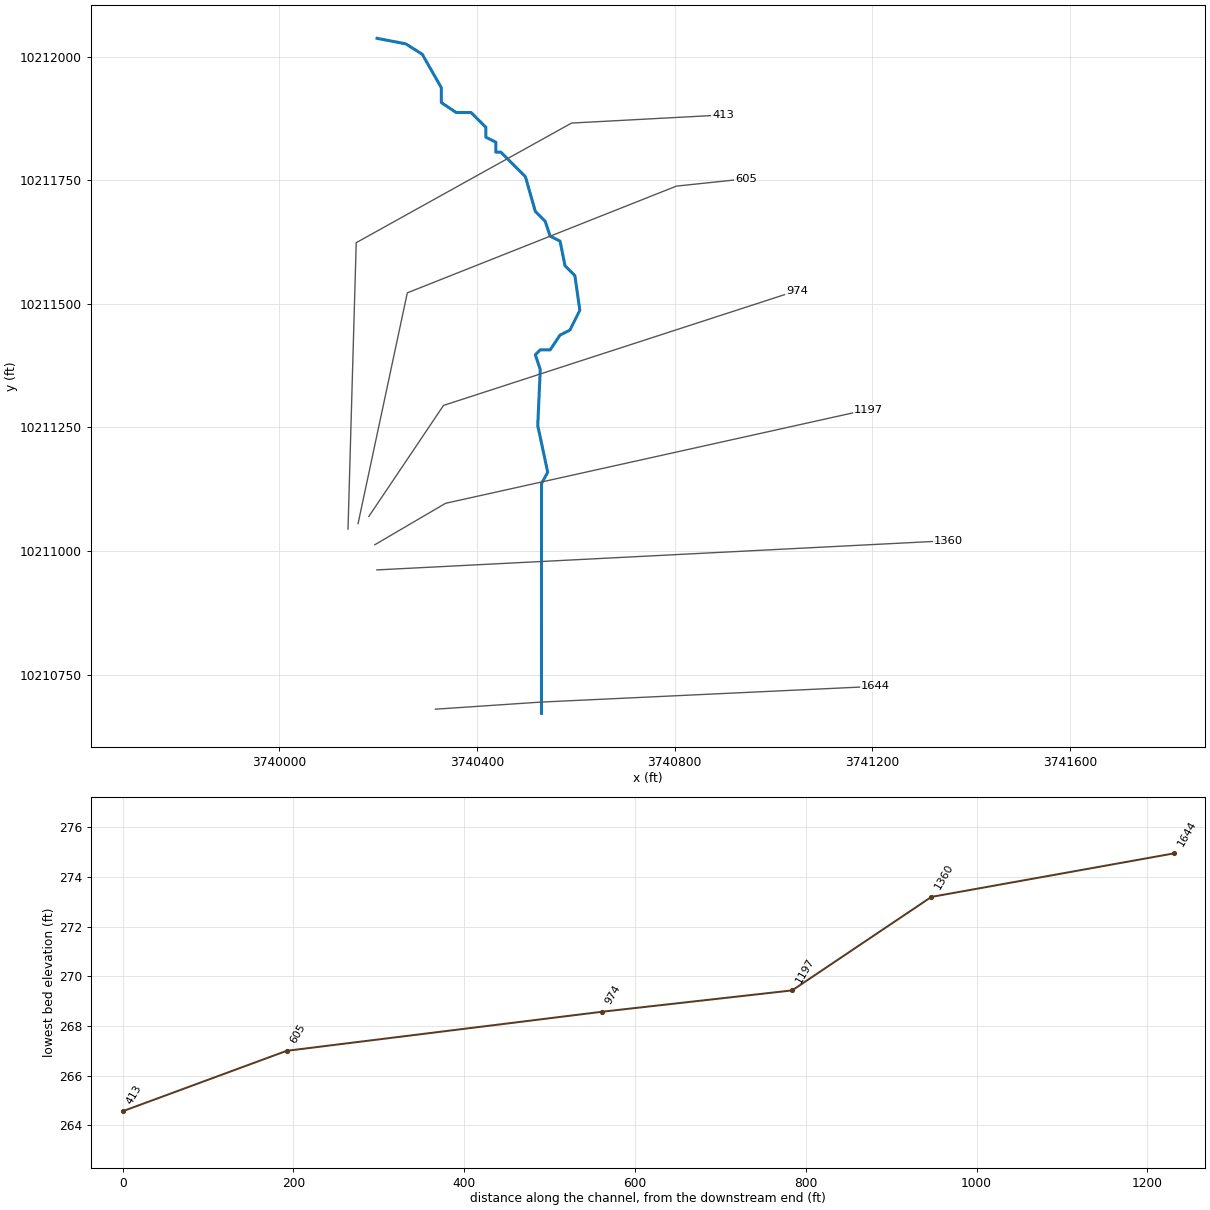
--- WFSJR 019.prj (project) ---

Proj Title=WFSJR 019 Base Level Engineering
Current Plan=p01
Default Exp/Contr=0.3,0.1
English Units
Geom File=g01
Flow File=f01
Plan File=p01
Y Axis Title=Elevation
X Axis Title(PF)=Main Channel Distance
X Axis Title(XS)=Station
BEGIN DESCRIPTION:
WFSJR 019
END DESCRIPTION:
DSS Export Rating Curves= 0
DSS Export Rating Curve Sorted= 0
DSS Export Volume Flow Curves= 0
DXF OffsetX= 0
DXF OffsetY= 0
DXF ScaleX= 1
DXF ScaleY= 10

--- WFSJR 019.p01 (plan) ---

Plan Title=Multiple Run
Program Version=4.10
Short Identifier=Multiple
Geom File=g01
Flow File=f01
Subcritical Flow
K Sum by GR= 0
Std Step Tol= 0.01
Critical Tol= 0.01
Num of Std Step Trials= 20
Max Error Tol= 0.3
Flow Tol Ratio= 0.001
Split Flow NTrial= 30
Split Flow Tol= 0.02
Split Flow Ratio= 0.02
Log Output Level= 0
Friction Slope Method= 1
Unsteady Friction Slope Method= 2
Unsteady Bridges Friction Slope Method= 1
Parabolic Critical Depth
Global Vel Dist= 1 , 1 , 1
Global Log Level= 0
CheckData=True
Encroach Param=-1 ,0,0, 0
BEGIN DESCRIPTION:
Multiple Run
END DESCRIPTION:
Computation Interval=1HOUR
Output Interval=1HOUR
Run HTab= 0
Run UNet= 0
Run PostProcess= 0
Run WQNet= 0
UNET Theta= 1
UNET Theta Warmup= 1
UNET ZTol= 0.02
UNET ZSATol= 0.05
UNET MxIter= 20
UNET MaxInSteps= 0
UNET DtIC= 0
UNET DtMin= 0
UNET MaxCRTS= 20
UNET WFStab= 2
UNET SFStab= 1
UNET WFX= 1
UNET SFX= 1
UNET DSS MLevel= 4
UNET DZMax Abort= 100
UNET Convert EG Bridges= 0
UNET Use Existing IB Tables=-1
UNET Froude Reduction=False
UNET Froude Limit= 1
UNET Froude Power= 10
UNET Time Slicing=0,0, 5
UNET Junction Losses=0
Instantaneous Interval=1HOUR
Write IC File= 0
Write IC File at Sim End=0
Echo Input=False
Echo Parameters=False
Echo Output=False
Write Detailed= 0
WQ AD Non Conservative
WQ ULTIMATE=-1
WQ Max Comp Step=1HOUR
WQ Output Interval=15MIN
WQ Output Selected Increments= 0
WQ Output face flow=0
WQ Output face velocity=0
WQ Output face area=0
WQ Output face dispersion=0
WQ Output cell volume=0
WQ Output cell surface area=0
WQ Output cell continuity=0
WQ Output cumulative cell continuity=0
WQ Output face conc=0
WQ Output face dconc_dx=0
WQ Output face courant=0
WQ Output face peclet=0
WQ Output face adv mass=0
WQ Output face disp mass=0
WQ Output cell mass=0
WQ Output cell source sink temp=0
WQ Output cell source sink nsm=0
WQ Output MaxMinRange=-1
WQ Daily Max Min Mean=-1
WQ Daily Range=0
WQ Daily Time=0
WQ Create Restart=0
WQ Fixed Restart=0
WQ System Summary=0
WQ Use Fixed Temperature=0
Sorting and Armoring Iterations= 10
XS Update Threshold= 0.02
Hydraulics Update Threshold= 0.02
Energy Slope Method= 1
Volume Change Method= 0
XS Weighting Method= 0
Number of US Weighted Cross Sections= 1
Number of DS Weighted Cross Sections= 1
Upstream XS Weight=0.25
Main XS Weight=0.5
Downstream XS Weight=0.25
Number of DS XS's Weighted with US Boundary= 1
Upstream Boundary Weight= 1
Weight of XSs Associated with US Boundary= 0
Number of US XS's Weighted with DS Boundary= 1
Downstream Boundary Weight= 0.5
Weight of XSs Associated with DS Boundary= 0.5
Sediment Output Level= 4
Mass or Volume Output= 0
Output Increment Type= 1
Profile and TS Output Increment= 10
XS Output Flag= 0
XS Output Increment= 10
Disregard all LS=0
Disregard all Conn=0
Disregard all Breaches=0
Disregard all Pumps=0

--- WFSJR 019.f01 (steady flow) ---

Flow Title=Multiple
Program Version=4.10
Number of Profiles= 7
Profile Names=10-year,25-year,50-year,1pct_min,100-year,1pct_plu,500-year
River Rch & RM=WFSJR 019,Reach-1         ,1644
     453     605     810     357    1079    3259    1980
Boundary for River Rch & Prof#=WFSJR 019,Reach-1         , 1
Up Type= 0
Dn Type= 3
Dn Slope=0.013
Boundary for River Rch & Prof#=WFSJR 019,Reach-1         , 2
Up Type= 0
Dn Type= 3
Dn Slope=0.013
Boundary for River Rch & Prof#=WFSJR 019,Reach-1         , 3
Up Type= 0
Dn Type= 3
Dn Slope=0.013
Boundary for River Rch & Prof#=WFSJR 019,Reach-1         , 4
Up Type= 0
Dn Type= 3
Dn Slope=0.013
Boundary for River Rch & Prof#=WFSJR 019,Reach-1         , 5
Up Type= 0
Dn Type= 3
Dn Slope=0.013
Boundary for River Rch & Prof#=WFSJR 019,Reach-1         , 6
Up Type= 0
Dn Type= 3
Dn Slope=0.013
Boundary for River Rch & Prof#=WFSJR 019,Reach-1         , 7
Up Type= 0
Dn Type= 3
Dn Slope=0.013
DSS Import GetInterval= 0
DSS Import GetPeak= 0
DSS Import FillOption= 0

--- WFSJR 019.g01 (geometry) ---

Geom Title=Existing Conditions
Program Version=4.10

River Reach=WFSJR 019       ,Reach-1
Reach XY= 30
      3740530.64     10210671.68      3740530.76     10211136.49
      3740543.26     10211159.41      3740523.12     10211253.85
      3740528.23     10211366.84      3740518.23     10211396.84
      3740528.23     10211406.84      3740548.23     10211406.84
      3740568.23     10211436.84      3740588.23     10211446.84
      3740608.23     10211486.84      3740598.23     10211556.84
      3740578.23     10211576.84      3740568.23     10211626.84
      3740548.23     10211636.84      3740538.23     10211666.84
      3740518.23     10211686.84      3740498.23     10211756.84
      3740448.23     10211806.84      3740438.23     10211806.84
      3740438.23     10211826.84      3740418.23     10211836.84
      3740418.23     10211856.84      3740388.23     10211886.84
      3740358.23     10211886.84      3740328.23     10211906.84
      3740328.23     10211936.84      3740289.52     10212004.63
       3740256.4     10212025.64      3740198.23     10212036.84

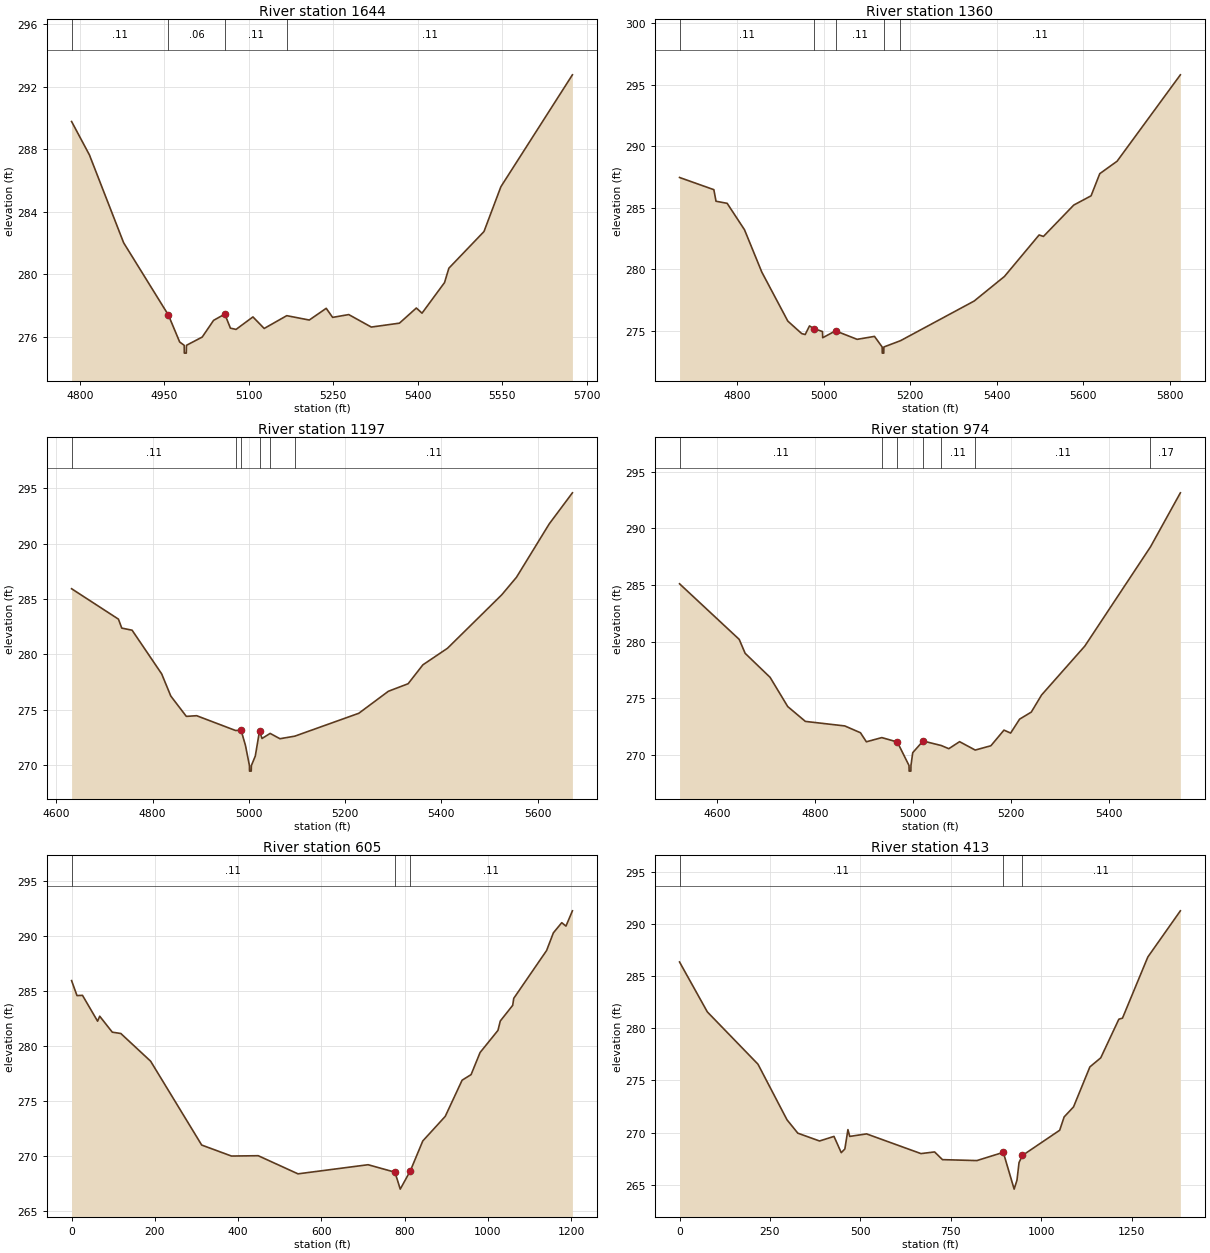
Type RM Length L Ch R = 1 ,1644    ,284,284,284
BEGIN DESCRIPTION:
WFSJR 019 2.0
END DESCRIPTION:
XS GIS Cut Line= 3
      3740316.23     10210680.15      3740528.52     10210694.44
       3741204.8     10210726.26
#Sta/Elev= 30
  4785.1  289.78  4816.8  287.64  4877.6  282.01  4957.1  277.38  4977.2  275.65
  4985.2  275.44  4985.4  274.94  4988.9  274.94  4989.2  275.44  5017.2  275.97
  5037.4  277.04  5057.3  277.44  5067.3  276.54  5077.3  276.46  5107.3  277.26
  5127.3  276.52  5167.4  277.34  5207.4  277.06  5237.5  277.81  5248.9  277.23
  5277.5  277.41  5317.6  276.61  5367.6  276.86  5397.6  277.83  5407.7   277.5
  5447.7  279.46  5455.4  280.38  5517.8  282.73  5547.8   285.6  5674.9  292.77
#Mann= 4 ,-1 , 0
  4785.1     .11       0  4957.1     .06       0  5057.3     .11       0
  5167.4     .11       0
#XS Ineff= 1 ,-1
  5237.5    5430  277.81
Permanent Ineff=
       T
Bank Sta=4957.1,5057.3
XS Rating Curve= 0 ,0
Exp/Cntr=0.3,0.1

Type RM Length L Ch R = 1 ,1360    ,163,163,163
BEGIN DESCRIPTION:
Mapping XS f95acfab
END DESCRIPTION:
XS GIS Cut Line= 2
      3740197.85     10210961.81      3741353.94     10211020.94
#Sta/Elev= 30
  4666.7  287.46    4746  286.47    4751  285.53  4776.8  285.36  4816.9  283.21
  4856.9  279.77    4917  275.79    4949  274.78  4957.1   274.7  4967.1   275.4
  4977.1  275.19  4997.1  274.94  4997.6  274.44  5027.2     275  5077.2  274.31
  5117.3  274.55    5135  273.69  5135.3  273.19  5138.8  273.19    5139  273.69
  5177.4   274.2  5347.6  277.42  5417.7  279.42  5497.8  282.79  5507.8  282.67
  5577.9  285.22  5617.9  285.97    5638  287.77    5678  288.78  5824.3   295.8
#Mann= 5 ,-1 , 0
  4666.7     .11       0  4977.1     .06       0  5027.2     .11       0
    5139     .11       0  5177.4     .11       0
Bank Sta=4977.1,5027.2
XS Rating Curve= 0 ,0
Exp/Cntr=0.3,0.1

Type RM Length L Ch R = 1 ,1197    ,223,223,223
BEGIN DESCRIPTION:
Mapping XS 825ba9ef
END DESCRIPTION:
XS GIS Cut Line= 3
      3740193.77     10211012.81      3740336.67     10211096.51
      3741191.27      10211286.2
#Sta/Elev= 30
  4631.5  285.92  4728.9  283.17  4735.8  282.36  4757.3  282.17  4818.8  278.22
  4837.7  276.22    4870  274.38  4891.5  274.44  4972.5   273.1  4983.7  273.14
  4992.9  271.76  5001.2  269.93  5001.4  269.43  5004.9  269.43  5005.2  269.93
  5013.4   270.8  5022.2  273.08  5027.3  272.38  5044.2  272.84  5064.6  272.36
  5095.4  272.59  5228.5  274.66    5290  276.65    5331  277.33  5361.7  279.04
  5412.9  280.54  5525.6  285.37  5556.3  286.96  5624.3  291.78  5672.5  294.59
#Mann= 6 ,-1 , 0
  4631.5     .11       0  4972.5     .11       0  4983.7     .06       0
  5022.2     .11       0  5044.2     .11       0  5095.4     .11       0
Bank Sta=4983.7,5022.2
XS Rating Curve= 0 ,0
Exp/Cntr=0.3,0.1

Type RM Length L Ch R = 1 ,974     ,369,369,369
BEGIN DESCRIPTION:
WFSJR 019 1.0
END DESCRIPTION:
XS GIS Cut Line= 3
      3740181.53     10211069.94      3740332.59     10211294.49
      3741047.31     10211526.62
#Sta/Elev= 30
  4523.5  285.11  4645.3   280.2  4657.4  278.97  4708.3  276.85  4744.3  274.27
  4780.3  272.96  4860.7  272.56  4892.7  271.96  4904.8  271.16  4936.3  271.53
  4967.9  271.14  4991.8  269.07  4992.1  268.57  4995.6  268.57  4995.8  269.07
  4999.4   270.2  5020.5  271.23  5057.7  270.83    5073  270.55    5095  271.17
  5126.9  270.43  5158.9  270.81  5185.6  272.19  5199.2  271.93  5217.5  273.16
  5241.3  273.78  5262.3  275.29  5350.6  279.61  5484.6  288.37  5545.6  293.14
#Mann= 7 ,-1 , 0
  4523.5     .11       0  4936.3     .11       0  4967.9     .06       0
  5020.5     .11       0  5057.7     .11       0  5126.9     .11       0
  5484.6     .17       0
Bank Sta=4967.9,5020.5
XS Rating Curve= 0 ,0
Exp/Cntr=0.3,0.1

Type RM Length L Ch R = 1 ,605     ,192,192,192
XS GIS Cut Line= 4
      3740159.71      10211055.4      3740259.33     10211522.14
      3740803.56     10211737.98      3740943.76     10211752.74
#Sta/Elev= 30
       0  285.97      13  284.61    26.2  284.63    62.5  282.28    67.6  282.73
    97.8  281.28   118.3  281.16   189.9  278.64   312.6  271.01   384.1  270.01
   448.4  270.04   543.9  268.39   712.3  269.22   776.9  268.54   789.6     267
     814  268.68   843.7  271.38   897.7  273.62   938.2  276.91   959.8  277.42
   981.4  279.43  1024.3  281.44    1030   282.3  1059.7  283.72  1062.3  284.36
  1141.2  288.71  1157.5  290.32  1177.6  291.24  1187.7  290.93  1203.2  292.32
#Mann= 3 , 0 , 0
       0     .11       0   776.9     .06       0     814     .11       0
Bank Sta=776.9,814
XS Rating Curve= 0 ,0
Exp/Cntr=0.3,0.1

Type RM Length L Ch R = 1 ,413     ,0,0,0
XS GIS Cut Line= 4
      3740139.42     10211044.33      3740156.02      10211623.6
      3740591.51     10211865.48      3740897.64     10211881.88
#Sta/Elev= 30
       0  286.37    76.8  281.58   216.8  276.56   296.9  271.23   326.9  269.94
   386.9  269.19   426.9  269.63   446.9  268.07   456.9  268.42   465.4  270.28
   470.4  269.63     517  269.87   667.2  267.98   704.9  268.14   726.7   267.4
   821.8  267.31   894.8   268.1   924.8  264.57   932.6  265.43   938.3  267.12
   947.6   267.8  1050.6  270.22    1063   271.5  1088.9  272.46  1134.1   276.3
  1164.1  277.17  1214.2  280.88  1224.2  280.98  1294.3  286.85  1384.2  291.28
#Mann= 3 , 0 , 0
       0     .11       0   894.8     .06       0   947.6     .11       0
Bank Sta=894.8,947.6
XS Rating Curve= 0 ,0
Exp/Cntr=0.3,0.1

Chan Stop Cuts=-1
Use User Specified Reach Order=0
Composite Channel Slope=5