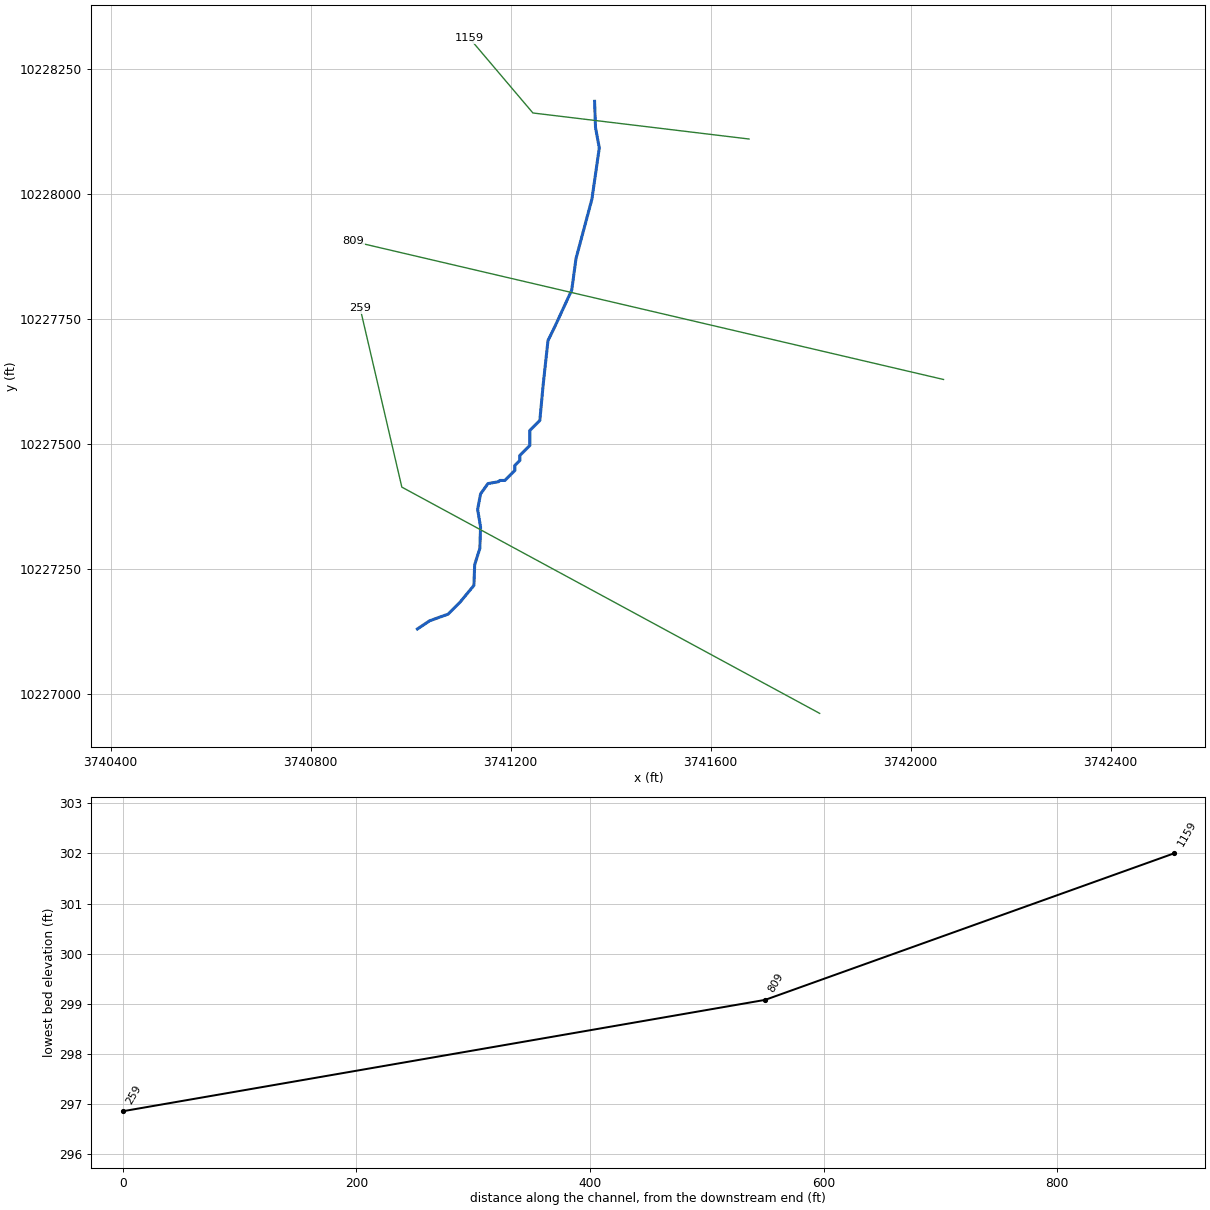
--- WFSJR 021.prj (project) ---

Proj Title=WFSJR 021 Base Level Engineering
Current Plan=p01
Default Exp/Contr=0.3,0.1
English Units
Geom File=g01
Flow File=f01
Plan File=p01
Y Axis Title=Elevation
X Axis Title(PF)=Main Channel Distance
X Axis Title(XS)=Station
BEGIN DESCRIPTION:
WFSJR 021
END DESCRIPTION:
DSS Export Rating Curves= 0
DSS Export Rating Curve Sorted= 0
DSS Export Volume Flow Curves= 0
DXF OffsetX= 0
DXF OffsetY= 0
DXF ScaleX= 1
DXF ScaleY= 10

--- WFSJR 021.p01 (plan) ---

Plan Title=Multiple Run
Program Version=4.10
Short Identifier=Multiple
Geom File=g01
Flow File=f01
Subcritical Flow
K Sum by GR= 0
Std Step Tol= 0.01
Critical Tol= 0.01
Num of Std Step Trials= 20
Max Error Tol= 0.3
Flow Tol Ratio= 0.001
Split Flow NTrial= 30
Split Flow Tol= 0.02
Split Flow Ratio= 0.02
Log Output Level= 0
Friction Slope Method= 1
Unsteady Friction Slope Method= 2
Unsteady Bridges Friction Slope Method= 1
Parabolic Critical Depth
Global Vel Dist= 1 , 1 , 1
Global Log Level= 0
CheckData=True
Encroach Param=-1 ,0,0, 0
BEGIN DESCRIPTION:
Multiple Run
END DESCRIPTION:
Computation Interval=1HOUR
Output Interval=1HOUR
Run HTab= 0
Run UNet= 0
Run PostProcess= 0
Run WQNet= 0
UNET Theta= 1
UNET Theta Warmup= 1
UNET ZTol= 0.02
UNET ZSATol= 0.05
UNET MxIter= 20
UNET MaxInSteps= 0
UNET DtIC= 0
UNET DtMin= 0
UNET MaxCRTS= 20
UNET WFStab= 2
UNET SFStab= 1
UNET WFX= 1
UNET SFX= 1
UNET DSS MLevel= 4
UNET DZMax Abort= 100
UNET Convert EG Bridges= 0
UNET Use Existing IB Tables=-1
UNET Froude Reduction=False
UNET Froude Limit= 1
UNET Froude Power= 10
UNET Time Slicing=0,0, 5
UNET Junction Losses=0
Instantaneous Interval=1HOUR
Write IC File= 0
Write IC File at Sim End=0
Echo Input=False
Echo Parameters=False
Echo Output=False
Write Detailed= 0
WQ AD Non Conservative
WQ ULTIMATE=-1
WQ Max Comp Step=1HOUR
WQ Output Interval=15MIN
WQ Output Selected Increments= 0
WQ Output face flow=0
WQ Output face velocity=0
WQ Output face area=0
WQ Output face dispersion=0
WQ Output cell volume=0
WQ Output cell surface area=0
WQ Output cell continuity=0
WQ Output cumulative cell continuity=0
WQ Output face conc=0
WQ Output face dconc_dx=0
WQ Output face courant=0
WQ Output face peclet=0
WQ Output face adv mass=0
WQ Output face disp mass=0
WQ Output cell mass=0
WQ Output cell source sink temp=0
WQ Output cell source sink nsm=0
WQ Output MaxMinRange=-1
WQ Daily Max Min Mean=-1
WQ Daily Range=0
WQ Daily Time=0
WQ Create Restart=0
WQ Fixed Restart=0
WQ System Summary=0
WQ Use Fixed Temperature=0
Sorting and Armoring Iterations= 10
XS Update Threshold= 0.02
Hydraulics Update Threshold= 0.02
Energy Slope Method= 1
Volume Change Method= 0
XS Weighting Method= 0
Number of US Weighted Cross Sections= 1
Number of DS Weighted Cross Sections= 1
Upstream XS Weight=0.25
Main XS Weight=0.5
Downstream XS Weight=0.25
Number of DS XS's Weighted with US Boundary= 1
Upstream Boundary Weight= 1
Weight of XSs Associated with US Boundary= 0
Number of US XS's Weighted with DS Boundary= 1
Downstream Boundary Weight= 0.5
Weight of XSs Associated with DS Boundary= 0.5
Sediment Output Level= 4
Mass or Volume Output= 0
Output Increment Type= 1
Profile and TS Output Increment= 10
XS Output Flag= 0
XS Output Increment= 10
Disregard all LS=0
Disregard all Conn=0
Disregard all Breaches=0
Disregard all Pumps=0

--- WFSJR 021.f01 (steady flow) ---

Flow Title=Multiple
Program Version=4.10
Number of Profiles= 7
Profile Names=10-year,25-year,50-year,1pct_min,100-year,1pct_plu,500-year
River Rch & RM=WFSJR 021,Reach-1         ,1159
     542     731     987     439    1325    4001    2468
Boundary for River Rch & Prof#=WFSJR 021,Reach-1         , 1
Up Type= 0
Dn Type= 3
Dn Slope=0.004
Boundary for River Rch & Prof#=WFSJR 021,Reach-1         , 2
Up Type= 0
Dn Type= 3
Dn Slope=0.004
Boundary for River Rch & Prof#=WFSJR 021,Reach-1         , 3
Up Type= 0
Dn Type= 3
Dn Slope=0.004
Boundary for River Rch & Prof#=WFSJR 021,Reach-1         , 4
Up Type= 0
Dn Type= 3
Dn Slope=0.004
Boundary for River Rch & Prof#=WFSJR 021,Reach-1         , 5
Up Type= 0
Dn Type= 3
Dn Slope=0.004
Boundary for River Rch & Prof#=WFSJR 021,Reach-1         , 6
Up Type= 0
Dn Type= 3
Dn Slope=0.004
Boundary for River Rch & Prof#=WFSJR 021,Reach-1         , 7
Up Type= 0
Dn Type= 3
Dn Slope=0.004
DSS Import GetInterval= 0
DSS Import GetPeak= 0
DSS Import FillOption= 0

--- WFSJR 021.g01 (geometry) ---

Geom Title=Existing Conditions
Program Version=4.10

River Reach=WFSJR 021       ,Reach-1
Reach XY= 30
      3741367.72      10228185.1      3741369.61     10228132.54
      3741377.16     10228091.94      3741362.37     10227989.35
      3741330.59      10227870.7      3741322.09     10227807.75
      3741288.41     10227734.74      3741274.57     10227706.73
      3741265.12     10227620.18      3741258.23     10227546.84
      3741238.23     10227526.84      3741238.23     10227496.84
      3741218.23     10227476.84      3741218.23     10227466.84
      3741208.23     10227456.84      3741208.23     10227446.84
      3741188.23     10227426.84      3741178.23     10227426.84
      3741175.77     10227424.39      3741154.48     10227420.63
      3741139.73     10227399.98      3741133.83     10227368.99
      3741139.73     10227333.59      3741138.26      10227290.8
      3741127.93     10227258.34      3741126.45     10227217.03
      3741098.42      10227183.1      3741074.82      10227159.5
      3741037.93     10227146.22      3741013.34     10227129.83

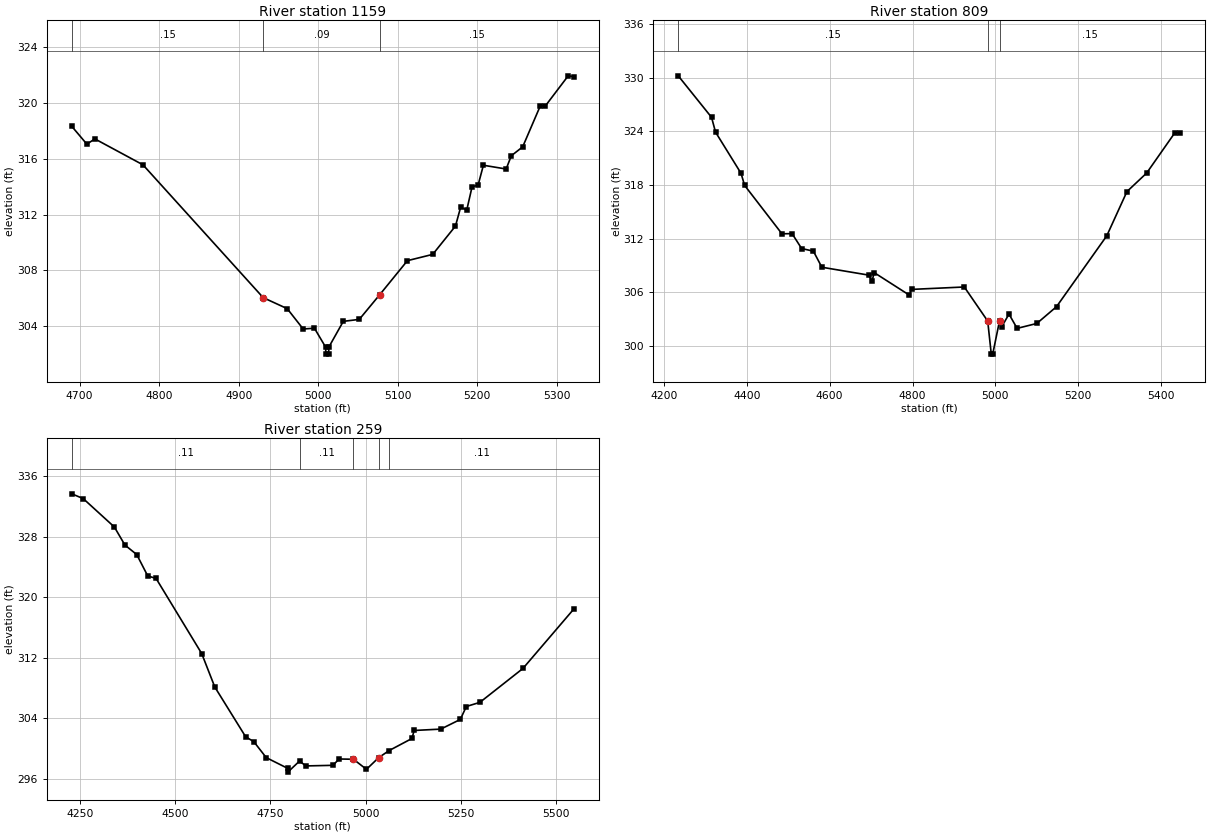
Type RM Length L Ch R = 1 ,1159    ,350,350,350
BEGIN DESCRIPTION:
WFSJR 021 2.0
END DESCRIPTION:
XS GIS Cut Line= 3
      3741676.68     10228109.71      3741244.41     10228161.79
      3741117.85     10228311.07
#Sta/Elev= 30
  4690.2  318.33  4709.2  317.05  4719.2  317.43  4779.7  315.57  4930.8  306.05
    4961  305.26  4981.1   303.8  4995.2  303.86  5009.3   302.5  5009.6     302
  5013.1     302  5013.3   302.5  5031.5  304.35  5051.6  304.49  5077.3  306.26
  5112.1   308.7  5143.9  309.15  5172.5  311.18    5179  312.53  5186.7  312.33
  5193.3  313.98    5201  314.13  5207.6  315.54  5236.2  315.27  5242.7  316.22
    5257  316.86    5279  319.78  5285.6   319.8  5314.2  321.95  5321.3  321.89
#Mann= 3 , 0 , 0
  4690.2     .15       0  4930.8     .09       0  5077.3     .15       0
Bank Sta=4930.8,5077.3
XS Rating Curve= 0 ,0
Exp/Cntr=0.3,0.1

Type RM Length L Ch R = 1 ,809     ,550,550,550
BEGIN DESCRIPTION:
Mapping XS 13ff6740
END DESCRIPTION:
XS GIS Cut Line= 2
      3742065.56     10227628.81        3740885.     10227904.86
#Sta/Elev= 30
  4234.3  330.21  4314.7  325.57  4324.4  323.91    4386   319.3  4394.5  317.96
  4484.7  312.54  4509.2  312.56  4532.3  310.89  4560.6   310.6  4581.1   308.8
  4694.1  307.92  4702.3  307.23  4707.4   308.2  4792.4  305.68  4797.6  306.32
  4925.1  306.59  4981.6  302.78  4990.2  299.08  4993.7  299.08  5010.1  302.79
  5015.2  302.12    5033  303.56  5052.6  301.96  5100.2  302.51  5147.8  304.39
  5269.2  312.32  5317.8  317.26  5365.5  319.34  5433.5  323.84  5446.7  323.83
#Mann= 3 , 0 , 0
  4234.3     .15       0  4981.6     .08       0  5010.1     .15       0
Bank Sta=4981.6,5010.1
XS Rating Curve= 0 ,0
Exp/Cntr=0.3,0.1

Type RM Length L Ch R = 1 ,259     ,0,0,0
BEGIN DESCRIPTION:
WFSJR 021 1.0
END DESCRIPTION:
XS GIS Cut Line= 3
      3741817.89     10226961.05      3740982.26     10227413.53
      3740898.92     10227771.18
#Sta/Elev= 30
  4228.6  333.67  4258.6  333.04  4340.4  329.28    4368   326.9  4399.2  325.63
  4427.9  322.81  4449.8  322.48  4569.6  312.54  4603.9  308.12  4684.7  301.55
  4706.6  300.87  4738.9  298.78  4795.2  297.36  4795.5  296.86  4826.4  298.33
  4842.6  297.68  4913.9  297.76  4930.1   298.6  4967.8  298.56  5001.9  297.23
  5033.8  298.77  5061.3  299.71  5121.3  301.31    5127  302.37  5196.9  302.55
  5248.2  303.83    5264  305.54  5299.6  306.09  5412.5  310.57  5546.1  318.44
#Mann= 5 ,-1 , 0
  4228.6     .11       0  4826.4     .11       0  4967.8     .06       0
  5033.8     .11       0  5061.3     .11       0
Bank Sta=4967.8,5033.8
XS Rating Curve= 0 ,0
Exp/Cntr=0.3,0.1

Chan Stop Cuts=-1
Use User Specified Reach Order=0
Composite Channel Slope=5