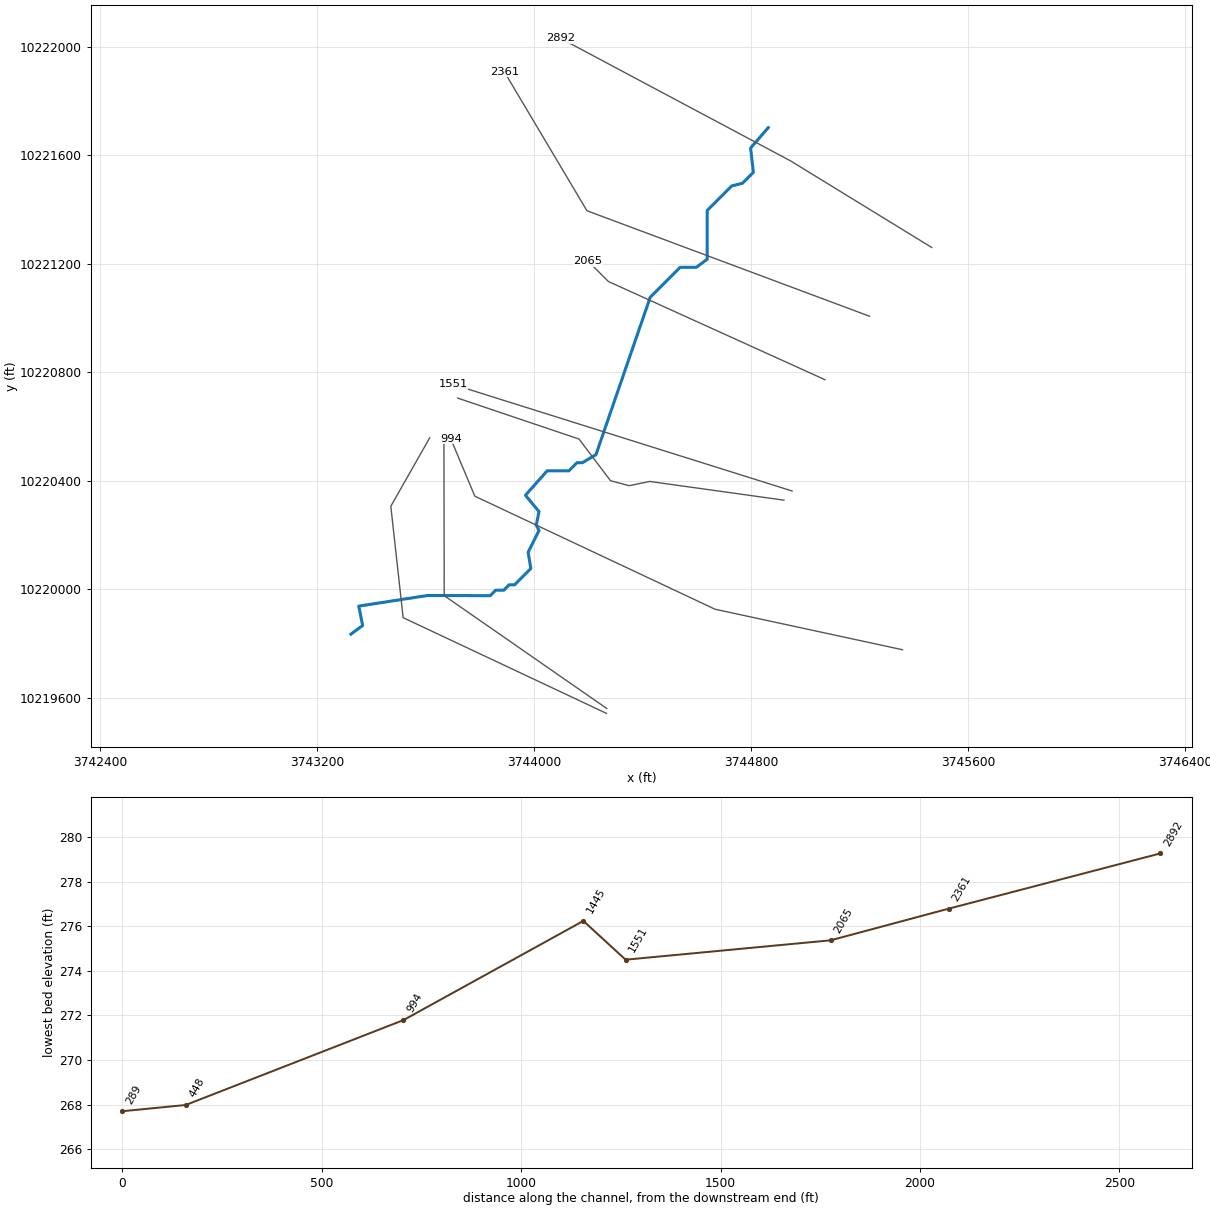
--- WFSJR 022.prj (project) ---

Proj Title=WFSJR 022 Base Level Engineering
Current Plan=p01
Default Exp/Contr=0.3,0.1
English Units
Geom File=g01
Flow File=f01
Plan File=p01
Y Axis Title=Elevation
X Axis Title(PF)=Main Channel Distance
X Axis Title(XS)=Station
BEGIN DESCRIPTION:
WFSJR 022
END DESCRIPTION:
DSS Export Rating Curves= 0
DSS Export Rating Curve Sorted= 0
DSS Export Volume Flow Curves= 0
DXF OffsetX= 0
DXF OffsetY= 0
DXF ScaleX= 1
DXF ScaleY= 10

--- WFSJR 022.p01 (plan) ---

Plan Title=Multiple Run
Program Version=4.10
Short Identifier=Multiple
Geom File=g01
Flow File=f01
Subcritical Flow
K Sum by GR= 0
Std Step Tol= 0.01
Critical Tol= 0.01
Num of Std Step Trials= 20
Max Error Tol= 0.3
Flow Tol Ratio= 0.001
Split Flow NTrial= 30
Split Flow Tol= 0.02
Split Flow Ratio= 0.02
Log Output Level= 0
Friction Slope Method= 1
Unsteady Friction Slope Method= 2
Unsteady Bridges Friction Slope Method= 1
Parabolic Critical Depth
Global Vel Dist= 1 , 1 , 1
Global Log Level= 0
CheckData=True
Encroach Param=-1 ,0,0, 0
BEGIN DESCRIPTION:
Multiple Run
END DESCRIPTION:
Computation Interval=1HOUR
Output Interval=1HOUR
Run HTab= 0
Run UNet= 0
Run PostProcess= 0
Run WQNet= 0
UNET Theta= 1
UNET Theta Warmup= 1
UNET ZTol= 0.02
UNET ZSATol= 0.05
UNET MxIter= 20
UNET MaxInSteps= 0
UNET DtIC= 0
UNET DtMin= 0
UNET MaxCRTS= 20
UNET WFStab= 2
UNET SFStab= 1
UNET WFX= 1
UNET SFX= 1
UNET DSS MLevel= 4
UNET DZMax Abort= 100
UNET Convert EG Bridges= 0
UNET Use Existing IB Tables=-1
UNET Froude Reduction=False
UNET Froude Limit= 1
UNET Froude Power= 10
UNET Time Slicing=0,0, 5
UNET Junction Losses=0
Instantaneous Interval=1HOUR
Write IC File= 0
Write IC File at Sim End=0
Echo Input=False
Echo Parameters=False
Echo Output=False
Write Detailed= 0
WQ AD Non Conservative
WQ ULTIMATE=-1
WQ Max Comp Step=1HOUR
WQ Output Interval=15MIN
WQ Output Selected Increments= 0
WQ Output face flow=0
WQ Output face velocity=0
WQ Output face area=0
WQ Output face dispersion=0
WQ Output cell volume=0
WQ Output cell surface area=0
WQ Output cell continuity=0
WQ Output cumulative cell continuity=0
WQ Output face conc=0
WQ Output face dconc_dx=0
WQ Output face courant=0
WQ Output face peclet=0
WQ Output face adv mass=0
WQ Output face disp mass=0
WQ Output cell mass=0
WQ Output cell source sink temp=0
WQ Output cell source sink nsm=0
WQ Output MaxMinRange=-1
WQ Daily Max Min Mean=-1
WQ Daily Range=0
WQ Daily Time=0
WQ Create Restart=0
WQ Fixed Restart=0
WQ System Summary=0
WQ Use Fixed Temperature=0
Sorting and Armoring Iterations= 10
XS Update Threshold= 0.02
Hydraulics Update Threshold= 0.02
Energy Slope Method= 1
Volume Change Method= 0
XS Weighting Method= 0
Number of US Weighted Cross Sections= 1
Number of DS Weighted Cross Sections= 1
Upstream XS Weight=0.25
Main XS Weight=0.5
Downstream XS Weight=0.25
Number of DS XS's Weighted with US Boundary= 1
Upstream Boundary Weight= 1
Weight of XSs Associated with US Boundary= 0
Number of US XS's Weighted with DS Boundary= 1
Downstream Boundary Weight= 0.5
Weight of XSs Associated with DS Boundary= 0.5
Sediment Output Level= 4
Mass or Volume Output= 0
Output Increment Type= 1
Profile and TS Output Increment= 10
XS Output Flag= 0
XS Output Increment= 10
Disregard all LS=0
Disregard all Conn=0
Disregard all Breaches=0
Disregard all Pumps=0

--- WFSJR 022.f01 (steady flow) ---

Flow Title=Multiple
Program Version=4.10
Number of Profiles= 7
Profile Names=10-year,25-year,50-year,1pct_min,100-year,1pct_plu,500-year
River Rch & RM=WFSJR 022,Reach-1         ,2892
     633     862    1168     522    1577    4762    2964
Boundary for River Rch & Prof#=WFSJR 022,Reach-1         , 1
Up Type= 0
Dn Type= 3
Dn Slope=0.007
Boundary for River Rch & Prof#=WFSJR 022,Reach-1         , 2
Up Type= 0
Dn Type= 3
Dn Slope=0.007
Boundary for River Rch & Prof#=WFSJR 022,Reach-1         , 3
Up Type= 0
Dn Type= 3
Dn Slope=0.007
Boundary for River Rch & Prof#=WFSJR 022,Reach-1         , 4
Up Type= 0
Dn Type= 3
Dn Slope=0.007
Boundary for River Rch & Prof#=WFSJR 022,Reach-1         , 5
Up Type= 0
Dn Type= 3
Dn Slope=0.007
Boundary for River Rch & Prof#=WFSJR 022,Reach-1         , 6
Up Type= 0
Dn Type= 3
Dn Slope=0.007
Boundary for River Rch & Prof#=WFSJR 022,Reach-1         , 7
Up Type= 0
Dn Type= 3
Dn Slope=0.007
DSS Import GetInterval= 0
DSS Import GetPeak= 0
DSS Import FillOption= 0

--- WFSJR 022.g01 (geometry) ---

Geom Title=Existing Conditions
Program Version=4.10

River Reach=WFSJR 022       ,Reach-1
Reach XY= 30
      3744863.23     10221701.84      3744798.23     10221626.84
      3744808.23     10221536.84      3744768.23     10221496.84
      3744728.23     10221486.84      3744638.23     10221396.84
      3744638.23     10221216.84      3744598.23     10221186.84
      3744538.23     10221186.84      3744428.23     10221076.84
      3744228.23     10220496.84      3744178.23     10220466.84
      3744158.23     10220466.84      3744128.23     10220436.84
      3744048.23     10220436.84      3743968.23     10220346.84
      3744018.23     10220286.84      3744008.23     10220236.84
      3744018.23     10220216.84      3743978.23     10220136.84
      3743988.23     10220076.84      3743928.23     10220016.84
      3743908.23     10220016.84      3743888.23     10219996.84
      3743858.23     10219996.84      3743838.23     10219976.84
      3743606.68     10219977.38      3743354.07     10219938.32
      3743368.23     10219866.84      3743325.27     10219835.03

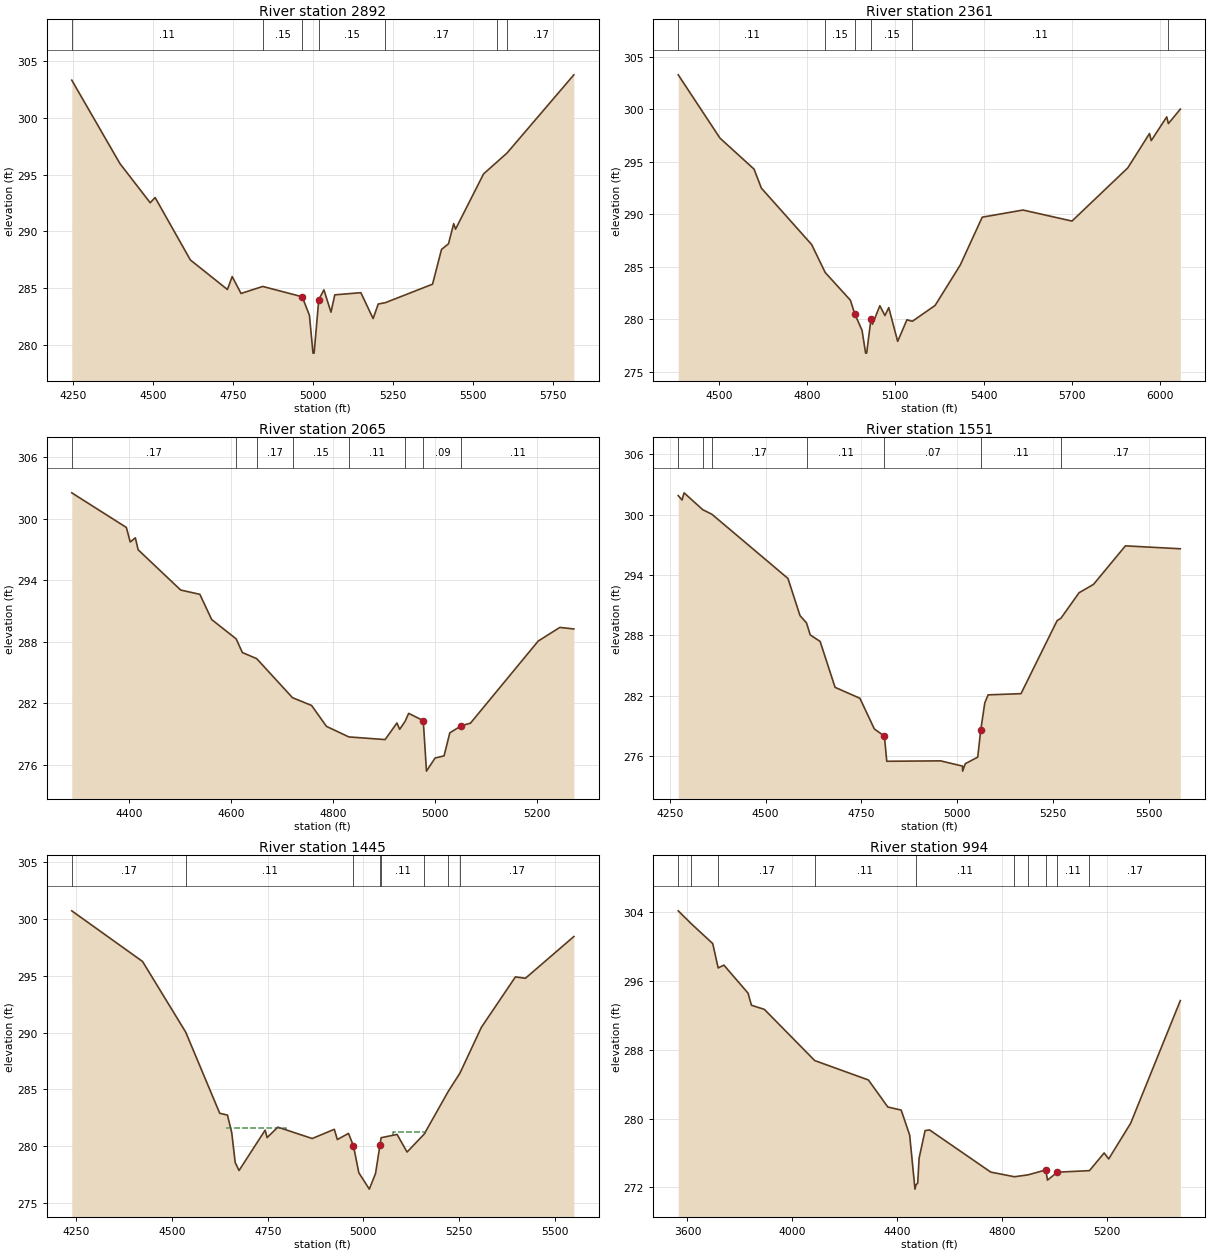
Type RM Length L Ch R = 1 ,2892    ,531,531,531
BEGIN DESCRIPTION:
WFSJR 022 3.0
END DESCRIPTION:
XS GIS Cut Line= 3
       3745465.8     10221260.12      3744944.93     10221579.59
      3744097.71     10222030.97
#Sta/Elev= 30
  4245.4  303.34    4396  295.99  4490.8  292.53  4506.2  292.99  4616.4  287.49
  4732.4  284.88  4747.4  286.02    4775  284.53    4843  285.15  4966.4  284.24
  4989.1   282.6  5000.2  279.27  5003.7  279.27  5018.3  283.99  5034.4  284.85
  5056.5  282.88  5068.4  284.41    5150   284.6  5188.3  282.32  5204.4   283.6
  5226.7  283.72  5374.3  285.35  5402.3  288.41  5424.2  288.91  5440.5  290.69
  5446.2   290.2  5534.1  295.08  5574.5  296.09  5607.5  296.92  5816.4  303.81
#Mann= 7 ,-1 , 0
  4245.4     .11       0    4843     .15       0  4966.4     .09       0
  5018.3     .15       0  5226.7     .17       0  5574.5     .11       0
  5607.5     .17       0
Bank Sta=4966.4,5018.3
XS Rating Curve= 0 ,0
Exp/Cntr=0.3,0.1

Type RM Length L Ch R = 1 ,2361    ,296,296,296
BEGIN DESCRIPTION:
Mapping XS ba7f902e
END DESCRIPTION:
XS GIS Cut Line= 3
      3745236.59     10221006.67      3744194.93     10221395.56
      3743890.37     10221907.77
#Sta/Elev= 30
  4361.3  303.26  4503.3  297.24  4619.2  294.29  4644.2  292.48  4815.3  287.11
  4861.2  284.46    4947  281.82  4961.5  280.54  4986.5  278.96  4998.7  276.79
  5002.2  276.79  5016.8  280.01  5022.1  279.54  5047.1   281.3  5064.4  280.36
  5077.4  281.12  5107.7  277.91  5139.2  279.96  5157.8  279.82  5235.2  281.33
  5320.6  285.17  5395.3  289.72    5534   290.4  5700.6  289.35  5890.4  294.41
  5964.4  297.68  5970.2     297  6022.9  299.26  6028.6  298.62  6069.1     300
#Mann= 6 ,-1 , 0
  4361.3     .11       0  4861.2     .15       0  4961.5     .09       0
  5016.8     .15       0  5157.8     .11       0  6028.6     .17       0
Bank Sta=4961.5,5016.8
XS Rating Curve= 0 ,0
Exp/Cntr=0.3,0.1

Type RM Length L Ch R = 1 ,2065    ,514,514,514
BEGIN DESCRIPTION:
Mapping XS 8eb9bea1
END DESCRIPTION:
XS GIS Cut Line= 3
      3745072.14      10220772.8      3744273.93      10221134.8
      3744198.38     10221210.34
#Sta/Elev= 30
  4288.5  302.54  4395.4  299.16    4403  297.74    4413  298.15  4418.5  296.98
  4501.8  293.05  4539.4  292.63  4562.5  290.17  4610.5  288.28  4622.6  286.95
  4650.7  286.35  4720.8  282.54  4758.2  281.78  4787.3  279.74  4831.1  278.71
  4902.2  278.45  4925.3  280.07  4930.7  279.45  4941.5  280.25  4948.3  281.01
  4976.9   280.3  4983.2  275.37    5000  276.65  5017.6  276.86  5028.9  279.11
  5051.7  279.81  5069.3  280.05    5202  288.07  5244.4   289.4  5271.8  289.25
#Mann= 8 ,-1 , 0
  4288.5     .17       0  4610.5     .11       0  4650.7     .17       0
  4720.8     .15       0  4831.1     .11       0  4941.5     .15       0
  4976.9     .09       0  5051.7     .11       0
Bank Sta=4976.9,5051.7
XS Rating Curve= 0 ,0
Exp/Cntr=0.3,0.1

Type RM Length L Ch R = 1 ,1551    ,106,106,106
BEGIN DESCRIPTION:
Mapping XS 20efc7c3
END DESCRIPTION:
XS GIS Cut Line= 2
      3744950.98     10220362.67      3743701.24     10220755.41
#Sta/Elev= 30
  4272.3  301.88  4282.2  301.45  4287.5  302.16  4336.4  300.48  4360.2  300.03
  4558.6  293.65    4590  289.96    4607  289.23  4616.7  288.04  4642.5  287.39
  4681.5  282.83  4746.3  281.74    4784  278.69  4810.2  277.98  4816.4  275.48
  4956.9  275.52    5014     275  5014.3   274.5  5021.3  275.24  5053.7  275.89
  5061.7  278.62  5072.2  281.29  5080.8  282.08  5166.6   282.2  5260.9  289.46
  5270.7  289.69  5318.1  292.23  5355.8  293.06  5439.1  296.89  5582.3   296.6
#Mann= 7 ,-1 , 0
  4272.3     .17       0  4336.4     .11       0  4360.2     .17       0
    4607     .11       0  4810.2     .07       0  5061.7     .11       0
  5270.7     .17       0
Bank Sta=4810.2,5061.7
XS Rating Curve= 0 ,0
Exp/Cntr=0.3,0.1

Type RM Length L Ch R = 1 ,1445    ,451,451,451
BEGIN DESCRIPTION:
Mapping XS 3a7dc4a3
END DESCRIPTION:
XS GIS Cut Line= 6
      3744921.09      10220328.8      3744426.27     10220397.82
      3744350.75     10220382.19      3744281.74     10220400.42
      3744165.85     10220554.07      3743718.38     10220705.02
#Sta/Elev= 30
  4237.7  300.71  4422.7  296.26  4535.7  290.04  4624.6  282.91  4644.8  282.75
  4656.1  281.18    4665  278.58  4675.1  277.88  4743.4  281.43  4748.5  280.77
  4776.5  281.69  4866.4  280.69  4924.2   281.5  4932.1   280.6  4961.3  281.14
  4974.3  280.04  4988.3  277.68  5015.7  276.24    5032  277.62  5043.5 280.093
  5046.6  280.76  5088.3  281.05  5114.4   279.5  5159.2  281.08  5222.4  284.85
  5252.7  286.44  5308.6  290.46  5397.7   294.9  5423.9  294.78  5550.5  298.45
#Mann= 8 ,-1 , 0
  4237.7     .17       0  4535.7     .11       0  4974.3     .07       0
  5043.5     .11       0  5046.6     .11       0  5159.2     .17       0
  5222.4     .11       0  5252.7     .17       0
#XS Ineff= 2 ,-1
    4640  4798.7  281.58  5078.3    5160  281.22
Permanent Ineff=
       F       F
Bank Sta=4974.3,5043.5
XS Rating Curve= 0 ,0
Exp/Cntr=0.3,0.1

Type RM Length L Ch R = 1 ,994     ,546,546,546
BEGIN DESCRIPTION:
WFSJR 022 2.0
END DESCRIPTION:
XS GIS Cut Line= 4
       3745358.1     10219777.51      3744667.16     10219926.81
      3743781.74     10220343.48      3743692.74     10220555.72
#Sta/Elev= 30
  3564.9  304.15    3615  302.64  3696.6  300.34  3717.2  297.51  3739.1  297.84
  3831.2  294.58  3844.3  293.17  3893.6  292.69  4085.6  286.74  4290.6  284.48
  4364.5  281.34  4415.6  280.98  4447.9  278.07  4468.2  271.79    4472  272.29
  4478.5  272.48    4484  275.41  4506.8   278.6    4524  278.67  4757.3  273.77
  4847.7  273.23  4899.8  273.45  4967.3  274.02  4973.7  272.84  5011.5  273.76
  5133.9  273.94  5189.9     276  5207.2   275.3  5291.1  279.45  5480.5  293.71
#Mann= 10 ,-1 , 0
  3564.9     .17       0    3615     .11       0  3717.2     .17       0
  4085.6     .11       0    4472     .11       0  4847.7     .15       0
  4899.8     .11       0  4967.3     .09       0  5011.5     .11       0
  5133.9     .17       0
#XS Ineff= 1 ,-1
    4430  4506.8   278.6
Permanent Ineff=
       F
Bank Sta=4967.3,5011.5
XS Rating Curve= 0 ,0
Exp/Cntr=0.3,0.1

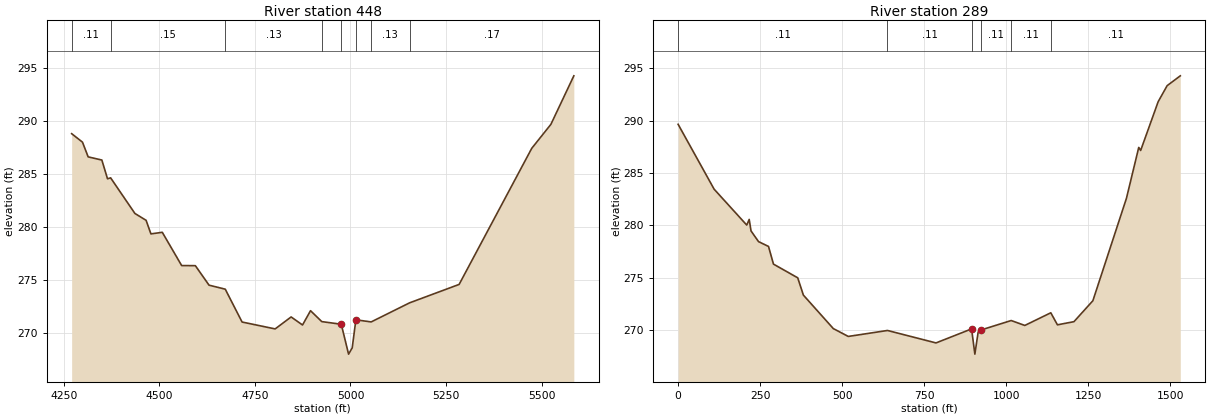
Type RM Length L Ch R = 1 ,448     ,159,159,159
BEGIN DESCRIPTION:
WFSJR 022 1.0
END DESCRIPTION:
XS GIS Cut Line= 3
      3744267.82      10219561.1      3743668.87     10219976.84
      3743667.85     10220561.04
#Sta/Elev= 30
  4270.9  288.79  4299.2  287.99  4314.1   286.6  4349.9   286.3  4364.7  284.53
  4372.8  284.62  4436.3  281.26  4465.6  280.61  4478.2  279.33  4507.9  279.48
  4558.6  276.34  4594.4  276.33  4630.2  274.49  4672.6  274.11  4716.6  271.01
  4803.1  270.36  4844.9  271.49  4874.7  270.73  4895.6  272.08    4925  271.05
    4976   270.8  4995.1  267.98  5004.6  268.57  5014.2  271.22  5054.2  271.02
  5154.6  272.82  5284.2  274.56  5474.2  287.41  5524.2  289.67  5584.2  294.25
#Mann= 8 ,-1 , 0
  4270.9     .11       0  4372.8     .15       0  4672.6     .13       0
    4925     .11       0    4976     .06       0  5014.2     .11       0
  5054.2     .13       0  5154.6     .17       0
Bank Sta=4976,5014.2
XS Rating Curve= 0 ,0
Exp/Cntr=0.3,0.1

Type RM Length L Ch R = 1 ,289     ,0,0,0
XS GIS Cut Line= 4
      3744267.08     10219542.98      3743517.53      10219895.7
      3743472.06      10220306.3      3743615.36     10220558.45
#Sta/Elev= 30
       0  289.66   109.7  283.46   209.1  280.03   216.6  280.57   222.2  279.47
     245  278.45   275.4  277.99   290.6   276.3   364.5  274.99   381.7  273.34
   472.9  270.14   518.5  269.39     638  269.96   785.8  268.77   894.2  270.11
   904.2   267.7   914.3  269.81   924.3  270.02  1014.9  270.91  1056.4  270.44
  1135.6  271.65  1155.8   270.5  1206.1   270.8  1263.8   272.8  1366.1  282.59
  1403.6  287.45  1409.4  287.16  1462.8  291.82  1490.1  293.35  1530.2  294.29
#Mann= 6 ,-1 , 0
       0     .11       0     638     .11       0   894.2     .06       0
   924.3     .11       0  1014.9     .11       0  1135.6     .11       0
Bank Sta=894.2,924.3
XS Rating Curve= 0 ,0
Exp/Cntr=0.3,0.1

Chan Stop Cuts=-1
Use User Specified Reach Order=0
Composite Channel Slope=5