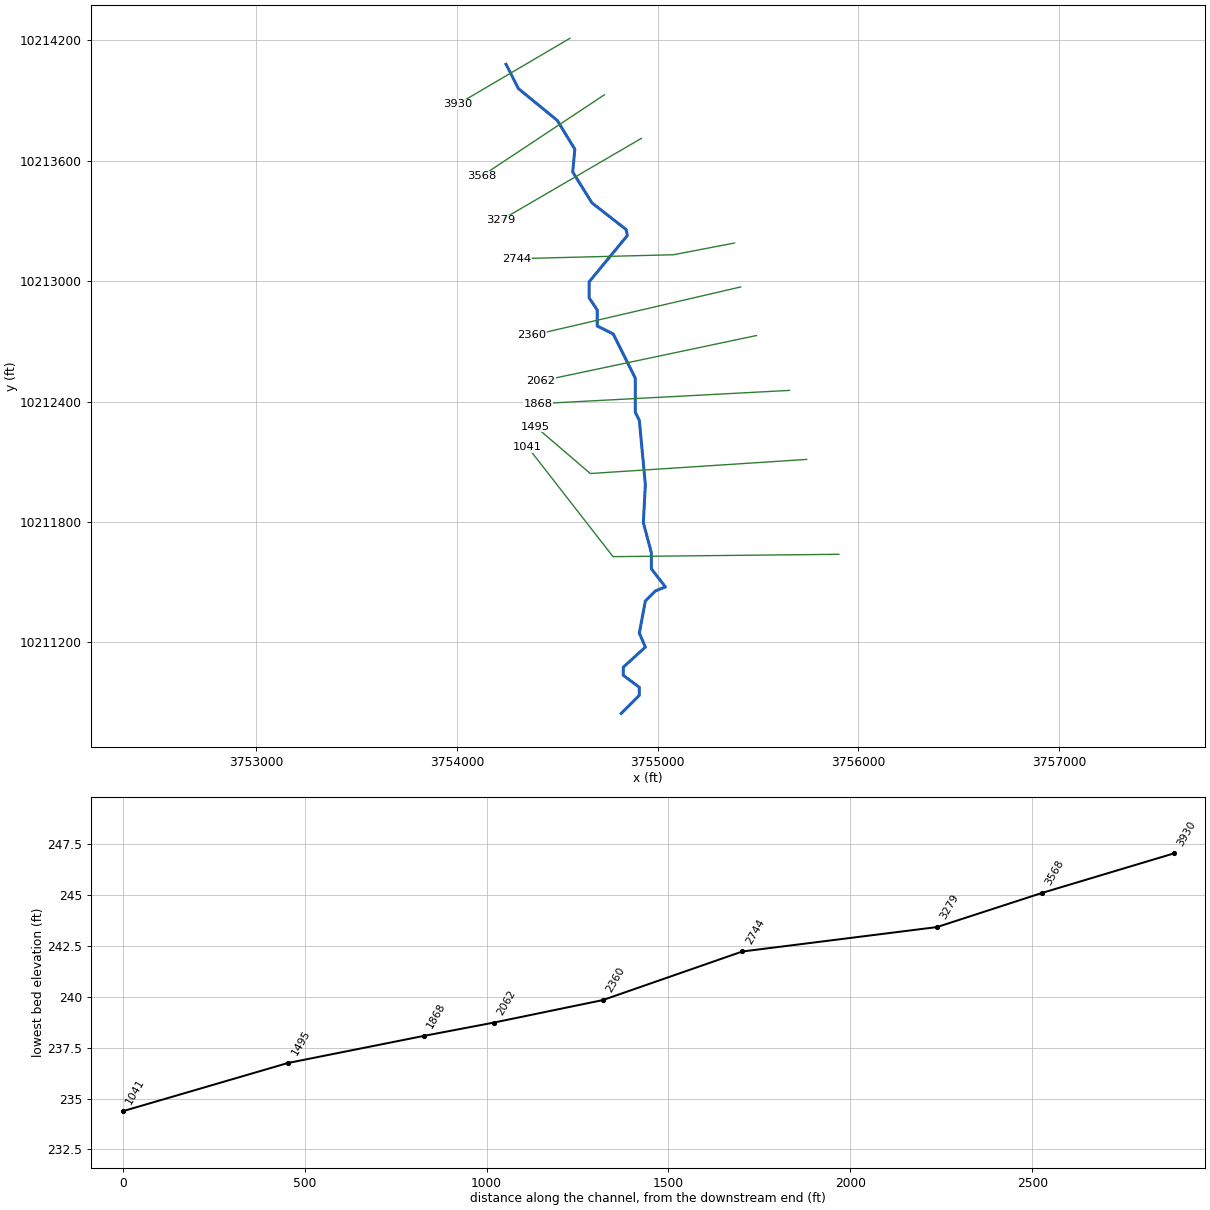
--- WFSJR 023.prj (project) ---

Proj Title=WFSJR 023 Base Level Engineering
Current Plan=p01
Default Exp/Contr=0.3,0.1
English Units
Geom File=g01
Flow File=f01
Plan File=p01
Y Axis Title=Elevation
X Axis Title(PF)=Main Channel Distance
X Axis Title(XS)=Station
BEGIN DESCRIPTION:
WFSJR 023
END DESCRIPTION:
DSS Export Rating Curves= 0
DSS Export Rating Curve Sorted= 0
DSS Export Volume Flow Curves= 0
DXF OffsetX= 0
DXF OffsetY= 0
DXF ScaleX= 1
DXF ScaleY= 10

--- WFSJR 023.p01 (plan) ---

Plan Title=Multiple Run
Program Version=4.10
Short Identifier=Multiple
Geom File=g01
Flow File=f01
Subcritical Flow
K Sum by GR= 0
Std Step Tol= 0.01
Critical Tol= 0.01
Num of Std Step Trials= 20
Max Error Tol= 0.3
Flow Tol Ratio= 0.001
Split Flow NTrial= 30
Split Flow Tol= 0.02
Split Flow Ratio= 0.02
Log Output Level= 0
Friction Slope Method= 1
Unsteady Friction Slope Method= 2
Unsteady Bridges Friction Slope Method= 1
Parabolic Critical Depth
Global Vel Dist= 1 , 1 , 1
Global Log Level= 0
CheckData=True
Encroach Param=-1 ,0,0, 0
BEGIN DESCRIPTION:
Multiple Run
END DESCRIPTION:
Computation Interval=1HOUR
Output Interval=1HOUR
Run HTab= 0
Run UNet= 0
Run PostProcess= 0
Run WQNet= 0
UNET Theta= 1
UNET Theta Warmup= 1
UNET ZTol= 0.02
UNET ZSATol= 0.05
UNET MxIter= 20
UNET MaxInSteps= 0
UNET DtIC= 0
UNET DtMin= 0
UNET MaxCRTS= 20
UNET WFStab= 2
UNET SFStab= 1
UNET WFX= 1
UNET SFX= 1
UNET DSS MLevel= 4
UNET DZMax Abort= 100
UNET Convert EG Bridges= 0
UNET Use Existing IB Tables=-1
UNET Froude Reduction=False
UNET Froude Limit= 1
UNET Froude Power= 10
UNET Time Slicing=0,0, 5
UNET Junction Losses=0
Instantaneous Interval=1HOUR
Write IC File= 0
Write IC File at Sim End=0
Echo Input=False
Echo Parameters=False
Echo Output=False
Write Detailed= 0
WQ AD Non Conservative
WQ ULTIMATE=-1
WQ Max Comp Step=1HOUR
WQ Output Interval=15MIN
WQ Output Selected Increments= 0
WQ Output face flow=0
WQ Output face velocity=0
WQ Output face area=0
WQ Output face dispersion=0
WQ Output cell volume=0
WQ Output cell surface area=0
WQ Output cell continuity=0
WQ Output cumulative cell continuity=0
WQ Output face conc=0
WQ Output face dconc_dx=0
WQ Output face courant=0
WQ Output face peclet=0
WQ Output face adv mass=0
WQ Output face disp mass=0
WQ Output cell mass=0
WQ Output cell source sink temp=0
WQ Output cell source sink nsm=0
WQ Output MaxMinRange=-1
WQ Daily Max Min Mean=-1
WQ Daily Range=0
WQ Daily Time=0
WQ Create Restart=0
WQ Fixed Restart=0
WQ System Summary=0
WQ Use Fixed Temperature=0
Sorting and Armoring Iterations= 10
XS Update Threshold= 0.02
Hydraulics Update Threshold= 0.02
Energy Slope Method= 1
Volume Change Method= 0
XS Weighting Method= 0
Number of US Weighted Cross Sections= 1
Number of DS Weighted Cross Sections= 1
Upstream XS Weight=0.25
Main XS Weight=0.5
Downstream XS Weight=0.25
Number of DS XS's Weighted with US Boundary= 1
Upstream Boundary Weight= 1
Weight of XSs Associated with US Boundary= 0
Number of US XS's Weighted with DS Boundary= 1
Downstream Boundary Weight= 0.5
Weight of XSs Associated with DS Boundary= 0.5
Sediment Output Level= 4
Mass or Volume Output= 0
Output Increment Type= 1
Profile and TS Output Increment= 10
XS Output Flag= 0
XS Output Increment= 10
Disregard all LS=0
Disregard all Conn=0
Disregard all Breaches=0
Disregard all Pumps=0

--- WFSJR 023.f01 (steady flow) ---

Flow Title=Multiple
Program Version=4.10
Number of Profiles= 7
Profile Names=10-year,25-year,50-year,1pct_min,100-year,1pct_plu,500-year
River Rch & RM=WFSJR 023,Reach-1         ,3930
     501     672     905     401    1212    3660    2243
River Rch & RM=WFSJR 023,Reach-1         ,2744
     552     744    1003     446    1346    4065    2503
Boundary for River Rch & Prof#=WFSJR 023,Reach-1         , 1
Up Type= 0
Dn Type= 3
Dn Slope=0.005
Boundary for River Rch & Prof#=WFSJR 023,Reach-1         , 2
Up Type= 0
Dn Type= 3
Dn Slope=0.005
Boundary for River Rch & Prof#=WFSJR 023,Reach-1         , 3
Up Type= 0
Dn Type= 3
Dn Slope=0.005
Boundary for River Rch & Prof#=WFSJR 023,Reach-1         , 4
Up Type= 0
Dn Type= 3
Dn Slope=0.005
Boundary for River Rch & Prof#=WFSJR 023,Reach-1         , 5
Up Type= 0
Dn Type= 3
Dn Slope=0.005
Boundary for River Rch & Prof#=WFSJR 023,Reach-1         , 6
Up Type= 0
Dn Type= 3
Dn Slope=0.005
Boundary for River Rch & Prof#=WFSJR 023,Reach-1         , 7
Up Type= 0
Dn Type= 3
Dn Slope=0.005
DSS Import GetInterval= 0
DSS Import GetPeak= 0
DSS Import FillOption= 0

--- WFSJR 023.g01 (geometry) ---

Geom Title=Existing Conditions
Program Version=4.10

River Reach=WFSJR 023       ,Reach-1
Reach XY= 30
      3754244.38     10214080.34       3754305.7     10213959.38
      3754499.46     10213800.87      3754586.92     10213657.17
      3754576.36     10213543.92      3754672.01     10213390.12
      3754842.69     10213256.96      3754848.23     10213226.84
      3754658.23     10212996.84      3754658.23     10212916.84
      3754698.23     10212856.84      3754698.23     10212776.84
      3754778.23     10212736.84      3754888.23     10212516.84
      3754888.23     10212346.84      3754908.23     10212306.84
      3754938.23     10211986.84      3754928.23     10211796.84
      3754968.23     10211646.84      3754968.23     10211566.84
      3755038.23     10211476.84      3754988.23     10211456.84
      3754938.23     10211406.84      3754908.23     10211246.84
      3754938.23     10211176.84      3754828.23     10211076.84
      3754828.23     10211036.84      3754908.23     10210976.84
      3754908.23     10210936.84      3754818.23     10210846.84

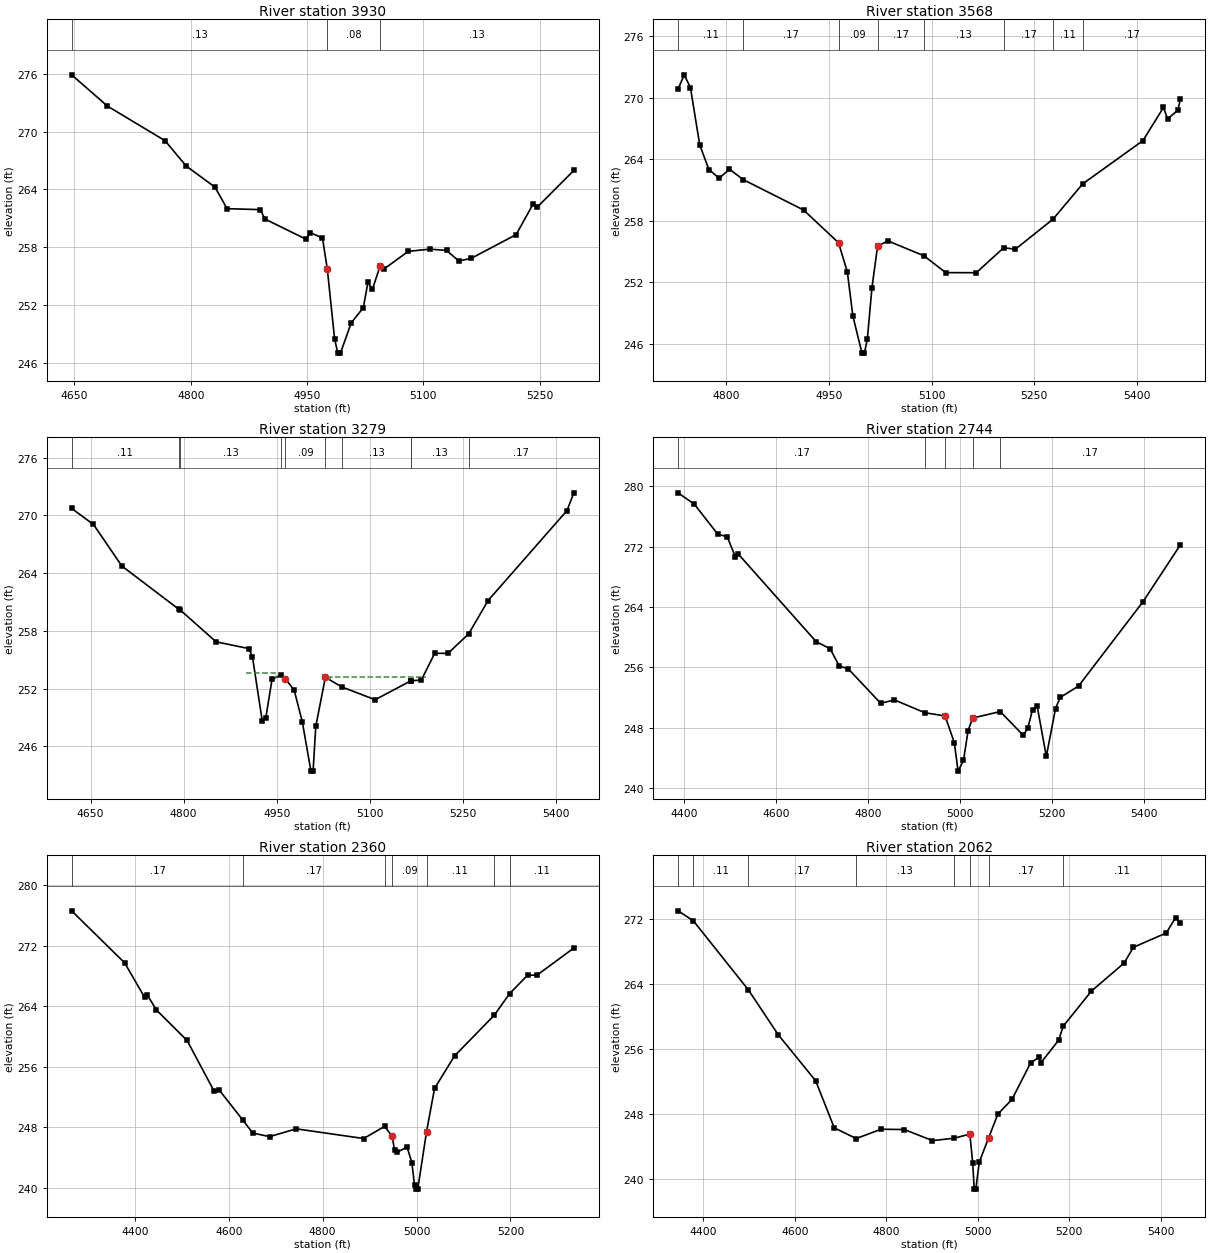
Type RM Length L Ch R = 1 ,3930    ,362,362,362
BEGIN DESCRIPTION:
WFSJR 023 7.0
END DESCRIPTION:
XS GIS Cut Line= 2
      3754562.29     10214209.69      3754003.64     10213881.53
#Sta/Elev= 30
  4646.4  275.87  4692.6  272.63  4766.9  269.05  4794.1  266.43  4831.3  264.24
  4846.9  262.01  4889.9  261.91  4895.7  260.94  4948.5  258.86  4954.3  259.54
    4970  258.96  4976.3  255.72  4985.6  248.56  4989.7  247.05  4993.2  247.05
  5007.1  250.19  5022.7  251.75  5028.6  254.37  5034.4  253.65  5044.2  256.03
    5050   255.8  5080.7  257.59  5108.6  257.82  5130.1  257.68  5145.8   256.6
  5161.5  256.85  5219.8  259.32  5241.5  262.45  5247.3  262.19  5294.3  265.97
#Mann= 3 , 0 , 0
  4646.4     .13       0  4976.3     .08       0  5044.2     .13       0
Bank Sta=4976.3,5044.2
XS Rating Curve= 0 ,0
Exp/Cntr=0.3,0.1

Type RM Length L Ch R = 1 ,3568    ,289,289,289
BEGIN DESCRIPTION:
Mapping XS e4230154
END DESCRIPTION:
XS GIS Cut Line= 2
      3754734.17     10213928.44      3754121.83     10213522.81
#Sta/Elev= 30
  4729.3  270.83  4738.2  272.21  4747.3  270.97  4760.9  265.39  4774.3  262.99
  4789.4  262.14  4804.4  263.02  4824.4  262.01  4912.7  259.05  4963.9  255.86
  4976.8  253.02  4984.9  248.72  4998.2  245.11  5001.7  245.11    5006  246.44
  5012.8  251.48    5021  255.51  5036.1  256.04  5088.8  254.59  5120.7  252.95
  5165.4  252.94  5205.5  255.37  5222.6  255.23  5277.7  258.16    5321  261.59
  5409.1   265.8  5439.2  269.03  5445.2  267.92  5460.2  268.76  5463.8  269.82
#Mann= 8 ,-1 , 0
  4729.3     .11       0  4824.4     .17       0  4963.9     .09       0
    5021     .17       0  5088.8     .13       0  5205.5     .17       0
  5277.7     .11       0    5321     .17       0
#XS Ineff= 1 ,-1
  5036.1    5240  256.04
Permanent Ineff=
       F
Bank Sta=4963.9,5021
XS Rating Curve= 0 ,0
Exp/Cntr=0.3,0.1

Type RM Length L Ch R = 1 ,3279    ,535,535,535
BEGIN DESCRIPTION:
WFSJR 023 6.0
END DESCRIPTION:
XS GIS Cut Line= 2
      3754917.85     10213711.07       3754218.5     10213303.41
#Sta/Elev= 30
  4619.5  270.73  4654.7  269.06  4700.5  264.74  4792.5  260.24  4793.7  260.22
  4852.3  256.87  4905.3  256.16    4911  255.28  4926.8  248.62  4932.5  248.98
  4942.5  252.96  4957.7  253.44    4964  253.04  4978.3  251.82  4991.3  248.56
  5005.2  243.43  5008.7  243.43    5013  248.08  5028.5  253.17  5055.4  252.17
  5108.7  250.85  5166.7  252.83  5167.3  252.82  5183.2   252.9  5204.7  255.67
  5226.2  255.67  5259.5   257.7  5290.8  261.16    5418  270.51    5429  272.35
#Mann= 10 ,-1 , 0
  4619.5     .11       0  4792.5     .17       0  4793.7     .13       0
  4957.7     .17       0    4964     .09       0  5028.5     .17       0
  5055.4     .13       0  5166.7     .17       0  5167.3     .13       0
  5259.5     .17       0
#XS Ineff= 2 ,-1
    4900  4948.3  253.63  5036.2    5190  253.24
Permanent Ineff=
       F       F
Bank Sta=4964,5028.5
XS Rating Curve= 0 ,0
Exp/Cntr=0.3,0.1

Type RM Length L Ch R = 1 ,2744    ,384,384,384
BEGIN DESCRIPTION:
WFSJR 023 5.0
END DESCRIPTION:
XS GIS Cut Line= 3
      3755382.59     10213190.14      3755077.88     10213131.54
      3754296.61     10213112.01
#Sta/Elev= 30
  4387.1  279.14  4422.5  277.62  4473.4  273.65  4493.8  273.32  4511.8  270.61
  4516.9  271.09  4687.2   259.4  4717.4  258.47  4737.4  256.19  4757.4  255.77
  4827.5  251.23  4857.5  251.67  4923.8  249.97  4967.5  249.55  4987.5  246.02
  4995.8  242.23  5007.5  243.64  5017.5  247.61  5027.5  249.27  5087.5  250.13
  5137.6  246.97  5147.6  247.99  5157.6  250.37  5167.6  250.89  5187.6  244.18
  5207.6  250.53  5217.6     252  5257.6  253.51  5397.6  264.68  5478.9  272.23
#Mann= 5 ,-1 , 0
  4387.1     .17       0  4923.8     .11       0  4967.5     .06       0
  5027.5     .11       0  5087.5     .17       0
#XS Ineff= 2 ,-1
  5087.5    5158  250.13  5167.6    5215  250.89
Permanent Ineff=
       F       F
Bank Sta=4967.5,5027.5
XS Rating Curve= 0 ,0
Exp/Cntr=0.3,0.1

Type RM Length L Ch R = 1 ,2360    ,298,298,298
BEGIN DESCRIPTION:
WFSJR 023 4.0
END DESCRIPTION:
XS GIS Cut Line= 2
      3755413.79     10212971.38      3754371.81     10212729.42
#Sta/Elev= 30
  4265.4  276.63  4378.3  269.75  4420.9  265.19  4426.1  265.54    4446  263.52
  4511.3  259.49  4569.2  252.75  4579.5  252.96  4630.6  248.92  4651.3  247.25
    4687  246.78  4743.7  247.81  4887.5  246.53  4931.9  248.13    4948  246.85
  4953.1  245.04  4959.3  244.75  4979.9   245.4  4990.1  243.34  4995.7  240.37
  4999.1  239.84  5002.6  239.84  5021.4  247.45  5038.4  253.15    5081  257.45
  5165.5  262.82  5198.1  265.67  5236.5  268.12  5256.7  268.13  5335.1  271.71
#Mann= 7 ,-1 , 0
  4265.4     .17       0  4630.6     .17       0  4931.9     .17       0
    4948     .09       0  5021.4     .11       0  5165.5     .17       0
  5198.1     .11       0
Bank Sta=4948,5021.4
XS Rating Curve= 0 ,0
Exp/Cntr=0.3,0.1

Type RM Length L Ch R = 1 ,2062    ,194,194,194
BEGIN DESCRIPTION:
WFSJR 023 3.0
END DESCRIPTION:
XS GIS Cut Line= 2
      3755491.95      10212729.2      3754417.68     10212502.63
#Sta/Elev= 30
    4345  272.98  4378.3  271.75  4498.8  263.24  4563.8  257.74  4645.6  252.08
  4686.4  246.28  4734.3  244.96  4788.6  246.11  4839.7  246.07  4901.1  244.71
  4947.3  244.99  4982.8  245.51    4989  241.99  4992.4  238.74  4995.9  238.74
  5003.3  242.05  5023.7  245.03  5044.1  247.98  5074.8  249.77  5115.7  254.27
  5133.2  254.94  5138.4   254.3    5177  257.07  5186.9  258.78  5248.5   263.1
  5320.1  266.56  5340.5   268.5  5412.1  270.25  5432.5  272.13  5442.9  271.53
#Mann= 8 ,-1 , 0
    4345     .17       0  4378.3     .11       0  4498.8     .17       0
  4734.3     .13       0  4947.3     .17       0  4982.8     .09       0
  5023.7     .17       0  5186.9     .11       0
Bank Sta=4982.8,5023.7
XS Rating Curve= 0 ,0
Exp/Cntr=0.3,0.1

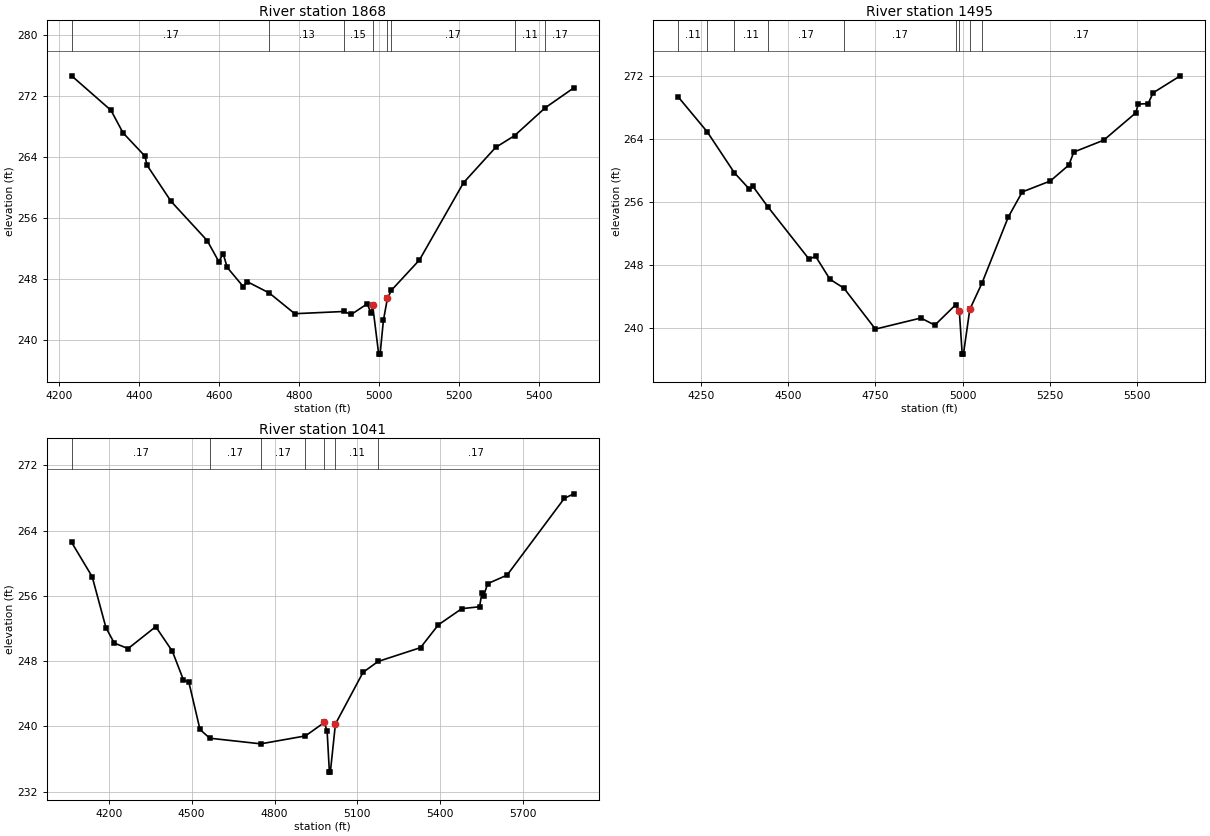
Type RM Length L Ch R = 1 ,1868    ,373,373,373
BEGIN DESCRIPTION:
Mapping XS d8417af7
END DESCRIPTION:
XS GIS Cut Line= 2
      3755656.05     10212455.76      3754402.51     10212389.38
#Sta/Elev= 30
  4231.1  274.64  4329.4  270.11  4359.5  267.15  4414.5  264.08  4419.6  262.89
  4479.6  258.15  4569.8     253  4599.1  250.22  4609.8  251.29  4619.8  249.48
  4659.9  246.96  4669.9   247.6  4725.1  246.11  4788.8  243.39  4910.7  243.68
  4930.3   243.3  4970.3   244.7  4978.5  243.52  4983.5  244.47  4998.6  238.08
  5002.1  238.08  5010.4  242.53  5020.4  245.39  5030.4  246.47  5100.5  250.45
  5210.7   260.6  5290.8  265.23  5338.2  266.78  5415.1  270.45  5486.4  273.06
#Mann= 8 ,-1 , 0
  4231.1     .17       0  4725.1     .13       0  4910.7     .15       0
  4983.5     .09       0  5020.4     .15       0  5030.4     .17       0
  5338.2     .11       0  5415.1     .17       0
Bank Sta=4983.5,5020.4
XS Rating Curve= 0 ,0
Exp/Cntr=0.3,0.1

Type RM Length L Ch R = 1 ,1495    ,454,454,454
BEGIN DESCRIPTION:
WFSJR 023 2.0
END DESCRIPTION:
XS GIS Cut Line= 3
       3755741.9     10212112.01      3754663.82      10212041.7
      3754391.61     10212275.03
#Sta/Elev= 30
  4184.6  269.33    4268   264.9  4345.7  259.72  4389.1  257.63  4399.1  257.98
  4441.8   255.4  4559.4   248.8  4578.8  249.12  4619.6  246.23  4659.7   245.1
  4749.8  239.92  4880.1  241.32  4920.2  240.42  4980.3  243.02  4990.4  242.15
  4998.6  236.75  5002.1  236.75  5020.4  242.42  5055.3  245.75  5130.7  254.12
  5170.7  257.29  5250.9  258.67  5304.1  260.69  5318.4  262.34    5404  263.84
  5496.2  267.31  5502.8  268.41  5531.3  268.47  5545.6  269.84  5623.5  271.99
#Mann= 9 ,-1 , 0
  4184.6     .11       0    4268     .17       0  4345.7     .11       0
  4441.8     .17       0  4659.7     .17       0  4980.3     .13       0
  4990.4     .09       0  5020.4     .15       0  5055.3     .17       0
Bank Sta=4990.4,5020.4
XS Rating Curve= 0 ,0
Exp/Cntr=0.3,0.1

Type RM Length L Ch R = 1 ,1041    ,0,0,0
BEGIN DESCRIPTION:
WFSJR 023 1.0
END DESCRIPTION:
XS GIS Cut Line= 3
      3755902.08     10211639.35       3754777.1     10211627.64
      3754352.07     10212173.55
#Sta/Elev= 30
  4066.1  262.55  4140.3  258.35  4190.3  252.08  4220.3  250.21  4270.3  249.53
  4370.3  252.22  4430.3  249.21  4470.3  245.71  4490.4  245.38  4530.4  239.61
  4565.7  238.54  4750.4  237.85  4911.8  238.82  4980.4  240.47  4990.4   239.4
  4998.6  234.38  5002.1  234.38  5020.4  240.28  5120.4  246.62  5174.6  247.95
  5328.4  249.65  5392.7  252.44  5477.7  254.43    5542  254.66  5550.1  256.33
  5556.4  255.94  5570.9  257.49  5641.5  258.54  5848.7  267.96    5883  268.51
#Mann= 7 ,-1 , 0
  4066.1     .17       0  4565.7     .17       0  4750.4     .17       0
  4911.8     .11       0  4980.4     .06       0  5020.4     .11       0
  5174.6     .17       0
Bank Sta=4980.4,5020.4
XS Rating Curve= 0 ,0
Exp/Cntr=0.3,0.1

Chan Stop Cuts=-1
Use User Specified Reach Order=0
Composite Channel Slope=5