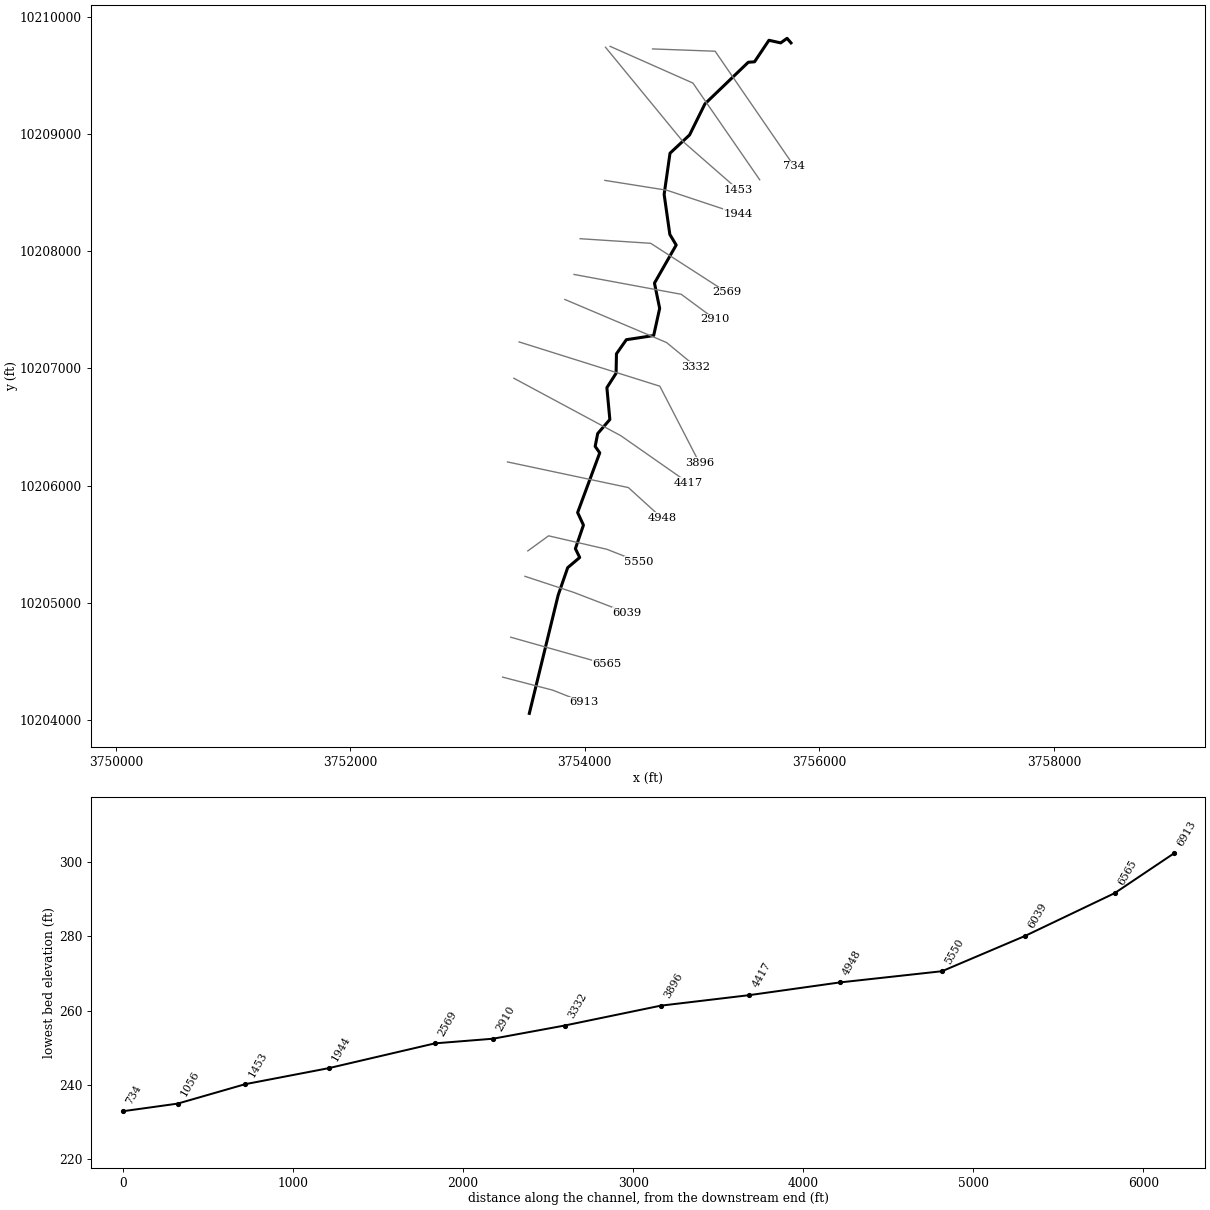
--- WFSJR 024.prj (project) ---

Proj Title=WFSJR 024 Base Level Engineering
Current Plan=p01
Default Exp/Contr=0.3,0.1
English Units
Geom File=g01
Flow File=f01
Plan File=p01
Y Axis Title=Elevation
X Axis Title(PF)=Main Channel Distance
X Axis Title(XS)=Station
BEGIN DESCRIPTION:
WFSJR 024
END DESCRIPTION:
DSS Export Rating Curves= 0
DSS Export Rating Curve Sorted= 0
DSS Export Volume Flow Curves= 0
DXF OffsetX= 0
DXF OffsetY= 0
DXF ScaleX= 1
DXF ScaleY= 10

--- WFSJR 024.p01 (plan) ---

Plan Title=Multiple Run
Program Version=4.10
Short Identifier=Multiple
Geom File=g01
Flow File=f01
Subcritical Flow
K Sum by GR= 0
Std Step Tol= 0.01
Critical Tol= 0.01
Num of Std Step Trials= 20
Max Error Tol= 0.3
Flow Tol Ratio= 0.001
Split Flow NTrial= 30
Split Flow Tol= 0.02
Split Flow Ratio= 0.02
Log Output Level= 0
Friction Slope Method= 1
Unsteady Friction Slope Method= 2
Unsteady Bridges Friction Slope Method= 1
Parabolic Critical Depth
Global Vel Dist= 1 , 1 , 1
Global Log Level= 0
CheckData=True
Encroach Param=-1 ,0,0, 0
BEGIN DESCRIPTION:
Multiple Run
END DESCRIPTION:
Computation Interval=1HOUR
Output Interval=1HOUR
Run HTab= 0
Run UNet= 0
Run PostProcess= 0
Run WQNet= 0
UNET Theta= 1
UNET Theta Warmup= 1
UNET ZTol= 0.02
UNET ZSATol= 0.05
UNET MxIter= 20
UNET MaxInSteps= 0
UNET DtIC= 0
UNET DtMin= 0
UNET MaxCRTS= 20
UNET WFStab= 2
UNET SFStab= 1
UNET WFX= 1
UNET SFX= 1
UNET DSS MLevel= 4
UNET DZMax Abort= 100
UNET Convert EG Bridges= 0
UNET Use Existing IB Tables=-1
UNET Froude Reduction=False
UNET Froude Limit= 1
UNET Froude Power= 10
UNET Time Slicing=0,0, 5
UNET Junction Losses=0
Instantaneous Interval=1HOUR
Write IC File= 0
Write IC File at Sim End=0
Echo Input=False
Echo Parameters=False
Echo Output=False
Write Detailed= 0
WQ AD Non Conservative
WQ ULTIMATE=-1
WQ Max Comp Step=1HOUR
WQ Output Interval=15MIN
WQ Output Selected Increments= 0
WQ Output face flow=0
WQ Output face velocity=0
WQ Output face area=0
WQ Output face dispersion=0
WQ Output cell volume=0
WQ Output cell surface area=0
WQ Output cell continuity=0
WQ Output cumulative cell continuity=0
WQ Output face conc=0
WQ Output face dconc_dx=0
WQ Output face courant=0
WQ Output face peclet=0
WQ Output face adv mass=0
WQ Output face disp mass=0
WQ Output cell mass=0
WQ Output cell source sink temp=0
WQ Output cell source sink nsm=0
WQ Output MaxMinRange=-1
WQ Daily Max Min Mean=-1
WQ Daily Range=0
WQ Daily Time=0
WQ Create Restart=0
WQ Fixed Restart=0
WQ System Summary=0
WQ Use Fixed Temperature=0
Sorting and Armoring Iterations= 10
XS Update Threshold= 0.02
Hydraulics Update Threshold= 0.02
Energy Slope Method= 1
Volume Change Method= 0
XS Weighting Method= 0
Number of US Weighted Cross Sections= 1
Number of DS Weighted Cross Sections= 1
Upstream XS Weight=0.25
Main XS Weight=0.5
Downstream XS Weight=0.25
Number of DS XS's Weighted with US Boundary= 1
Upstream Boundary Weight= 1
Weight of XSs Associated with US Boundary= 0
Number of US XS's Weighted with DS Boundary= 1
Downstream Boundary Weight= 0.5
Weight of XSs Associated with DS Boundary= 0.5
Sediment Output Level= 4
Mass or Volume Output= 0
Output Increment Type= 1
Profile and TS Output Increment= 10
XS Output Flag= 0
XS Output Increment= 10
Disregard all LS=0
Disregard all Conn=0
Disregard all Breaches=0
Disregard all Pumps=0

--- WFSJR 024.f01 (steady flow) ---

Flow Title=Multiple
Program Version=4.10
Number of Profiles= 7
Profile Names=10-year,25-year,50-year,1pct_min,100-year,1pct_plu,500-year
River Rch & RM=WFSJR 024,Reach-1         ,6913
     721    1005    1387     631    1907    5759    3722
Boundary for River Rch & Prof#=WFSJR 024,Reach-1         , 1
Up Type= 0
Dn Type= 3
Dn Slope=0.003
Boundary for River Rch & Prof#=WFSJR 024,Reach-1         , 2
Up Type= 0
Dn Type= 3
Dn Slope=0.003
Boundary for River Rch & Prof#=WFSJR 024,Reach-1         , 3
Up Type= 0
Dn Type= 3
Dn Slope=0.003
Boundary for River Rch & Prof#=WFSJR 024,Reach-1         , 4
Up Type= 0
Dn Type= 3
Dn Slope=0.003
Boundary for River Rch & Prof#=WFSJR 024,Reach-1         , 5
Up Type= 0
Dn Type= 3
Dn Slope=0.003
Boundary for River Rch & Prof#=WFSJR 024,Reach-1         , 6
Up Type= 0
Dn Type= 3
Dn Slope=0.003
Boundary for River Rch & Prof#=WFSJR 024,Reach-1         , 7
Up Type= 0
Dn Type= 3
Dn Slope=0.003
DSS Import GetInterval= 0
DSS Import GetPeak= 0
DSS Import FillOption= 0

--- WFSJR 024.g01 (geometry) ---

Geom Title=Existing Conditions
Program Version=4.10

River Reach=WFSJR 024       ,Reach-1
Reach XY= 30
       3753526.9     10204058.83      3753772.75     10205066.82
      3753854.05     10205301.44       3753956.5     10205388.26
      3753919.76     10205463.53       3753988.4     10205664.33
      3753938.75     10205771.65      3754127.41     10206280.54
       3754088.3     10206335.85      3754109.88      10206445.1
      3754213.53     10206564.97      3754188.26     10206836.53
      3754266.79      10206959.3      3754269.92     10207125.23
       3754354.2     10207245.53       3754587.3     10207281.06
      3754638.36     10207512.54      3754594.11     10207728.17
      3754779.37     10208052.91      3754725.13     10208143.08
      3754676.52     10208484.72      3754726.61     10208835.92
      3754893.32     10208991.63      3755024.41     10209256.68
      3755394.16     10209611.71      3755447.35     10209615.49
      3755570.29     10209799.13      3755670.14     10209776.79
      3755724.99     10209815.64      3755758.23     10209776.84

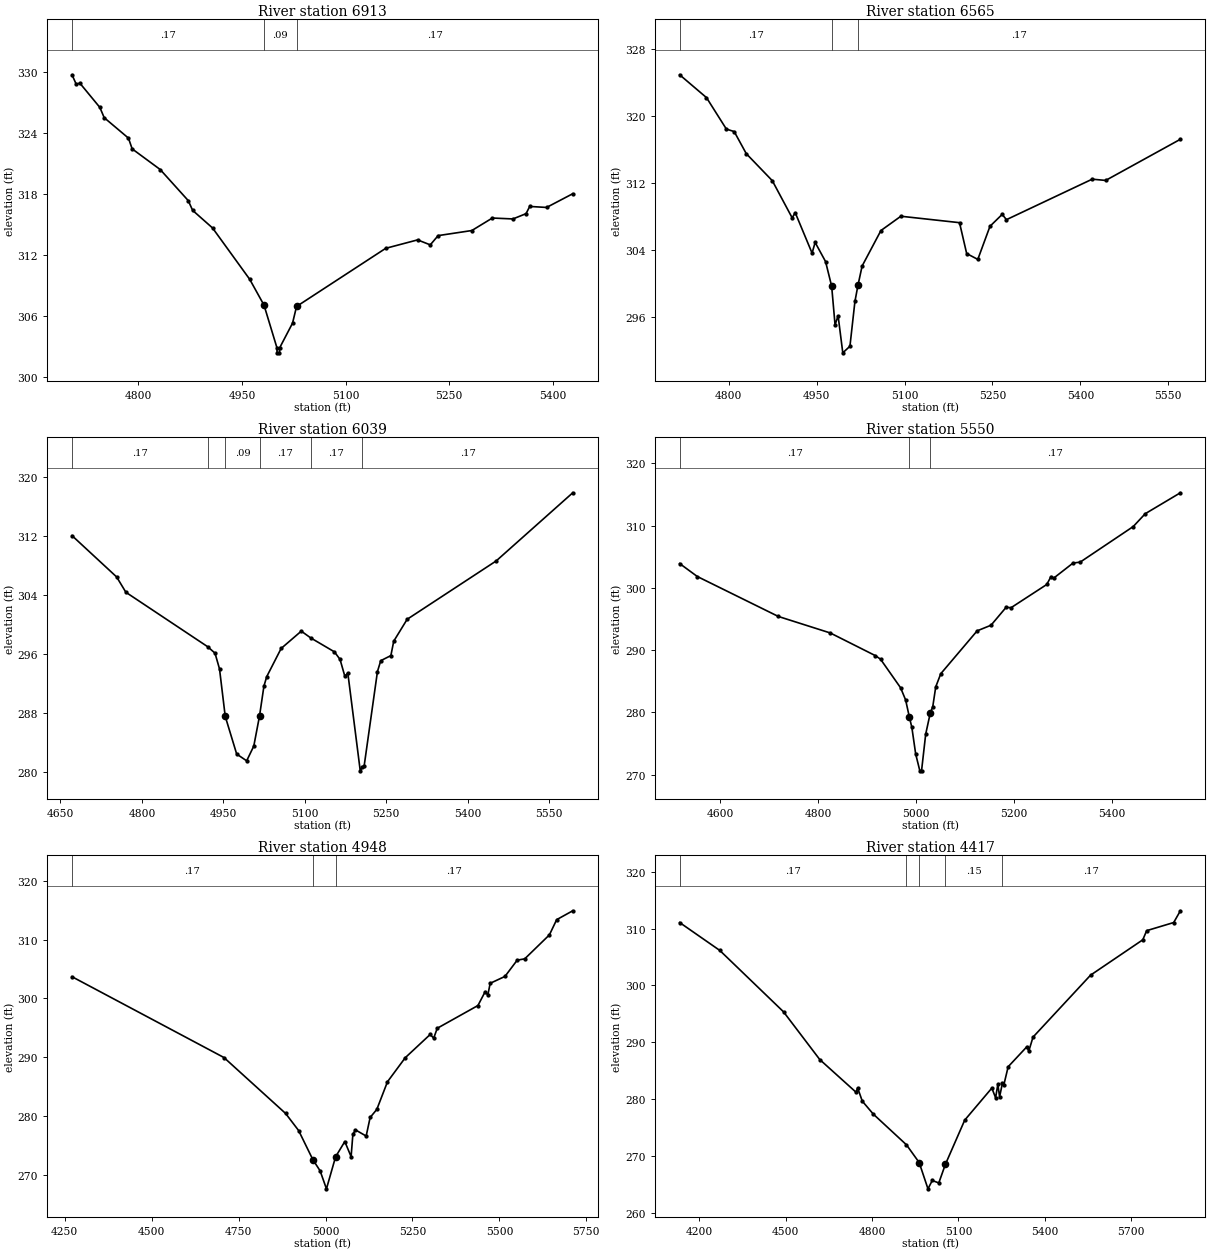
Type RM Length L Ch R = 1 ,6913    ,348,348,348
BEGIN DESCRIPTION:
WFSJR 024 14.0
END DESCRIPTION:
XS GIS Cut Line= 3
       3753298.8     10204368.09      3753725.89     10204256.98
      3753989.77     10204152.81
#Sta/Elev= 30
  4703.8  329.74  4709.9  328.81  4715.1  328.92  4744.1  326.53  4750.4  325.52
  4785.5  323.51  4790.9  322.45  4831.5  320.42    4872  317.37  4878.5   316.4
  4907.3  314.67  4961.1  309.62  4981.8  307.08  5000.5  302.89  5000.7  302.39
  5004.2  302.39  5004.5  302.89  5023.1  305.31  5028.9  306.95    5158  312.67
  5204.2   313.5  5222.5  313.01  5233.9  313.92  5282.7  314.42  5312.4  315.65
  5342.2  315.56  5361.2  316.08  5366.5  316.79  5390.9  316.69  5428.8  318.04
#Mann= 3 , 0 , 0
  4703.8     .17       0  4981.8     .09       0  5028.9     .17       0
Bank Sta=4981.8,5028.9
XS Rating Curve= 0 ,0
Exp/Cntr=0.3,0.1

Type RM Length L Ch R = 1 ,6565    ,526,526,526
BEGIN DESCRIPTION:
WFSJR 024 13.0
END DESCRIPTION:
XS GIS Cut Line= 2
      3753368.24     10204708.37      3754190.51     10204475.91
#Sta/Elev= 30
  4716.2  324.92    4762  322.19  4795.9  318.43  4809.3  318.13  4829.9  315.49
  4874.3  312.26  4908.2  307.82  4913.4  308.44  4942.2   303.6  4947.4  304.88
  4965.2  302.59  4975.6  299.65  4981.4  295.02  4986.6  296.11  4994.6  291.68
  5006.8  292.47  5015.3  297.82  5020.5  299.76  5027.6  302.06  5059.7   306.3
  5093.7  308.01  5193.8  307.24    5206  303.55    5225  302.85  5245.8  306.81
  5266.6  308.23  5273.9   307.6  5420.2  312.44  5443.2  312.29  5570.7  317.21
#Mann= 3 , 0 , 0
  4716.2     .17       0  4975.6     .09       0  5020.5     .17       0
Bank Sta=4975.6,5020.5
XS Rating Curve= 0 ,0
Exp/Cntr=0.3,0.1

Type RM Length L Ch R = 1 ,6039    ,489,489,489
BEGIN DESCRIPTION:
WFSJR 024 12.0
END DESCRIPTION:
XS GIS Cut Line= 3
       3753489.8      10205227.5      3753906.44     10205090.31
      3754357.86     10204916.69
#Sta/Elev= 30
  4671.3   312.1  4753.5  306.49  4770.5  304.41  4921.1  297.02  4934.7  296.14
    4943  293.99  4953.5  287.56  4974.6  282.44    4993  281.52  5006.1  283.52
  5016.7  287.62  5024.8  291.67    5030  292.96  5056.5  296.78  5093.6  299.13
    5111  298.21  5154.6  296.32    5165  295.29  5173.9  292.98  5179.3  293.46
  5202.2  280.16  5205.9  280.66  5209.3  280.77  5233.9  293.65    5240  295.12
  5258.6  295.81  5263.9  297.77  5288.6  300.74  5452.5  308.66  5593.6  317.92
#Mann= 6 ,-1 , 0
  4671.3     .17       0  4921.1     .15       0  4953.5     .09       0
  5016.7     .17       0    5111     .17       0  5205.9     .17       0
#XS Ineff= 1 ,-1
  5093.6    5290  299.13
Permanent Ineff=
       F
Bank Sta=4953.5,5016.7
XS Rating Curve= 0 ,0
Exp/Cntr=0.3,0.1

Type RM Length L Ch R = 1 ,5550    ,602,602,602
BEGIN DESCRIPTION:
WFSJR 024 11.0
END DESCRIPTION:
XS GIS Cut Line= 4
      3753514.09     10205444.49      3753691.16     10205572.95
      3754187.69     10205458.36      3754461.99     10205350.73
#Sta/Elev= 30
  4516.7   303.9  4552.8  301.82  4718.3  295.41  4824.4  292.76  4916.8  289.11
  4927.1  288.55  4968.1  283.96  4978.4     282    4986  279.26  4991.1   277.6
  4998.9  273.34  5007.4  270.63  5010.9  270.63  5019.4  276.53  5028.7   279.9
  5033.8  280.92  5039.9  284.11  5050.2  286.22  5124.5   293.1  5152.8     294
  5183.6  296.87  5193.9  296.82  5266.7  300.54  5275.4  301.82  5280.7  301.55
  5320.4  303.98    5335  304.13  5443.4  309.84  5467.9   311.9  5539.7  315.26
#Mann= 3 , 0 , 0
  4516.7     .17       0    4986     .09       0  5028.7     .17       0
Bank Sta=4986,5028.7
XS Rating Curve= 0 ,0
Exp/Cntr=0.3,0.1

Type RM Length L Ch R = 1 ,4948    ,531,531,531
BEGIN DESCRIPTION:
WFSJR 024 10.0
END DESCRIPTION:
XS GIS Cut Line= 3
      3753340.48     10206203.15      3754371.72     10205984.41
      3754657.05     10205725.01
#Sta/Elev= 30
  4271.1  303.69    4708  289.94  4885.2  280.43  4922.7  277.52  4963.5  272.58
  4984.5  270.66  5002.7   267.6    5029  273.05  5055.5  275.65  5073.6  273.07
  5078.7  276.89  5086.2  277.63  5116.9  276.58  5128.3  279.74  5147.5  281.11
  5178.2  285.82  5229.3  289.91  5300.9  293.86  5311.1  293.24  5321.3  294.92
  5438.3  298.79  5459.3  301.17  5466.7  300.57  5473.5  302.57    5516  303.74
  5551.2  306.51  5572.8  306.73  5643.8  310.81  5664.7   313.4  5710.9  314.91
#Mann= 3 , 0 , 0
  4271.1     .17       0  4963.5     .09       0    5029     .17       0
Bank Sta=4963.5,5029
XS Rating Curve= 0 ,0
Exp/Cntr=0.3,0.1

Type RM Length L Ch R = 1 ,4417    ,521,521,521
BEGIN DESCRIPTION:
WFSJR 024 9.0
END DESCRIPTION:
XS GIS Cut Line= 3
      3753395.14     10206916.71      3754306.61     10206427.11
       3754883.8     10206024.12
#Sta/Elev= 30
  4132.1  311.08  4271.4  306.17  4492.7  295.36  4618.6  286.95  4744.4   281.2
  4750.1  281.95  4766.3  279.62  4804.5  277.34  4919.7  271.93  4963.8  268.81
  4994.3  264.18  5009.2  265.65  5031.9  265.22  5054.6  268.47  5121.9  276.28
    5216  281.92  5229.2  280.22  5236.9  282.59    5243  280.38  5252.9  282.81
  5257.8   282.5  5272.7  285.68  5338.1  289.23  5344.2  288.41    5359   290.9
  5558.8  301.81  5740.2  308.04  5753.7  309.65  5847.5  311.08  5870.7  313.15
#Mann= 5 ,-1 , 0
  4132.1     .17       0  4919.7     .15       0  4963.8     .09       0
  5054.6     .15       0  5252.9     .17       0
Bank Sta=4963.8,5054.6
XS Rating Curve= 0 ,0
Exp/Cntr=0.3,0.1

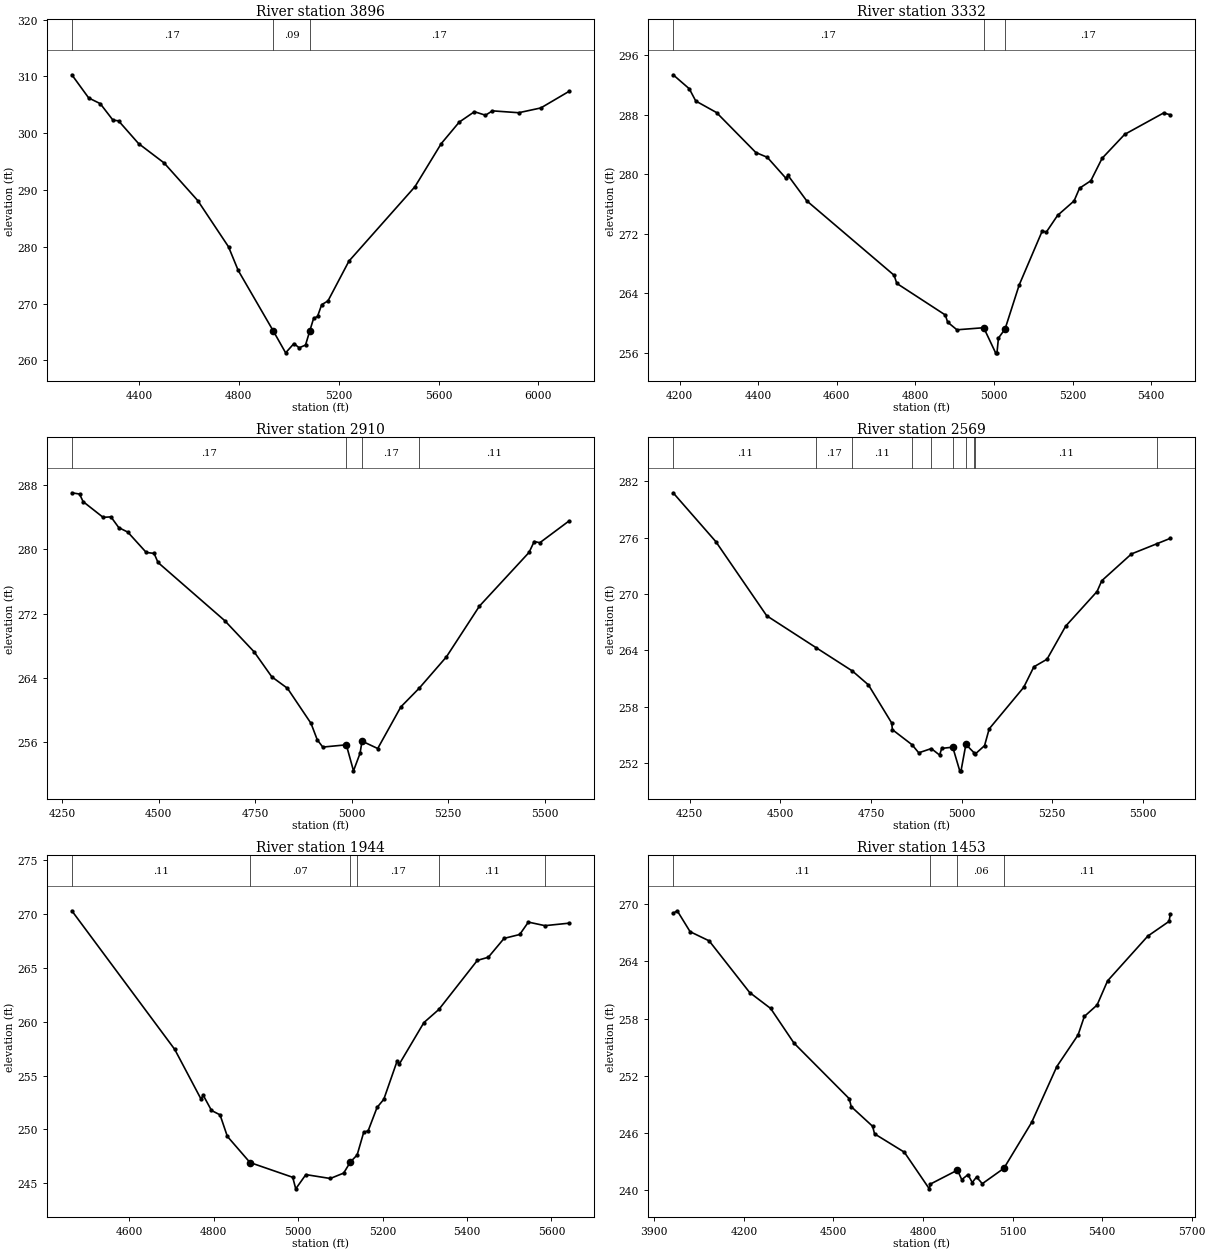
Type RM Length L Ch R = 1 ,3896    ,564,564,564
BEGIN DESCRIPTION:
WFSJR 024 8.0
END DESCRIPTION:
XS GIS Cut Line= 3
       3753439.4      10207226.6      3754639.95     10206848.99
      3754975.87     10206197.98
#Sta/Elev= 30
  4131.4  310.29  4198.9  306.21  4245.1  305.21    4296  302.31  4318.5  302.18
  4398.4  298.19  4500.9  294.77  4635.7  288.14  4758.8  280.01  4797.6  275.85
  4937.6  265.23  4987.6  261.34  5020.8  262.97  5041.8  262.23  5067.2  262.71
  5083.7  265.12  5099.6  267.41  5115.2  267.74    5132  269.82  5157.1  270.48
    5241  277.48  5505.5  290.59  5610.7  298.17  5682.8  301.96  5743.6  303.79
  5787.9  303.17  5815.7  303.94  5920.9  303.61  6009.5  304.45  6122.5  307.37
#Mann= 3 ,-1 , 0
  4131.4     .17       0  4937.6     .09       0  5083.7     .17       0
Bank Sta=4937.6,5083.7
XS Rating Curve= 0 ,0
Exp/Cntr=0.3,0.1

Type RM Length L Ch R = 1 ,3332    ,422,422,422
BEGIN DESCRIPTION:
WFSJR 024 7.0
END DESCRIPTION:
XS GIS Cut Line= 3
      3753830.02     10207588.59      3754697.24     10207221.39
      3754946.99     10207015.86
#Sta/Elev= 30
  4183.7   293.4  4224.8  291.52  4241.3  289.87  4294.1  288.32  4394.2  282.94
  4423.3   282.3  4470.7  279.48  4476.1  279.86  4523.5  276.45    4746  266.43
  4752.9  265.33  4876.4  261.08  4882.2  260.12  4905.9  259.09  4974.1  259.37
  5004.3  255.99  5007.8  255.99  5011.5  257.97  5028.4   259.2  5064.3  265.12
  5123.1   272.4  5133.3  272.23    5162  274.48    5204  276.43  5217.9  278.14
  5246.6  279.14  5275.3  282.16  5332.7  285.38  5431.7  288.26  5448.9  288.02
#Mann= 3 , 0 , 0
  4183.7     .17       0  4974.1     .09       0  5028.4     .17       0
Bank Sta=4974.1,5028.4
XS Rating Curve= 0 ,0
Exp/Cntr=0.3,0.1

Type RM Length L Ch R = 1 ,2910    ,341,341,341
BEGIN DESCRIPTION:
WFSJR 024 6.0
END DESCRIPTION:
XS GIS Cut Line= 3
      3753908.15     10207802.12      3754822.24     10207632.84
      3755111.29     10207419.31
#Sta/Elev= 30
  4274.6  287.06  4294.6   286.9  4303.8  285.96  4355.7     284    4376  284.06
  4396.3  282.72  4419.7  282.16  4467.5  279.63  4487.9  279.51    4498  278.38
  4670.9  271.14  4747.2  267.25    4793  264.14  4833.6  262.71  4894.7  258.34
  4910.9  256.29  4925.2  255.39  4986.2  255.67  5004.8  252.43  5021.8  254.61
  5026.9  256.13  5067.6  255.21  5127.5  260.39  5175.7  262.75  5245.8  266.63
  5331.4  272.95  5459.9  279.63  5473.3  280.99  5487.9  280.84  5563.6  283.55
#Mann= 4 ,-1 , 0
  4274.6     .17       0  4986.2     .09       0  5026.9     .17       0
  5175.7     .11       0
Bank Sta=4986.2,5026.9
XS Rating Curve= 0 ,0
Exp/Cntr=0.3,0.1

Type RM Length L Ch R = 1 ,2569    ,625,625,625
BEGIN DESCRIPTION:
WFSJR 024 5.0
END DESCRIPTION:
XS GIS Cut Line= 3
       3753960.3      10208106.8      3754561.82     10208067.74
      3755207.68     10207651.06
#Sta/Elev= 30
  4204.3  280.78  4322.1  275.58  4462.4  267.69  4599.5  264.27  4698.7  261.81
    4743  260.33  4807.1  256.28  4809.2  255.56  4863.3  253.96  4881.8   253.1
  4916.4  253.55  4939.3  252.86  4945.2  253.57  4975.6   253.7  4994.9  251.18
  4998.4  251.18  5011.8  253.99  5034.3  253.11    5037  252.95  5063.3  253.86
  5076.1  255.65  5171.3  260.07  5199.3  262.25  5235.6  263.06    5287  266.58
  5373.6  270.27  5386.7  271.42  5468.5  274.27  5539.7  275.37  5575.7  275.93
#Mann= 10 ,-1 , 0
  4204.3     .11       0  4599.5     .17       0  4698.7     .11       0
  4863.3     .17       0  4916.4     .11       0  4975.6     .07       0
  5011.8     .11       0  5034.3     .17       0    5037     .11       0
  5539.7     .17       0
Bank Sta=4975.6,5011.8
XS Rating Curve= 0 ,0
Exp/Cntr=0.3,0.1

Type RM Length L Ch R = 1 ,1944    ,491,491,491
BEGIN DESCRIPTION:
WFSJR 024 4.0
END DESCRIPTION:
XS GIS Cut Line= 3
      3754171.23     10208604.19      3754700.28     10208520.09
      3755309.24     10208317.73
#Sta/Elev= 30
  4464.3  270.28    4708  257.42  4770.3  252.81  4775.3  253.18    4795  251.76
  4815.3  251.35  4832.5  249.36  4886.2  246.93  4987.4  245.56  4994.5  244.49
  5018.5  245.81  5076.3  245.45    5108  245.95  5123.9  246.98  5139.9  247.63
  5155.5  249.74    5166  249.87  5187.1  252.04    5203  252.79  5234.6  256.34
  5239.9  256.07    5298  259.91  5333.5  261.13  5424.6  265.68  5450.6  265.97
  5487.9  267.72  5524.9  268.08  5545.4  269.23  5584.6   268.9  5641.7  269.13
#Mann= 6 ,-1 , 0
  4464.3     .11       0  4886.2     .07       0  5123.9     .11       0
  5139.9     .17       0  5333.5     .11       0  5584.6     .17       0
Bank Sta=4886.2,5123.9
XS Rating Curve= 0 ,0
Exp/Cntr=0.3,0.1

Type RM Length L Ch R = 1 ,1453    ,397,397,397
BEGIN DESCRIPTION:
WFSJR 024 3.0
END DESCRIPTION:
XS GIS Cut Line= 3
      3754176.41     10209739.61      3754834.38     10208938.22
      3755307.74     10208524.76
#Sta/Elev= 30
  3963.1  269.03  3976.9  269.29    4020   267.1  4083.8  266.14  4219.5  260.73
  4289.8  259.06    4368  255.43  4553.1  249.61  4559.6  248.78  4631.3  246.72
  4637.8  245.93  4737.5  244.01  4821.2  240.17  4824.9  240.67  4915.5  242.13
  4929.9  241.13  4950.7  241.66    4965  240.83  4979.4  241.41  4998.8  240.71
    5071  242.32  5163.9  247.12  5248.4  252.98  5319.6  256.29  5340.4  258.22
  5383.2  259.42  5418.3  261.95  5553.1  266.64  5624.3  268.18  5628.5  268.94
#Mann= 4 ,-1 , 0
  3963.1     .11       0  4824.9     .11       0  4915.5     .06       0
    5071     .11       0
Bank Sta=4915.5,5071
XS Rating Curve= 0 ,0
Exp/Cntr=0.3,0.1

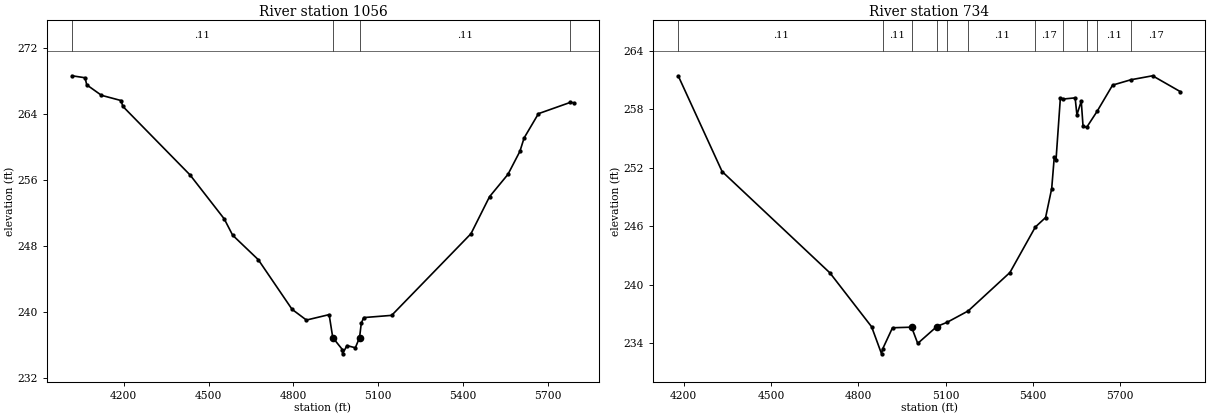
Type RM Length L Ch R = 1 ,1056    ,322,322,322
BEGIN DESCRIPTION:
WFSJR 024 2.0
END DESCRIPTION:
XS GIS Cut Line= 3
      3754215.44     10209747.44      3754921.87     10209434.25
      3755491.53     10208609.38
#Sta/Elev= 30
  4016.7  268.68  4063.1  268.44    4069  267.58    4121  266.31  4190.8  265.67
  4196.3  264.98  4434.5  256.64  4555.3  251.31  4585.1  249.33  4675.7  246.36
  4795.3  240.33    4846  239.03  4926.4  239.69  4939.1  236.91  4973.6  235.43
  4973.8  234.93  4989.3  235.93    5019  235.67  5033.9  236.89    5040  238.63
  5048.5  239.33  5147.5   239.6    5428  249.51  5493.6     254  5558.9  256.72
  5601.1  259.51  5615.9  261.13  5666.6  264.08  5779.3  265.45  5791.9   265.4
#Mann= 4 ,-1 , 0
  4016.7     .11       0  4939.1     .06       0  5033.9     .11       0
  5779.3     .17       0
Bank Sta=4939.1,5033.9
XS Rating Curve= 0 ,0
Exp/Cntr=0.3,0.1

Type RM Length L Ch R = 1 ,734     ,0,0,0
BEGIN DESCRIPTION:
WFSJR 024 1.0
END DESCRIPTION:
XS GIS Cut Line= 3
      3754577.91     10209725.29       3755111.3     10209705.76
      3755785.05     10208725.05
#Sta/Elev= 30
  4182.4  261.41  4332.4  251.62  4702.7   241.2  4845.9  235.66    4880  232.88
  4883.7  233.38  4917.6  235.56  4983.2  235.62  5004.2  233.95  5069.9  235.69
  5105.7  236.13  5177.5  237.29  5320.9  241.24    5408  245.91  5443.3  246.89
  5464.3  249.87  5473.1   253.1  5479.2  252.84  5494.1  259.19  5503.9  259.07
  5544.8  259.19  5550.9  257.45  5565.8  258.85  5571.9  256.29  5584.4  256.16
  5620.1   257.8  5673.4   260.5  5736.2  261.05  5810.8  261.46    5906  259.83
#Mann= 11 ,-1 , 0
  4182.4     .11       0  4883.7     .11       0  4983.2     .06       0
  5069.9     .11       0  5105.7     .15       0  5177.5     .11       0
    5408     .17       0  5503.9     .11       0  5584.4     .17       0
  5620.1     .11       0  5736.2     .17       0
Bank Sta=4983.2,5069.9
XS Rating Curve= 0 ,0
Exp/Cntr=0.3,0.1

Chan Stop Cuts=-1
Use User Specified Reach Order=0
Composite Channel Slope=5