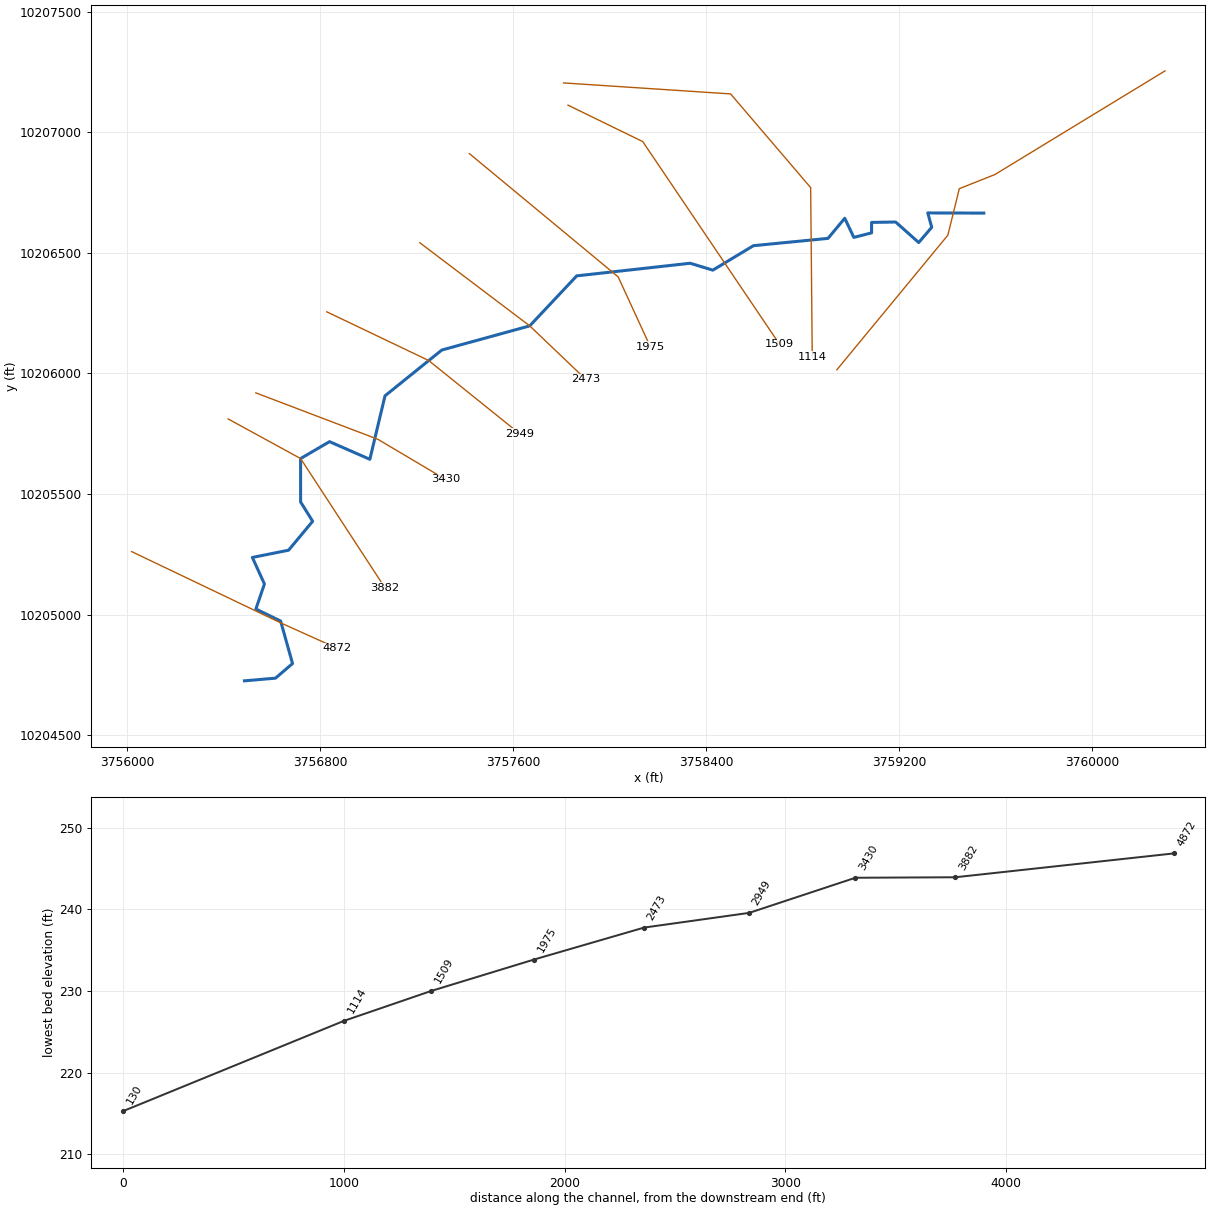
--- WFSJR 026.prj (project) ---

Proj Title=WFSJR 026 Base Level Engineering
Current Plan=p01
Default Exp/Contr=0.3,0.1
English Units
Geom File=g01
Flow File=f01
Plan File=p01
Y Axis Title=Elevation
X Axis Title(PF)=Main Channel Distance
X Axis Title(XS)=Station
BEGIN DESCRIPTION:
WFSJR 026
END DESCRIPTION:
DSS Export Rating Curves= 0
DSS Export Rating Curve Sorted= 0
DSS Export Volume Flow Curves= 0
DXF OffsetX= 0
DXF OffsetY= 0
DXF ScaleX= 1
DXF ScaleY= 10

--- WFSJR 026.p01 (plan) ---

Plan Title=Multiple Run
Program Version=4.10
Short Identifier=Multiple
Geom File=g01
Flow File=f01
Subcritical Flow
K Sum by GR= 0
Std Step Tol= 0.01
Critical Tol= 0.01
Num of Std Step Trials= 20
Max Error Tol= 0.3
Flow Tol Ratio= 0.001
Split Flow NTrial= 30
Split Flow Tol= 0.02
Split Flow Ratio= 0.02
Log Output Level= 0
Friction Slope Method= 1
Unsteady Friction Slope Method= 2
Unsteady Bridges Friction Slope Method= 1
Parabolic Critical Depth
Global Vel Dist= 1 , 1 , 1
Global Log Level= 0
CheckData=True
Encroach Param=-1 ,0,0, 0
BEGIN DESCRIPTION:
Multiple Run
END DESCRIPTION:
Computation Interval=1HOUR
Output Interval=1HOUR
Run HTab= 0
Run UNet= 0
Run PostProcess= 0
Run WQNet= 0
UNET Theta= 1
UNET Theta Warmup= 1
UNET ZTol= 0.02
UNET ZSATol= 0.05
UNET MxIter= 20
UNET MaxInSteps= 0
UNET DtIC= 0
UNET DtMin= 0
UNET MaxCRTS= 20
UNET WFStab= 2
UNET SFStab= 1
UNET WFX= 1
UNET SFX= 1
UNET DSS MLevel= 4
UNET DZMax Abort= 100
UNET Convert EG Bridges= 0
UNET Use Existing IB Tables=-1
UNET Froude Reduction=False
UNET Froude Limit= 1
UNET Froude Power= 10
UNET Time Slicing=0,0, 5
UNET Junction Losses=0
Instantaneous Interval=1HOUR
Write IC File= 0
Write IC File at Sim End=0
Echo Input=False
Echo Parameters=False
Echo Output=False
Write Detailed= 0
WQ AD Non Conservative
WQ ULTIMATE=-1
WQ Max Comp Step=1HOUR
WQ Output Interval=15MIN
WQ Output Selected Increments= 0
WQ Output face flow=0
WQ Output face velocity=0
WQ Output face area=0
WQ Output face dispersion=0
WQ Output cell volume=0
WQ Output cell surface area=0
WQ Output cell continuity=0
WQ Output cumulative cell continuity=0
WQ Output face conc=0
WQ Output face dconc_dx=0
WQ Output face courant=0
WQ Output face peclet=0
WQ Output face adv mass=0
WQ Output face disp mass=0
WQ Output cell mass=0
WQ Output cell source sink temp=0
WQ Output cell source sink nsm=0
WQ Output MaxMinRange=-1
WQ Daily Max Min Mean=-1
WQ Daily Range=0
WQ Daily Time=0
WQ Create Restart=0
WQ Fixed Restart=0
WQ System Summary=0
WQ Use Fixed Temperature=0
Sorting and Armoring Iterations= 10
XS Update Threshold= 0.02
Hydraulics Update Threshold= 0.02
Energy Slope Method= 1
Volume Change Method= 0
XS Weighting Method= 0
Number of US Weighted Cross Sections= 1
Number of DS Weighted Cross Sections= 1
Upstream XS Weight=0.25
Main XS Weight=0.5
Downstream XS Weight=0.25
Number of DS XS's Weighted with US Boundary= 1
Upstream Boundary Weight= 1
Weight of XSs Associated with US Boundary= 0
Number of US XS's Weighted with DS Boundary= 1
Downstream Boundary Weight= 0.5
Weight of XSs Associated with DS Boundary= 0.5
Sediment Output Level= 4
Mass or Volume Output= 0
Output Increment Type= 1
Profile and TS Output Increment= 10
XS Output Flag= 0
XS Output Increment= 10
Disregard all LS=0
Disregard all Conn=0
Disregard all Breaches=0
Disregard all Pumps=0

--- WFSJR 026.f01 (steady flow) ---

Flow Title=Multiple
Program Version=4.10
Number of Profiles= 7
Profile Names=10-year,25-year,50-year,1pct_min,100-year,1pct_plu,500-year
River Rch & RM=WFSJR 026,Reach-1         ,4872
     970    1367    1899     868    2621    7915    5167
Boundary for River Rch & Prof#=WFSJR 026,Reach-1         , 1
Up Type= 0
Dn Type= 3
Dn Slope=0.006
Boundary for River Rch & Prof#=WFSJR 026,Reach-1         , 2
Up Type= 0
Dn Type= 3
Dn Slope=0.006
Boundary for River Rch & Prof#=WFSJR 026,Reach-1         , 3
Up Type= 0
Dn Type= 3
Dn Slope=0.006
Boundary for River Rch & Prof#=WFSJR 026,Reach-1         , 4
Up Type= 0
Dn Type= 3
Dn Slope=0.006
Boundary for River Rch & Prof#=WFSJR 026,Reach-1         , 5
Up Type= 0
Dn Type= 3
Dn Slope=0.006
Boundary for River Rch & Prof#=WFSJR 026,Reach-1         , 6
Up Type= 0
Dn Type= 3
Dn Slope=0.006
Boundary for River Rch & Prof#=WFSJR 026,Reach-1         , 7
Up Type= 0
Dn Type= 3
Dn Slope=0.006
DSS Import GetInterval= 0
DSS Import GetPeak= 0
DSS Import FillOption= 0

--- WFSJR 026.g01 (geometry) ---

Geom Title=Existing Conditions
Program Version=4.10

River Reach=WFSJR 026       ,Reach-1
Reach XY= 30
      3756485.47     10204725.35      3756614.11     10204736.42
      3756684.82     10204796.91      3756635.41     10204973.26
       3756532.9     10205022.99      3756568.23     10205126.84
      3756518.23     10205236.84      3756668.23     10205266.84
      3756768.23     10205386.84      3756718.23     10205466.84
      3756718.23     10205646.84      3756838.23     10205716.84
      3757005.32     10205643.71      3757068.23     10205906.84
      3757303.77     10206096.71      3757668.23     10206196.84
      3757863.07     10206404.16      3758333.24     10206456.49
      3758427.27     10206427.87      3758595.72     10206529.26
       3758904.8     10206559.52      3758974.31     10206642.92
      3759011.92     10206563.61      3759085.51     10206582.41
      3759085.51     10206625.75      3759185.27     10206627.39
      3759280.94     10206542.35      3759334.91     10206605.31
      3759318.55       10206665.      3759550.68     10206664.39

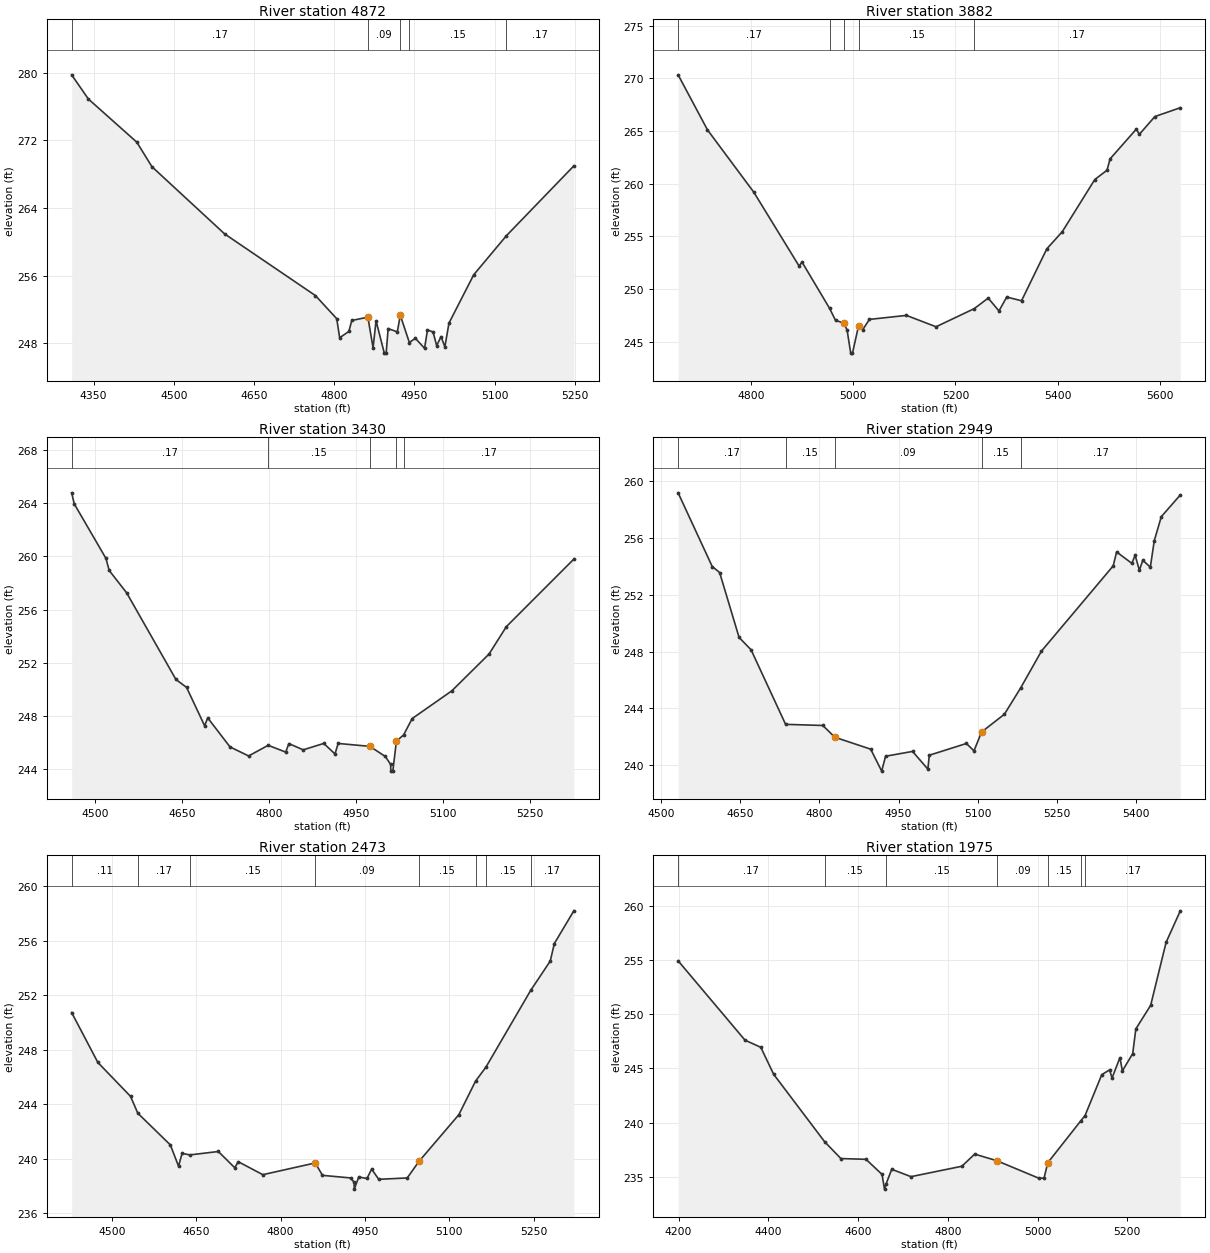
Type RM Length L Ch R = 1 ,4872    ,990,990,990
BEGIN DESCRIPTION:
WFSJR 026 7.0
END DESCRIPTION:
XS GIS Cut Line= 3
      3756017.84     10205261.07      3756641.38     10204963.03
      3756867.88     10204861.06
#Sta/Elev= 30
  4308.9  279.74  4340.2  276.88  4430.8  271.78  4459.1  268.88  4595.1  260.94
    4765  253.65  4804.8  250.92  4810.3  248.67  4827.5  249.41    4833  250.71
  4863.1   251.1  4872.8  247.48  4878.4  250.66  4893.8  246.85  4897.3  246.85
    4901  249.75  4918.2  249.36  4923.7  251.33  4940.7   248.1  4951.9  248.61
  4969.1  247.42  4974.6  249.58    4985  249.36  4991.8  247.73    5000  248.81
  5007.1  247.58  5014.8   250.4  5061.1  256.11  5122.3  260.73  5248.4  268.98
#Mann= 5 ,-1 , 0
  4308.9     .17       0  4863.1     .09       0  4923.7     .17       0
  4940.7     .15       0  5122.3     .17       0
Bank Sta=4863.1,4923.7
XS Rating Curve= 0 ,0
Exp/Cntr=0.3,0.1

Type RM Length L Ch R = 1 ,3882    ,452,452,452
BEGIN DESCRIPTION:
WFSJR 026 6.0
END DESCRIPTION:
XS GIS Cut Line= 3
      3756417.89     10205811.05      3756718.23     10205646.84
      3757067.88     10205111.03
#Sta/Elev= 30
  4657.7  270.33  4715.1  265.11  4805.8  259.19  4894.3  252.19    4900  252.57
    4954  248.17  4965.5  247.04  4981.6  246.78  4988.2  246.12  4995.2  243.93
  4998.7  243.93  5010.7  246.55  5018.8  246.16  5031.8  247.13  5104.2  247.51
  5162.1  246.43  5236.8  248.15  5264.1  249.15  5285.2  247.93  5300.3  249.25
  5329.3   248.9  5378.7  253.82    5409  255.45  5472.6   260.4  5496.5  261.28
  5502.5  262.36  5553.8  265.18  5559.8  264.69    5590  266.37  5639.8  267.21
#Mann= 5 ,-1 , 0
  4657.7     .17       0    4954     .15       0  4981.6     .09       0
  5010.7     .15       0  5236.8     .17       0
Bank Sta=4981.6,5010.7
XS Rating Curve= 0 ,0
Exp/Cntr=0.3,0.1

Type RM Length L Ch R = 1 ,3430    ,481,481,481
BEGIN DESCRIPTION:
WFSJR 026 5.0
END DESCRIPTION:
XS GIS Cut Line= 3
      3756532.56     10205919.13      3757038.23     10205726.84
      3757317.88     10205561.06
#Sta/Elev= 30
    4459  264.78  4463.5  263.95  4518.2  259.85  4523.7  258.95  4553.8  257.27
  4638.8  250.76  4657.2  250.16  4688.3  247.28  4693.7  247.87  4732.1  245.69
  4764.2  245.01  4797.9  245.81  4828.2   245.3  4833.6  245.94  4858.3  245.47
  4893.8  245.95  4913.2  245.16  4918.6  245.95  4973.4  245.73    5000  244.97
  5009.2  244.37  5009.4  243.87  5012.9  243.87  5019.1  246.12  5031.5  246.59
  5046.3  247.82  5114.6   249.9  5178.9  252.67  5208.8  254.73  5325.1   259.8
#Mann= 5 ,-1 , 0
    4459     .17       0  4797.9     .15       0  4973.4     .09       0
  5019.1     .15       0  5031.5     .17       0
Bank Sta=4973.4,5019.1
XS Rating Curve= 0 ,0
Exp/Cntr=0.3,0.1

Type RM Length L Ch R = 1 ,2949    ,476,476,476
BEGIN DESCRIPTION:
WFSJR 026 4.0
END DESCRIPTION:
XS GIS Cut Line= 3
       3756826.8     10206255.08      3757248.99     10206053.37
      3757626.36     10205749.83
#Sta/Elev= 30
  4532.1   259.2  4596.8     254  4610.8  253.58  4647.7     249  4670.4  248.13
  4735.9  242.87  4806.5  242.79  4829.2  241.96  4897.2  241.12  4918.1  239.57
  4925.4  240.62  4976.6  240.96  5005.7  239.71  5008.3  240.69  5078.7  241.52
  5093.1     241  5107.5  242.33  5150.7  243.58  5181.3  245.42  5221.1  248.04
  5357.1  254.05  5363.5  255.03  5392.3  254.23  5398.7  254.79  5406.7  253.74
  5413.1  254.44  5427.5  253.96  5434.9  255.82  5448.3  257.52  5484.3  259.05
#Mann= 5 ,-1 , 0
  4532.1     .17       0  4735.9     .15       0  4829.2     .09       0
  5107.5     .15       0  5181.3     .17       0
Bank Sta=4829.2,5107.5
XS Rating Curve= 0 ,0
Exp/Cntr=0.3,0.1

Type RM Length L Ch R = 1 ,2473    ,498,498,498
BEGIN DESCRIPTION:
WFSJR 026 3.0
END DESCRIPTION:
XS GIS Cut Line= 3
      3757212.25     10206541.53      3757668.23     10206196.84
      3757900.88     10205974.95
#Sta/Elev= 30
  4428.4  250.72    4475  247.06  4533.2  244.57    4546  243.34    4604  241.01
  4618.5  239.45  4624.8  240.39  4638.9  240.28  4689.3  240.53  4718.4  239.34
  4724.7  239.78  4768.4  238.83  4861.6  239.69  4874.5  238.78  4924.5  238.59
  4930.8  238.27    4931  237.77    4939  238.66  4953.6  238.55  4961.9  239.24
  4974.5  238.49  5025.2  238.59  5046.2  239.81    5117  243.23  5146.7  245.69
  5165.2  246.72  5244.7  252.34  5279.6   254.5  5286.8  255.78  5321.5  258.18
#Mann= 8 ,-1 , 0
  4428.4     .11       0    4546     .17       0  4638.9     .15       0
  4861.6     .09       0  5046.2     .15       0  5146.7     .17       0
  5165.2     .15       0  5244.7     .17       0
Bank Sta=4861.6,5046.2
XS Rating Curve= 0 ,0
Exp/Cntr=0.3,0.1

Type RM Length L Ch R = 1 ,1975    ,466,466,466
BEGIN DESCRIPTION:
WFSJR 026 2.0
END DESCRIPTION:
XS GIS Cut Line= 3
      3757417.84     10206911.08      3758034.79     10206400.07
      3758167.87     10206111.04
#Sta/Elev= 30
  4198.9  254.92    4348   247.6  4383.2  246.94  4411.9  244.45  4525.3  238.24
  4561.7  236.68  4617.6  236.61  4653.4  235.22  4658.9  233.86  4662.6  234.36
    4675  235.69    4718  235.01  4831.3  235.97  4859.9  237.09  4909.4  236.48
  5002.7  234.87  5014.4  234.87  5022.9   236.3  5096.4  240.16  5105.9  240.65
  5143.2  244.42  5160.6  244.86  5166.1  244.11  5183.6  245.99  5189.1  244.77
  5212.1  246.36  5219.1  248.64  5252.1  250.81  5286.5  256.62  5318.2  259.53
#Mann= 7 ,-1 , 0
  4198.9     .17       0  4525.3     .15       0  4662.6     .15       0
  4909.4     .09       0  5022.9     .15       0  5096.4     .15       0
  5105.9     .17       0
Bank Sta=4909.4,5022.9
XS Rating Curve= 0 ,0
Exp/Cntr=0.3,0.1

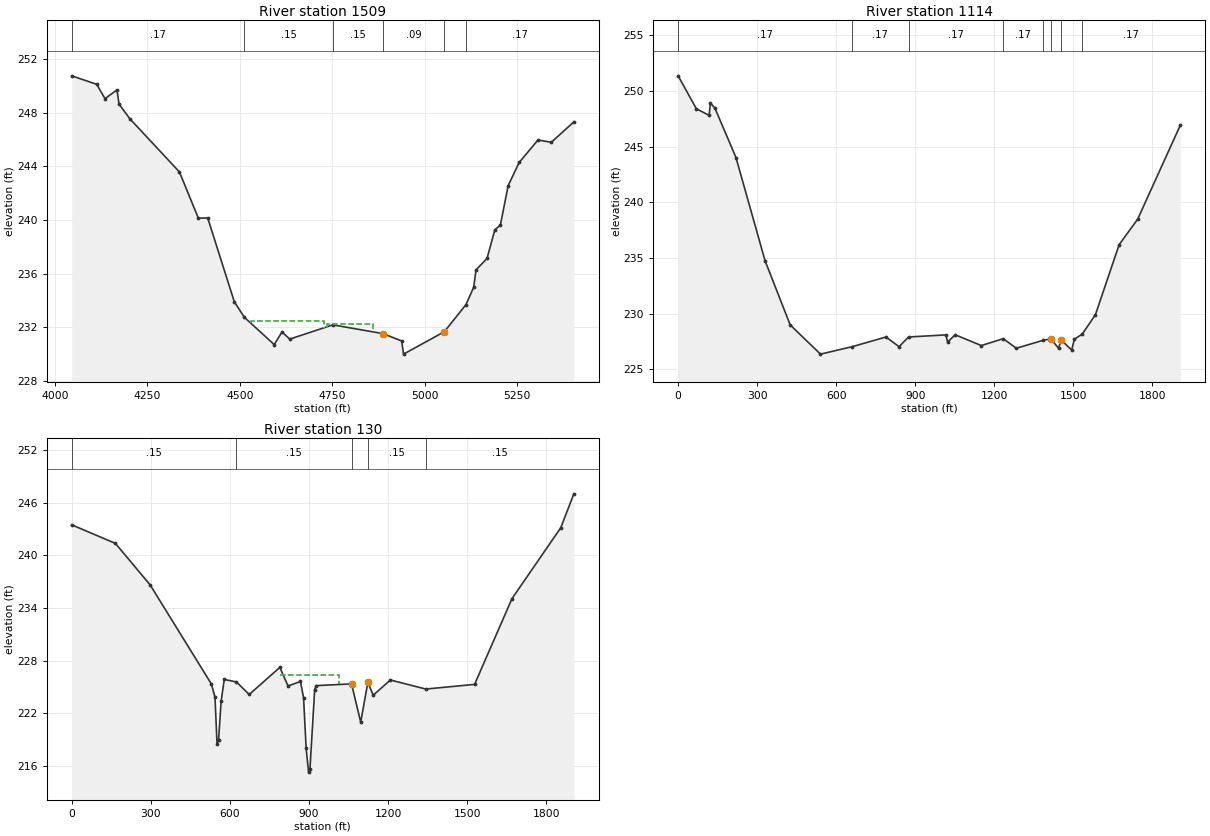
Type RM Length L Ch R = 1 ,1509    ,395,395,395
BEGIN DESCRIPTION:
WFSJR 026 1.0
END DESCRIPTION:
XS GIS Cut Line= 3
      3757826.87     10207111.82      3758136.74      10206960.8
      3758703.65     10206120.82
#Sta/Elev= 30
  4045.4  250.74  4113.2  250.11  4135.5  249.04    4168  249.69  4173.5  248.64
  4202.2  247.56  4336.9  243.58    4388  240.14  4413.4  240.15  4485.3  233.91
  4512.6  232.75  4593.3  230.72  4614.3  231.66  4635.3  231.13  4751.7  232.19
  4887.1  231.54    4938  230.99    4943  230.01  5053.3  231.68  5111.8   233.7
  5132.8     235  5138.9  236.28  5168.8  237.14  5189.8  239.27  5204.8  239.62
  5225.8  242.55  5255.7  244.29  5306.7  245.96  5342.6  245.79  5403.5  247.31
#Mann= 6 ,-1 , 0
  4045.4     .17       0  4512.6     .15       0  4751.7     .15       0
  4887.1     .09       0  5053.3     .15       0  5111.8     .17       0
#XS Ineff= 2 ,-1
    4530  4728.2  232.47    4735    4860  232.27
Permanent Ineff=
       T       F
Bank Sta=4887.1,5053.3
XS Rating Curve= 0 ,0
Exp/Cntr=0.3,0.1

Type RM Length L Ch R = 1 ,1114    ,1001,1001,1001
XS GIS Cut Line= 4
      3757808.71     10207204.01      3758500.98     10207158.43
      3758833.01     10206769.98      3758839.52     10206069.02
#Sta/Elev= 30
       0  251.37    69.3  248.41   117.6  247.82   122.6  248.91   139.4  248.48
   219.6  244.02   329.9  234.75   425.2  228.98   540.3  226.35   660.6  227.02
     789  227.89   838.4  227.02   874.5  227.89  1016.2  228.08  1022.8  227.44
  1051.4  228.09  1150.7  227.12  1233.7  227.74  1283.7  226.88  1383.7  227.58
  1413.7  227.73  1443.7  226.89  1453.7  227.62  1493.7  226.72  1503.7  227.69
  1533.7  228.15  1583.7   229.9  1673.7  236.19  1743.7  238.47  1905.8  246.93
#Mann= 8 ,-1 , 0
       0     .17       0   660.6     .17       0   874.5     .17       0
  1233.7     .17       0  1383.7     .15       0  1413.7     .09       0
  1453.7     .15       0  1533.7     .17       0
Bank Sta=1413.7,1453.7
XS Rating Curve= 0 ,0
Exp/Cntr=0.3,0.1

Type RM Length L Ch R = 1 ,130     ,0,0,0
XS GIS Cut Line= 5
       3760302.2     10207253.92       3759596.9     10206824.23
      3759449.33     10206765.64      3759401.59      10206572.5
      3758941.52     10206014.77
#Sta/Elev= 30
       0  243.48     166  241.36   297.7  236.63   530.1  225.33   543.7  223.83
   551.4  218.52   557.3  218.97   566.9  223.38   578.9  225.85     625  225.57
   673.5  224.14   789.7  227.23   820.6  225.11   867.9  225.62   879.6  223.76
   889.4  218.01   898.5  215.29   903.9  215.66   921.7   224.7   928.2  225.15
  1061.5  225.35  1096.3  220.99  1123.3  225.51  1143.9  224.06    1209  225.79
  1343.1  224.76  1528.2  225.29  1670.2  235.07  1855.2  243.15  1904.7  247.01
#Mann= 5 ,-1 , 0
       0     .15       0     625     .15       0  1061.5     .09       0
  1123.3     .15       0  1343.1     .15       0
#XS Ineff= 2 ,-1
     470   789.7  227.23     792  1013.4  226.36
Permanent Ineff=
       T       T
Bank Sta=1061.5,1123.3
XS Rating Curve= 0 ,0
Exp/Cntr=0.3,0.1

Chan Stop Cuts=-1
Use User Specified Reach Order=0
Composite Channel Slope=5