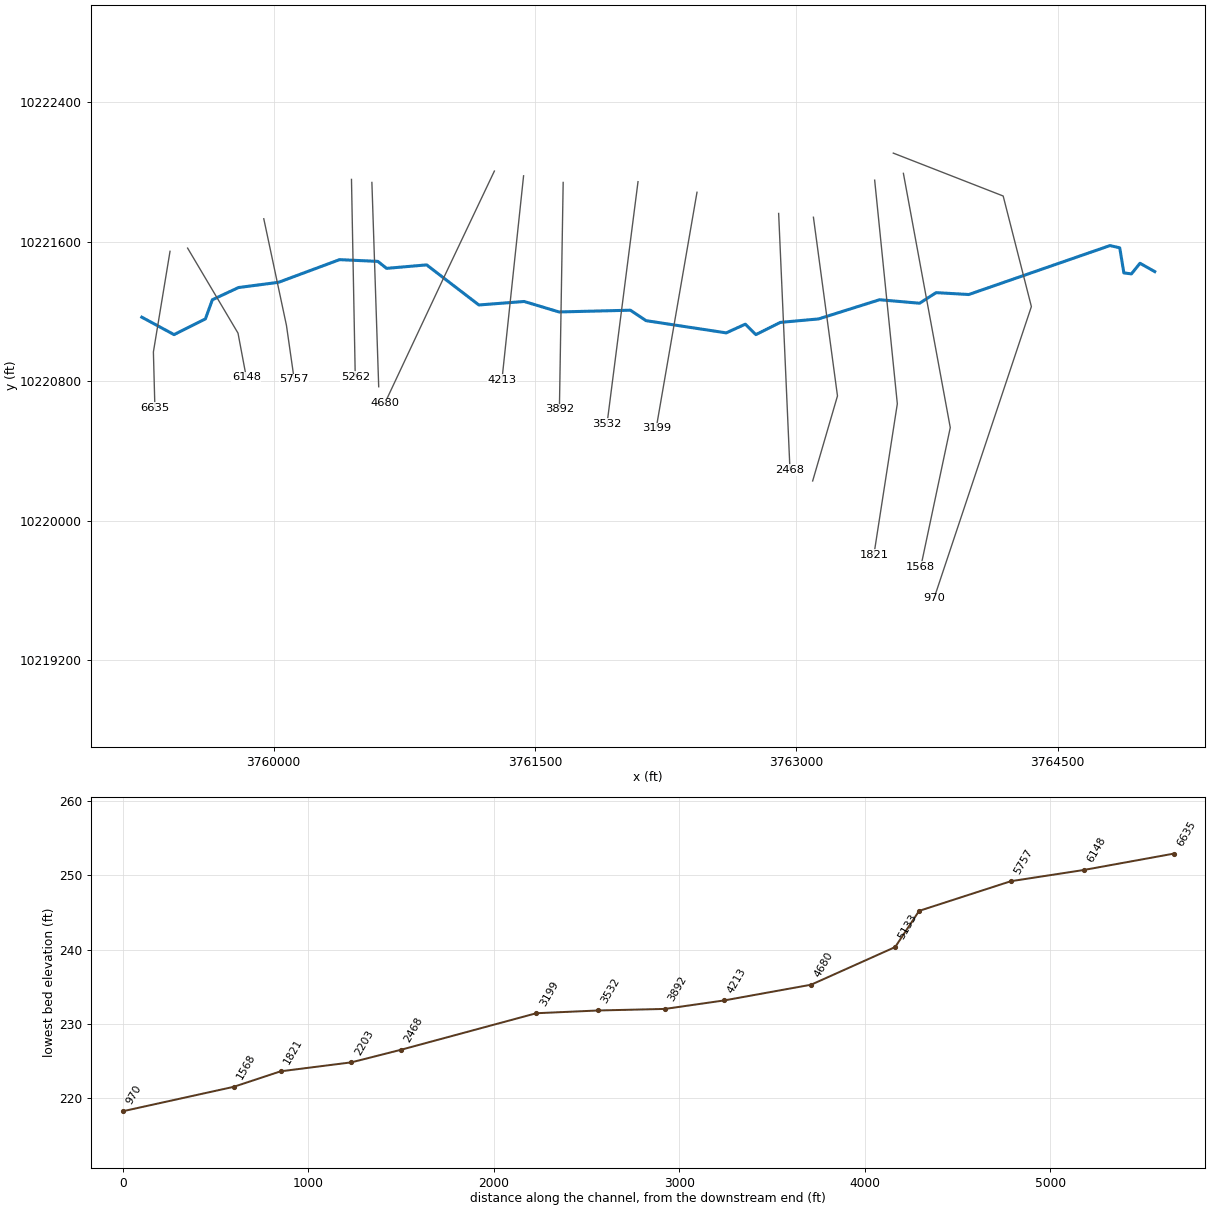
--- WFSJR 028.prj (project) ---

Proj Title=WFSJR 028 Base Level Engineering
Current Plan=p01
Default Exp/Contr=0.3,0.1
English Units
Geom File=g01
Flow File=f01
Plan File=p01
Y Axis Title=Elevation
X Axis Title(PF)=Main Channel Distance
X Axis Title(XS)=Station
BEGIN DESCRIPTION:
WFSJR 028
END DESCRIPTION:
DSS Export Rating Curves= 0
DSS Export Rating Curve Sorted= 0
DSS Export Volume Flow Curves= 0
DXF OffsetX= 0
DXF OffsetY= 0
DXF ScaleX= 1
DXF ScaleY= 10

--- WFSJR 028.p01 (plan) ---

Plan Title=Multiple Run
Program Version=4.10
Short Identifier=Multiple
Geom File=g01
Flow File=f01
Subcritical Flow
K Sum by GR= 0
Std Step Tol= 0.01
Critical Tol= 0.01
Num of Std Step Trials= 20
Max Error Tol= 0.3
Flow Tol Ratio= 0.001
Split Flow NTrial= 30
Split Flow Tol= 0.02
Split Flow Ratio= 0.02
Log Output Level= 0
Friction Slope Method= 1
Unsteady Friction Slope Method= 2
Unsteady Bridges Friction Slope Method= 1
Parabolic Critical Depth
Global Vel Dist= 1 , 1 , 1
Global Log Level= 0
CheckData=True
Encroach Param=-1 ,0,0, 0
BEGIN DESCRIPTION:
Multiple Run
END DESCRIPTION:
Computation Interval=1HOUR
Output Interval=1HOUR
Run HTab= 0
Run UNet= 0
Run PostProcess= 0
Run WQNet= 0
UNET Theta= 1
UNET Theta Warmup= 1
UNET ZTol= 0.02
UNET ZSATol= 0.05
UNET MxIter= 20
UNET MaxInSteps= 0
UNET DtIC= 0
UNET DtMin= 0
UNET MaxCRTS= 20
UNET WFStab= 2
UNET SFStab= 1
UNET WFX= 1
UNET SFX= 1
UNET DSS MLevel= 4
UNET DZMax Abort= 100
UNET Convert EG Bridges= 0
UNET Use Existing IB Tables=-1
UNET Froude Reduction=False
UNET Froude Limit= 1
UNET Froude Power= 10
UNET Time Slicing=0,0, 5
UNET Junction Losses=0
Instantaneous Interval=1HOUR
Write IC File= 0
Write IC File at Sim End=0
Echo Input=False
Echo Parameters=False
Echo Output=False
Write Detailed= 0
WQ AD Non Conservative
WQ ULTIMATE=-1
WQ Max Comp Step=1HOUR
WQ Output Interval=15MIN
WQ Output Selected Increments= 0
WQ Output face flow=0
WQ Output face velocity=0
WQ Output face area=0
WQ Output face dispersion=0
WQ Output cell volume=0
WQ Output cell surface area=0
WQ Output cell continuity=0
WQ Output cumulative cell continuity=0
WQ Output face conc=0
WQ Output face dconc_dx=0
WQ Output face courant=0
WQ Output face peclet=0
WQ Output face adv mass=0
WQ Output face disp mass=0
WQ Output cell mass=0
WQ Output cell source sink temp=0
WQ Output cell source sink nsm=0
WQ Output MaxMinRange=-1
WQ Daily Max Min Mean=-1
WQ Daily Range=0
WQ Daily Time=0
WQ Create Restart=0
WQ Fixed Restart=0
WQ System Summary=0
WQ Use Fixed Temperature=0
Sorting and Armoring Iterations= 10
XS Update Threshold= 0.02
Hydraulics Update Threshold= 0.02
Energy Slope Method= 1
Volume Change Method= 0
XS Weighting Method= 0
Number of US Weighted Cross Sections= 1
Number of DS Weighted Cross Sections= 1
Upstream XS Weight=0.25
Main XS Weight=0.5
Downstream XS Weight=0.25
Number of DS XS's Weighted with US Boundary= 1
Upstream Boundary Weight= 1
Weight of XSs Associated with US Boundary= 0
Number of US XS's Weighted with DS Boundary= 1
Downstream Boundary Weight= 0.5
Weight of XSs Associated with DS Boundary= 0.5
Sediment Output Level= 4
Mass or Volume Output= 0
Output Increment Type= 1
Profile and TS Output Increment= 10
XS Output Flag= 0
XS Output Increment= 10
Disregard all LS=0
Disregard all Conn=0
Disregard all Breaches=0
Disregard all Pumps=0

--- WFSJR 028.f01 (steady flow) ---

Flow Title=Multiple
Program Version=4.10
Number of Profiles= 7
Profile Names=10-year,25-year,50-year,1pct_min,100-year,1pct_plu,500-year
River Rch & RM=WFSJR 028,Reach-1         ,6635
     639     875    1193     536    1619    4889    3077
River Rch & RM=WFSJR 028,Reach-1         ,5262
     734    1005    1369     614    1853    5596    3507
Boundary for River Rch & Prof#=WFSJR 028,Reach-1         , 1
Up Type= 0
Dn Type= 3
Dn Slope=0.011
Boundary for River Rch & Prof#=WFSJR 028,Reach-1         , 2
Up Type= 0
Dn Type= 3
Dn Slope=0.011
Boundary for River Rch & Prof#=WFSJR 028,Reach-1         , 3
Up Type= 0
Dn Type= 3
Dn Slope=0.011
Boundary for River Rch & Prof#=WFSJR 028,Reach-1         , 4
Up Type= 0
Dn Type= 3
Dn Slope=0.011
Boundary for River Rch & Prof#=WFSJR 028,Reach-1         , 5
Up Type= 0
Dn Type= 3
Dn Slope=0.011
Boundary for River Rch & Prof#=WFSJR 028,Reach-1         , 6
Up Type= 0
Dn Type= 3
Dn Slope=0.011
Boundary for River Rch & Prof#=WFSJR 028,Reach-1         , 7
Up Type= 0
Dn Type= 3
Dn Slope=0.011
DSS Import GetInterval= 0
DSS Import GetPeak= 0
DSS Import FillOption= 0

--- WFSJR 028.g01 (geometry) ---

Geom Title=Existing Conditions
Program Version=4.10

River Reach=WFSJR 028       ,Reach-1
Reach XY= 30
      3759243.23     10221166.84      3759428.23     10221066.84
      3759608.23     10221156.84      3759648.23     10221266.84
      3759798.23     10221336.84      3760028.23     10221366.84
      3760378.23     10221496.84      3760598.23     10221486.84
      3760648.23     10221446.84      3760878.23     10221466.84
      3761178.23     10221236.84      3761438.23     10221256.84
      3761638.23     10221196.84      3762048.23     10221206.84
      3762138.23     10221146.84      3762598.23     10221076.84
      3762708.23     10221126.84      3762768.23     10221066.84
      3762908.23     10221136.84      3763128.23     10221156.84
      3763478.23     10221266.84      3763708.23     10221246.84
      3763803.32     10221307.64      3763990.47     10221296.81
      3764801.15     10221577.54      3764857.29     10221564.73
      3764880.93     10221420.92      3764924.28     10221415.01
      3764973.53     10221476.08      3765058.36      10221428.3

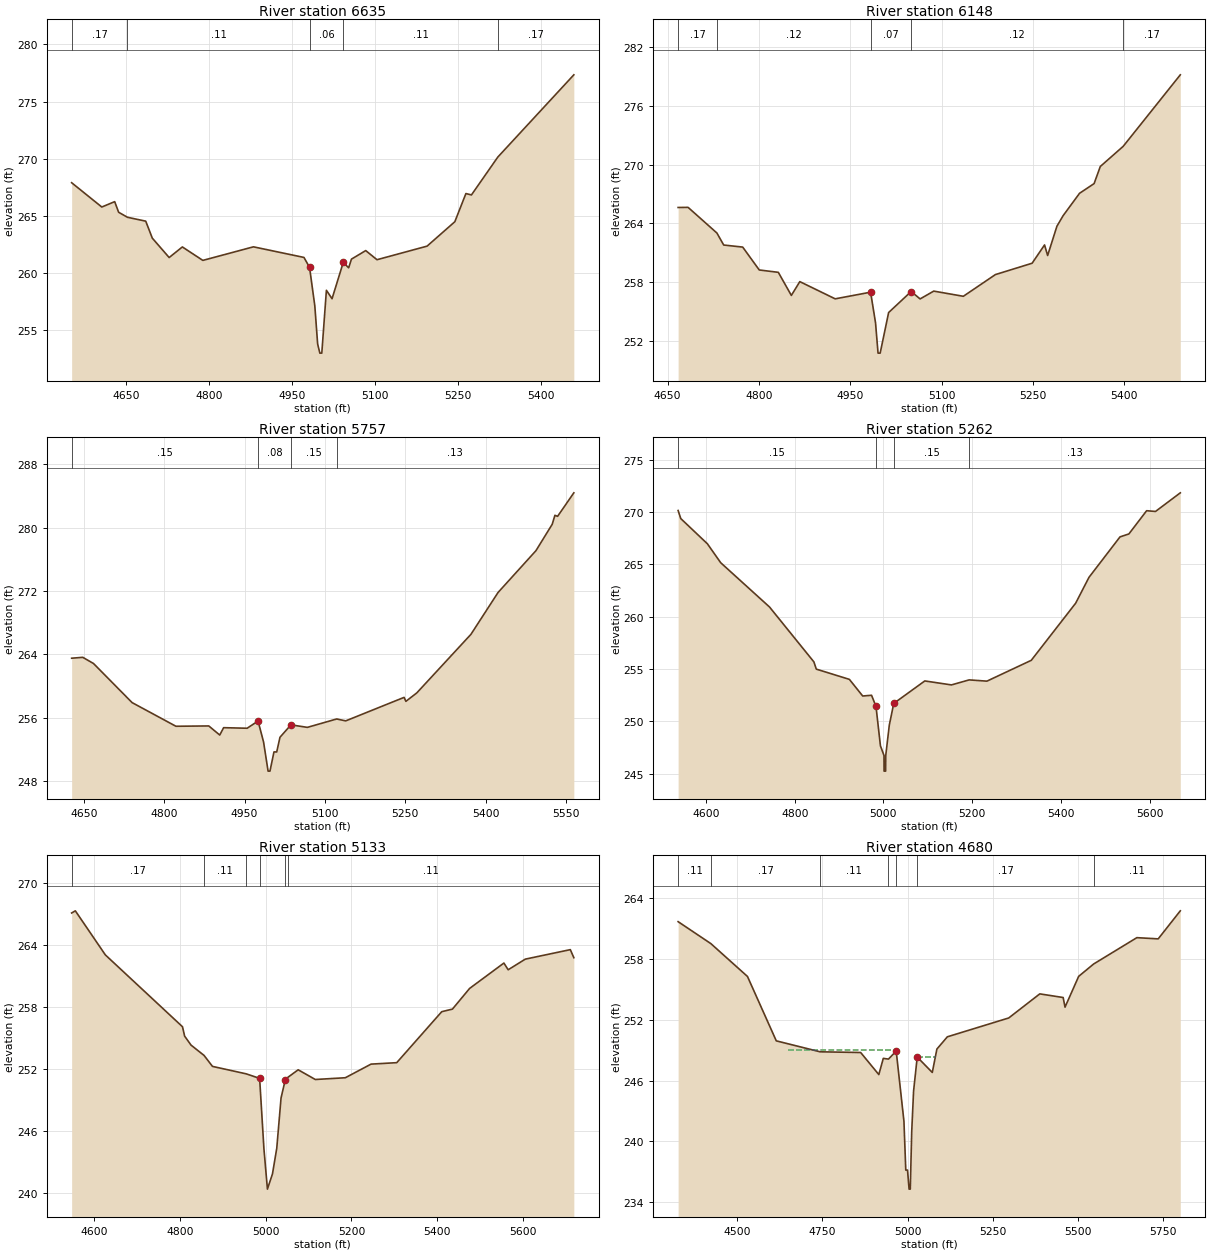
Type RM Length L Ch R = 1 ,6635    ,487,487,487
BEGIN DESCRIPTION:
WFSJR 028 13.0
END DESCRIPTION:
XS GIS Cut Line= 3
      3759405.21     10221544.74      3759309.72      10220967.5
       3759318.4     10220646.31
#Sta/Elev= 30
  4552.2  267.88  4606.6  265.75  4629.9  266.22    4637  265.29    4653  264.85
  4685.9  264.51  4697.8  263.02  4728.2  261.32    4752  262.25    4789  261.07
  4880.3  262.26  4971.5  261.33  4981.6  260.46  4991.1  257.08  4996.2  253.74
  5000.2  252.94  5003.7  252.94    5012  258.45  5022.2  257.71  5042.4  260.89
  5052.2  260.42  5057.2  261.18    5083  261.93  5103.3  261.13  5193.7  262.32
  5243.8  264.46  5263.8  266.93  5273.8  266.81  5321.4  270.13  5458.6  277.34
#Mann= 5 ,-1 , 0
  4552.2     .17       0    4653     .11       0  4981.6     .06       0
  5042.4     .11       0  5321.4     .17       0
Bank Sta=4981.6,5042.4
XS Rating Curve= 0 ,0
Exp/Cntr=0.3,0.1

Type RM Length L Ch R = 1 ,6148    ,391,391,391
BEGIN DESCRIPTION:
WFSJR 028 12.0
END DESCRIPTION:
XS GIS Cut Line= 3
      3759506.16     10221562.99      3759795.47     10221075.28
      3759843.21      10220821.9
#Sta/Elev= 30
  4667.3  265.62  4683.7  265.63    4731  263.01  4742.2  261.78  4773.4  261.57
  4800.6  259.23  4831.9  258.99  4853.3  256.63  4867.2  258.04  4925.3  256.28
  4983.5  256.96  4991.6  253.82  4995.7  250.73  4999.2  250.73  5013.1  254.88
  5050.1  257.03  5064.8  256.27  5087.2  257.07  5135.8  256.54  5188.5  258.76
  5248.8  259.92  5269.2  261.79  5274.3  260.71  5289.5   263.7  5299.7  264.78
  5326.7  267.07  5350.6  268.06  5360.8  269.81  5398.4  271.87  5492.2  279.18
#Mann= 5 ,-1 , 0
  4667.3     .17       0    4731     .12       0  4983.5     .07       0
  5050.1     .12       0  5398.4     .17       0
Bank Sta=4983.5,5050.1
XS Rating Curve= 0 ,0
Exp/Cntr=0.3,0.1

Type RM Length L Ch R = 1 ,5757    ,495,495,495
BEGIN DESCRIPTION:
WFSJR 028 11.0
END DESCRIPTION:
XS GIS Cut Line= 3
       3759943.4     10221731.38      3760073.61     10221119.41
      3760117.86     10220811.04
#Sta/Elev= 30
  4627.3   263.5  4648.1  263.61  4668.1  262.83  4740.1  257.89  4821.9   254.9
  4883.2  254.94  4903.7  253.79  4910.9  254.72  4954.8  254.65  4975.2  255.56
  4985.5   252.9  4993.9  249.23  4997.4  249.23  5004.9  251.66    5010  251.65
  5016.1  253.51  5036.6  255.08  5067.2  254.76  5121.9  255.82  5138.8  255.58
  5247.7  258.55  5251.1  258.05  5271.5  259.12  5372.5  266.52    5423   271.8
  5493.8  277.09  5524.1  280.42  5529.2  281.56  5534.2  281.43  5564.5   284.4
#Mann= 4 ,-1 , 0
  4627.3     .15       0  4975.2     .08       0  5036.6     .15       0
  5121.9     .13       0
Bank Sta=4975.2,5036.6
XS Rating Curve= 0 ,0
Exp/Cntr=0.3,0.1

Type RM Length L Ch R = 1 ,5262    ,129,129,129
BEGIN DESCRIPTION:
Mapping XS 4964b96f
END DESCRIPTION:
XS GIS Cut Line= 2
      3760446.88     10221957.07      3760468.56     10220825.18
#Sta/Elev= 30
  4537.2  270.14  4543.2  269.37  4603.2  266.96  4633.2  265.15  4743.2  260.92
  4843.3  255.67  4848.7  254.98  4923.3     254  4953.3  252.41  4973.3  252.48
  4983.3  251.41  4993.3  247.65  5001.3  246.73  5001.5  245.23    5005  245.23
  5005.3  246.73  5013.3  249.63  5023.3   251.7  5093.3  253.85  5153.3  253.47
  5193.3  253.95  5233.3  253.83  5333.3  255.82  5433.4  261.28  5463.4  263.75
  5533.4  267.62  5553.4   267.9  5593.4  270.12  5613.4  270.05  5669.3  271.83
#Mann= 4 ,-1 , 0
  4537.2     .15       0  4983.3     .08       0  5023.3     .15       0
  5193.3     .13       0
Bank Sta=4983.3,5023.3
XS Rating Curve= 0 ,0
Exp/Cntr=0.3,0.1

Type RM Length L Ch R = 1 ,5133    ,453,453,453
BEGIN DESCRIPTION:
WFSJR 028 10.0
END DESCRIPTION:
XS GIS Cut Line= 2
      3760564.06     10221939.69      3760603.13     10220767.84
#Sta/Elev= 30
  4546.9  267.11  4555.5  267.32  4625.6  263.05  4805.7  256.09  4810.7  255.18
  4825.7  254.31  4856.1  253.31  4875.7  252.25  4954.2  251.53  4985.8  251.09
  4995.8  244.28    5004  240.36  5015.8  241.84  5025.8  244.32  5035.8  249.19
  5045.8  250.97  5052.4  251.21  5075.8  251.92  5115.8  250.98  5185.9  251.15
  5245.9  252.47  5305.9  252.61    5411  257.55    5436   257.8    5476   259.8
  5556.1  262.26  5566.1  261.61  5606.1  262.64  5711.2  263.56  5719.4  262.78
#Mann= 6 ,-1 , 0
  4546.9     .17       0  4856.1     .11       0  4954.2     .17       0
  4985.8     .09       0  5045.8     .17       0  5052.4     .11       0
Bank Sta=4985.8,5045.8
XS Rating Curve= 0 ,0
Exp/Cntr=0.3,0.1

Type RM Length L Ch R = 1 ,4680    ,467,467,467
BEGIN DESCRIPTION:
WFSJR 028 9.0
END DESCRIPTION:
XS GIS Cut Line= 3
      3761267.21     10222004.87      3760978.23     10221396.84
      3760637.83     10220672.33
#Sta/Elev= 30
  4326.8   261.7    4423  259.53  4530.3  256.29  4614.9  249.93  4743.4  248.85
  4862.5  248.78  4915.8   246.6  4928.9   248.2  4944.1  248.13  4966.8  248.92
  4989.5     242  4994.9  237.17    5000  237.17  5004.6  235.29  5008.1  235.29
  5012.3  240.96  5017.8  244.98  5028.5  248.33  5072.7  246.81  5086.2  249.12
  5116.9  250.33    5297  252.19  5388.2  254.57  5456.7  254.21  5462.2  253.26
  5502.3   256.3  5546.2  257.52    5673  260.12  5735.6     260  5800.5  262.77
#Mann= 7 ,-1 , 0
  4326.8     .11       0    4423     .17       0  4743.4     .11       0
  4944.1     .17       0  4966.8     .09       0  5028.5     .17       0
  5546.2     .11       0
#XS Ineff= 2 ,-1
    4650  4961.3  249.04  5035.1    5085  248.32
Permanent Ineff=
       F       F
Bank Sta=4966.8,5028.5
XS Rating Curve= 0 ,0
Exp/Cntr=0.3,0.1

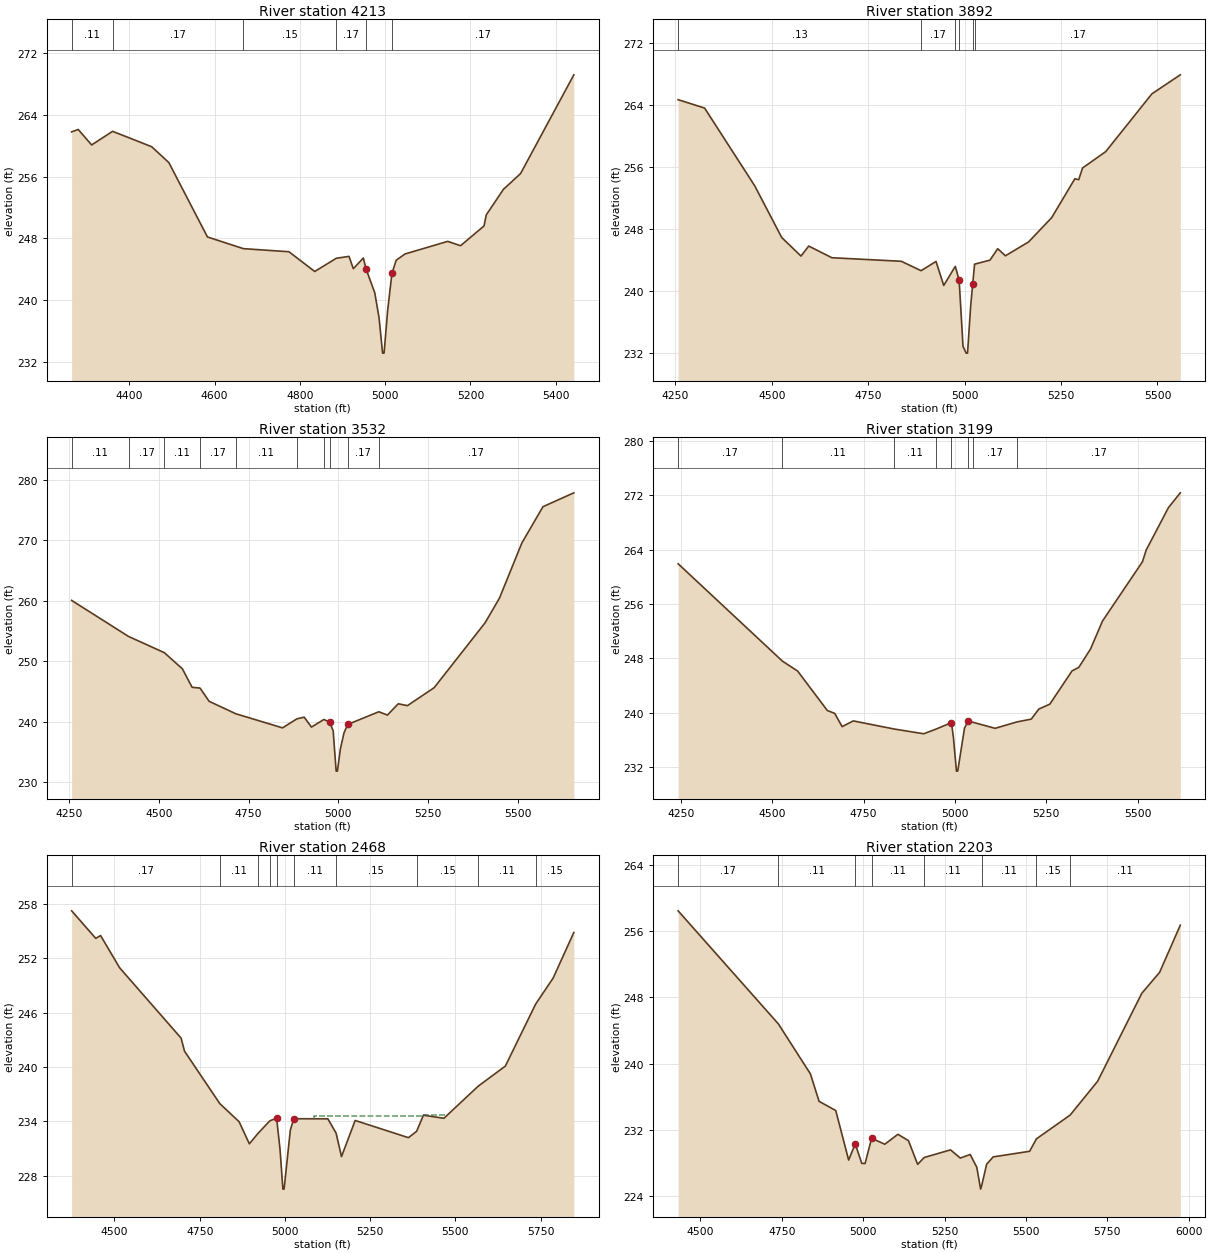
Type RM Length L Ch R = 1 ,4213    ,321,321,321
BEGIN DESCRIPTION:
WFSJR 028 8.0
END DESCRIPTION:
XS GIS Cut Line= 2
      3761434.87     10221977.74      3761310.59     10220806.92
#Sta/Elev= 30
    4265  261.77  4280.4  262.08  4311.9  260.08    4361  261.84  4452.7  259.85
  4492.9   257.8  4583.4  248.19  4667.7  246.68  4774.5  246.28  4834.9  243.73
  4885.6  245.44  4915.3  245.68  4925.4  244.09  4948.9  245.47  4955.5     244
  4975.6  240.99  4985.7  237.77    4994  233.18  4997.5  233.18  5005.8  238.66
  5015.9  243.48  5025.9  245.18  5046.5  245.99  5146.6  247.62  5176.8  247.06
  5231.8  249.61  5237.1  251.04  5277.3  254.34  5317.5  256.38  5442.4  269.14
#Mann= 6 ,-1 , 0
    4265     .11       0    4361     .17       0  4667.7     .15       0
  4885.6     .17       0  4955.5     .09       0  5015.9     .17       0
Bank Sta=4955.5,5015.9
XS Rating Curve= 0 ,0
Exp/Cntr=0.3,0.1

Type RM Length L Ch R = 1 ,3892    ,360,360,360
BEGIN DESCRIPTION:
WFSJR 028 7.0
END DESCRIPTION:
XS GIS Cut Line= 2
      3761662.15     10221939.74      3761640.45     10220637.62
#Sta/Elev= 30
    4257  264.65  4325.7  263.57  4455.7  253.56  4525.7  246.91  4575.7  244.52
  4595.7  245.81  4655.7  244.31  4835.8  243.85  4887.1  242.64  4925.8  243.83
  4945.8  240.74  4975.8   243.2  4985.8  241.41  4995.8   232.9    5004  232.03
  5007.5  232.03  5015.8  238.18    5021 240.936  5025.8  243.48  5065.8     244
  5085.8  245.47  5105.8  244.56  5165.8  246.34  5225.8  249.47  5285.8  254.47
  5295.8  254.35  5305.8  255.86  5365.8  257.96  5485.8  265.41  5559.3  267.85
#Mann= 6 ,-1 , 0
    4257     .13       0  4887.1     .17       0  4975.8     .12       0
  4985.8     .09       0    5021     .12       0  5025.8     .17       0
Bank Sta=4985.8,5021
XS Rating Curve= 0 ,0
Exp/Cntr=0.3,0.1

Type RM Length L Ch R = 1 ,3532    ,333,333,333
BEGIN DESCRIPTION:
WFSJR 028 6.0
END DESCRIPTION:
XS GIS Cut Line= 2
      3762091.83     10221944.02      3761913.95     10220555.67
#Sta/Elev= 30
  4256.8  260.08  4415.5  254.11  4515.1  251.43  4565.4  248.76  4592.5   245.7
  4614.6  245.57    4640  243.38  4714.2  241.32  4844.5  238.98  4884.8  240.48
    4905  240.75  4925.2  239.11    4960  240.37  4975.6  239.93  4985.7  238.51
    4994  231.82  4997.5  231.82  5005.8   235.5  5015.9  238.15    5026  239.54
    5113  241.65  5136.9   241.1  5167.1  242.97  5192.7  242.66  5267.3  245.64
  5409.1  256.37  5449.4  260.48  5511.4  269.56  5570.4  275.59  5656.5  277.89
#Mann= 10 ,-1 , 0
  4256.8     .11       0  4415.5     .17       0  4515.1     .11       0
  4614.6     .17       0  4714.2     .11       0  4884.8     .11       0
    4960     .17       0  4975.6     .09       0    5026     .17       0
    5113     .17       0
Bank Sta=4975.6,5026
XS Rating Curve= 0 ,0
Exp/Cntr=0.3,0.1

Type RM Length L Ch R = 1 ,3199    ,731,731,731
BEGIN DESCRIPTION:
WFSJR 028 5.0
END DESCRIPTION:
XS GIS Cut Line= 2
      3762430.39     10221883.35      3762196.02     10220529.18
#Sta/Elev= 30
  4242.4  261.92  4527.9  247.61  4569.5  246.15  4650.7  240.36    4671  239.93
  4691.2  237.99  4721.7  238.83  4833.3  237.64  4914.5  236.94    4947   237.6
  4990.4  238.57  4995.7  236.44  5004.1  231.45  5007.6  231.45  5026.2  237.79
  5036.3  238.76  5049.8  238.62    5110  237.74  5169.7  238.68  5208.8  239.09
  5229.5  240.57  5259.6  241.29  5320.5  246.18  5338.9  246.69  5371.2  249.41
  5403.7  253.49  5513.1  262.21  5523.4  263.94  5584.3  270.17  5616.7  272.34
#Mann= 8 ,-1 , 0
  4242.4     .17       0  4527.9     .11       0  4833.3     .11       0
    4947     .15       0  4990.4     .07       0  5036.3     .15       0
  5049.8     .17       0  5169.7     .17       0
Bank Sta=4990.4,5036.3
XS Rating Curve= 0 ,0
Exp/Cntr=0.3,0.1

Type RM Length L Ch R = 1 ,2468    ,265,265,265
BEGIN DESCRIPTION:
WFSJR 028 4.0
END DESCRIPTION:
XS GIS Cut Line= 2
      3762899.13     10221761.73      3762964.24     10220290.37
#Sta/Elev= 30
  4374.5  257.24  4445.2   254.2  4459.4  254.51  4515.3  250.95  4695.5  243.19
  4705.5  241.75  4808.8  235.97  4865.6  233.96  4895.7  231.52  4920.8  232.66
  4955.7  234.06  4975.7  234.35  4985.8  230.84    4994  226.52  4997.5  226.52
  5015.8  233.02  5025.8  234.29  5125.9  234.28    5150  232.71  5165.9  230.11
    5206   234.1  5362.3   232.2  5386.2   232.9  5406.2  234.68  5466.2  234.34
  5566.7  237.88  5646.4   240.1  5735.5  246.96  5786.5  249.81  5847.3  254.85
#Mann= 10 ,-1 , 0
  4374.5     .17       0  4808.8     .11       0  4920.8     .15       0
  4955.7     .11       0  4975.7     .06       0  5025.8     .11       0
    5150     .15       0  5386.2     .15       0  5566.7     .11       0
  5735.5     .15       0
#XS Ineff= 3 ,-1
    4830  4975.7  234.35  5085.9    5405  234.54  5406.2    5475  234.68
Permanent Ineff=
       F       F       F
Bank Sta=4975.7,5025.8
XS Rating Curve= 0 ,0
Exp/Cntr=0.3,0.1

Type RM Length L Ch R = 1 ,2203    ,382,382,382
BEGIN DESCRIPTION:
WFSJR 028 3.0
END DESCRIPTION:
XS GIS Cut Line= 3
      3763098.79     10221740.06      3763236.87      10220715.2
      3763094.44     10220227.49
#Sta/Elev= 30
  4431.7  258.44  4739.8  244.78    4838  238.75  4864.6  235.44  4915.8  234.33
  4955.4  228.35  4975.6  230.31  4995.7  227.95  5005.8  227.93    5026  230.98
  5066.4  230.26  5106.7  231.46  5139.1  230.69  5167.3  227.83  5187.5  228.66
  5268.2  229.58  5298.4  228.59  5328.7  229.02  5348.9  227.48  5360.7  224.84
  5364.4  225.34  5379.2  227.85  5399.3  228.73  5511.2  229.41  5532.1  230.91
  5635.6  233.78  5720.1  237.87  5855.6  248.48  5910.5  251.02  5973.9  256.71
#Mann= 8 ,-1 , 0
  4431.7     .17       0  4739.8     .11       0  4975.6     .06       0
    5026     .11       0  5187.5     .11       0  5364.4     .11       0
  5532.1     .15       0  5635.6     .11       0
#XS Ineff= 2 ,-1
    4935  4975.6  230.31  5106.7    5590  231.46
Permanent Ineff=
       T       T
Bank Sta=4975.6,5026
XS Rating Curve= 0 ,0
Exp/Cntr=0.3,0.1

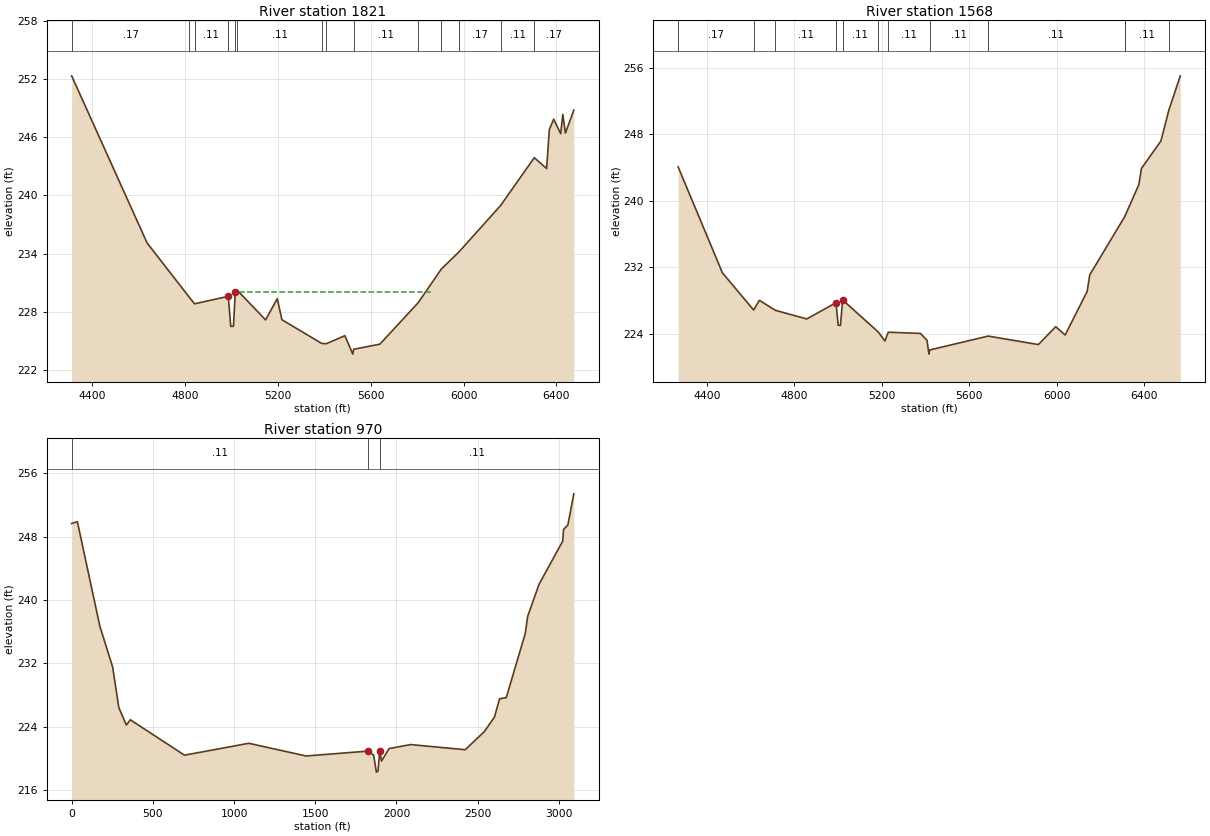
Type RM Length L Ch R = 1 ,1821    ,253,253,253
BEGIN DESCRIPTION:
WFSJR 028 2.0
END DESCRIPTION:
XS GIS Cut Line= 3
      3763450.35     10221952.73      3763580.42     10220670.04
      3763446.14     10219805.17
#Sta/Elev= 30
  4310.6  252.33  4635.9  235.09  4817.3  229.51  4840.4  228.82  4985.7  229.59
  4996.3   226.5    5008   226.5  5015.9  230.04  5025.3  230.19  5146.5  227.16
  5196.8  229.35  5216.9  227.18  5387.8  224.74  5407.9   224.7  5488.3  225.53
  5522.4  223.63  5526.2  224.13  5639.3  224.66  5804.5  228.94  5904.5  232.42
  5979.2  234.15  6159.6  238.96  6304.7  243.89  6357.8  242.77  6369.6  246.79
  6388.2  247.86  6418.5  246.36  6427.5  248.36  6438.8  246.42  6475.1   248.8
#Mann= 14 ,-1 , 0
  4310.6     .17       0  4817.3     .15       0  4840.4     .11       0
  4985.7     .06       0  5015.9     .11       0  5025.3     .11       0
  5387.8     .11       0  5407.9     .11       0  5526.2     .11       0
  5804.5     .17       0  5904.5     .11       0  5979.2     .17       0
  6159.6     .11       0  6304.7     .17       0
#XS Ineff= 2 ,-1
    4740  4774.6  230.76    5036    5870  230.06
Permanent Ineff=
       T       T
Bank Sta=4985.7,5015.9
XS Rating Curve= 0 ,0
Exp/Cntr=0.3,0.1

Type RM Length L Ch R = 1 ,1568    ,598,598,598
BEGIN DESCRIPTION:
WFSJR 028 1.0
END DESCRIPTION:
XS GIS Cut Line= 3
      3763615.28      10221991.8      3763884.38     10220533.47
      3763715.23     10219735.45
#Sta/Elev= 30
    4268  244.06    4471  231.31  4613.6  226.85  4640.1  228.01  4712.9  226.81
  4857.1  225.77  4990.7  227.72  5000.9     225  5011.1     225  5021.1  228.05
  5183.9  224.21  5214.4  223.12    5230 224.175  5377.1  224.03  5407.2  223.21
  5416.1  221.54  5419.8  222.04  5687.4  223.71    5917  222.69  5996.5  224.84
  6039.6  223.84  6140.4  229.08  6152.1  231.07  6311.5  238.04  6311.6  238.04
    6377  241.93  6388.8  243.87  6477.9  247.17  6514.1  250.87  6566.7  255.01
#Mann= 12 ,-1 , 0
    4268     .17       0  4613.6     .15       0  4712.9     .11       0
  4990.7     .06       0  5021.1     .11       0  5183.9     .11       0
    5230     .11       0  5419.8     .11       0  5687.4     .11       0
  6311.5     .17       0  6311.6     .11       0  6514.1     .17       0
#XS Ineff= 3 ,-1
    4570  4640.1  228.01    4645  4990.7  227.72  5026.2    6135  227.86
Permanent Ineff=
       F       T       T
Bank Sta=4990.7,5021.1
XS Rating Curve= 0 ,0
Exp/Cntr=0.3,0.1

Type RM Length L Ch R = 1 ,970     ,0,0,0
XS GIS Cut Line= 4
      3763557.38     10222107.82      3764188.11     10221861.88
      3764350.02     10221227.75      3763791.76     10219555.74
#Sta/Elev= 30
       0  249.64    35.2  249.88   173.8  236.67   252.6  231.51   290.3   226.4
   336.9   224.2   361.4  224.86   694.7  220.39  1090.7  221.89  1443.7  220.29
    1823   220.9  1859.8   220.4  1876.2  218.25  1886.2  218.36  1897.3  220.94
  1907.8  219.64  1954.6  221.22    2087  221.73  2423.4  221.08  2540.4  223.35
  2603.6   225.2  2635.2  227.51  2676.2  227.65  2793.4  235.77  2807.9  237.91
  2877.7  241.95  3023.8  247.42  3029.1   248.9  3055.4  249.45  3092.3  253.39
#Mann= 3 , 0 , 0
       0     .11       0    1823     .06       0  1897.3     .11       0
#XS Ineff= 1 ,-1
     500  1090.7  221.89
Permanent Ineff=
       F
Bank Sta=1823,1897.3
XS Rating Curve= 0 ,0
Exp/Cntr=0.3,0.1

Chan Stop Cuts=-1
Use User Specified Reach Order=0
Composite Channel Slope=5