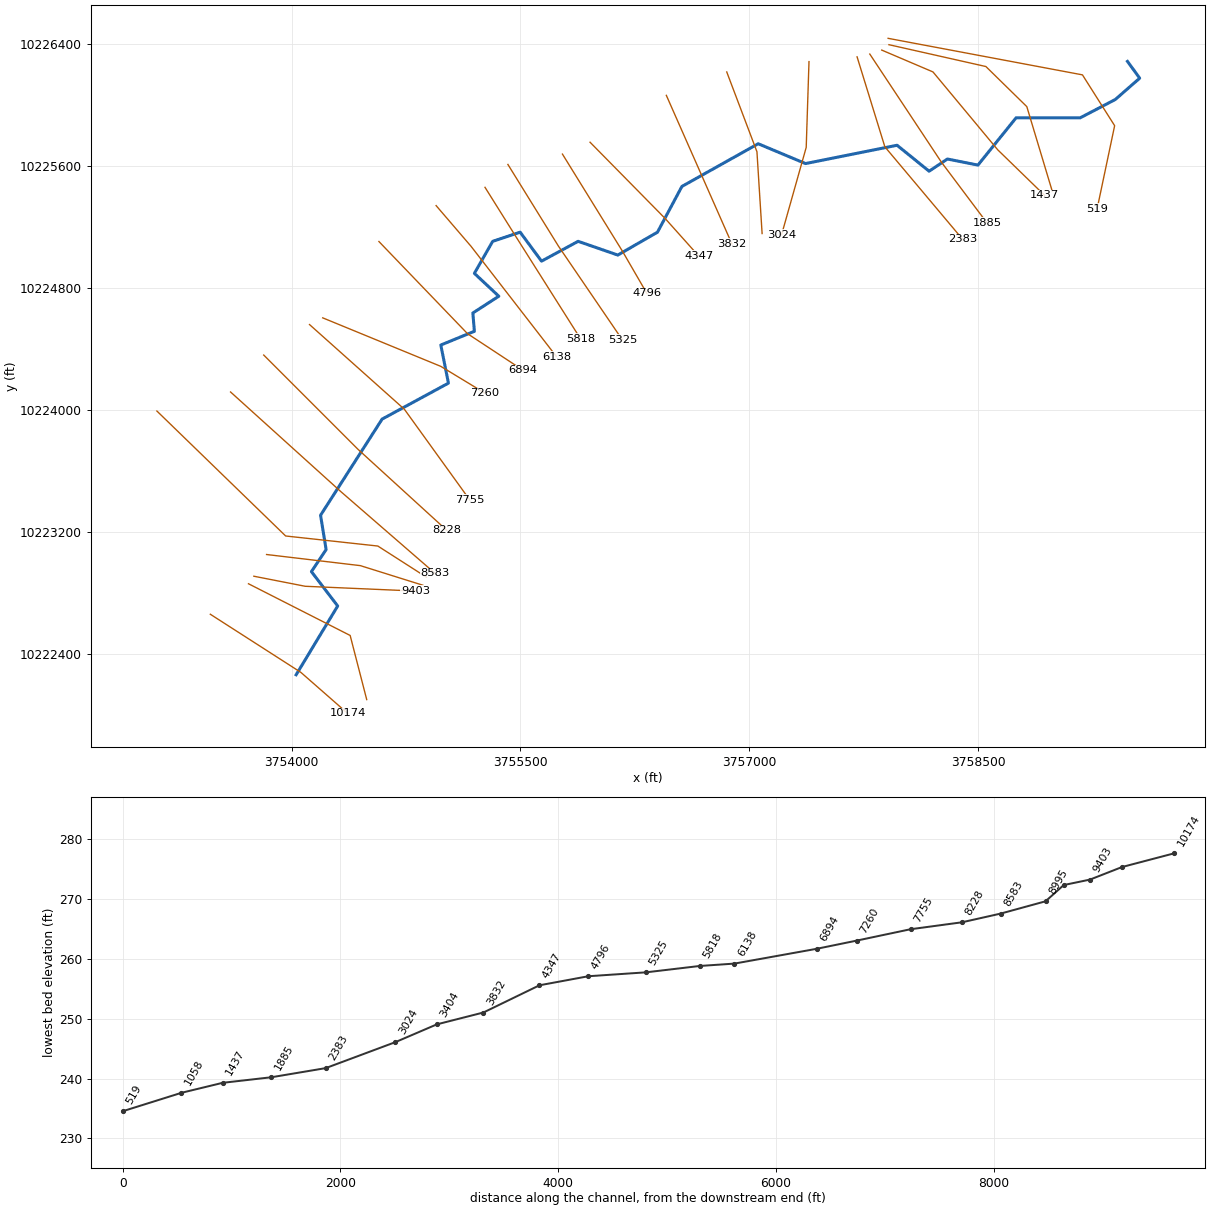
--- WFSJR 030.prj (project) ---

Proj Title=WFSJR 030 Base Level Engineering
Current Plan=p01
Default Exp/Contr=0.3,0.1
English Units
Geom File=g01
Flow File=f01
Plan File=p01
Y Axis Title=Elevation
X Axis Title(PF)=Main Channel Distance
X Axis Title(XS)=Station
BEGIN DESCRIPTION:
WFSJR 030
END DESCRIPTION:
DSS Export Rating Curves= 0
DSS Export Rating Curve Sorted= 0
DSS Export Volume Flow Curves= 0
DXF OffsetX= 0
DXF OffsetY= 0
DXF ScaleX= 1
DXF ScaleY= 10

--- WFSJR 030.p01 (plan) ---

Plan Title=Multiple Run
Program Version=4.10
Short Identifier=Multiple
Geom File=g01
Flow File=f01
Subcritical Flow
K Sum by GR= 0
Std Step Tol= 0.01
Critical Tol= 0.01
Num of Std Step Trials= 20
Max Error Tol= 0.3
Flow Tol Ratio= 0.001
Split Flow NTrial= 30
Split Flow Tol= 0.02
Split Flow Ratio= 0.02
Log Output Level= 0
Friction Slope Method= 1
Unsteady Friction Slope Method= 2
Unsteady Bridges Friction Slope Method= 1
Parabolic Critical Depth
Global Vel Dist= 1 , 1 , 1
Global Log Level= 0
CheckData=True
Encroach Param=-1 ,0,0, 0
BEGIN DESCRIPTION:
Multiple Run
END DESCRIPTION:
Computation Interval=1HOUR
Output Interval=1HOUR
Run HTab= 0
Run UNet= 0
Run PostProcess= 0
Run WQNet= 0
UNET Theta= 1
UNET Theta Warmup= 1
UNET ZTol= 0.02
UNET ZSATol= 0.05
UNET MxIter= 20
UNET MaxInSteps= 0
UNET DtIC= 0
UNET DtMin= 0
UNET MaxCRTS= 20
UNET WFStab= 2
UNET SFStab= 1
UNET WFX= 1
UNET SFX= 1
UNET DSS MLevel= 4
UNET DZMax Abort= 100
UNET Convert EG Bridges= 0
UNET Use Existing IB Tables=-1
UNET Froude Reduction=False
UNET Froude Limit= 1
UNET Froude Power= 10
UNET Time Slicing=0,0, 5
UNET Junction Losses=0
Instantaneous Interval=1HOUR
Write IC File= 0
Write IC File at Sim End=0
Echo Input=False
Echo Parameters=False
Echo Output=False
Write Detailed= 0
WQ AD Non Conservative
WQ ULTIMATE=-1
WQ Max Comp Step=1HOUR
WQ Output Interval=15MIN
WQ Output Selected Increments= 0
WQ Output face flow=0
WQ Output face velocity=0
WQ Output face area=0
WQ Output face dispersion=0
WQ Output cell volume=0
WQ Output cell surface area=0
WQ Output cell continuity=0
WQ Output cumulative cell continuity=0
WQ Output face conc=0
WQ Output face dconc_dx=0
WQ Output face courant=0
WQ Output face peclet=0
WQ Output face adv mass=0
WQ Output face disp mass=0
WQ Output cell mass=0
WQ Output cell source sink temp=0
WQ Output cell source sink nsm=0
WQ Output MaxMinRange=-1
WQ Daily Max Min Mean=-1
WQ Daily Range=0
WQ Daily Time=0
WQ Create Restart=0
WQ Fixed Restart=0
WQ System Summary=0
WQ Use Fixed Temperature=0
Sorting and Armoring Iterations= 10
XS Update Threshold= 0.02
Hydraulics Update Threshold= 0.02
Energy Slope Method= 1
Volume Change Method= 0
XS Weighting Method= 0
Number of US Weighted Cross Sections= 1
Number of DS Weighted Cross Sections= 1
Upstream XS Weight=0.25
Main XS Weight=0.5
Downstream XS Weight=0.25
Number of DS XS's Weighted with US Boundary= 1
Upstream Boundary Weight= 1
Weight of XSs Associated with US Boundary= 0
Number of US XS's Weighted with DS Boundary= 1
Downstream Boundary Weight= 0.5
Weight of XSs Associated with DS Boundary= 0.5
Sediment Output Level= 4
Mass or Volume Output= 0
Output Increment Type= 1
Profile and TS Output Increment= 10
XS Output Flag= 0
XS Output Increment= 10
Disregard all LS=0
Disregard all Conn=0
Disregard all Breaches=0
Disregard all Pumps=0

--- WFSJR 030.f01 (steady flow) ---

Flow Title=Multiple
Program Version=4.10
Number of Profiles= 7
Profile Names=10-year,25-year,50-year,1pct_min,100-year,1pct_plu,500-year
River Rch & RM=WFSJR 030,Reach-1         ,10174
     775    1072    1471     664    2006    6058    3856
River Rch & RM=WFSJR 030,Reach-1         ,8228
     958    1326    1818     819    2474    7471    4737
Boundary for River Rch & Prof#=WFSJR 030,Reach-1         , 1
Up Type= 0
Dn Type= 3
Dn Slope=0.007
Boundary for River Rch & Prof#=WFSJR 030,Reach-1         , 2
Up Type= 0
Dn Type= 3
Dn Slope=0.007
Boundary for River Rch & Prof#=WFSJR 030,Reach-1         , 3
Up Type= 0
Dn Type= 3
Dn Slope=0.007
Boundary for River Rch & Prof#=WFSJR 030,Reach-1         , 4
Up Type= 0
Dn Type= 3
Dn Slope=0.007
Boundary for River Rch & Prof#=WFSJR 030,Reach-1         , 5
Up Type= 0
Dn Type= 3
Dn Slope=0.007
Boundary for River Rch & Prof#=WFSJR 030,Reach-1         , 6
Up Type= 0
Dn Type= 3
Dn Slope=0.007
Boundary for River Rch & Prof#=WFSJR 030,Reach-1         , 7
Up Type= 0
Dn Type= 3
Dn Slope=0.007
DSS Import GetInterval= 0
DSS Import GetPeak= 0
DSS Import FillOption= 0

--- WFSJR 030.g01 (geometry) ---

Geom Title=Existing Conditions
Program Version=4.10

River Reach=WFSJR 030       ,Reach-1
Reach XY= 30
      3754030.24     10222264.33      3754302.47     10222715.35
      3754130.31     10222940.68      3754226.61     10223085.33
      3754190.17      10223310.3      3754593.62     10223940.94
      3755028.23     10224176.84      3754978.23     10224426.84
      3755198.23     10224516.84      3755188.23     10224636.84
      3755358.23     10224746.84      3755198.23     10224896.84
      3755318.23     10225106.84      3755498.23     10225166.84
      3755638.23     10224976.84      3755878.23     10225106.84
      3756138.23     10225016.84      3756398.23     10225166.84
      3756558.23     10225466.84      3757058.23     10225746.84
      3757368.23     10225616.84      3757968.23     10225736.84
      3758178.23     10225566.84      3758298.23     10225646.84
      3758498.23     10225606.84      3758748.23     10225916.84
      3759168.23     10225916.84      3759398.23     10226036.84
      3759558.23     10226176.84      3759478.23     10226286.84

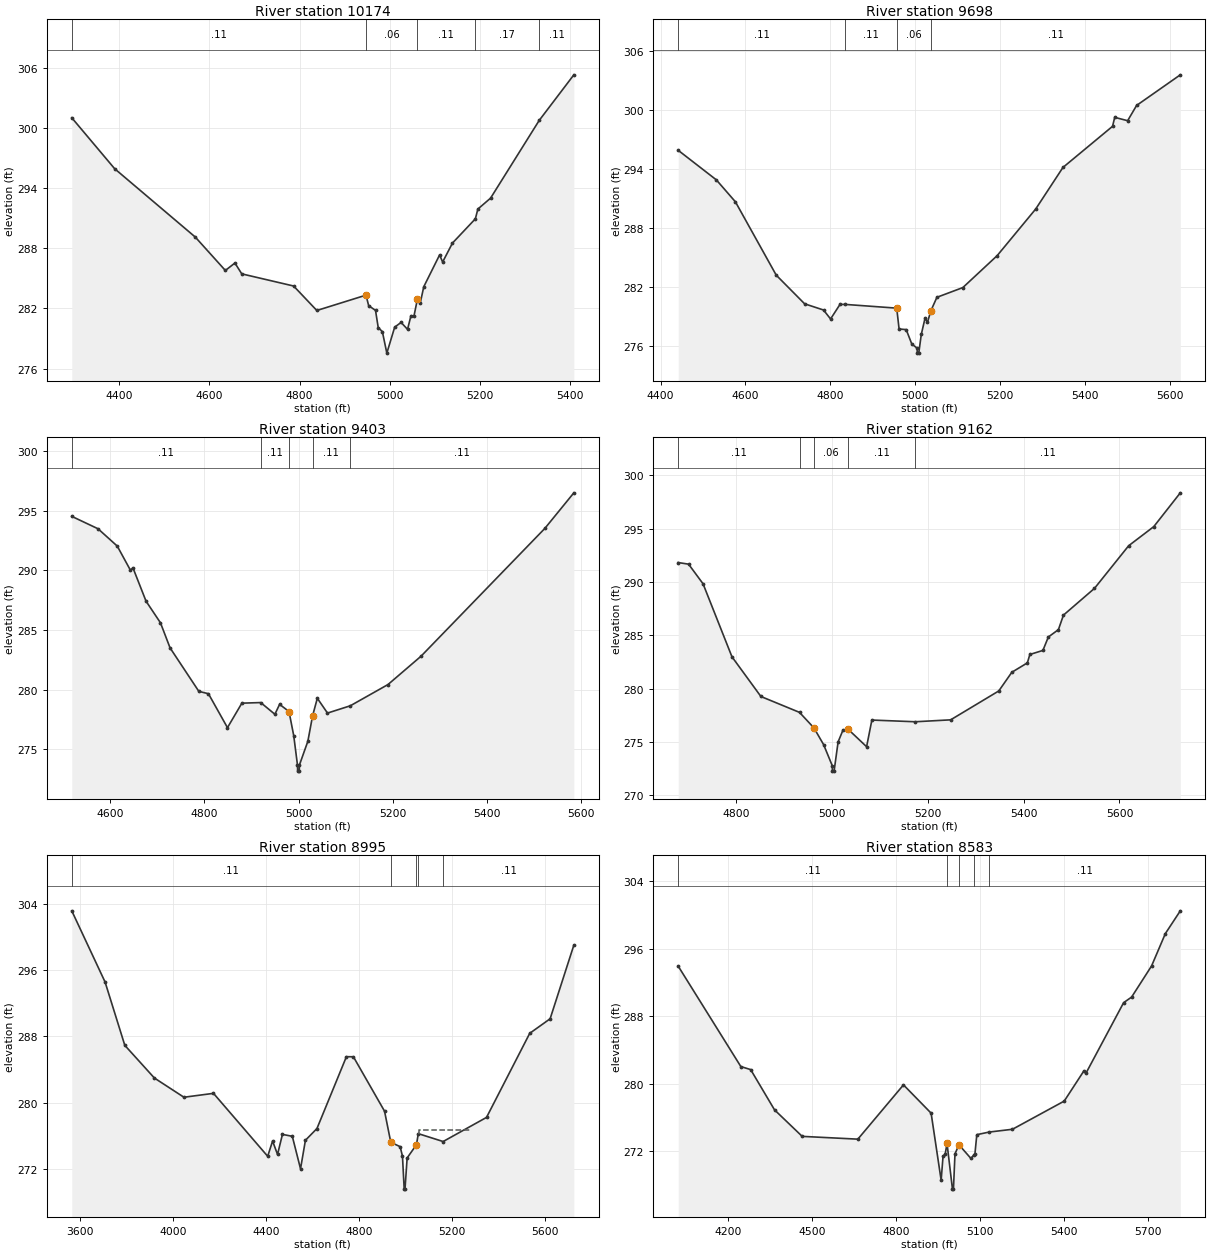
Type RM Length L Ch R = 1 ,10174   ,476,476,476
BEGIN DESCRIPTION:
WFSJR 030 19.0
END DESCRIPTION:
XS GIS Cut Line= 3
      3753467.83     10222661.08      3754061.14     10222279.92
      3754367.88     10222011.04
#Sta/Elev= 30
  4294.8  301.01  4389.9  295.93  4568.6  289.12  4635.3  285.79  4656.5  286.53
  4671.7  285.45  4786.6  284.24  4838.1   281.8  4947.1  283.33    4953  282.28
  4968.2  281.81  4974.2   280.1  4983.4  279.69  4993.3  277.55  5010.7  280.14
  5024.9  280.61  5039.2  279.92  5046.8  281.28  5053.4  281.23    5061  282.91
  5067.6  282.59  5075.2  284.17  5110.3  287.34    5117  286.63  5138.8  288.52
  5189.6  290.94  5195.1  291.91  5223.3     293    5331  300.74  5407.9  305.29
#Mann= 5 ,-1 , 0
  4294.8     .11       0  4947.1     .06       0    5061     .11       0
  5189.6     .17       0    5331     .11       0
#XS Ineff= 1 ,-1
    4790  4947.1  283.33
Permanent Ineff=
       F
Bank Sta=4947.1,5061
XS Rating Curve= 0 ,0
Exp/Cntr=0.3,0.1

Type RM Length L Ch R = 1 ,9698    ,295,295,295
BEGIN DESCRIPTION:
WFSJR 030 18.0
END DESCRIPTION:
XS GIS Cut Line= 3
      3753717.86     10222861.06      3754384.15     10222521.99
      3754492.68     10222101.47
#Sta/Elev= 30
  4441.7  295.88  4531.4  292.88  4576.3  290.65  4672.4   283.2  4739.2  280.29
  4783.7  279.66  4800.3  278.75  4822.5  280.23  4834.4  280.23    4956  279.85
  4961.6  277.73  4978.3  277.67  4991.5  276.21  5004.1  275.78  5004.4  275.28
  5007.9  275.28  5013.9  277.19  5022.8  278.85  5028.4  278.41  5036.4  279.58
  5050.6  280.95  5111.7  281.94  5192.4  285.18  5283.2  289.92  5347.3  294.14
  5464.1  298.32  5469.2  299.23  5499.6  298.89  5520.7  300.44  5623.6  303.55
#Mann= 4 ,-1 , 0
  4441.7     .11       0  4834.4     .11       0    4956     .06       0
  5036.4     .11       0
Bank Sta=4956,5036.4
XS Rating Curve= 0 ,0
Exp/Cntr=0.3,0.1

Type RM Length L Ch R = 1 ,9403    ,241,241,241
BEGIN DESCRIPTION:
WFSJR 030 17.0
END DESCRIPTION:
XS GIS Cut Line= 3
      3753753.06     10222910.53      3754089.89     10222844.56
      3754812.08     10222813.31
#Sta/Elev= 30
  4518.3  294.51  4574.1  293.47  4614.9  292.02    4643  289.99  4648.1  290.21
    4676  287.41  4706.6   285.6    4727   283.5  4788.1  279.86  4808.5  279.66
  4848.9  276.82  4879.5  278.87  4919.5  278.92  4949.6  277.94  4959.6  278.77
  4979.6  278.17  4989.6  276.15  4997.6  273.68  4997.9  273.18  5001.4  273.18
  5001.6  273.68  5019.6  275.68  5029.6   277.8  5039.7  279.28  5061.3  278.04
  5109.7  278.65  5189.8  280.43  5259.9   282.8  5522.8   293.5  5584.4  296.48
#Mann= 5 ,-1 , 0
  4518.3     .11       0  4919.5     .11       0  4979.6     .06       0
  5029.6     .11       0  5109.7     .11       0
#XS Ineff= 1 ,-1
  5039.7    5150  279.28
Permanent Ineff=
       F
Bank Sta=4979.6,5029.6
XS Rating Curve= 0 ,0
Exp/Cntr=0.3,0.1

Type RM Length L Ch R = 1 ,9162    ,167,167,167
BEGIN DESCRIPTION:
Mapping XS 650a5429
END DESCRIPTION:
XS GIS Cut Line= 3
      3753836.41     10223052.89        3754451.     10222979.97
      3754860.73      10222851.5
#Sta/Elev= 30
  4678.7  291.83  4700.3  291.68  4730.5  289.84  4790.9  282.99  4851.3  279.27
  4931.9  277.78  4962.1  276.32  4982.3  274.75  5000.4  272.77  5000.6  272.27
  5004.1  272.27  5012.5  275.01  5022.5   276.1  5032.6  276.23    5072  274.56
    5083  277.06  5173.6   276.9  5247.5  277.08    5348  279.79  5375.2  281.54
  5407.6  282.42  5412.9  283.21  5440.1  283.59  5451.5  284.85  5472.5  285.54
    5483   286.9  5547.8  289.41  5619.2  293.41  5671.6   295.2    5727  298.37
#Mann= 5 ,-1 , 0
  4678.7     .11       0  4931.9     .11       0  4962.1     .06       0
  5032.6     .11       0  5173.6     .11       0
Bank Sta=4962.1,5032.6
XS Rating Curve= 0 ,0
Exp/Cntr=0.3,0.1

Type RM Length L Ch R = 1 ,8995    ,412,412,412
BEGIN DESCRIPTION:
Mapping XS e3998e0d
END DESCRIPTION:
XS GIS Cut Line= 4
      3753117.66     10223993.87      3753961.42     10223174.42
      3754565.58     10223108.45       3754883.9     10222904.31
#Sta/Elev= 30
  3563.5  303.12    3707  294.53  3791.9   286.9  3919.2  282.96  4046.5  280.64
  4173.8  281.11  4407.2  273.52  4428.3  275.36  4449.6  273.74  4470.7  276.16
  4513.2  275.93  4548.6  272.01  4569.7  275.45  4619.4  276.87  4746.2  285.53
  4776.3  285.52  4910.4  278.96  4937.3  275.21  4977.5  274.68  4987.6  273.54
    4995  269.56  4998.5  269.56  5007.7  273.32  5047.9  274.92  5055.7  276.25
  5162.7   275.3  5349.6  278.21  5535.7  288.35  5623.4   290.1  5725.6  298.98
#Mann= 5 ,-1 , 0
  3563.5     .11       0  4937.3     .06       0  5047.9     .11       0
  5055.7     .15       0  5162.7     .11       0
#XS Ineff= 2 ,-1
    3790  4746.2  285.53    5058    5280  276.64
Permanent Ineff=
       F       F
Bank Sta=4937.3,5047.9
XS Rating Curve= 0 ,0
Exp/Cntr=0.3,0.1

Type RM Length L Ch R = 1 ,8583    ,355,355,355
BEGIN DESCRIPTION:
WFSJR 030 16.0
END DESCRIPTION:
XS GIS Cut Line= 3
      3753600.28     10224118.88      3754322.96     10223465.54
      3754940.76     10222929.14
#Sta/Elev= 30
  4023.2  293.92  4246.7  282.03  4281.8  281.67    4367   276.9  4465.7  273.76
  4664.4  273.43  4827.3  279.86    4926  276.51  4961.8  268.56  4968.6  271.42
    4976  271.63  4982.8  272.92  5002.2  267.51  5005.7  267.51  5011.2  271.69
  5025.4  272.76  5068.2  271.14  5078.2  271.55  5082.4  271.68  5089.1  273.96
  5132.9  274.27  5216.3   274.6  5401.2  277.94  5471.8  281.54  5479.4  281.28
  5613.2   289.6  5641.7  290.26    5713  293.95  5762.3  297.79  5815.6  300.48
#Mann= 5 ,-1 , 0
  4023.2     .11       0  4982.8     .06       0  5025.4     .11       0
  5078.2     .11       0  5132.9     .11       0
#XS Ineff= 1 ,-1
    4250  4827.3  279.86
Permanent Ineff=
       F
Bank Sta=4982.8,5025.4
XS Rating Curve= 0 ,0
Exp/Cntr=0.3,0.1

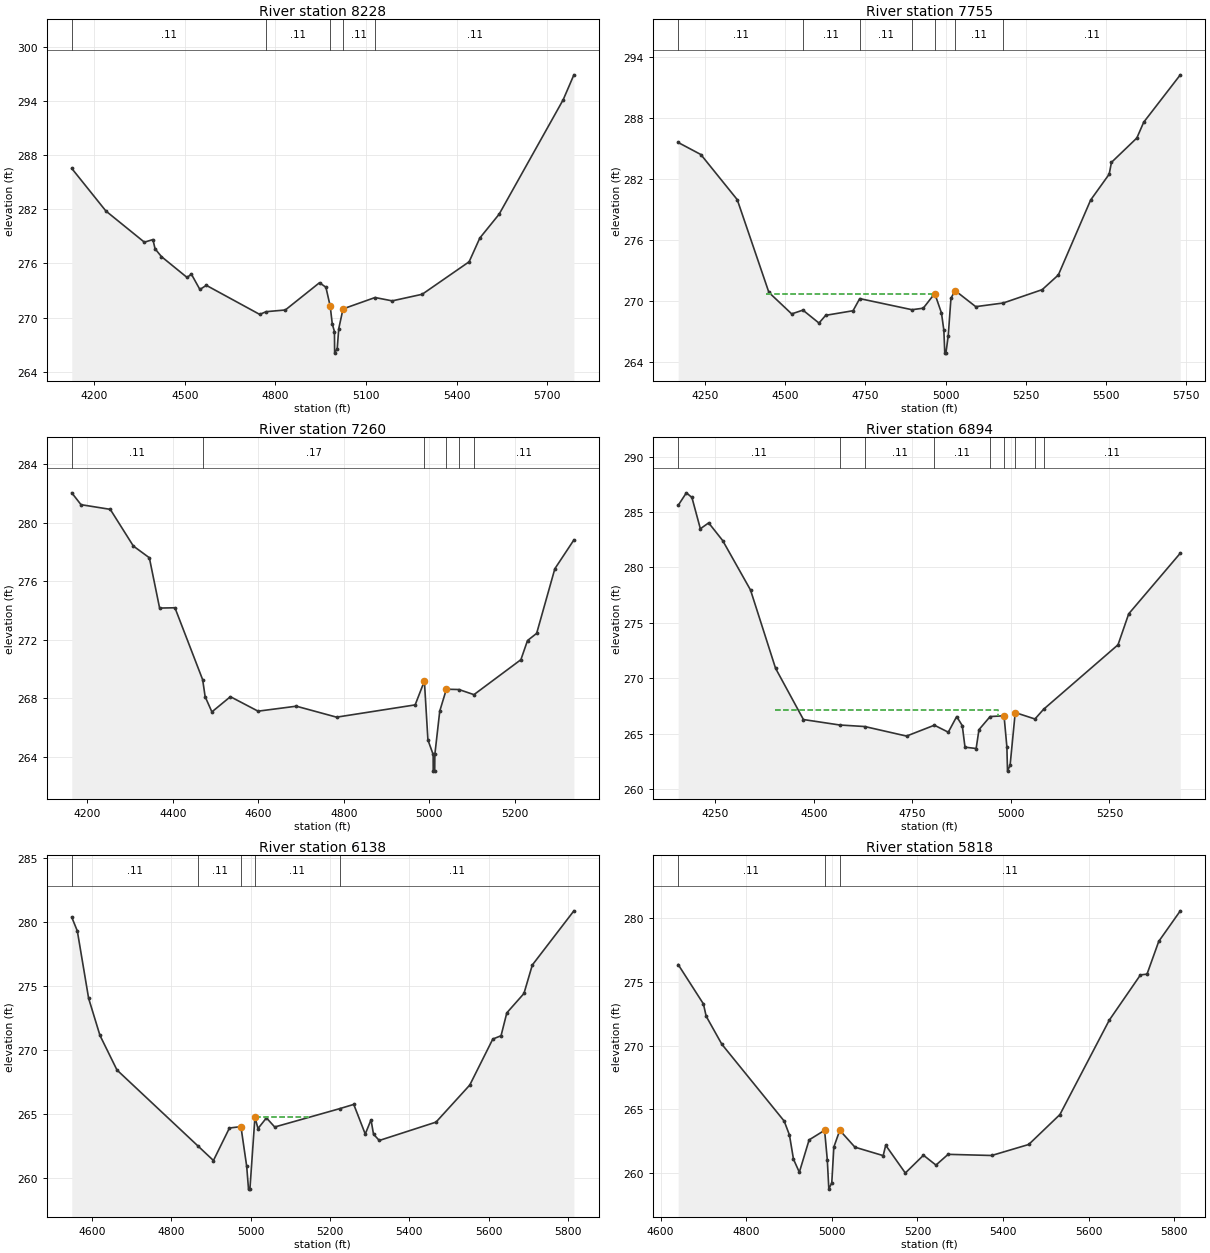
Type RM Length L Ch R = 1 ,8228    ,473,473,473
BEGIN DESCRIPTION:
WFSJR 030 15.0
END DESCRIPTION:
XS GIS Cut Line= 3
      3753817.87     10224361.05      3754435.59     10223742.75
      3755017.86     10223211.06
#Sta/Elev= 30
    4126  286.52  4239.1   281.8  4366.4  278.35  4394.7  278.64  4401.7  277.62
    4423  276.75  4507.8  274.44    4522  274.81  4550.2  273.11  4571.5  273.57
  4748.2  270.35  4769.4  270.65  4833.1  270.84  4946.2  273.86  4967.4  273.36
  4981.6  271.26  4988.6  269.27  4995.7  268.45  4996.3  266.06  5004.9  266.56
  5009.9  268.76  5024.1  270.96  5130.1  272.22  5186.9  271.85  5286.2  272.58
  5441.6  276.18    5477  278.81  5540.9  281.45    5753  294.13  5788.5  296.89
#Mann= 5 ,-1 , 0
    4126     .11       0  4769.4     .11       0  4981.6     .06       0
  5024.1     .11       0  5130.1     .11       0
#XS Ineff= 1 ,-1
    4520  4946.2  273.86
Permanent Ineff=
       T
Bank Sta=4981.6,5024.1
XS Rating Curve= 0 ,0
Exp/Cntr=0.3,0.1

Type RM Length L Ch R = 1 ,7755    ,495,495,495
BEGIN DESCRIPTION:
WFSJR 030 14.0
END DESCRIPTION:
XS GIS Cut Line= 3
      3754117.83     10224561.09      3754739.76     10224005.27
      3755167.88     10223411.03
#Sta/Elev= 30
  4165.9  285.57  4236.6  284.39  4350.2  279.96  4448.9  270.86    4520  268.75
  4555.1  269.12  4605.2  267.85  4626.1  268.61  4711.4  269.06  4732.3  270.25
  4895.3  269.16  4930.4  269.31  4966.3  270.75  4987.3  268.84  4994.8  267.13
  4997.6   264.9  5001.1   264.9  5008.3  266.57  5016.9  270.28  5029.8  271.04
  5094.2  269.46  5180.1  269.82  5301.6  271.13  5351.9  272.57  5452.6  279.92
  5510.5  282.46  5517.6  283.62  5596.8  286.01  5618.2  287.56  5732.4  292.21
#Mann= 7 ,-1 , 0
  4165.9     .11       0  4555.1     .11       0  4732.3     .11       0
  4895.3     .11       0  4966.3     .06       0  5029.8     .11       0
  5180.1     .11       0
#XS Ineff= 2 ,-1
    4440  4958.8  270.75  5029.8    5295  271.04
Permanent Ineff=
       T       T
Bank Sta=4966.3,5029.8
XS Rating Curve= 0 ,0
Exp/Cntr=0.3,0.1

Type RM Length L Ch R = 1 ,7260    ,366,366,366
BEGIN DESCRIPTION:
WFSJR 030 13.0
END DESCRIPTION:
XS GIS Cut Line= 3
      3754204.48     10224604.97      3754978.23     10224286.84
      3755267.86     10224111.06
#Sta/Elev= 30
  4163.4  282.03    4185  281.22  4253.5   280.9  4307.6  278.39    4345  277.59
    4369  274.15  4404.9  274.17  4469.8  269.25  4475.6  268.09  4491.4  267.05
  4534.7  268.09  4599.5   267.1    4689  267.44  4783.3  266.69  4967.2  267.53
  4988.8  269.16  4997.1  265.13  5009.3  264.14  5009.5     263    5013     263
  5013.3  264.14  5024.8  267.11  5040.3   268.6  5069.7  268.58  5104.8  268.23
  5214.7  270.62  5230.2  271.93  5251.6  272.42  5294.2  276.84  5338.8  278.81
#Mann= 6 ,-1 , 0
  4163.4     .11       0  4469.8     .17       0  4988.8     .06       0
  5040.3     .11       0  5069.7     .11       0  5104.8     .11       0
#XS Ineff= 1 ,-1
    4455  4988.8  269.16
Permanent Ineff=
       T
Bank Sta=4988.8,5040.3
XS Rating Curve= 0 ,0
Exp/Cntr=0.3,0.1

Type RM Length L Ch R = 1 ,6894    ,756,756,756
BEGIN DESCRIPTION:
WFSJR 030 12.0
END DESCRIPTION:
XS GIS Cut Line= 3
      3754572.73     10225105.49      3755153.09     10224501.29
      3755517.82     10224261.09
#Sta/Elev= 30
  4155.3   285.6  4176.1  286.73  4190.2  286.31  4211.6  283.49  4232.7  284.02
  4268.2  282.43  4338.9  277.97  4402.5  270.91  4473.2  266.29  4565.1   265.8
  4628.9  265.66  4734.9   264.8  4805.6  265.78  4840.9  265.15  4862.2  266.56
  4876.4  265.74  4883.3   263.8  4911.6  263.68  4918.8  265.38  4947.1  266.56
  4982.4  266.63  4989.6  263.83  4991.2  261.64  4997.8  262.18  5010.8  266.92
  5060.9  266.34  5082.6  267.21  5271.7  273.03  5298.8  275.82  5429.8  281.29
#Mann= 9 ,-1 , 0
  4155.3     .11       0  4565.1     .11       0  4628.9     .11       0
  4805.6     .11       0  4947.1     .11       0  4982.4     .06       0
  5010.8     .11       0  5060.9     .11       0  5082.6     .11       0
#XS Ineff= 1 ,-1
    4400  4968.2  267.17
Permanent Ineff=
       T
Bank Sta=4982.4,5010.8
XS Rating Curve= 0 ,0
Exp/Cntr=0.3,0.1

Type RM Length L Ch R = 1 ,6138    ,320,320,320
BEGIN DESCRIPTION:
WFSJR 030 11.0
END DESCRIPTION:
XS GIS Cut Line= 3
      3754947.53     10225341.09       3755176.7     10225073.72
       3755735.7     10224351.53
#Sta/Elev= 30
  4549.2  280.35  4563.2  279.28  4591.7  274.03  4620.3  271.14  4663.1  268.45
  4868.3   262.5  4906.2   261.4  4946.5  263.93  4975.5  264.04    4990  260.95
  4994.6  259.17  4998.1  259.17  5010.8  264.78  5018.5  263.89  5039.8  264.72
  5060.6  264.01  5224.5  265.44  5259.8  265.77  5288.8  263.46  5303.3  264.57
  5309.6  263.45  5324.1  262.96  5467.1  264.39  5552.2  267.28  5610.2  270.86
    5631  271.12  5645.5   272.9  5688.7  274.41  5709.8  276.63  5814.6  280.85
#Mann= 5 ,-1 , 0
  4549.2     .11       0  4868.3     .11       0  4975.5     .06       0
  5010.8     .11       0  5224.5     .11       0
#XS Ineff= 2 ,-1
  5010.8    5145  264.78  5259.8    5515  265.77
Permanent Ineff=
       F       F
Bank Sta=4975.5,5010.8
XS Rating Curve= 0 ,0
Exp/Cntr=0.3,0.1

Type RM Length L Ch R = 1 ,5818    ,493,493,493
BEGIN DESCRIPTION:
WFSJR 030 10.0
END DESCRIPTION:
XS GIS Cut Line= 3
      3755267.84     10225461.08      3755458.23     10225156.84
      3755893.28      10224468.5
#Sta/Elev= 30
  4641.1  276.33  4700.1  273.25  4706.5  272.29  4743.1   270.1  4888.8  264.09
  4901.1     263  4910.5  261.11  4924.2  260.09    4947  262.62  4983.2  263.37
  4989.5  261.07  4993.1  258.77    5000  259.27  5004.8  262.06  5018.7  263.37
  5054.1  262.05  5120.1  261.39    5126   262.2  5171.8  260.03  5214.2  261.42
  5243.4  260.65  5271.8  261.49  5373.6   261.4  5460.1  262.26    5533   264.6
  5648.3  271.98  5721.2  275.52  5736.5  275.58  5763.9  278.14  5814.3  280.53
#Mann= 3 , 0 , 0
  4641.1     .11       0  4983.2     .06       0  5018.7     .11       0
Bank Sta=4983.2,5018.7
XS Rating Curve= 0 ,0
Exp/Cntr=0.3,0.1

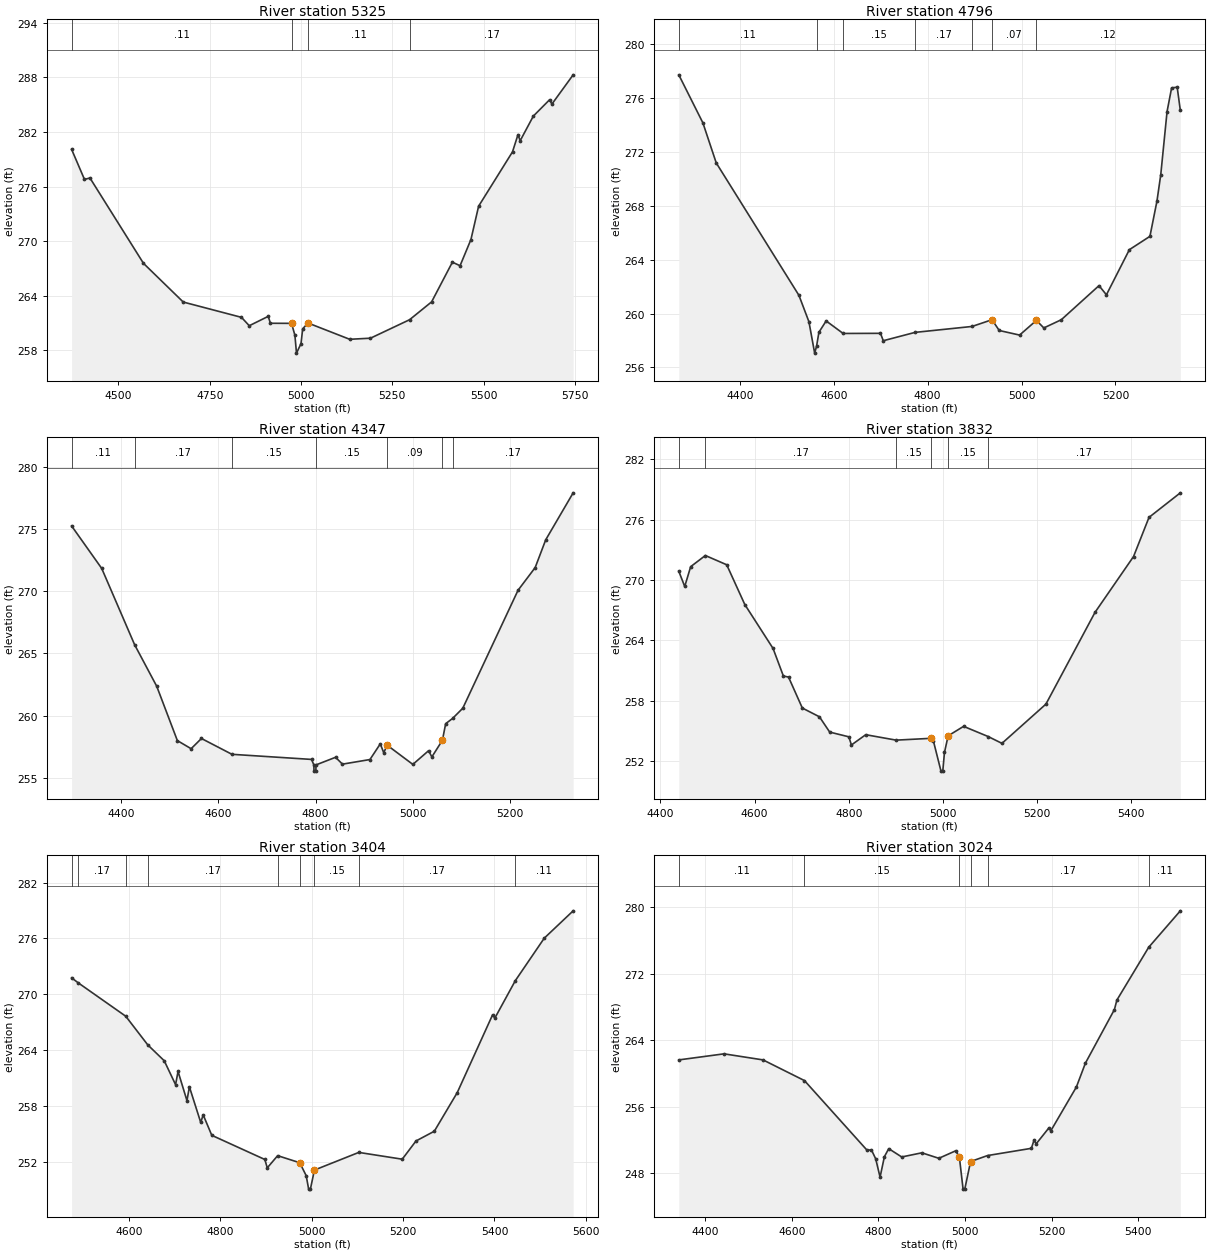
Type RM Length L Ch R = 1 ,5325    ,529,529,529
BEGIN DESCRIPTION:
WFSJR 030 9.0
END DESCRIPTION:
XS GIS Cut Line= 3
      3755417.87     10225611.05      3755748.23     10225076.84
      3756167.88     10224461.04
#Sta/Elev= 30
  4371.9  280.09  4407.1  276.79  4422.1  276.95  4568.7  267.57  4677.6  263.32
    4837  261.64  4858.3  260.72  4910.3  261.75  4916.2  260.99  4974.1  260.98
  4983.3  259.67  4987.6  257.71    5000  258.75  5004.6  260.38  5019.1  261.02
  5133.3  259.23  5190.2  259.35  5297.3  261.38  5357.6  263.34  5414.5   267.7
  5435.5  267.31  5465.3  270.19  5486.3  273.85  5579.1  279.82  5594.1  281.71
  5600.1  281.04  5636.2  283.75  5680.8  285.55  5686.9  285.06  5745.2  288.28
#Mann= 4 ,-1 , 0
  4371.9     .11       0  4974.1     .06       0  5019.1     .11       0
  5297.3     .17       0
Bank Sta=4974.1,5019.1
XS Rating Curve= 0 ,0
Exp/Cntr=0.3,0.1

Type RM Length L Ch R = 1 ,4796    ,449,449,449
BEGIN DESCRIPTION:
WFSJR 030 8.0
END DESCRIPTION:
XS GIS Cut Line= 3
      3755775.28     10225678.97      3756170.04     10225039.62
      3756328.99       10224765.
#Sta/Elev= 30
  4269.7  277.72  4321.1  274.15  4349.5  271.18  4525.7  261.35    4547  259.39
  4559.2  257.06  4563.2  257.56  4568.3  258.61  4583.7  259.45  4619.9  258.52
  4699.5  258.53  4705.4  257.98  4773.1   258.6  4894.6  259.04  4937.1  259.54
  4952.5  258.74  4995.9   258.4  5031.7  259.49  5047.5  258.93  5084.8  259.54
  5165.1  262.07  5180.9  261.39  5229.8  264.74  5273.6  265.73  5288.6  268.35
  5296.7  270.31  5310.1  274.99  5319.8  276.75  5331.7   276.8  5338.4  275.08
#Mann= 7 ,-1 , 0
  4269.7     .11       0  4563.2     .11       0  4619.9     .15       0
  4773.1     .17       0  4894.6     .12       0  4937.1     .07       0
  5031.7     .12       0
Bank Sta=4937.1,5031.7
XS Rating Curve= 0 ,0
Exp/Cntr=0.3,0.1

Type RM Length L Ch R = 1 ,4347    ,515,515,515
BEGIN DESCRIPTION:
WFSJR 030 7.0
END DESCRIPTION:
XS GIS Cut Line= 3
      3755956.22     10225756.87      3756448.23     10225256.84
      3756667.85     10225011.07
#Sta/Elev= 30
  4298.5  275.23  4360.4  271.82  4428.1  265.69  4473.5  262.36  4515.9     258
  4544.2  257.35  4565.4  258.17  4628.1   256.9  4791.7  256.49  4796.5  256.05
  4796.8  255.55  4800.6  255.55  4800.9  256.05  4841.1  256.66  4855.3  256.11
  4911.8  256.48  4933.1  257.74  4940.1  257.03  4947.3  257.63    5000  256.09
  5032.4  257.19  5039.1  256.69  5060.8  258.03  5067.5  259.36  5081.7  259.78
  5102.7   260.6  5216.3  270.07  5251.5  271.89  5273.2  274.12  5329.6  277.89
#Mann= 7 ,-1 , 0
  4298.5     .11       0  4428.1     .17       0  4628.1     .15       0
  4800.9     .15       0  4947.3     .09       0  5060.8     .15       0
  5081.7     .17       0
Bank Sta=4947.3,5060.8
XS Rating Curve= 0 ,0
Exp/Cntr=0.3,0.1

Type RM Length L Ch R = 1 ,3832    ,428,428,428
BEGIN DESCRIPTION:
WFSJR 030 6.0
END DESCRIPTION:
XS GIS Cut Line= 2
      3756456.22     10226064.15       3756885.9     10225090.22
#Sta/Elev= 30
  4439.3  270.88  4451.9  269.36  4464.5  271.33  4495.7  272.44    4541  271.52
  4579.4  267.57  4639.4   263.2  4661.3  260.46  4672.2  260.36  4701.5  257.28
  4737.8  256.41  4759.6  254.89  4800.2  254.42  4805.7  253.61  4836.1  254.63
  4900.6  254.09  4974.4  254.27  4979.8  253.99  4995.8  251.01  4999.6  251.01
  5003.2  252.87    5011  254.52  5043.8  255.46  5095.8  254.45  5125.2  253.77
  5218.5  257.67  5322.7  266.79  5404.5  272.34  5437.3  276.23  5503.8  278.67
#Mann= 6 ,-1 , 0
  4439.3     .11       0  4495.7     .17       0  4900.6     .15       0
  4974.4     .09       0    5011     .15       0  5095.8     .17       0
Bank Sta=4974.4,5011
XS Rating Curve= 0 ,0
Exp/Cntr=0.3,0.1

Type RM Length L Ch R = 1 ,3404    ,380,380,380
BEGIN DESCRIPTION:
WFSJR 030 5.0
END DESCRIPTION:
XS GIS Cut Line= 3
      3756852.04     10226217.82      3757049.96     10225694.38
      3757083.81     10225157.95
#Sta/Elev= 30
  4475.1  271.76  4489.9  271.21  4593.5  267.63  4641.8  264.54  4677.7  262.84
  4702.5  260.27  4707.9  261.69  4727.4  258.55  4732.7  260.04  4757.5  256.21
  4762.9  257.02  4781.7  254.82  4897.7  252.22  4903.1  251.32  4925.8  252.63
  4974.1  251.87  4988.2  250.48  4993.6  249.03  4997.4  249.03  5006.2  251.08
  5103.3  252.98  5198.3  252.25  5228.4  254.21  5268.5  255.26  5318.6  259.41
    5396  267.79    5401  267.44  5445.7  271.46    5509  276.03  5572.2  278.97
#Mann= 9 ,-1 , 0
  4475.1     .11       0  4489.9     .17       0  4593.5     .11       0
  4641.8     .17       0  4925.8     .15       0  4974.1     .09       0
  5006.2     .15       0  5103.3     .17       0  5445.7     .11       0
Bank Sta=4974.1,5006.2
XS Rating Curve= 0 ,0
Exp/Cntr=0.3,0.1

Type RM Length L Ch R = 1 ,3024    ,641,641,641
BEGIN DESCRIPTION:
WFSJR 030 4.0
END DESCRIPTION:
XS GIS Cut Line= 3
       3757391.1      10226285.5      3757372.88     10225723.03
      3757211.42     10225150.11
#Sta/Elev= 30
  4339.3  261.62  4443.8  262.35  4533.8  261.62  4629.5  259.13    4774  250.75
    4784   250.8    4794  249.71    4804  247.51    4814  249.97    4824  250.94
    4854  249.94  4900.5  250.44  4939.7  249.78    4979  250.69  4987.2  249.88
  4995.7  246.07  4999.6  246.07    5013  249.39  5052.2  250.11  5153.4  250.98
  5159.4  251.95  5164.6  251.53  5193.4  253.41  5198.6  253.12  5257.3  258.36
  5278.1  261.23  5345.1  267.68  5350.8  268.82  5424.2  275.17  5497.3  279.56
#Mann= 6 ,-1 , 0
  4339.3     .11       0  4629.5     .15       0  4987.2     .09       0
    5013     .15       0  5052.2     .17       0  5424.2     .11       0
Bank Sta=4987.2,5013
XS Rating Curve= 0 ,0
Exp/Cntr=0.3,0.1

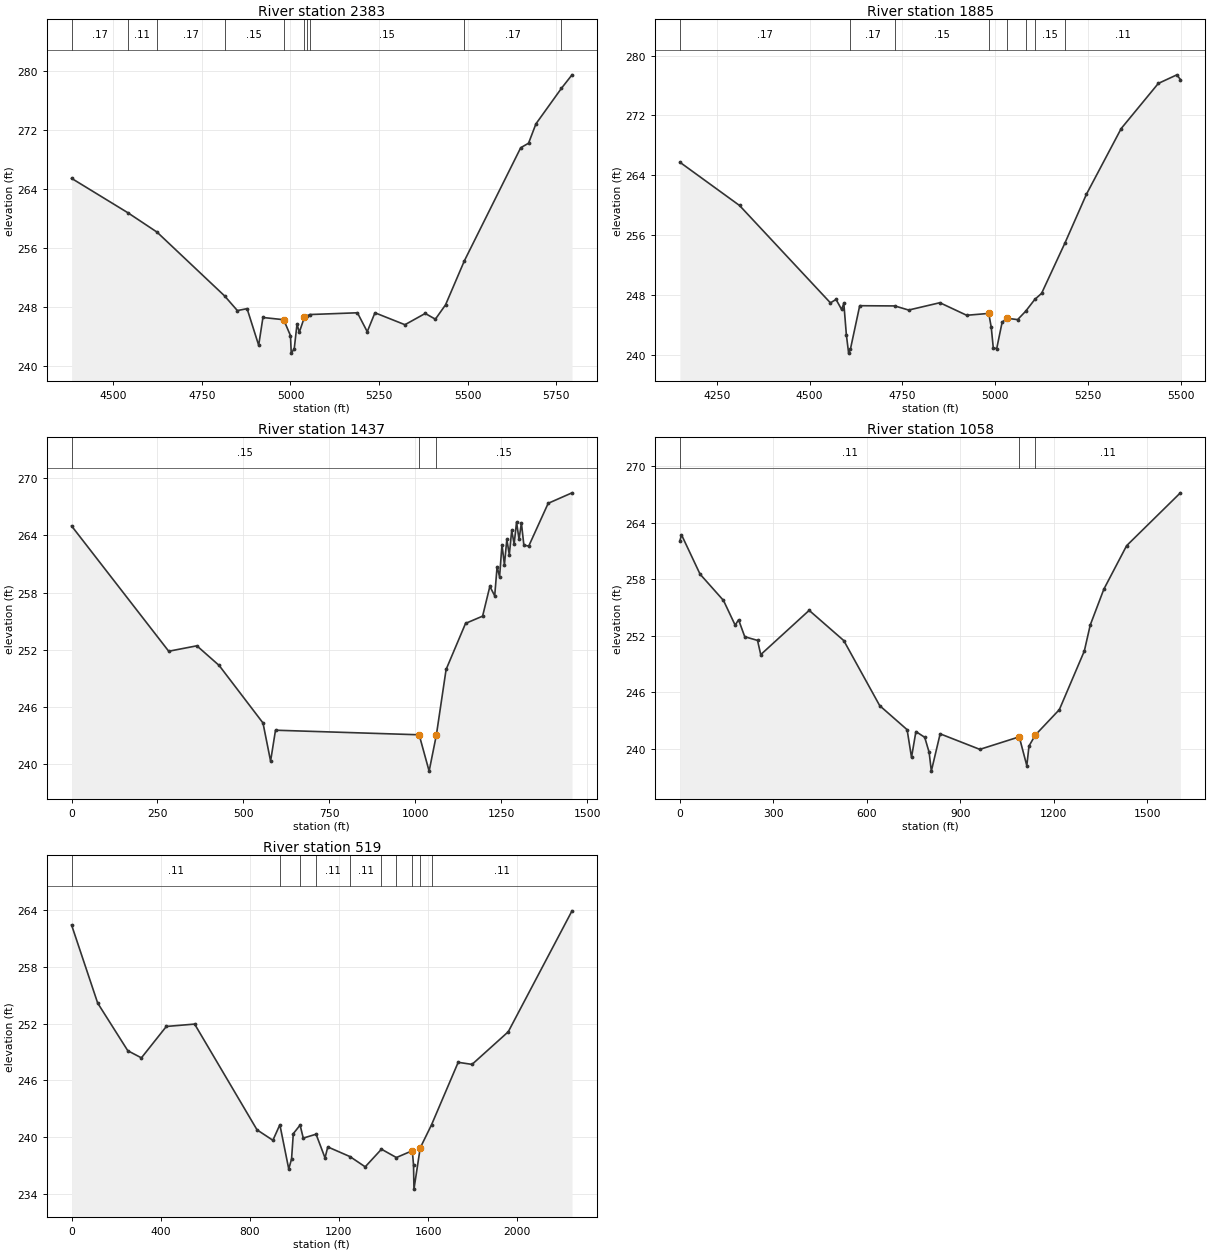
Type RM Length L Ch R = 1 ,2383    ,498,498,498
BEGIN DESCRIPTION:
WFSJR 030 3.0
END DESCRIPTION:
XS GIS Cut Line= 3
       3757706.2      10226316.8      3757888.23     10225726.84
      3758398.91     10225118.87
#Sta/Elev= 30
  4382.6  265.47  4541.3   260.8  4623.5  258.17    4814  249.51  4850.2  247.51
  4877.6  247.77  4910.3   242.8  4922.3  246.57  4980.8  246.27    5000   244.1
  5002.1  241.73  5010.6  242.32  5018.4  245.67  5024.9  244.57  5039.2  246.59
  5046.9  246.75  5054.1  246.97  5188.8  247.21  5216.5  244.64  5238.2  247.21
  5322.8  245.59    5380  247.12  5408.6  246.34  5437.3  248.29  5490.4  254.27
  5649.3  269.63  5671.4  270.24  5692.2  272.87  5764.3  277.71    5794  279.53
#Mann= 10 ,-1 , 0
  4382.6     .17       0  4541.3     .11       0  4623.5     .17       0
    4814     .15       0  4980.8     .09       0  5039.2     .15       0
  5046.9     .17       0  5054.1     .15       0  5490.4     .17       0
  5764.3     .11       0
Bank Sta=4980.8,5039.2
XS Rating Curve= 0 ,0
Exp/Cntr=0.3,0.1

Type RM Length L Ch R = 1 ,1885    ,448,448,448
BEGIN DESCRIPTION:
WFSJR 030 2.0
END DESCRIPTION:
XS GIS Cut Line= 3
      3757789.55       10226335.      3758258.23     10225626.84
      3758557.77      10225227.5
#Sta/Elev= 30
  4150.8  265.73  4311.4  259.95  4556.3  246.93  4571.4  247.39  4586.4  246.05
  4592.4  246.86  4599.2  242.68  4605.3  240.21    4610  240.71  4635.2  246.55
  4729.7  246.52    4767  245.97  4851.2  246.95  4923.4  245.27  4982.9  245.52
  4989.6  243.66  4995.1   240.9  5004.3  240.82  5018.9  244.34  5032.2  244.87
  5060.6  244.69  5082.1   245.8  5106.9  247.39  5125.2   248.2  5188.3  254.95
    5246  261.45  5339.7  270.24  5439.7  276.27  5489.7  277.42  5499.2  276.79
#Mann= 8 ,-1 , 0
  4150.8     .17       0    4610     .17       0  4729.7     .15       0
  4982.9     .09       0  5032.2     .17       0  5082.1     .17       0
  5106.9     .15       0  5188.3     .11       0
Bank Sta=4982.9,5032.2
XS Rating Curve= 0 ,0
Exp/Cntr=0.3,0.1

Type RM Length L Ch R = 1 ,1437    ,379,379,379
XS GIS Cut Line= 4
      3757867.85     10226361.07      3758203.61     10226217.82
      3758628.23     10225706.84      3758935.38     10225407.93
#Sta/Elev= 30
       0  264.99   282.7  251.85   364.6  252.42   429.4  250.36     557  244.33
   579.1  240.33   593.4  243.57  1011.4  243.09  1040.4  239.28  1061.5  243.07
  1089.8  249.94  1146.4  254.77    1196  255.53  1217.1  258.65  1231.2  257.66
  1238.2  260.72  1245.4  259.65  1252.4  263.02  1259.5  260.92  1266.5  263.58
  1273.7  261.97  1280.7  264.51  1287.8  263.11  1294.8  265.39    1302  263.58
  1308.9   265.3  1316.1  262.97  1330.3  262.88  1386.8  267.36  1456.2  268.46
#Mann= 3 , 0 , 0
       0     .15       0  1011.4     .09       0  1061.5     .15       0
Bank Sta=1011.4,1061.5
XS Rating Curve= 0 ,0
Exp/Cntr=0.3,0.1

Type RM Length L Ch R = 1 ,1058    ,539,539,539
XS GIS Cut Line= 4
      3757914.95     10226396.49      3758550.36     10226253.26
      3758818.59     10225990.24      3758985.26     10225435.55
#Sta/Elev= 30
       0  262.07       5  262.71    64.5  258.53   139.8  255.73   177.2  253.11
   188.2  253.68     208  251.88     249  251.49   259.3  249.98   414.7  254.68
   525.8  251.47   641.1  244.56     729  242.01   743.1  239.07   757.2  241.81
   785.5   241.2   799.7   239.6   806.7  237.61     835  241.57   962.3  239.92
  1088.8  241.25  1113.1  238.19  1120.1  240.28  1140.9  241.46  1217.5  244.14
  1297.6  250.36  1316.6  253.12  1360.3  256.93  1433.4  261.55  1605.9  267.16
#Mann= 3 , 0 , 0
       0     .11       0  1088.8     .06       0  1140.9     .11       0
Bank Sta=1088.8,1140.9
XS Rating Curve= 0 ,0
Exp/Cntr=0.3,0.1

Type RM Length L Ch R = 1 ,519     ,0,0,0
XS GIS Cut Line= 4
      3757909.74     10226438.16      3759183.18     10226198.57
      3759394.11     10225865.24      3759279.53     10225320.97
#Sta/Elev= 30
       0  262.39   117.3  254.15   252.5  249.13   313.5  248.38   425.4  251.69
   552.4  251.94   832.5  240.79   903.7  239.69     935  241.33   974.9  236.66
   987.5  237.72   995.3  240.39  1025.8  241.29    1040  239.92  1097.5  240.33
  1137.7  237.83    1150  238.99  1249.7  237.97  1318.1  236.89    1391  238.75
    1458  237.87  1529.5  238.59    1535 237.066  1536.9  234.54    1565  238.89
  1615.7  241.32  1735.4  247.91  1797.6  247.69  1960.2  251.13  2246.4  263.88
#Mann= 10 ,-1 , 0
       0     .11       0     935     .11       0  1025.8     .11       0
  1097.5     .11       0  1249.7     .11       0    1391     .11       0
    1458     .11       0  1529.5     .06       0    1565     .11       0
  1615.7     .11       0
Bank Sta=1529.5,1565
XS Rating Curve= 0 ,0
Exp/Cntr=0.3,0.1

Chan Stop Cuts=-1
Use User Specified Reach Order=0
Composite Channel Slope=5