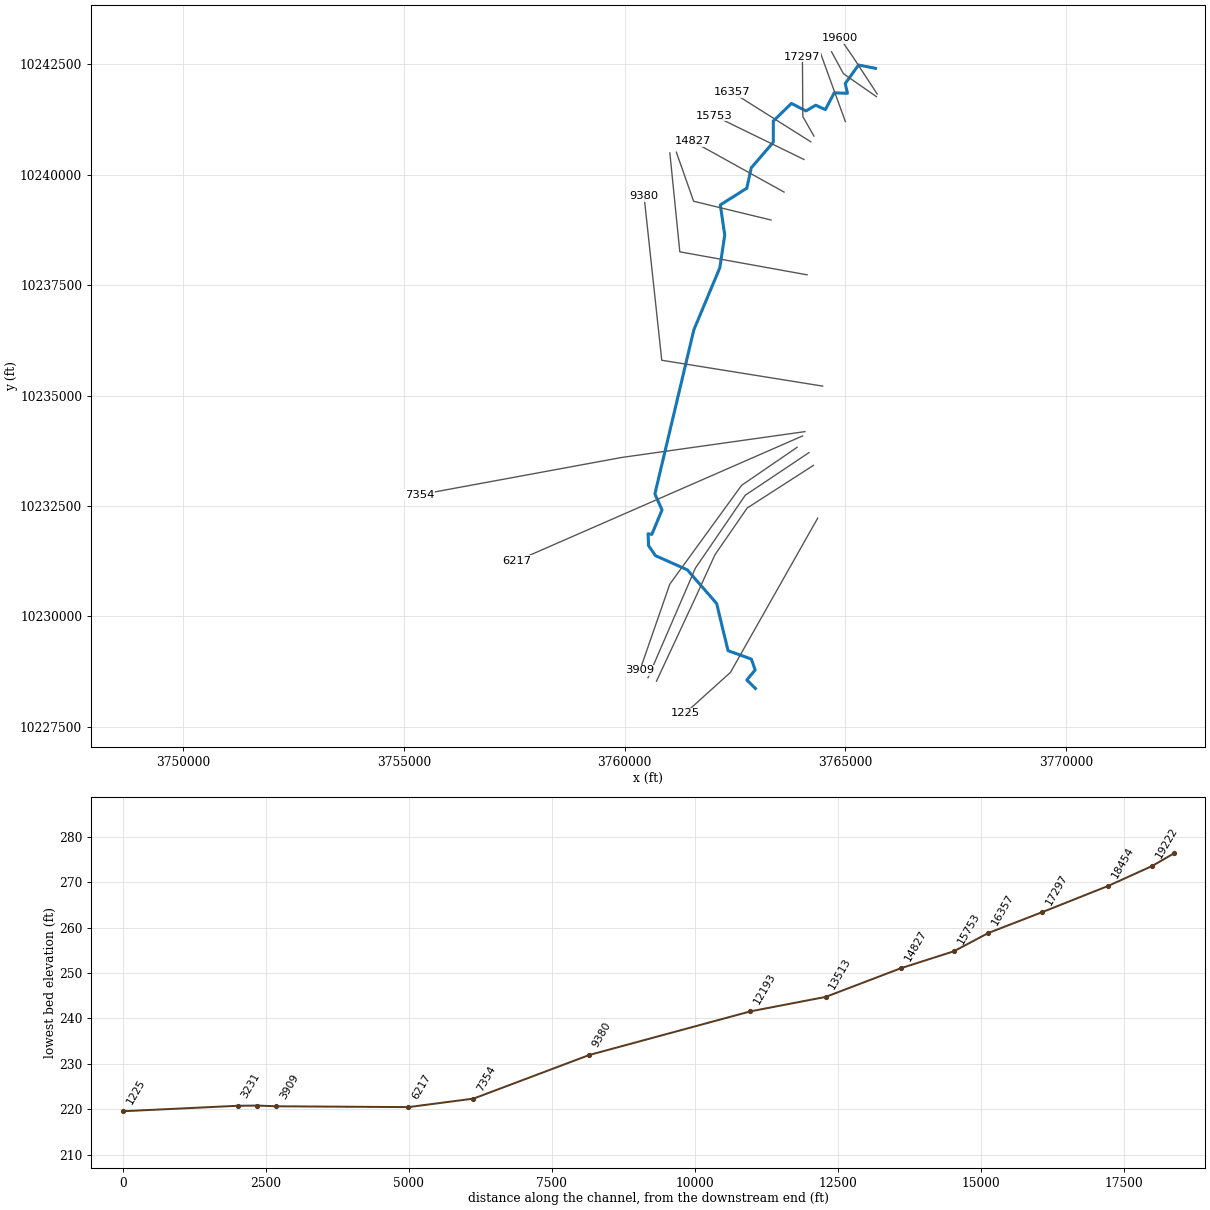
--- WFSJR 033.prj (project) ---

Proj Title=WFSJR 033 Base Level Engineering
Current Plan=p01
Default Exp/Contr=0.3,0.1
English Units
Geom File=g01
Flow File=f01
Plan File=p01
Y Axis Title=Elevation
X Axis Title(PF)=Main Channel Distance
X Axis Title(XS)=Station
BEGIN DESCRIPTION:
WFSJR 033
END DESCRIPTION:
DSS Export Rating Curves= 0
DSS Export Rating Curve Sorted= 0
DSS Export Volume Flow Curves= 0
DXF OffsetX= 0
DXF OffsetY= 0
DXF ScaleX= 1
DXF ScaleY= 10

--- WFSJR 033.p01 (plan) ---

Plan Title=Multiple Run
Program Version=4.10
Short Identifier=Multiple
Geom File=g01
Flow File=f01
Subcritical Flow
K Sum by GR= 0
Std Step Tol= 0.01
Critical Tol= 0.01
Num of Std Step Trials= 20
Max Error Tol= 0.3
Flow Tol Ratio= 0.001
Split Flow NTrial= 30
Split Flow Tol= 0.02
Split Flow Ratio= 0.02
Log Output Level= 0
Friction Slope Method= 1
Unsteady Friction Slope Method= 2
Unsteady Bridges Friction Slope Method= 1
Parabolic Critical Depth
Global Vel Dist= 1 , 1 , 1
Global Log Level= 0
CheckData=True
Encroach Param=-1 ,0,0, 0
BEGIN DESCRIPTION:
Multiple Run
END DESCRIPTION:
Computation Interval=1HOUR
Output Interval=1HOUR
Run HTab= 0
Run UNet= 0
Run PostProcess= 0
Run WQNet= 0
UNET Theta= 1
UNET Theta Warmup= 1
UNET ZTol= 0.02
UNET ZSATol= 0.05
UNET MxIter= 20
UNET MaxInSteps= 0
UNET DtIC= 0
UNET DtMin= 0
UNET MaxCRTS= 20
UNET WFStab= 2
UNET SFStab= 1
UNET WFX= 1
UNET SFX= 1
UNET DSS MLevel= 4
UNET DZMax Abort= 100
UNET Convert EG Bridges= 0
UNET Use Existing IB Tables=-1
UNET Froude Reduction=False
UNET Froude Limit= 1
UNET Froude Power= 10
UNET Time Slicing=0,0, 5
UNET Junction Losses=0
Instantaneous Interval=1HOUR
Write IC File= 0
Write IC File at Sim End=0
Echo Input=False
Echo Parameters=False
Echo Output=False
Write Detailed= 0
WQ AD Non Conservative
WQ ULTIMATE=-1
WQ Max Comp Step=1HOUR
WQ Output Interval=15MIN
WQ Output Selected Increments= 0
WQ Output face flow=0
WQ Output face velocity=0
WQ Output face area=0
WQ Output face dispersion=0
WQ Output cell volume=0
WQ Output cell surface area=0
WQ Output cell continuity=0
WQ Output cumulative cell continuity=0
WQ Output face conc=0
WQ Output face dconc_dx=0
WQ Output face courant=0
WQ Output face peclet=0
WQ Output face adv mass=0
WQ Output face disp mass=0
WQ Output cell mass=0
WQ Output cell source sink temp=0
WQ Output cell source sink nsm=0
WQ Output MaxMinRange=-1
WQ Daily Max Min Mean=-1
WQ Daily Range=0
WQ Daily Time=0
WQ Create Restart=0
WQ Fixed Restart=0
WQ System Summary=0
WQ Use Fixed Temperature=0
Sorting and Armoring Iterations= 10
XS Update Threshold= 0.02
Hydraulics Update Threshold= 0.02
Energy Slope Method= 1
Volume Change Method= 0
XS Weighting Method= 0
Number of US Weighted Cross Sections= 1
Number of DS Weighted Cross Sections= 1
Upstream XS Weight=0.25
Main XS Weight=0.5
Downstream XS Weight=0.25
Number of DS XS's Weighted with US Boundary= 1
Upstream Boundary Weight= 1
Weight of XSs Associated with US Boundary= 0
Number of US XS's Weighted with DS Boundary= 1
Downstream Boundary Weight= 0.5
Weight of XSs Associated with DS Boundary= 0.5
Sediment Output Level= 4
Mass or Volume Output= 0
Output Increment Type= 1
Profile and TS Output Increment= 10
XS Output Flag= 0
XS Output Increment= 10
Disregard all LS=0
Disregard all Conn=0
Disregard all Breaches=0
Disregard all Pumps=0

--- WFSJR 033.f01 (steady flow) ---

Flow Title=Multiple
Program Version=4.10
Number of Profiles= 7
Profile Names=10-year,25-year,50-year,1pct_min,100-year,1pct_plu,500-year
River Rch & RM=WFSJR 033,Reach-1         ,19600
    1122    1570    2170     985    2974    8981    5783
River Rch & RM=WFSJR 033,Reach-1         ,9380
    1617    2303    3219    1476    4458   13463    8848
River Rch & RM=WFSJR 033,Reach-1         ,6217
    2035    2926    4117    1898    5733   17313   11507
River Rch & RM=WFSJR 033,Reach-1         ,1225
    2142    3070    4309    1981    5983   18068   11940
Boundary for River Rch & Prof#=WFSJR 033,Reach-1         , 1
Up Type= 0
Dn Type= 3
Dn Slope=0.005
Boundary for River Rch & Prof#=WFSJR 033,Reach-1         , 2
Up Type= 0
Dn Type= 3
Dn Slope=0.005
Boundary for River Rch & Prof#=WFSJR 033,Reach-1         , 3
Up Type= 0
Dn Type= 3
Dn Slope=0.005
Boundary for River Rch & Prof#=WFSJR 033,Reach-1         , 4
Up Type= 0
Dn Type= 3
Dn Slope=0.005
Boundary for River Rch & Prof#=WFSJR 033,Reach-1         , 5
Up Type= 0
Dn Type= 3
Dn Slope=0.005
Boundary for River Rch & Prof#=WFSJR 033,Reach-1         , 6
Up Type= 0
Dn Type= 3
Dn Slope=0.005
Boundary for River Rch & Prof#=WFSJR 033,Reach-1         , 7
Up Type= 0
Dn Type= 3
Dn Slope=0.005
DSS Import GetInterval= 0
DSS Import GetPeak= 0
DSS Import FillOption= 0

--- WFSJR 033.g01 (geometry) ---

Geom Title=Existing Conditions
Program Version=4.10

River Reach=WFSJR 033       ,Reach-1
Reach XY= 30
      3765683.23     10242411.84      3765298.23     10242486.84
      3764998.23     10242066.84      3765048.23     10241846.84
      3764748.23     10241856.84      3764548.23     10241476.84
      3764328.23     10241576.84      3764108.23     10241446.84
      3763778.23     10241616.84      3763368.23     10241216.84
      3763368.23     10240736.84      3762868.23     10240156.84
      3762768.23     10239696.84      3762168.23     10239316.84
      3762268.23     10238636.84      3762158.23     10237896.84
      3761568.23     10236486.84      3760686.27      10232771.8
       3760847.5     10232408.01      3760617.47     10231855.06
      3760531.53     10231866.35      3760543.68     10231598.12
       3760698.2     10231372.42      3761421.29     10231050.37
      3762084.48     10230288.22      3762343.16     10229219.65
      3762871.81     10229028.67      3762957.68     10228781.86
       3762768.3     10228555.02      3762964.13     10228362.92

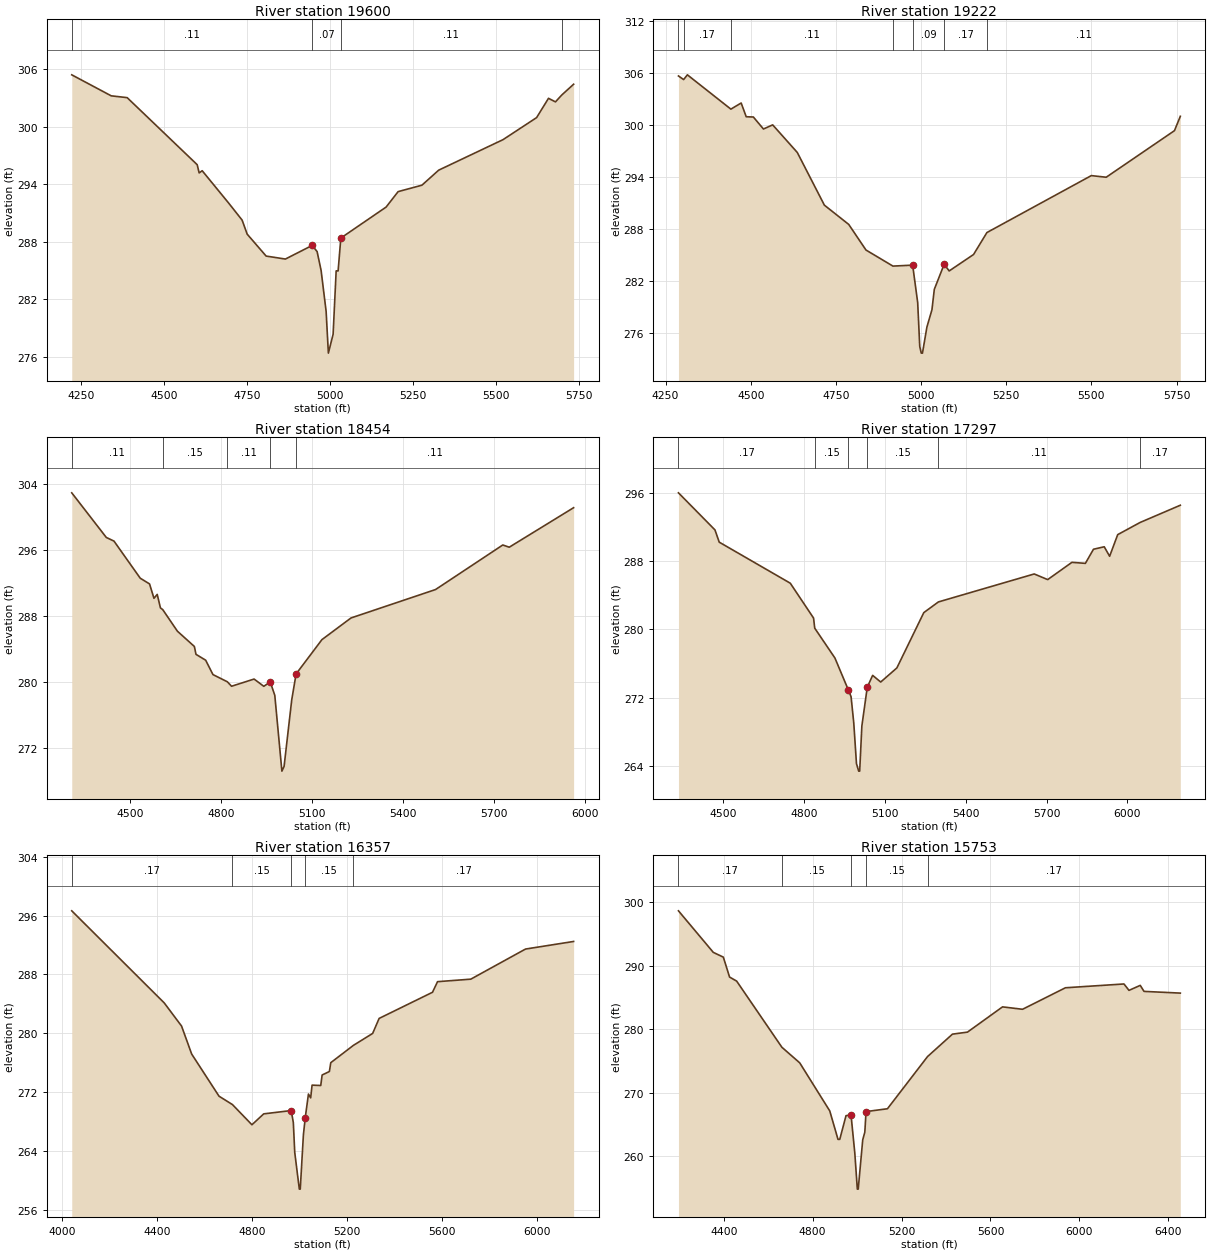
Type RM Length L Ch R = 1 ,19600   ,378,378,378
BEGIN DESCRIPTION:
WFSJR 033 3.0
END DESCRIPTION:
XS GIS Cut Line= 3
      3765721.25     10241831.48      3765179.44      10242660.6
      3764881.96     10243091.54
#Sta/Elev= 30
  4220.9   305.4  4339.9  303.21  4388.1  303.02  4599.3  296.03  4605.3  295.17
  4614.4   295.4  4692.8  292.09  4734.9  290.25  4750.1  288.79  4807.3   286.5
  4865.5  286.19  4946.2  287.61  4961.1  286.97  4973.2     285  4988.3  280.74
  4995.1  276.38  5009.4  278.35  5018.6  284.96  5024.5  284.95  5032.7  288.38
  5169.3  291.61  5205.5  293.22  5277.3  293.89    5328  295.46    5522  298.64
  5623.4  300.94  5659.2  302.95  5680.2  302.58  5699.4   303.3    5735  304.42
#Mann= 4 ,-1 , 0
  4220.9     .11       0  4946.2     .07       0  5032.7     .11       0
  5699.4     .17       0
#XS Ineff= 1 ,-1
    4770  4946.2  287.61
Permanent Ineff=
       F
Bank Sta=4946.2,5032.7
XS Rating Curve= 0 ,0
Exp/Cntr=0.3,0.1

Type RM Length L Ch R = 1 ,19222   ,768,768,768
BEGIN DESCRIPTION:
Mapping XS 7d5b0650
END DESCRIPTION:
XS GIS Cut Line= 3
      3765703.87     10241770.75      3764957.35     10242291.58
      3764688.34      10242786.2
#Sta/Elev= 30
  4287.7  305.69  4302.9  305.27  4313.9  305.82  4441.6  301.85  4471.8  302.56
  4486.6  300.97  4507.6  300.94  4537.2  299.55  4564.3  300.03  4636.5  296.84
  4716.1  290.74  4787.6  288.51  4838.2  285.55  4917.3  283.69  4975.2   283.8
    4990  279.47  4996.1  274.37  5000.5  273.62    5004  273.62  5017.1  276.64
  5031.9  278.65  5038.8     281  5067.7   283.9  5082.5  283.13    5154  285.03
  5193.2  287.57  5499.7  294.16  5543.4  293.97  5743.8  299.36    5761  301.02
#Mann= 7 ,-1 , 0
  4287.7     .11       0  4302.9     .17       0  4441.6     .11       0
  4917.3     .17       0  4975.2     .09       0  5067.7     .17       0
  5193.2     .11       0
Bank Sta=4975.2,5067.7
XS Rating Curve= 0 ,0
Exp/Cntr=0.3,0.1

Type RM Length L Ch R = 1 ,18454   ,1157,1157,1157
BEGIN DESCRIPTION:
Mapping XS 2f060953
END DESCRIPTION:
XS GIS Cut Line= 2
      3765000.75      10241206.5      3764436.52     10242760.32
#Sta/Elev= 30
  4308.1   302.9  4421.9   297.5  4447.2  297.06  4533.7  292.57  4564.3  291.88
  4578.9  290.14  4589.6  290.61  4600.2  288.98  4607.8  288.77  4656.1  286.16
    4712  284.31  4717.3  283.36  4749.2  282.65  4773.2  280.91  4820.6  280.04
  4834.5   279.5  4908.7  280.37  4940.7  279.49  4961.9  280.02  4976.9   278.4
  5000.3  269.23  5007.5   269.8  5032.7  277.86  5047.1  280.99  5132.2  285.14
  5227.9  287.76  5506.5   291.2  5727.9  296.59  5749.2  296.32  5961.2   301.1
#Mann= 5 ,-1 , 0
  4308.1     .11       0  4607.8     .15       0  4820.6     .11       0
  4961.9     .07       0  5047.1     .11       0
Bank Sta=4961.9,5047.1
XS Rating Curve= 0 ,0
Exp/Cntr=0.3,0.1

Type RM Length L Ch R = 1 ,17297   ,940,940,940
BEGIN DESCRIPTION:
Mapping XS 2d75fa46
END DESCRIPTION:
XS GIS Cut Line= 3
      3764288.96     10240876.62      3764037.21     10241319.36
      3764028.53     10242673.52
#Sta/Elev= 30
  4333.2  295.98  4468.8  291.64  4484.6  290.21  4748.4  285.41  4834.9  281.33
  4839.2  280.15  4914.2  276.66  4964.2  272.91  4974.2  272.13  4984.2  269.05
  4994.2   264.3  5002.4  263.43  5006.1  263.43  5014.2   268.7  5034.2  273.23
  5054.2  274.63  5084.2  273.85  5144.2   275.5  5244.2  281.97  5298.5  283.22
  5654.2  286.49  5704.2  285.83  5794.2  287.85  5844.2  287.73  5874.2  289.38
  5914.2  289.67  5934.2  288.56  5964.2  291.09  6047.2  292.51  6196.7  294.53
#Mann= 6 ,-1 , 0
  4333.2     .17       0  4839.2     .15       0  4964.2     .09       0
  5034.2     .15       0  5298.5     .11       0  6047.2     .17       0
Bank Sta=4964.2,5034.2
XS Rating Curve= 0 ,0
Exp/Cntr=0.3,0.1

Type RM Length L Ch R = 1 ,16357   ,604,604,604
BEGIN DESCRIPTION:
Mapping XS 397588ee
END DESCRIPTION:
XS GIS Cut Line= 2
      3764219.52     10240746.43      3762432.09     10241874.42
#Sta/Elev= 30
  4041.8  296.64  4431.4  284.13  4504.3  280.99  4546.7   277.2    4662  271.47
  4718.6  270.33  4800.6  267.59  4850.3  269.07  4966.1  269.52    4975  267.87
  4980.9  263.84  5000.2  258.85  5004.1  258.85  5017.4  266.23  5025.2  268.56
  5038.6  271.76    5048  271.24  5053.9  272.97  5090.4  272.92  5096.3  274.35
  5126.8  274.82  5132.7  276.02  5227.9  278.37    5309  279.99  5336.3  282.03
  5561.1  285.58  5582.3  287.02  5722.3  287.36  5952.9  291.45  6155.4  292.48
#Mann= 5 ,-1 , 0
  4041.8     .17       0  4718.6     .15       0  4966.1     .09       0
  5025.2     .15       0  5227.9     .17       0
Bank Sta=4966.1,5025.2
XS Rating Curve= 0 ,0
Exp/Cntr=0.3,0.1

Type RM Length L Ch R = 1 ,15753   ,926,926,926
BEGIN DESCRIPTION:
Mapping XS 81b520ac
END DESCRIPTION:
XS GIS Cut Line= 2
      3764063.29     10240347.12       3762033.1     10241336.19
#Sta/Elev= 30
  4196.1  298.68  4352.9  292.13    4398  291.38  4426.1  288.24    4458   287.6
  4661.6  277.17  4741.7  274.72  4876.9  267.14  4914.1  262.65    4922  262.66
  4950.1  266.39  4972.6  266.52  4989.6  260.51    5001  254.81    5005  254.81
  5025.3  262.58  5034.7  263.79  5040.2  267.03  5136.5  267.48  5317.1  275.71
    5429  279.24  5496.6  279.56  5654.4  283.54  5744.5  283.16  5937.4  286.55
  6200.9  287.15  6223.4  286.14  6274.1  286.93  6291.1  285.98  6454.4  285.71
#Mann= 5 ,-1 , 0
  4196.1     .17       0  4661.6     .15       0  4972.6     .09       0
  5040.2     .15       0  5317.1     .17       0
Bank Sta=4972.6,5040.2
XS Rating Curve= 0 ,0
Exp/Cntr=0.3,0.1

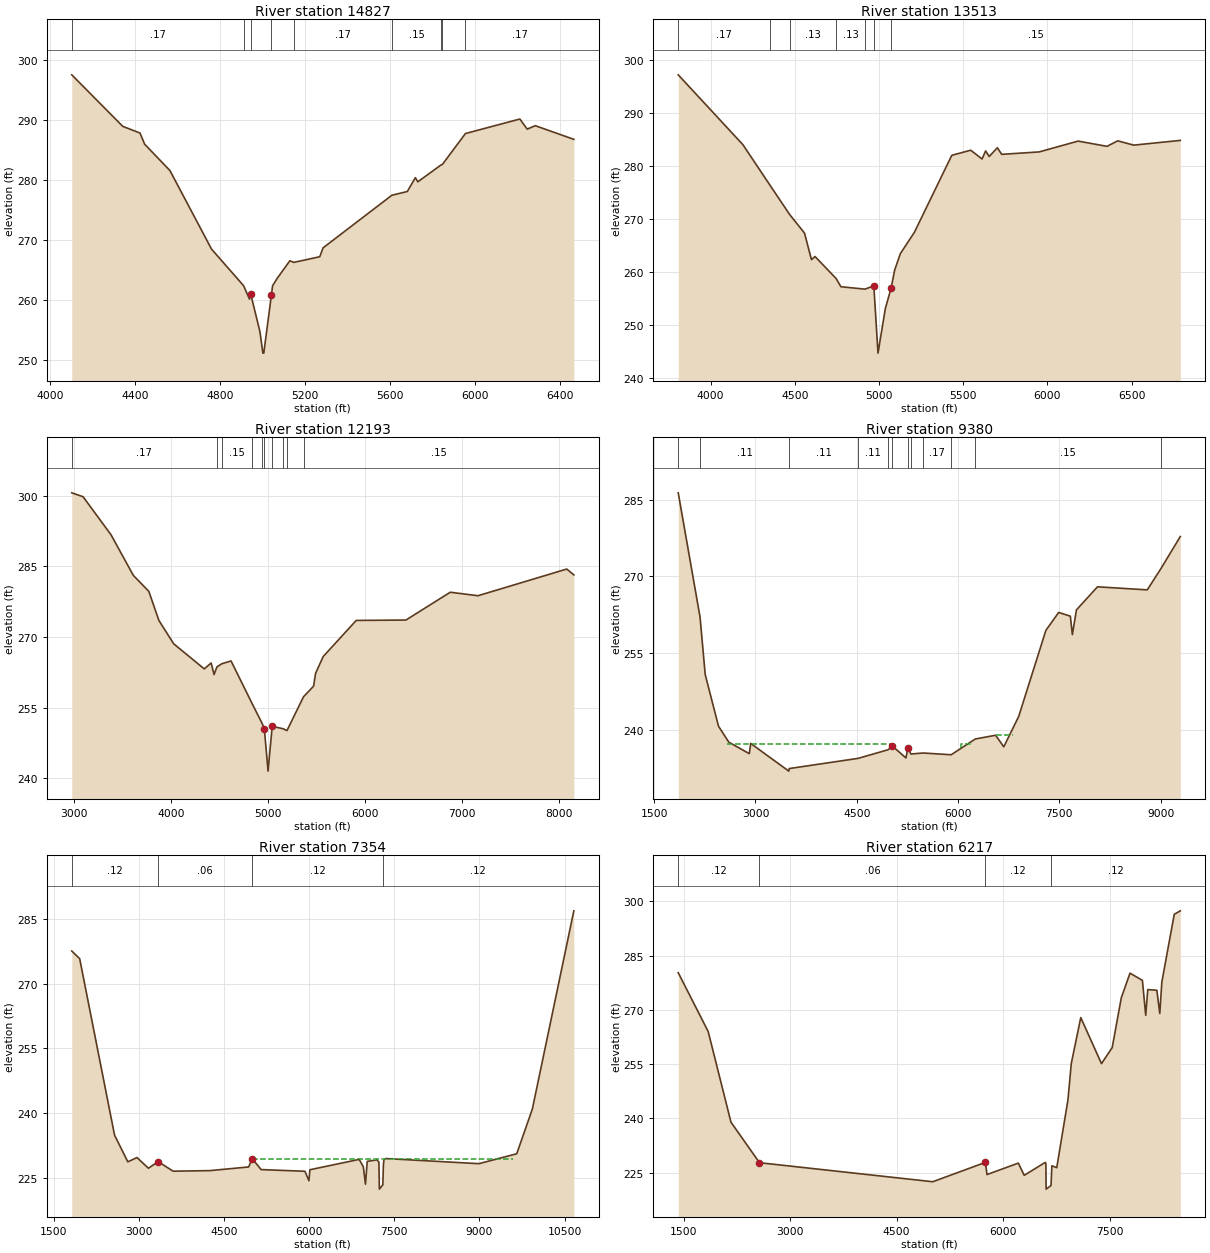
Type RM Length L Ch R = 1 ,14827   ,1314,1314,1314
BEGIN DESCRIPTION:
Mapping XS a6bd86c6
END DESCRIPTION:
XS GIS Cut Line= 2
      3763611.87     10239609.28      3761545.86     10240755.14
#Sta/Elev= 30
  4103.9  297.54  4343.8  288.94  4425.1  287.82  4446.8  285.96  4565.8  281.56
  4761.5  268.45  4912.6  262.33  4940.1   260.1  4945.8  260.96  4989.3  254.67
  5003.2  251.08  5007.4  251.08  5043.1  260.72  5048.8  262.32  5070.5  263.56
  5130.1   266.5  5148.9  266.23  5270.8  267.17  5286.3  268.65  5610.3  277.44
  5682.8  278.06  5720.6  280.37  5732.3  279.68    5841  282.48  5848.3   282.6
  5956.4  287.74  6212.5  290.16    6247  288.47  6284.8  289.05  6466.4  286.77
#Mann= 9 ,-1 , 0
  4103.9     .17       0  4912.6     .15       0  4945.8     .09       0
  5043.1     .15       0  5148.9     .17       0  5610.3     .15       0
    5841     .17       0  5848.3     .11       0  5956.4     .17       0
Bank Sta=4945.8,5043.1
XS Rating Curve= 0 ,0
Exp/Cntr=0.3,0.1

Type RM Length L Ch R = 1 ,13513   ,1320,1320,1320
BEGIN DESCRIPTION:
Mapping XS 7a423c92
END DESCRIPTION:
XS GIS Cut Line= 3
      3763316.73     10238975.61      3761563.25     10239400.96
      3761172.73     10240511.77
#Sta/Elev= 30
  3807.9  297.25  4192.1  284.07  4355.1  276.32  4470.4  270.87  4557.9   267.4
  4599.1  262.39  4620.3  262.98  4745.7  258.83    4774  257.28  4917.6  256.83
  4969.5  257.46  4994.3  244.76  5038.2  253.22  5072.4  257.03    5093  260.39
    5127  263.52  5210.5  267.55  5432.6  282.07  5544.9  283.03  5612.2  281.38
  5633.6  282.89  5654.8  281.85  5703.2   283.5  5728.8  282.25  5951.6  282.71
  6182.9  284.75  6354.4  283.76    6418   284.8    6513  283.99  6789.7  284.88
#Mann= 7 ,-1 , 0
  3807.9     .17       0  4355.1     .11       0  4470.4     .13       0
  4745.7     .13       0  4917.6     .13       0  4969.5     .08       0
  5072.4     .15       0
#XS Ineff= 1 ,-1
    4740  4969.5  257.46
Permanent Ineff=
       F
Bank Sta=4969.5,5072.4
XS Rating Curve= 0 ,0
Exp/Cntr=0.3,0.1

Type RM Length L Ch R = 1 ,12193   ,2813,2813,2813
BEGIN DESCRIPTION:
Mapping XS 768b2702
END DESCRIPTION:
XS GIS Cut Line= 3
      3764132.72     10237734.28      3761250.75     10238255.12
      3761025.05     10240494.72
#Sta/Elev= 30
  2973.2   300.6  3089.9  299.77  3378.2   291.7  3608.2  283.09  3768.1   279.7
  3872.4  273.51  4024.8  268.57  4339.9  263.25    4411   264.5  4440.8  262.05
  4470.8  263.66  4520.7  264.34  4616.6  264.93  4827.6  256.15  4935.9  251.73
  4959.7  250.59  4998.2  241.56    5041  251.07  5152.8  250.55  5193.5  250.17
    5364  257.33  5467.8  259.58  5488.2  262.29  5567.1  265.87  5907.8  273.53
  6420.4  273.61    6878  279.51  7164.2  278.77  8079.4  284.43  8152.8  283.19
#Mann= 10 ,-1 , 0
  2973.2     .17       0  4470.8     .11       0  4520.7     .15       0
  4827.6     .11       0  4935.9     .11       0  4959.7     .06       0
    5041     .11       0  5152.8     .11       0  5193.5     .11       0
    5364     .15       0
Bank Sta=4959.7,5041
XS Rating Curve= 0 ,0
Exp/Cntr=0.3,0.1

Type RM Length L Ch R = 1 ,9380    ,2026,2026,2026
BEGIN DESCRIPTION:
Mapping XS 5f9c01e8
END DESCRIPTION:
XS GIS Cut Line= 3
      3764487.28     10235212.72      3760841.47     10235798.65
      3760439.99     10239520.46
#Sta/Elev= 30
  1855.9  286.33  2179.3  262.03  2255.3  250.83  2452.9  240.72  2604.8  237.62
  2908.7  235.37  2928.9  237.37  3493.9  231.96  3498.8  232.46    4519  234.45
  4962.4  236.13 5029.19236.8363  5228.1  234.54  5258.4  236.54  5301.6   235.3
  5481.2   235.5  5898.4  235.16    6256  238.24  6556.5  238.97  6677.4  236.71
  6898.7  242.65    7301  259.46  7490.4  262.96  7663.1  262.23  7693.3  258.64
  7753.6  263.46  8065.4  267.97  8801.9  267.37    8999   271.4  9291.9  277.79
#Mann= 12 ,-1 , 0
  1855.9     .17       0  2179.3     .11       0  3498.8     .11       0
    4519     .11       0  4962.4     .11       0 5029.19     .06       0
  5258.4     .11       0  5301.6     .11       0  5481.2     .17       0
  5898.4     .11       0    6256     .15       0    8999     .11       0
#XS Ineff= 3 ,-1
    2580  5015.4  237.19  6043.8    6200   237.2  6556.3    6820  238.97
Permanent Ineff=
       T       F       F
Bank Sta=5029.19,5258.4
XS Rating Curve= 0 ,0
Exp/Cntr=0.3,0.1

Type RM Length L Ch R = 1 ,7354    ,1137,1137,1137
BEGIN DESCRIPTION:
Mapping XS 563491d0
END DESCRIPTION:
XS GIS Cut Line= 3
      3764085.81     10234181.89      3759930.01     10233595.96
      3755357.36     10232752.97
#Sta/Elev= 30
  1817.3  277.54  1956.6  275.77  2571.4  234.85  2804.9  228.67  2966.5  229.66
  3168.5  227.18  3340.2  228.71  3602.7   226.5  4249.1  226.63  4934.9  227.48
  4996.4  229.44  5153.4  226.87  5925.5  226.48  5996.2  224.29  6012.4  226.83
  6880.7  229.23  6954.1  227.55  6992.6  223.49  7023.1  228.77  7195.9  229.13
  7229.3  228.57  7237.4  222.34  7298.3  223.34  7307.8  227.91    7318  229.19
  7348.5  229.43  8991.4  228.24  9657.9  230.54    9933  240.91 10663.9  286.86
#Mann= 4 ,-1 , 0
  1817.3     .12       0  3340.2     .06       0  4996.4     .12       0
  7298.3     .12       0
#XS Ineff= 3 ,-1
    2975  3340.2  228.71  5011.1    9596  229.39
Permanent Ineff=
       T       T       F
Bank Sta=3340.2,4996.4
XS Rating Curve= 0 ,0
Exp/Cntr=0.3,0.1

Type RM Length L Ch R = 1 ,6217    ,2308,2308,2308
BEGIN DESCRIPTION:
Mapping XS 25f81f0c
END DESCRIPTION:
XS GIS Cut Line= 2
      3764031.62     10234084.26      3757553.73     10231252.22
#Sta/Elev= 30
  1424.5  280.27  1846.6  263.99  2167.1  238.97  2568.7  227.77  5008.4  222.51
  5750.5  227.86  5772.3  224.49  6213.7  227.66  6296.2  224.28  6591.9  227.85
  6601.8  227.56  6604.8  220.47  6674.1  221.47  6685.5  226.91  6754.6   226.4
  6912.4  245.14  6959.2  255.19  7092.9  267.87  7384.3  255.14  7535.5  259.57
  7663.4  273.33  7785.9  280.14  7960.6  278.15  8007.4   268.5  8036.2   275.6
  8164.1  275.41  8205.4  269.01  8234.3  277.68    8409   296.4  8494.4  297.36
#Mann= 4 ,-1 , 0
  1424.5     .12       0  2568.7     .06       0  5750.5     .12       0
  6674.1     .12       0
#XS Ineff= 1 ,-1
  5750.5    6780  227.86
Permanent Ineff=
       F
Bank Sta=2568.7,5750.5
XS Rating Curve= 0 ,0
Exp/Cntr=0.3,0.1

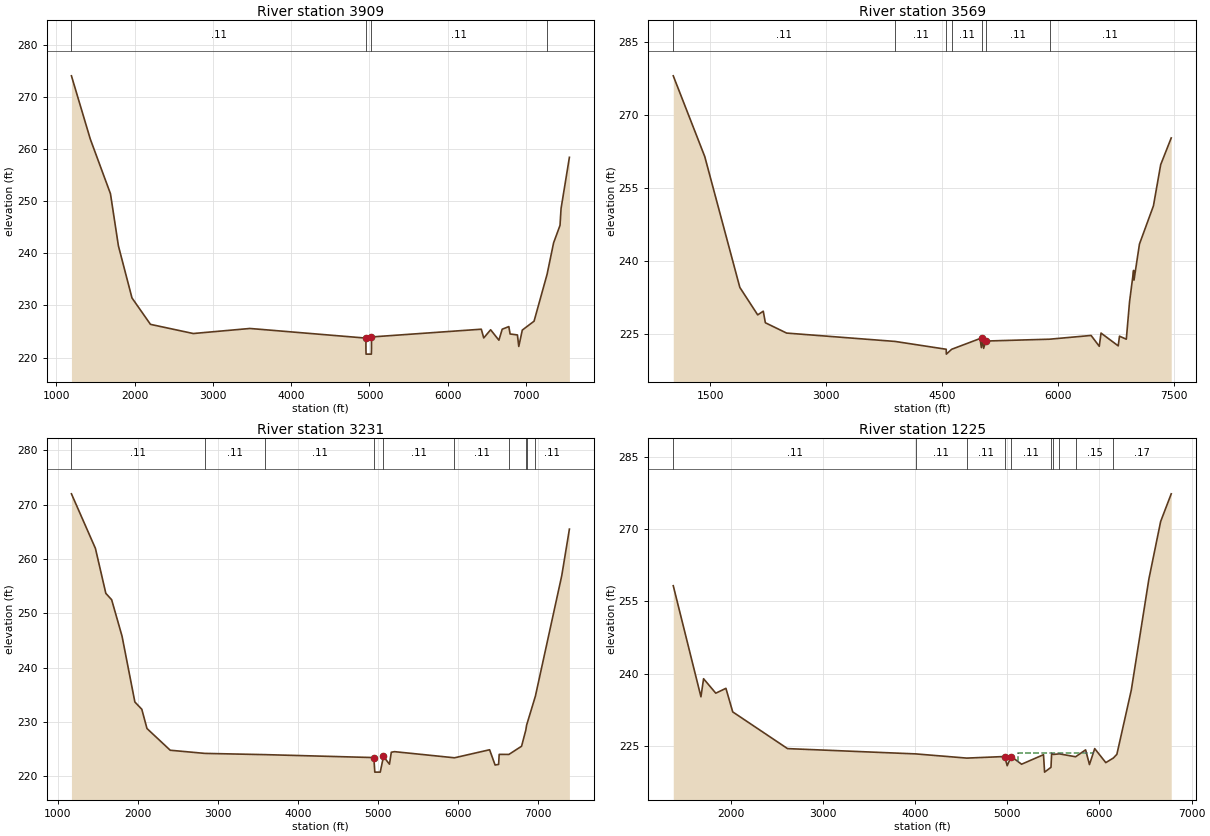
Type RM Length L Ch R = 1 ,3909    ,340,340,340
BEGIN DESCRIPTION:
Mapping XS 0b078d3a
END DESCRIPTION:
XS GIS Cut Line= 4
      3763906.86     10233825.84      3762649.92     10232964.74
      3761024.92     10230728.63      3760344.37     10228770.32
#Sta/Elev= 30
  1193.1  274.13  1434.3  261.96  1691.5  251.48  1793.1  241.46  1966.4  231.45
  2202.6  226.37  2748.9  224.61  3473.2  225.58  4954.8  223.73    4955  221.65
  4956.5  220.65  5024.3  220.65  5025.8  221.65  5025.9  223.95  6428.7  225.44
  6459.8  223.76  6547.6  225.33  6653.4  223.33  6695.8  225.44  6780.5  225.94
  6796.8  224.52  6890.1  224.34  6907.5  222.13  6952.3  225.27  7102.6  226.98
  7268.9  235.99  7352.2  242.04  7434.2   245.4  7447.4  248.62  7554.1  258.47
#Mann= 4 ,-1 , 0
  1193.1     .11       0  4954.8     .06       0  5025.9     .11       0
  7268.9     .17       0
#XS Ineff= 1 ,-1
  6780.5    7075  225.94
Permanent Ineff=
       F
Bank Sta=4954.8,5025.9
XS Rating Curve= 0 ,0
Exp/Cntr=0.3,0.1

Type RM Length L Ch R = 1 ,3569    ,338,338,338
BEGIN DESCRIPTION:
Mapping XS d2b2dac5
END DESCRIPTION:
XS GIS Cut Line= 4
      3764176.46     10233706.39      3762733.32     10232740.68
      3761604.85     10231091.37      3760530.64      10228606.6
#Sta/Elev= 30
  1019.3  278.04  1426.7  261.44  1880.5  234.53  2111.6  228.88  2183.7  229.64
  2210.7  227.26  2485.6  225.14  3889.1  223.42  4550.4  221.81  4551.9  220.81
  4621.2  221.81  4987.4  224.01  5005.1  222.15  5016.3  224.05  5034.3     222
  5063.3   223.5  5887.5  223.88  6424.6  224.65  6530.3  222.42    6553  225.14
  6775.3  222.51  6791.8   224.5  6880.2  223.88  6921.7  231.54  6974.2  238.02
  6979.6  236.03  7050.1  243.44  7230.9   251.3  7324.9  259.78  7461.2  265.27
#Mann= 7 ,-1 , 0
  1019.3     .11       0  3889.1     .11       0  4550.4     .11       0
  4621.2     .11       0  5016.3     .06       0  5063.3     .11       0
  5887.5     .11       0
Bank Sta=5016.3,5063.3
XS Rating Curve= 0 ,0
Exp/Cntr=0.3,0.1

Type RM Length L Ch R = 1 ,3231    ,2006,2006,2006
BEGIN DESCRIPTION:
WFSJR 033 2.0
END DESCRIPTION:
XS GIS Cut Line= 5
       3764277.4      10233416.9      3762776.47     10232450.75
       3762047.6     10231393.74       3761587.3     10230383.02
      3760722.37     10228529.11
#Sta/Elev= 30
  1168.6  272.01  1468.5  261.96  1598.6  253.68  1671.2  252.51  1801.3  245.79
  1961.7  233.67  2048.1  232.34    2113  228.79  2403.5  224.79  2835.9  224.21
  3592.5  223.98    4949  223.44  4961.2  220.76    5029  220.76  5069.7  223.64
  5144.4  222.22  5167.4  224.42  5207.4  224.53  5957.2   223.4  6396.2  224.88
  6464.8  222.07  6508.9  222.18    6516  224.03  6637.6  224.02  6795.9  225.53
  6849.2  228.52  6858.4  229.39  6968.8  234.76    7298  256.93  7393.9  265.51
#Mann= 10 ,-1 , 0
  1168.6     .11       0  2835.9     .11       0  3592.5     .11       0
    4949     .06       0  5069.7     .11       0  5957.2     .11       0
  6637.6     .15       0  6849.2     .11       0  6858.4     .15       0
  6968.8     .11       0
Bank Sta=4949,5069.7
XS Rating Curve= 0 ,0
Exp/Cntr=0.3,0.1

Type RM Length L Ch R = 1 ,1225    ,0,0,0
BEGIN DESCRIPTION:
WFSJR 033 1.0
END DESCRIPTION:
XS GIS Cut Line= 3
      3764374.64     10232222.47      3762397.16     10228726.28
      3761367.69     10227798.85
#Sta/Elev= 30
  1376.1  258.24  1676.4  235.19  1704.9  238.94  1837.3  235.94  1947.4  236.95
  2021.1  232.06  2615.8  224.44  4008.6  223.34  4560.1  222.47  4971.5   222.8
  4998.8  220.89  5042.6   222.8  5154.8   221.2  5392.8  223.18  5404.5  219.56
  5473.9  220.56    5481  223.47  5499.2  223.23  5565.1  223.35    5741  222.75
  5849.5  224.18  5891.4  221.13  5948.2  224.44  6068.5  221.53  6150.7  222.49
  6188.8  223.26    6345  236.57  6535.9  259.62  6663.4  271.56  6778.4  277.31
#Mann= 10 ,-1 , 0
  1376.1     .11       0  4008.6     .11       0  4560.1     .11       0
  4971.5     .06       0  5042.6     .11       0  5473.9     .11       0
  5499.2     .15       0  5565.1     .11       0    5741     .15       0
  6150.7     .17       0
#XS Ineff= 2 ,-1
  5117.2    5943   223.6  5948.2    6210  224.44
Permanent Ineff=
       T       T
Bank Sta=4971.5,5042.6
XS Rating Curve= 0 ,0
Exp/Cntr=0.3,0.1

Chan Stop Cuts=-1
Use User Specified Reach Order=0
Composite Channel Slope=5