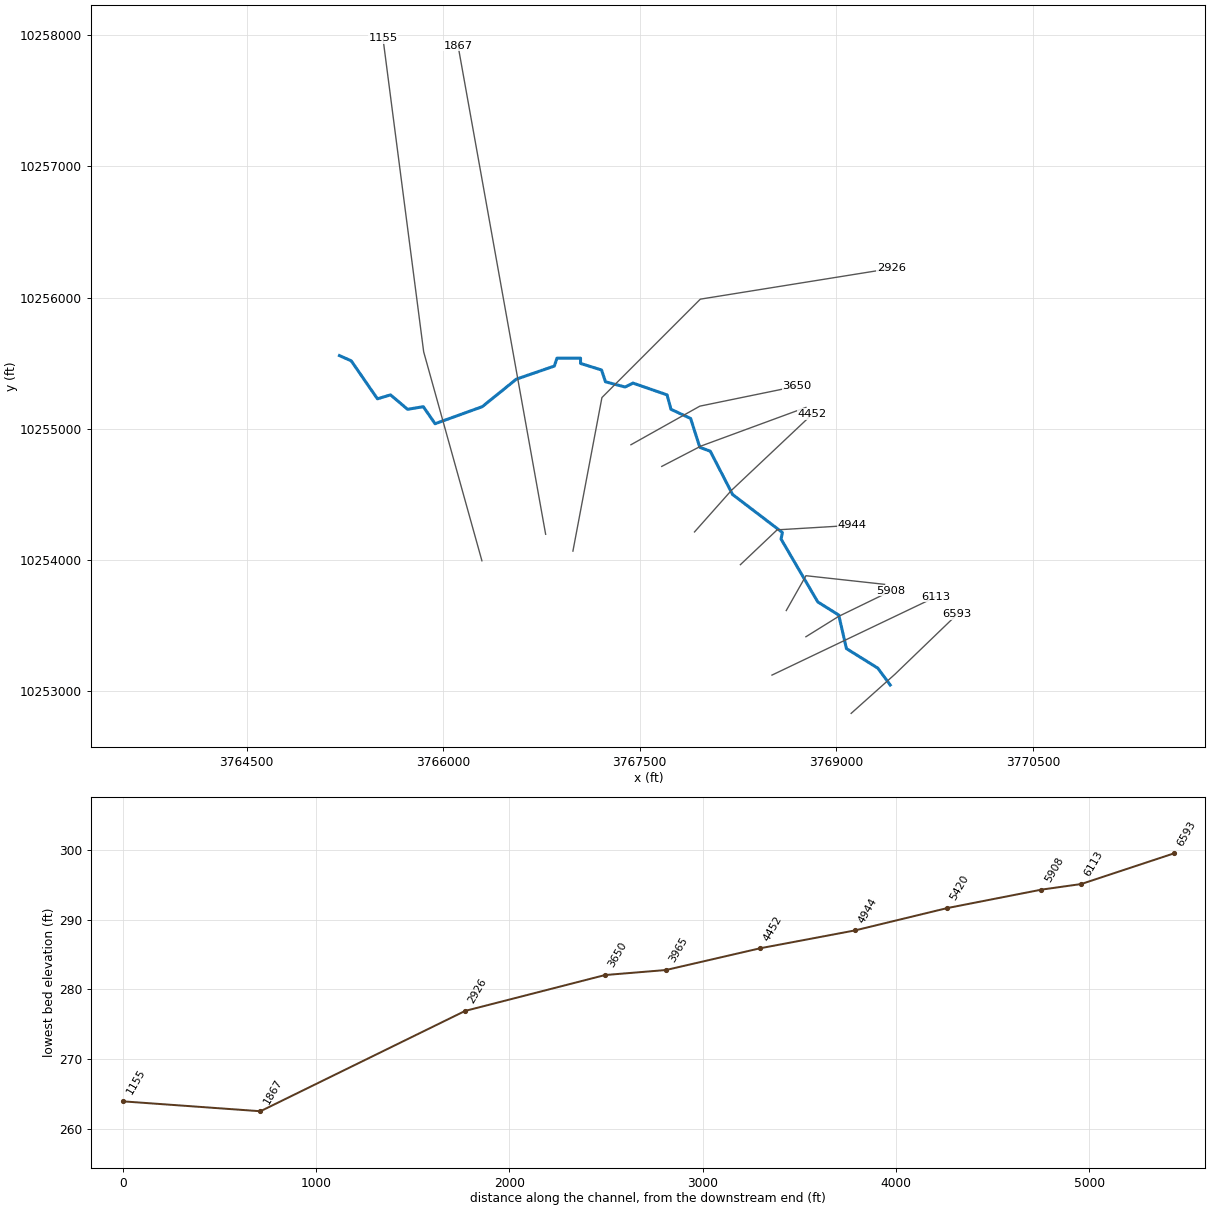
--- WFSJR 034.prj (project) ---

Proj Title=WFSJR 034 Base Level Engineering
Current Plan=p01
Default Exp/Contr=0.3,0.1
English Units
Geom File=g01
Flow File=f01
Plan File=p01
Y Axis Title=Elevation
X Axis Title(PF)=Main Channel Distance
X Axis Title(XS)=Station
BEGIN DESCRIPTION:
WFSJR 034
END DESCRIPTION:
DSS Export Rating Curves= 0
DSS Export Rating Curve Sorted= 0
DSS Export Volume Flow Curves= 0
DXF OffsetX= 0
DXF OffsetY= 0
DXF ScaleX= 1
DXF ScaleY= 10

--- WFSJR 034.p01 (plan) ---

Plan Title=Multiple Run
Program Version=4.10
Short Identifier=Multiple
Geom File=g01
Flow File=f01
Subcritical Flow
K Sum by GR= 0
Std Step Tol= 0.01
Critical Tol= 0.01
Num of Std Step Trials= 20
Max Error Tol= 0.3
Flow Tol Ratio= 0.001
Split Flow NTrial= 30
Split Flow Tol= 0.02
Split Flow Ratio= 0.02
Log Output Level= 0
Friction Slope Method= 1
Unsteady Friction Slope Method= 2
Unsteady Bridges Friction Slope Method= 1
Parabolic Critical Depth
Global Vel Dist= 1 , 1 , 1
Global Log Level= 0
CheckData=True
Encroach Param=-1 ,0,0, 0
BEGIN DESCRIPTION:
Multiple Run
END DESCRIPTION:
Computation Interval=1HOUR
Output Interval=1HOUR
Run HTab= 0
Run UNet= 0
Run PostProcess= 0
Run WQNet= 0
UNET Theta= 1
UNET Theta Warmup= 1
UNET ZTol= 0.02
UNET ZSATol= 0.05
UNET MxIter= 20
UNET MaxInSteps= 0
UNET DtIC= 0
UNET DtMin= 0
UNET MaxCRTS= 20
UNET WFStab= 2
UNET SFStab= 1
UNET WFX= 1
UNET SFX= 1
UNET DSS MLevel= 4
UNET DZMax Abort= 100
UNET Convert EG Bridges= 0
UNET Use Existing IB Tables=-1
UNET Froude Reduction=False
UNET Froude Limit= 1
UNET Froude Power= 10
UNET Time Slicing=0,0, 5
UNET Junction Losses=0
Instantaneous Interval=1HOUR
Write IC File= 0
Write IC File at Sim End=0
Echo Input=False
Echo Parameters=False
Echo Output=False
Write Detailed= 0
WQ AD Non Conservative
WQ ULTIMATE=-1
WQ Max Comp Step=1HOUR
WQ Output Interval=15MIN
WQ Output Selected Increments= 0
WQ Output face flow=0
WQ Output face velocity=0
WQ Output face area=0
WQ Output face dispersion=0
WQ Output cell volume=0
WQ Output cell surface area=0
WQ Output cell continuity=0
WQ Output cumulative cell continuity=0
WQ Output face conc=0
WQ Output face dconc_dx=0
WQ Output face courant=0
WQ Output face peclet=0
WQ Output face adv mass=0
WQ Output face disp mass=0
WQ Output cell mass=0
WQ Output cell source sink temp=0
WQ Output cell source sink nsm=0
WQ Output MaxMinRange=-1
WQ Daily Max Min Mean=-1
WQ Daily Range=0
WQ Daily Time=0
WQ Create Restart=0
WQ Fixed Restart=0
WQ System Summary=0
WQ Use Fixed Temperature=0
Sorting and Armoring Iterations= 10
XS Update Threshold= 0.02
Hydraulics Update Threshold= 0.02
Energy Slope Method= 1
Volume Change Method= 0
XS Weighting Method= 0
Number of US Weighted Cross Sections= 1
Number of DS Weighted Cross Sections= 1
Upstream XS Weight=0.25
Main XS Weight=0.5
Downstream XS Weight=0.25
Number of DS XS's Weighted with US Boundary= 1
Upstream Boundary Weight= 1
Weight of XSs Associated with US Boundary= 0
Number of US XS's Weighted with DS Boundary= 1
Downstream Boundary Weight= 0.5
Weight of XSs Associated with DS Boundary= 0.5
Sediment Output Level= 4
Mass or Volume Output= 0
Output Increment Type= 1
Profile and TS Output Increment= 10
XS Output Flag= 0
XS Output Increment= 10
Disregard all LS=0
Disregard all Conn=0
Disregard all Breaches=0
Disregard all Pumps=0

--- WFSJR 034.f01 (steady flow) ---

Flow Title=Multiple
Program Version=4.10
Number of Profiles= 7
Profile Names=10-year,25-year,50-year,1pct_min,100-year,1pct_plu,500-year
River Rch & RM=WFSJR 034,Reach-1         ,6593
     457     611     819     363    1095    3307    2016
River Rch & RM=WFSJR 034,Reach-1         ,5908
     831    1145    1566     705    2129    6429    4064
Boundary for River Rch & Prof#=WFSJR 034,Reach-1         , 1
Up Type= 0
Dn Type= 3
Dn Slope=0.0025
Boundary for River Rch & Prof#=WFSJR 034,Reach-1         , 2
Up Type= 0
Dn Type= 3
Dn Slope=0.0025
Boundary for River Rch & Prof#=WFSJR 034,Reach-1         , 3
Up Type= 0
Dn Type= 3
Dn Slope=0.0025
Boundary for River Rch & Prof#=WFSJR 034,Reach-1         , 4
Up Type= 0
Dn Type= 3
Dn Slope=0.0025
Boundary for River Rch & Prof#=WFSJR 034,Reach-1         , 5
Up Type= 0
Dn Type= 3
Dn Slope=0.0025
Boundary for River Rch & Prof#=WFSJR 034,Reach-1         , 6
Up Type= 0
Dn Type= 3
Dn Slope=0.0025
Boundary for River Rch & Prof#=WFSJR 034,Reach-1         , 7
Up Type= 0
Dn Type= 3
Dn Slope=0.0025
DSS Import GetInterval= 0
DSS Import GetPeak= 0
DSS Import FillOption= 0

--- WFSJR 034.g01 (geometry) ---

Geom Title=Existing Conditions
Program Version=4.10

River Reach=WFSJR 034       ,Reach-1
Reach XY= 30
      3769411.31     10253042.79      3769316.31      10253171.6
      3769077.04      10253320.7      3769018.23     10253576.84
      3768858.23     10253676.84      3768578.23     10254156.84
      3768588.23     10254206.84      3768208.23     10254496.84
      3768038.23     10254826.84      3767958.23     10254856.84
      3767888.23     10255076.84      3767738.23     10255146.84
      3767708.23     10255256.84      3767448.23     10255346.84
      3767388.23     10255316.84      3767238.23     10255356.84
      3767208.23     10255446.84      3767048.23     10255496.84
      3767048.23     10255536.84      3766868.23     10255536.84
      3766848.23     10255476.84      3766558.23     10255376.84
      3766298.23     10255166.84      3765938.23     10255036.84
      3765848.23     10255166.84      3765728.23     10255146.84
      3765598.23     10255256.84      3765498.23     10255226.84
      3765298.23     10255516.84      3765208.23     10255556.84

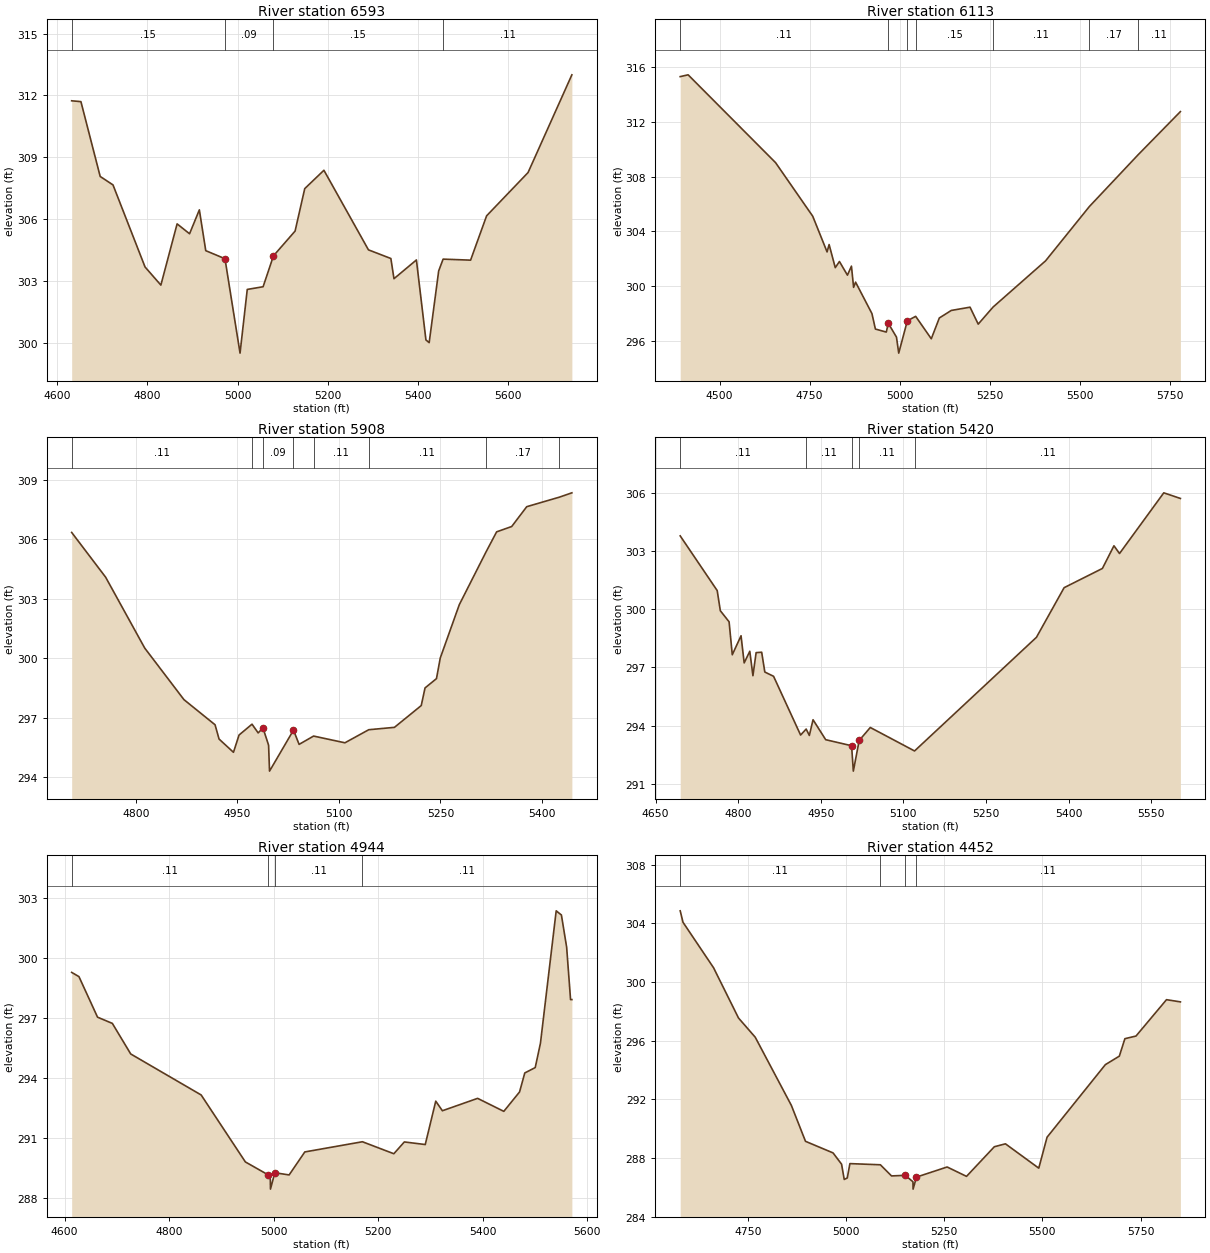
Type RM Length L Ch R = 1 ,6593    ,480,480,480
BEGIN DESCRIPTION:
WFSJR 034 8.0
END DESCRIPTION:
XS GIS Cut Line= 3
      3769113.16     10252826.31      3769446.64     10253124.49
      3769922.94     10253583.33
#Sta/Elev= 30
  4632.3  311.74  4652.8   311.7  4695.5  308.07  4723.9  307.66  4794.9  303.68
    4830   302.8    4866  305.77  4893.6  305.29  4915.3  306.45  4929.5  304.47
  4972.1  304.08  5005.5   299.5  5021.5  302.59  5056.6  302.72  5079.6  304.22
  5127.5  305.42  5148.9  307.48  5191.4  308.37  5290.1  304.51  5339.8  304.09
  5346.7  303.11  5396.4  304.02  5417.5  300.14  5424.7  300.01  5445.8  303.49
  5455.6  304.06  5516.5  304.01    5552  306.16  5643.9  308.26    5741     313
#Mann= 4 ,-1 , 0
  4632.3     .15       0  4972.1     .09       0  5079.6     .15       0
  5455.6     .11       0
#XS Ineff= 2 ,-1
    4720  4915.3  306.45  5191.4    5680  308.37
Permanent Ineff=
       F       F
Bank Sta=4972.1,5079.6
XS Rating Curve= 0 ,0
Exp/Cntr=0.3,0.1

Type RM Length L Ch R = 1 ,6113    ,205,205,205
BEGIN DESCRIPTION:
Mapping XS 6fc092a0
END DESCRIPTION:
XS GIS Cut Line= 2
      3768509.07      10253118.5      3769761.69     10253716.63
#Sta/Elev= 30
  4390.9  315.32  4412.9  315.45  4655.5  309.03  4758.7  305.11  4798.5   302.5
  4804.1  303.04  4821.2  301.35  4832.8   301.8    4855   300.8  4866.1  301.46
  4872.1  299.91  4877.6  300.29    4923  297.99  4932.6  296.86  4962.8  296.64
  4968.4  297.28  4991.1  296.27  4997.3   295.1  5021.2  297.46  5044.3  297.79
  5087.7  296.15    5110  297.67  5143.1  298.22  5195.2  298.46  5217.9  297.22
  5259.2  298.47  5404.9  301.85  5526.4  305.82  5661.5   309.6    5779  312.76
#Mann= 7 ,-1 , 0
  4390.9     .11       0  4968.4     .06       0  5021.2     .11       0
  5044.3     .15       0  5259.2     .11       0  5526.4     .17       0
  5661.5     .11       0
Bank Sta=4968.4,5021.2
XS Rating Curve= 0 ,0
Exp/Cntr=0.3,0.1

Type RM Length L Ch R = 1 ,5908    ,488,488,488
BEGIN DESCRIPTION:
WFSJR 034 7.0
END DESCRIPTION:
XS GIS Cut Line= 3
      3768767.84     10253411.06      3769018.23     10253566.84
      3769417.83     10253761.06
#Sta/Elev= 30
  4705.1  306.35  4755.3  304.09  4813.1  300.51    4871  297.91    4917  296.64
  4922.9  295.92  4944.2  295.25  4952.4  296.12  4971.6  296.67  4980.7  296.23
  4987.8  296.48  4996.1  295.61  4997.5   294.3  5032.9  296.37  5041.2  295.65
  5062.6  296.07  5108.9  295.73  5144.1  296.39  5182.1  296.51  5221.7  297.61
  5227.3   298.5  5244.2  298.97  5249.8  300.01  5277.9   302.7  5317.2  305.35
  5333.1  306.38  5355.4  306.65  5377.6  307.65  5425.7  308.13  5444.3  308.35
#Mann= 8 ,-1 , 0
  4705.1     .11       0  4971.6     .15       0  4987.8     .09       0
  5032.9     .15       0  5062.6     .11       0  5144.1     .11       0
  5317.2     .17       0  5425.7     .11       0
Bank Sta=4987.8,5032.9
XS Rating Curve= 0 ,0
Exp/Cntr=0.3,0.1

Type RM Length L Ch R = 1 ,5420    ,476,476,476
BEGIN DESCRIPTION:
WFSJR 034 6.0
END DESCRIPTION:
XS GIS Cut Line= 3
      3768617.84     10253611.04      3768768.23     10253876.84
      3769367.83     10253811.07
#Sta/Elev= 30
  4694.6  303.78  4761.8  300.96  4767.5  299.92  4783.4  299.35  4789.2  297.65
  4805.1  298.63  4810.8  297.23    4821  297.83  4826.7  296.57  4832.5  297.76
  4842.6  297.78  4848.3  296.76  4864.2  296.54  4913.3  293.51  4923.4  293.82
  4929.2  293.49  4935.9   294.3  4958.9  293.27  5005.9  292.96  5009.1  291.65
  5019.7  293.23  5039.9   293.9  5120.3  292.69  5341.7  298.55    5392  301.11
  5461.5   302.1  5482.5  303.27  5492.6  302.87    5573     306  5603.2  305.71
#Mann= 5 ,-1 , 0
  4694.6     .11       0  4923.4     .11       0  5005.9     .06       0
  5019.7     .11       0  5120.3     .11       0
Bank Sta=5005.9,5019.7
XS Rating Curve= 0 ,0
Exp/Cntr=0.3,0.1

Type RM Length L Ch R = 1 ,4944    ,492,492,492
BEGIN DESCRIPTION:
WFSJR 034 5.0
END DESCRIPTION:
XS GIS Cut Line= 3
      3768267.87     10253961.09      3768548.23     10254226.84
       3769117.8     10254261.07
#Sta/Elev= 30
  4613.7  299.29  4627.6  299.08  4663.2  297.05  4691.5  296.74  4726.7  295.21
  4861.4  293.16    4946  289.81  4988.5  289.18  4993.7  288.95    4994  288.45
  5002.3  289.27  5029.7  289.16  5059.7  290.31  5169.9  290.82    5230  290.22
  5250.1  290.81  5290.1  290.68  5310.2  292.85  5322.9  292.37  5390.3  292.99
  5440.4  292.34  5470.5  293.31  5480.5  294.26  5500.5  294.53  5510.5  295.75
  5540.6  302.37  5550.6  302.16  5560.6  300.55  5568.1  297.93  5570.6  297.93
#Mann= 4 ,-1 , 0
  4613.7     .11       0  4988.5     .06       0  5002.3     .11       0
  5169.9     .11       0
Bank Sta=4988.5,5002.3
XS Rating Curve= 0 ,0
Exp/Cntr=0.3,0.1

Type RM Length L Ch R = 1 ,4452    ,487,487,487
BEGIN DESCRIPTION:
WFSJR 034 4.0
END DESCRIPTION:
XS GIS Cut Line= 3
      3767917.84     10254211.06      3768198.23     10254526.84
      3768817.84     10255111.06
#Sta/Elev= 30
  4577.7  304.86  4584.8  304.08  4662.6  300.98  4726.2  297.55  4768.8  296.24
  4860.8  291.59  4896.8  289.14    4967  288.35  4988.7  287.58  4995.4  286.54
  5003.2  286.64  5009.9  287.62  5087.6  287.54  5115.9  286.78  5151.1  286.82
  5170.5  286.38  5170.8  285.88  5179.4   286.7  5257.5  287.39  5306.9  286.75
  5377.7  288.77    5406  288.97  5490.9  287.31    5512  289.42  5660.5  294.37
  5696.1  294.95  5710.2  296.14  5738.5  296.32  5816.2   298.8  5851.6  298.65
#Mann= 4 ,-1 , 0
  4577.7     .11       0  5087.6     .11       0  5151.1     .06       0
  5179.4     .11       0
#XS Ineff= 1 ,-1
    5406    5515  288.97
Permanent Ineff=
       T
Bank Sta=5151.1,5179.4
XS Rating Curve= 0 ,0
Exp/Cntr=0.3,0.1

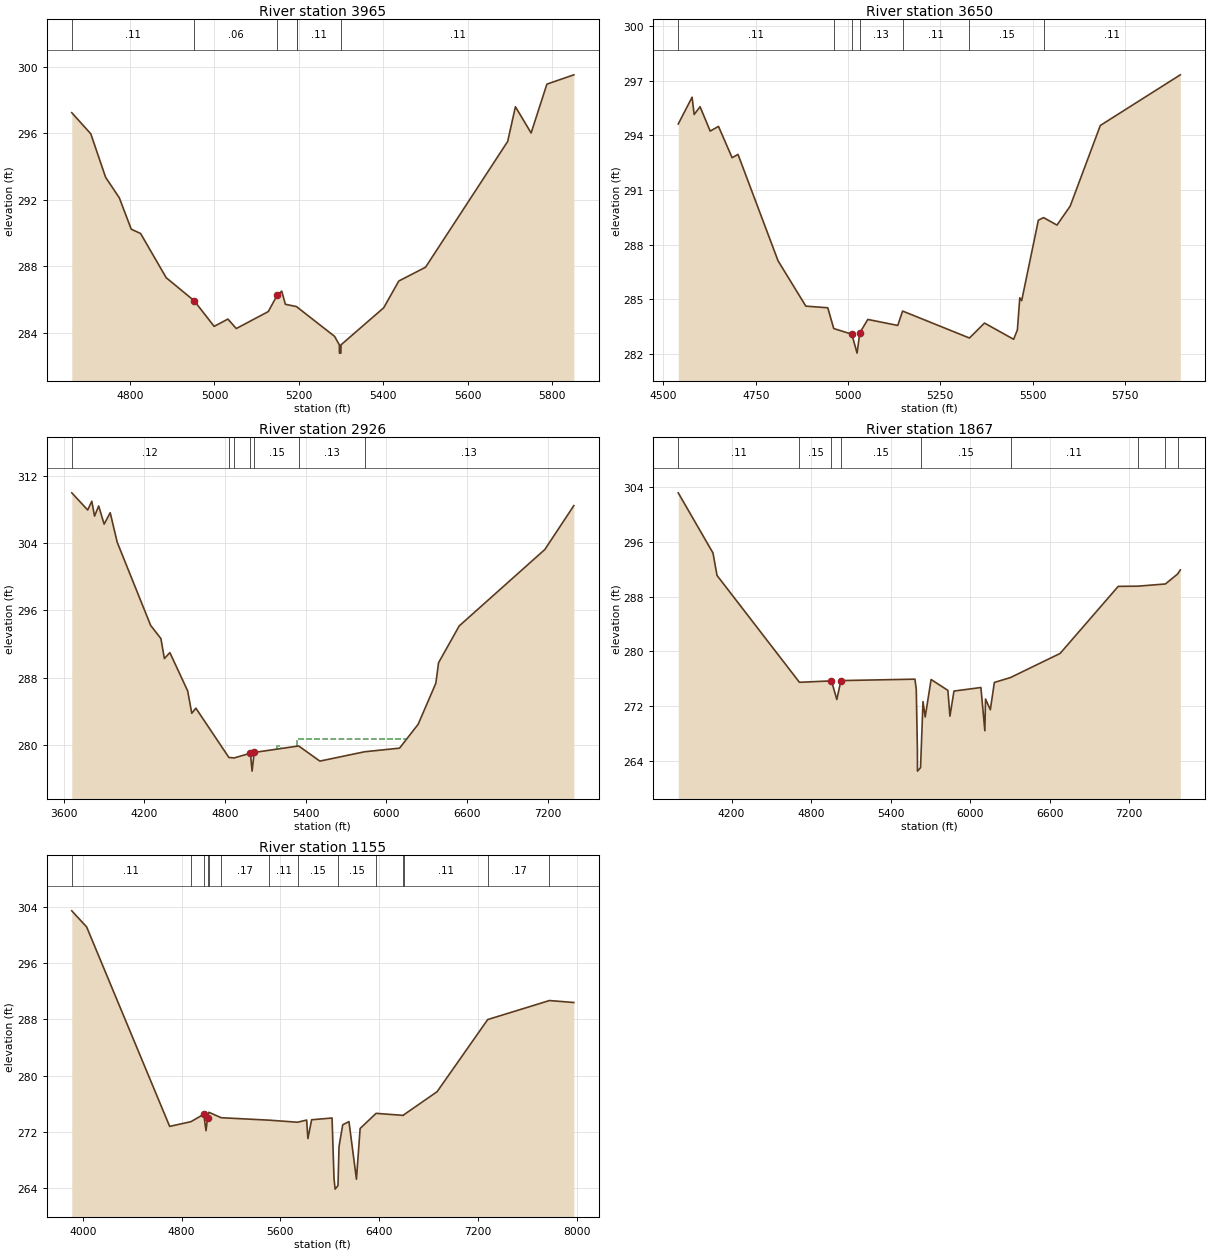
Type RM Length L Ch R = 1 ,3965    ,315,315,315
BEGIN DESCRIPTION:
WFSJR 034 3.0
END DESCRIPTION:
XS GIS Cut Line= 3
      3767667.82     10254711.06      3767968.23     10254866.84
      3768767.82     10255161.06
#Sta/Elev= 30
  4661.6  297.23  4706.7  295.96  4741.9  293.34  4774.3  292.11  4802.6  290.22
  4824.8  289.96  4885.5   287.3  4951.9  285.91  4999.2  284.37  5031.8  284.81
  5051.6  284.24  5127.5  285.26  5148.8  286.25  5159.4  286.49  5168.1   285.7
  5194.7  285.56  5194.9  285.55  5284.7  283.77    5296  283.26  5296.2  282.76
  5299.7  282.76    5300  283.26  5401.2  285.49    5437   287.1  5500.4  287.93
  5695.1   295.5  5713.5  297.59  5750.7  296.01  5788.1  298.95    5852  299.51
#Mann= 6 ,-1 , 0
  4661.6     .11       0  4951.9     .06       0  5148.8     .11       0
  5194.7     .15       0  5194.9     .11       0    5300     .11       0
#XS Ineff= 1 ,-1
  5159.4    5440  286.49
Permanent Ineff=
       T
Bank Sta=4951.9,5148.8
XS Rating Curve= 0 ,0
Exp/Cntr=0.3,0.1

Type RM Length L Ch R = 1 ,3650    ,724,724,724
BEGIN DESCRIPTION:
WFSJR 034 2.0
END DESCRIPTION:
XS GIS Cut Line= 3
      3767432.72     10254876.34      3767958.38     10255170.86
      3768700.02     10255323.36
#Sta/Elev= 30
  4540.1  294.62  4577.6  296.09  4583.3  295.14  4599.2  295.57  4626.7  294.23
  4649.1  294.49    4686  292.77    4702  292.95  4810.4  287.11  4885.7  284.62
  4945.1  284.53  4961.2  283.39  5010.2  283.08  5024.4  282.04  5031.8  283.15
  5053.5  283.89  5134.6  283.56  5147.7  284.35  5328.7  282.87  5369.5  283.69
  5448.4   282.8  5458.6  283.32  5465.1  285.08  5470.2  284.92  5515.4  289.34
  5529.6  289.48  5565.8  289.07  5601.5  290.11  5683.2  294.54  5899.8  297.32
#Mann= 7 ,-1 , 0
  4540.1     .11       0  4961.2     .13       0  5010.2     .07       0
  5031.8     .13       0  5147.7     .11       0  5328.7     .15       0
  5529.6     .11       0
Bank Sta=5010.2,5031.8
XS Rating Curve= 0 ,0
Exp/Cntr=0.3,0.1

Type RM Length L Ch R = 1 ,2926    ,1059,1059,1059
BEGIN DESCRIPTION:
Mapping XS 45f811ee
END DESCRIPTION:
XS GIS Cut Line= 4
      3766989.98     10254064.68      3767211.33     10255236.56
       3767962.2     10255987.43       3769420.5      10256221.8
#Sta/Elev= 30
  3660.9  309.95  3779.2  307.91  3809.9  308.95  3830.2  307.18  3860.8  308.39
  3901.5  306.23  3946.5  307.59  3998.9  304.07  4247.5  294.19  4323.4  292.64
  4349.3  290.26    4390  290.97  4522.3  286.42  4552.8  283.76  4583.3  284.37
  4828.8  278.51  4868.4  278.46  4988.6  279.02    5001  276.89  5016.9  279.11
  5347.4  279.88  5504.8  278.08  5837.1  279.19  6097.1  279.62  6235.1  282.45
  6366.8  287.33    6387  289.77  6540.5  294.14    7177  303.22  7392.4  308.43
#Mann= 7 ,-1 , 0
  3660.9     .12       0  4828.8     .15       0  4868.4     .12       0
  4988.6     .08       0  5016.9     .15       0  5347.4     .13       0
  5837.1     .13       0
#XS Ineff= 2 ,-1
  5186.6    5215  279.87  5335.1    6160  280.69
Permanent Ineff=
       T       T
Bank Sta=4988.6,5016.9
XS Rating Curve= 0 ,0
Exp/Cntr=0.3,0.1

Type RM Length L Ch R = 1 ,1867    ,712,712,712
BEGIN DESCRIPTION:
Mapping XS ca42ce42
END DESCRIPTION:
XS GIS Cut Line= 2
      3766781.82     10254193.01      3766113.42     10257922.18
#Sta/Elev= 30
  3797.3  303.16  4059.5  294.37    4090  291.09  4711.9  275.47  4953.5  275.68
  4994.1  272.96  5024.6  275.72  5583.4  275.93  5593.5  274.46  5601.9  265.69
  5602.6  262.49  5625.7  262.99  5644.3  272.65  5660.8   270.4  5705.3  275.88
  5832.1  274.29  5847.5  270.53    5878  274.19  6081.2  274.71    6111  268.39
  6116.1  273.03  6152.3  271.46  6182.8  275.45  6304.9  276.17  6678.9  279.69
  7117.4  289.49  7267.3  289.52  7473.3  289.84  7564.7  291.28  7585.9  291.89
#Mann= 9 ,-1 , 0
  3797.3     .11       0  4711.9     .15       0  4953.5     .09       0
  5024.6     .15       0  5625.7     .15       0  6304.9     .11       0
  7267.3     .17       0  7473.3     .11       0  7564.7     .17       0
Bank Sta=4953.5,5024.6
XS Rating Curve= 0 ,0
Exp/Cntr=0.3,0.1

Type RM Length L Ch R = 1 ,1155    ,0,0,0
BEGIN DESCRIPTION:
WFSJR 034 1.0
END DESCRIPTION:
XS GIS Cut Line= 3
      3766295.53     10253990.91      3765851.15      10255585.3
      3765540.56     10257977.86
#Sta/Elev= 30
  3909.5  303.43  4030.1  301.14  4702.7  272.82  4875.1  273.49  4978.9  274.54
  4997.1  272.21  5010.1  274.02  5020.5  274.82  5120.5  274.05  5511.3   273.7
  5738.7  273.41  5812.5  273.72  5822.6  271.09  5852.8  273.76  6018.4  274.01
  6034.3  265.41  6043.2  263.91  6066.3  264.41  6074.7  269.95  6104.9  273.05
  6155.4   273.5  6215.9  265.32  6245.8  272.52    6375  274.67  6596.9  274.38
  6601.5  274.49  6869.1  277.74  7279.4  287.99  7779.7  290.69  7977.3  290.41
#Mann= 14 ,-1 , 0
  3909.5     .11       0  4875.1     .15       0  4978.9     .07       0
  5010.1     .11       0  5020.5     .15       0  5120.5     .17       0
  5511.3     .11       0  5738.7     .15       0  6066.3     .15       0
    6375     .11       0  6596.9     .15       0  6601.5     .11       0
  7279.4     .17       0  7779.7     .11       0
Bank Sta=4978.9,5010.1
XS Rating Curve= 0 ,0
Exp/Cntr=0.3,0.1

Chan Stop Cuts=-1
Use User Specified Reach Order=0
Composite Channel Slope=5