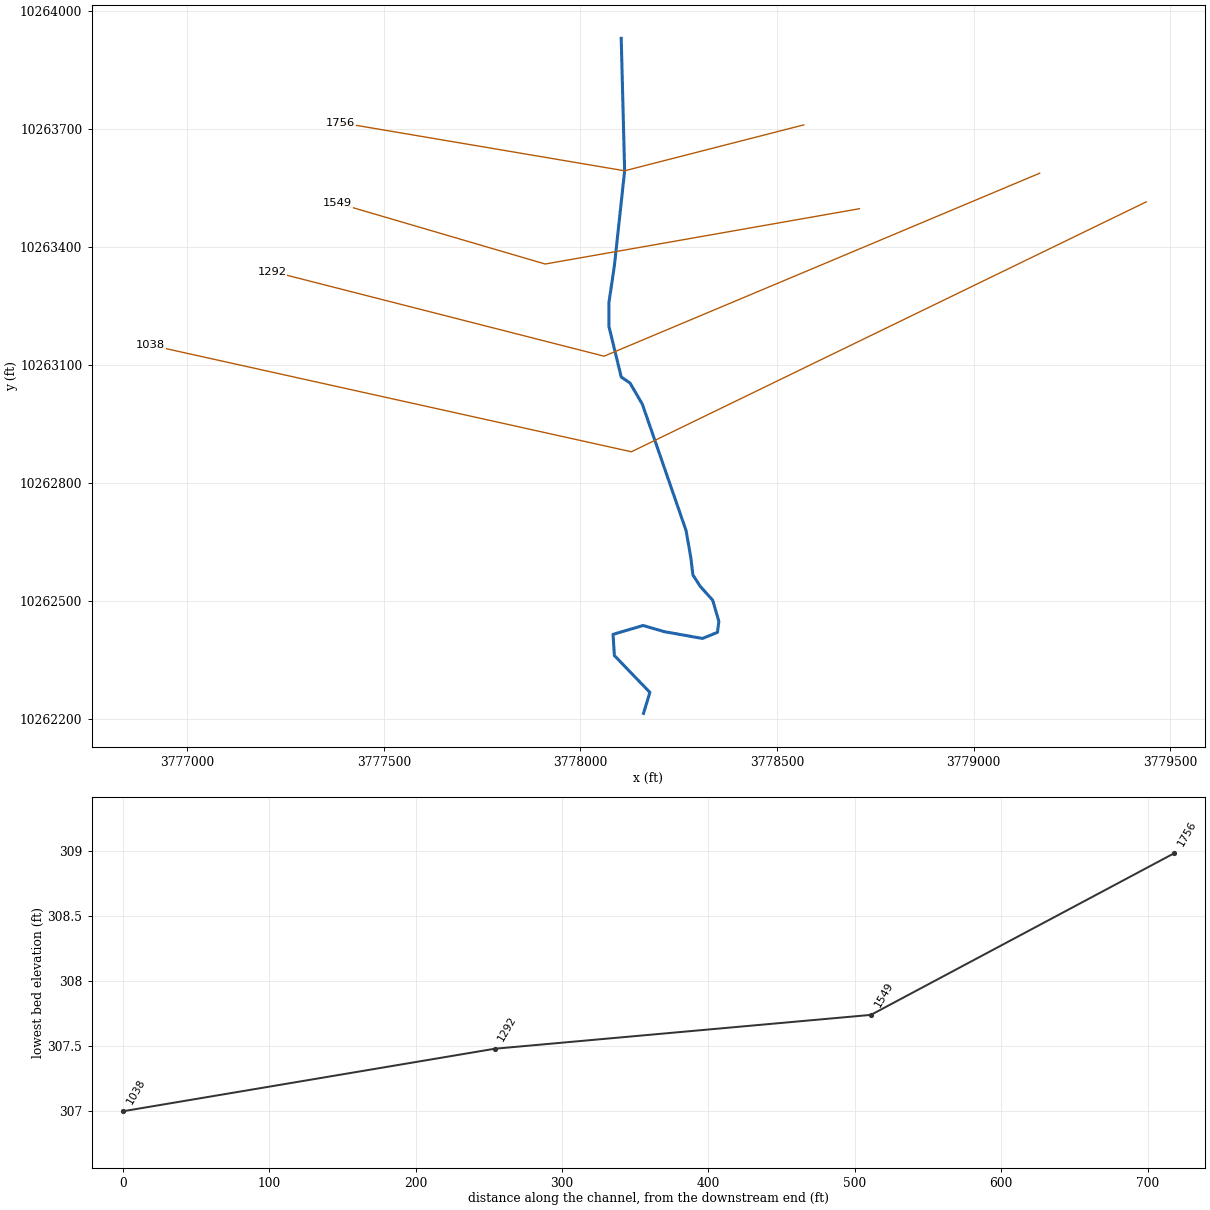
--- WFSJR 037.prj (project) ---

Proj Title=WFSJR 037 Base Level Engineering
Current Plan=p01
Default Exp/Contr=0.3,0.1
English Units
Geom File=g01
Flow File=f01
Plan File=p01
Y Axis Title=Elevation
X Axis Title(PF)=Main Channel Distance
X Axis Title(XS)=Station
BEGIN DESCRIPTION:
WFSJR 037
END DESCRIPTION:
DSS Export Rating Curves= 0
DSS Export Rating Curve Sorted= 0
DSS Export Volume Flow Curves= 0
DXF OffsetX= 0
DXF OffsetY= 0
DXF ScaleX= 1
DXF ScaleY= 10

--- WFSJR 037.p01 (plan) ---

Plan Title=Multiple Run
Program Version=4.10
Short Identifier=Multiple
Geom File=g01
Flow File=f01
Subcritical Flow
K Sum by GR= 0
Std Step Tol= 0.01
Critical Tol= 0.01
Num of Std Step Trials= 20
Max Error Tol= 0.3
Flow Tol Ratio= 0.001
Split Flow NTrial= 30
Split Flow Tol= 0.02
Split Flow Ratio= 0.02
Log Output Level= 0
Friction Slope Method= 1
Unsteady Friction Slope Method= 2
Unsteady Bridges Friction Slope Method= 1
Parabolic Critical Depth
Global Vel Dist= 1 , 1 , 1
Global Log Level= 0
CheckData=True
Encroach Param=-1 ,0,0, 0
BEGIN DESCRIPTION:
Multiple Run
END DESCRIPTION:
Computation Interval=1HOUR
Output Interval=1HOUR
Run HTab= 0
Run UNet= 0
Run PostProcess= 0
Run WQNet= 0
UNET Theta= 1
UNET Theta Warmup= 1
UNET ZTol= 0.02
UNET ZSATol= 0.05
UNET MxIter= 20
UNET MaxInSteps= 0
UNET DtIC= 0
UNET DtMin= 0
UNET MaxCRTS= 20
UNET WFStab= 2
UNET SFStab= 1
UNET WFX= 1
UNET SFX= 1
UNET DSS MLevel= 4
UNET DZMax Abort= 100
UNET Convert EG Bridges= 0
UNET Use Existing IB Tables=-1
UNET Froude Reduction=False
UNET Froude Limit= 1
UNET Froude Power= 10
UNET Time Slicing=0,0, 5
UNET Junction Losses=0
Instantaneous Interval=1HOUR
Write IC File= 0
Write IC File at Sim End=0
Echo Input=False
Echo Parameters=False
Echo Output=False
Write Detailed= 0
WQ AD Non Conservative
WQ ULTIMATE=-1
WQ Max Comp Step=1HOUR
WQ Output Interval=15MIN
WQ Output Selected Increments= 0
WQ Output face flow=0
WQ Output face velocity=0
WQ Output face area=0
WQ Output face dispersion=0
WQ Output cell volume=0
WQ Output cell surface area=0
WQ Output cell continuity=0
WQ Output cumulative cell continuity=0
WQ Output face conc=0
WQ Output face dconc_dx=0
WQ Output face courant=0
WQ Output face peclet=0
WQ Output face adv mass=0
WQ Output face disp mass=0
WQ Output cell mass=0
WQ Output cell source sink temp=0
WQ Output cell source sink nsm=0
WQ Output MaxMinRange=-1
WQ Daily Max Min Mean=-1
WQ Daily Range=0
WQ Daily Time=0
WQ Create Restart=0
WQ Fixed Restart=0
WQ System Summary=0
WQ Use Fixed Temperature=0
Sorting and Armoring Iterations= 10
XS Update Threshold= 0.02
Hydraulics Update Threshold= 0.02
Energy Slope Method= 1
Volume Change Method= 0
XS Weighting Method= 0
Number of US Weighted Cross Sections= 1
Number of DS Weighted Cross Sections= 1
Upstream XS Weight=0.25
Main XS Weight=0.5
Downstream XS Weight=0.25
Number of DS XS's Weighted with US Boundary= 1
Upstream Boundary Weight= 1
Weight of XSs Associated with US Boundary= 0
Number of US XS's Weighted with DS Boundary= 1
Downstream Boundary Weight= 0.5
Weight of XSs Associated with DS Boundary= 0.5
Sediment Output Level= 4
Mass or Volume Output= 0
Output Increment Type= 1
Profile and TS Output Increment= 10
XS Output Flag= 0
XS Output Increment= 10
Disregard all LS=0
Disregard all Conn=0
Disregard all Breaches=0
Disregard all Pumps=0

--- WFSJR 037.f01 (steady flow) ---

Flow Title=Multiple
Program Version=4.10
Number of Profiles= 7
Profile Names=10-year,25-year,50-year,1pct_min,100-year,1pct_plu,500-year
River Rch & RM=WFSJR 037,Reach-1         ,1756
     626     849    1147     511    1543    4660    2883
Boundary for River Rch & Prof#=WFSJR 037,Reach-1         , 1
Up Type= 0
Dn Type= 3
Dn Slope=0.003
Boundary for River Rch & Prof#=WFSJR 037,Reach-1         , 2
Up Type= 0
Dn Type= 3
Dn Slope=0.003
Boundary for River Rch & Prof#=WFSJR 037,Reach-1         , 3
Up Type= 0
Dn Type= 3
Dn Slope=0.003
Boundary for River Rch & Prof#=WFSJR 037,Reach-1         , 4
Up Type= 0
Dn Type= 3
Dn Slope=0.003
Boundary for River Rch & Prof#=WFSJR 037,Reach-1         , 5
Up Type= 0
Dn Type= 3
Dn Slope=0.003
Boundary for River Rch & Prof#=WFSJR 037,Reach-1         , 6
Up Type= 0
Dn Type= 3
Dn Slope=0.003
Boundary for River Rch & Prof#=WFSJR 037,Reach-1         , 7
Up Type= 0
Dn Type= 3
Dn Slope=0.003
DSS Import GetInterval= 0
DSS Import GetPeak= 0
DSS Import FillOption= 0

--- WFSJR 037.g01 (geometry) ---

Geom Title=Existing Conditions
Program Version=4.10

River Reach=WFSJR 037       ,Reach-1
Reach XY= 23
      3778103.71      10263931.2      3778112.39     10263594.39
      3778086.35     10263353.07      3778072.46     10263259.32
      3778072.46     10263198.56      3778103.71     10263070.08
      3778126.28     10263054.46      3778157.53     10263000.64
      3778268.64     10262679.46      3778280.79     10262610.02
        3778286.     10262566.61       3778305.1      10262537.1
      3778336.35     10262502.38      3778351.98     10262448.56
       3778348.5     10262420.78      3778310.31     10262405.15
      3778213.09     10262422.52      3778159.27     10262438.14
      3778082.88     10262415.57      3778086.35     10262361.75
      3778129.75     10262316.61      3778176.63       10262268.
       3778160.4     10262214.67

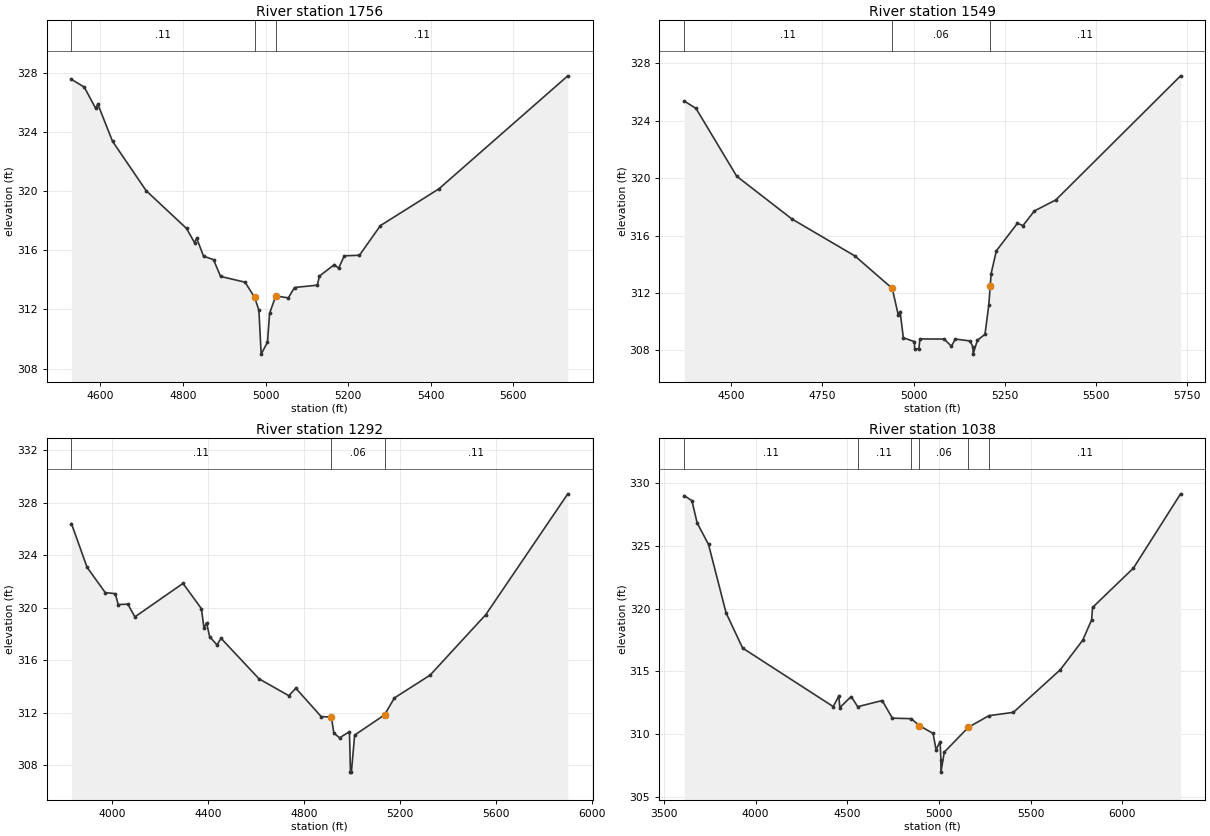
Type RM Length L Ch R = 1 ,1756    ,207,207,207
BEGIN DESCRIPTION:
WFSJR 037 3.0
END DESCRIPTION:
XS GIS Cut Line= 3
      3778567.88     10263711.08      3778112.39     10263594.39
      3777390.07     10263716.68
#Sta/Elev= 30
  4529.8  327.54  4560.8  327.02  4588.4  325.58  4593.6  325.87  4629.2  323.36
  4710.8  320.02  4808.6  317.47    4828  316.51  4833.2  316.81  4849.8   315.6
    4874  315.36  4891.1  314.23  4950.4  313.84  4973.7  312.81    4984  311.94
  4989.5  308.98  5004.8  309.79  5009.9  311.74  5024.9  312.91  5055.3  312.78
  5070.3  313.48  5125.6  313.64  5130.6  314.25  5166.9  315.03    5177  314.78
    5191  315.62  5227.7  315.66  5278.4  317.66  5420.4  320.15  5732.6  327.78
#Mann= 3 , 0 , 0
  4529.8     .11       0  4973.7     .06       0  5024.9     .11       0
Bank Sta=4973.7,5024.9
XS Rating Curve= 0 ,0
Exp/Cntr=0.3,0.1

Type RM Length L Ch R = 1 ,1549    ,257,257,257
BEGIN DESCRIPTION:
WFSJR 037 2.0
END DESCRIPTION:
XS GIS Cut Line= 3
      3778709.51     10263497.95      3777910.31     10263357.31
      3777383.07     10263511.84
#Sta/Elev= 30
  4371.2  325.38  4403.3  324.87    4515  320.14  4666.4  317.16  4839.3  314.58
  4941.5  312.32  4957.9  310.48    4963  310.71  4971.9  308.88  5002.4  308.61
  5002.9  308.11  5014.6  308.11  5017.2   308.8  5083.6  308.79  5103.9  308.29
  5114.1  308.79  5154.7  308.66  5162.9  308.24  5163.1  307.74    5175  308.71
  5195.7  309.12  5206.1  311.14    5210 312.472  5212.6  313.36  5226.9  314.94
  5284.6  316.86  5299.9   316.7  5331.1  317.72    5390  318.49  5732.1  327.14
#Mann= 3 , 0 , 0
  4371.2     .11       0  4941.5     .06       0    5210     .11       0
Bank Sta=4941.5,5210
XS Rating Curve= 0 ,0
Exp/Cntr=0.3,0.1

Type RM Length L Ch R = 1 ,1292    ,254,254,254
BEGIN DESCRIPTION:
Mapping XS 2bee197c
END DESCRIPTION:
XS GIS Cut Line= 3
      3779167.81     10263588.22      3778060.17     10263122.94
       3777216.4     10263338.22
#Sta/Elev= 30
  3828.8   326.4  3893.8  323.08  3969.8  321.15  4011.4  321.07    4024  320.24
  4064.3  320.27  4093.5   319.3  4294.4  321.85  4371.1  319.93    4382  318.45
  4392.8  318.85  4405.7  317.79  4436.2  317.17  4453.2  317.67  4612.1  314.58
  4736.3   313.3  4765.4  313.87  4871.3  311.71 4913.83  311.67  4924.3  310.46
    4948  310.09  4989.3  310.56  4993.5  307.48  4997.5  307.48    5011   310.3
  5135.8  311.84  5177.1  313.13  5326.4  314.87  5558.9  319.48    5901  328.67
#Mann= 3 ,-1 , 0
  3828.8     .11       0 4913.83     .06       0  5135.8     .11       0
Bank Sta=4913.83,5135.8
XS Rating Curve= 0 ,0
Exp/Cntr=0.3,0.1

Type RM Length L Ch R = 1 ,1038    ,0,0,0
BEGIN DESCRIPTION:
WFSJR 037 1.0
END DESCRIPTION:
XS GIS Cut Line= 3
      3779438.67     10263515.32      3778129.61     10262879.89
      3776907.39     10263150.72
#Sta/Elev= 30
  3611.2  328.98  3653.1  328.57  3681.3  326.81  3743.4   325.1  3839.2  319.66
  3929.5  316.86  4423.6  312.21  4454.1  313.05  4459.6  312.13  4521.8  313.01
    4557   312.2  4690.8  312.69  4745.9  311.29  4848.8  311.25  4893.9  310.69
  4968.2  310.08  4984.2  308.79  5006.8  309.42  5010.7  307.98    5011     307
  5029.3  308.59  5160.3  310.56    5273  311.49  5406.1  311.75  5662.2  315.14
  5784.1  317.48  5832.8   319.1    5838  320.09  6061.1  323.22  6318.2  329.12
#Mann= 6 ,-1 , 0
  3611.2     .11       0    4557     .11       0  4848.8     .11       0
  4893.9     .06       0  5160.3     .11       0    5273     .11       0
Bank Sta=4893.9,5160.3
XS Rating Curve= 0 ,0
Exp/Cntr=0.3,0.1

Chan Stop Cuts=-1
Use User Specified Reach Order=0
Composite Channel Slope=5