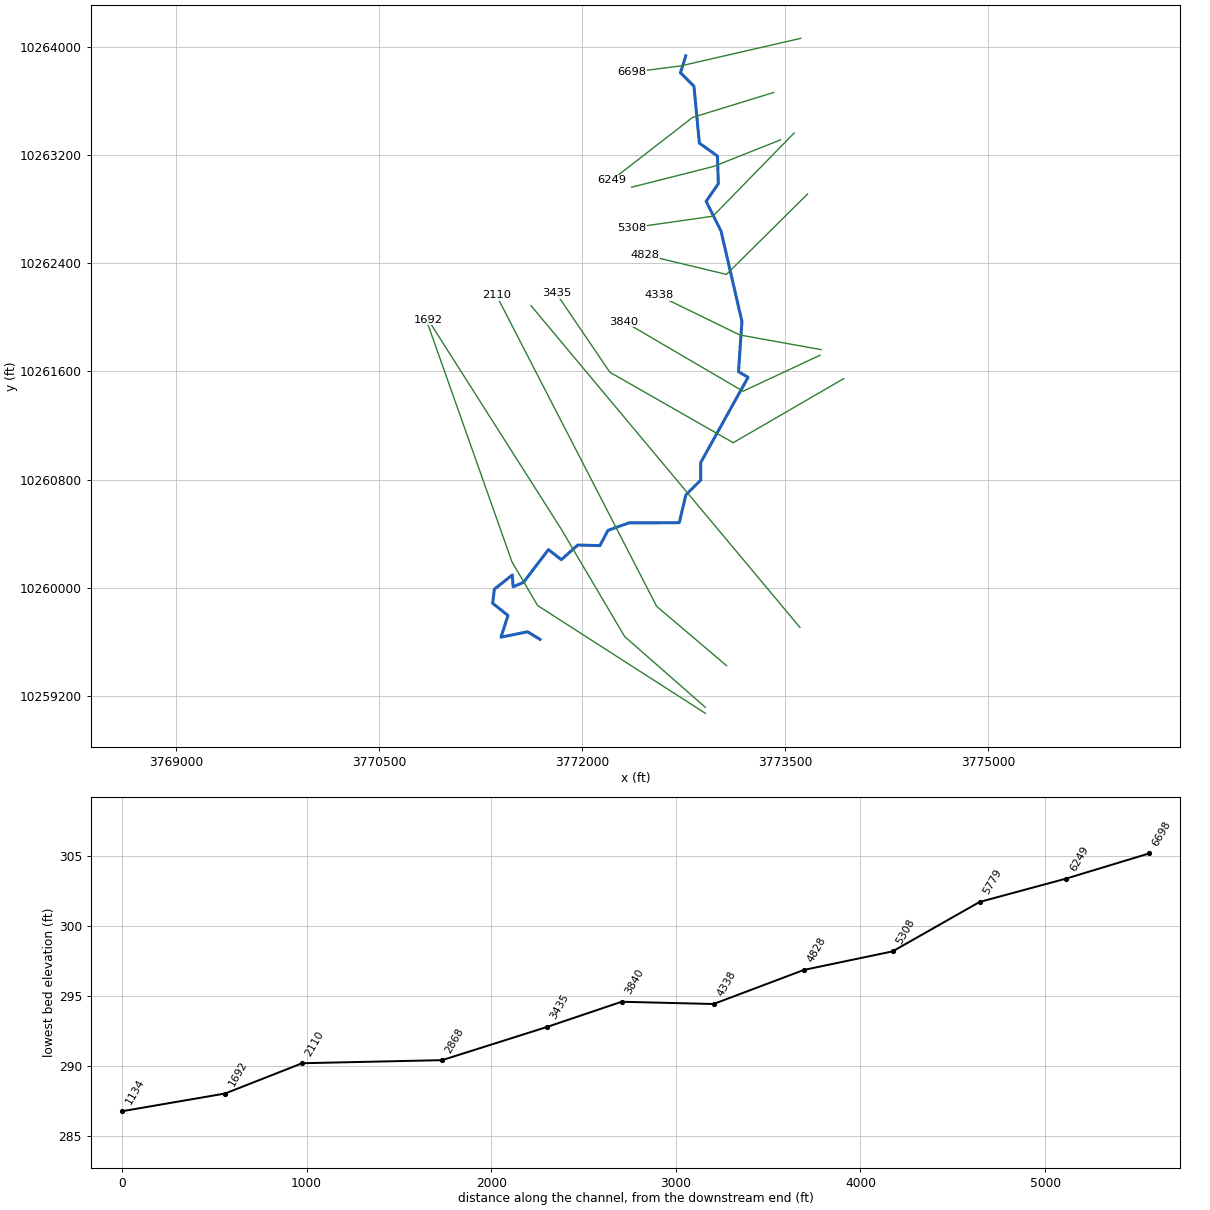
--- WFSJR 038.prj (project) ---

Proj Title=WFSJR 038 Base Level Engineering
Current Plan=p01
Default Exp/Contr=0.3,0.1
English Units
Geom File=g01
Flow File=f01
Plan File=p01
Y Axis Title=Elevation
X Axis Title(PF)=Main Channel Distance
X Axis Title(XS)=Station
BEGIN DESCRIPTION:
WFSJR 038
END DESCRIPTION:
DSS Export Rating Curves= 0
DSS Export Rating Curve Sorted= 0
DSS Export Volume Flow Curves= 0
DXF OffsetX= 0
DXF OffsetY= 0
DXF ScaleX= 1
DXF ScaleY= 10

--- WFSJR 038.p01 (plan) ---

Plan Title=Multiple Run
Program Version=4.10
Short Identifier=Multiple
Geom File=g01
Flow File=f01
Subcritical Flow
K Sum by GR= 0
Std Step Tol= 0.01
Critical Tol= 0.01
Num of Std Step Trials= 20
Max Error Tol= 0.3
Flow Tol Ratio= 0.001
Split Flow NTrial= 30
Split Flow Tol= 0.02
Split Flow Ratio= 0.02
Log Output Level= 0
Friction Slope Method= 1
Unsteady Friction Slope Method= 2
Unsteady Bridges Friction Slope Method= 1
Parabolic Critical Depth
Global Vel Dist= 1 , 1 , 1
Global Log Level= 0
CheckData=True
Encroach Param=-1 ,0,0, 0
BEGIN DESCRIPTION:
Multiple Run
END DESCRIPTION:
Computation Interval=1HOUR
Output Interval=1HOUR
Run HTab= 0
Run UNet= 0
Run PostProcess= 0
Run WQNet= 0
UNET Theta= 1
UNET Theta Warmup= 1
UNET ZTol= 0.02
UNET ZSATol= 0.05
UNET MxIter= 20
UNET MaxInSteps= 0
UNET DtIC= 0
UNET DtMin= 0
UNET MaxCRTS= 20
UNET WFStab= 2
UNET SFStab= 1
UNET WFX= 1
UNET SFX= 1
UNET DSS MLevel= 4
UNET DZMax Abort= 100
UNET Convert EG Bridges= 0
UNET Use Existing IB Tables=-1
UNET Froude Reduction=False
UNET Froude Limit= 1
UNET Froude Power= 10
UNET Time Slicing=0,0, 5
UNET Junction Losses=0
Instantaneous Interval=1HOUR
Write IC File= 0
Write IC File at Sim End=0
Echo Input=False
Echo Parameters=False
Echo Output=False
Write Detailed= 0
WQ AD Non Conservative
WQ ULTIMATE=-1
WQ Max Comp Step=1HOUR
WQ Output Interval=15MIN
WQ Output Selected Increments= 0
WQ Output face flow=0
WQ Output face velocity=0
WQ Output face area=0
WQ Output face dispersion=0
WQ Output cell volume=0
WQ Output cell surface area=0
WQ Output cell continuity=0
WQ Output cumulative cell continuity=0
WQ Output face conc=0
WQ Output face dconc_dx=0
WQ Output face courant=0
WQ Output face peclet=0
WQ Output face adv mass=0
WQ Output face disp mass=0
WQ Output cell mass=0
WQ Output cell source sink temp=0
WQ Output cell source sink nsm=0
WQ Output MaxMinRange=-1
WQ Daily Max Min Mean=-1
WQ Daily Range=0
WQ Daily Time=0
WQ Create Restart=0
WQ Fixed Restart=0
WQ System Summary=0
WQ Use Fixed Temperature=0
Sorting and Armoring Iterations= 10
XS Update Threshold= 0.02
Hydraulics Update Threshold= 0.02
Energy Slope Method= 1
Volume Change Method= 0
XS Weighting Method= 0
Number of US Weighted Cross Sections= 1
Number of DS Weighted Cross Sections= 1
Upstream XS Weight=0.25
Main XS Weight=0.5
Downstream XS Weight=0.25
Number of DS XS's Weighted with US Boundary= 1
Upstream Boundary Weight= 1
Weight of XSs Associated with US Boundary= 0
Number of US XS's Weighted with DS Boundary= 1
Downstream Boundary Weight= 0.5
Weight of XSs Associated with DS Boundary= 0.5
Sediment Output Level= 4
Mass or Volume Output= 0
Output Increment Type= 1
Profile and TS Output Increment= 10
XS Output Flag= 0
XS Output Increment= 10
Disregard all LS=0
Disregard all Conn=0
Disregard all Breaches=0
Disregard all Pumps=0

--- WFSJR 038.f01 (steady flow) ---

Flow Title=Multiple
Program Version=4.10
Number of Profiles= 7
Profile Names=10-year,25-year,50-year,1pct_min,100-year,1pct_plu,500-year
River Rch & RM=WFSJR 038,Reach-1         ,6698
     496     662     886     390    1179    3561    2160
River Rch & RM=WFSJR 038,Reach-1         ,6249
     643     863    1159     512    1546    4669    2843
Boundary for River Rch & Prof#=WFSJR 038,Reach-1         , 1
Up Type= 0
Dn Type= 3
Dn Slope=0.006
Boundary for River Rch & Prof#=WFSJR 038,Reach-1         , 2
Up Type= 0
Dn Type= 3
Dn Slope=0.006
Boundary for River Rch & Prof#=WFSJR 038,Reach-1         , 3
Up Type= 0
Dn Type= 3
Dn Slope=0.006
Boundary for River Rch & Prof#=WFSJR 038,Reach-1         , 4
Up Type= 0
Dn Type= 3
Dn Slope=0.006
Boundary for River Rch & Prof#=WFSJR 038,Reach-1         , 5
Up Type= 0
Dn Type= 3
Dn Slope=0.006
Boundary for River Rch & Prof#=WFSJR 038,Reach-1         , 6
Up Type= 0
Dn Type= 3
Dn Slope=0.006
Boundary for River Rch & Prof#=WFSJR 038,Reach-1         , 7
Up Type= 0
Dn Type= 3
Dn Slope=0.006
DSS Import GetInterval= 0
DSS Import GetPeak= 0
DSS Import FillOption= 0

--- WFSJR 038.g01 (geometry) ---

Geom Title=Existing Conditions
Program Version=4.10

River Reach=WFSJR 038       ,Reach-1
Reach XY= 30
      3772768.23     10263931.84      3772728.23     10263806.84
      3772828.23     10263706.84      3772868.23     10263286.84
       3773001.9     10263191.16      3773008.23     10262986.84
      3772918.23     10262856.84      3773028.23     10262636.84
      3773182.63     10261969.86      3773157.52     10261597.55
      3773228.23     10261556.84      3772878.23     10260926.84
      3772878.23     10260796.84      3772768.23     10260686.84
      3772719.68     10260482.27      3772347.15     10260480.74
      3772192.95     10260425.78       3772133.4      10260312.8
      3771970.04     10260317.38       3771847.9     10260208.98
      3771753.24     10260283.79       3771568.5     10260041.03
      3771492.16     10260008.97      3771486.05       10260096.
      3771353.22     10259990.65      3771341.01     10259886.83
      3771453.99     10259796.75      3771402.08     10259636.44
      3771599.03     10259676.14      3771691.47     10259619.85

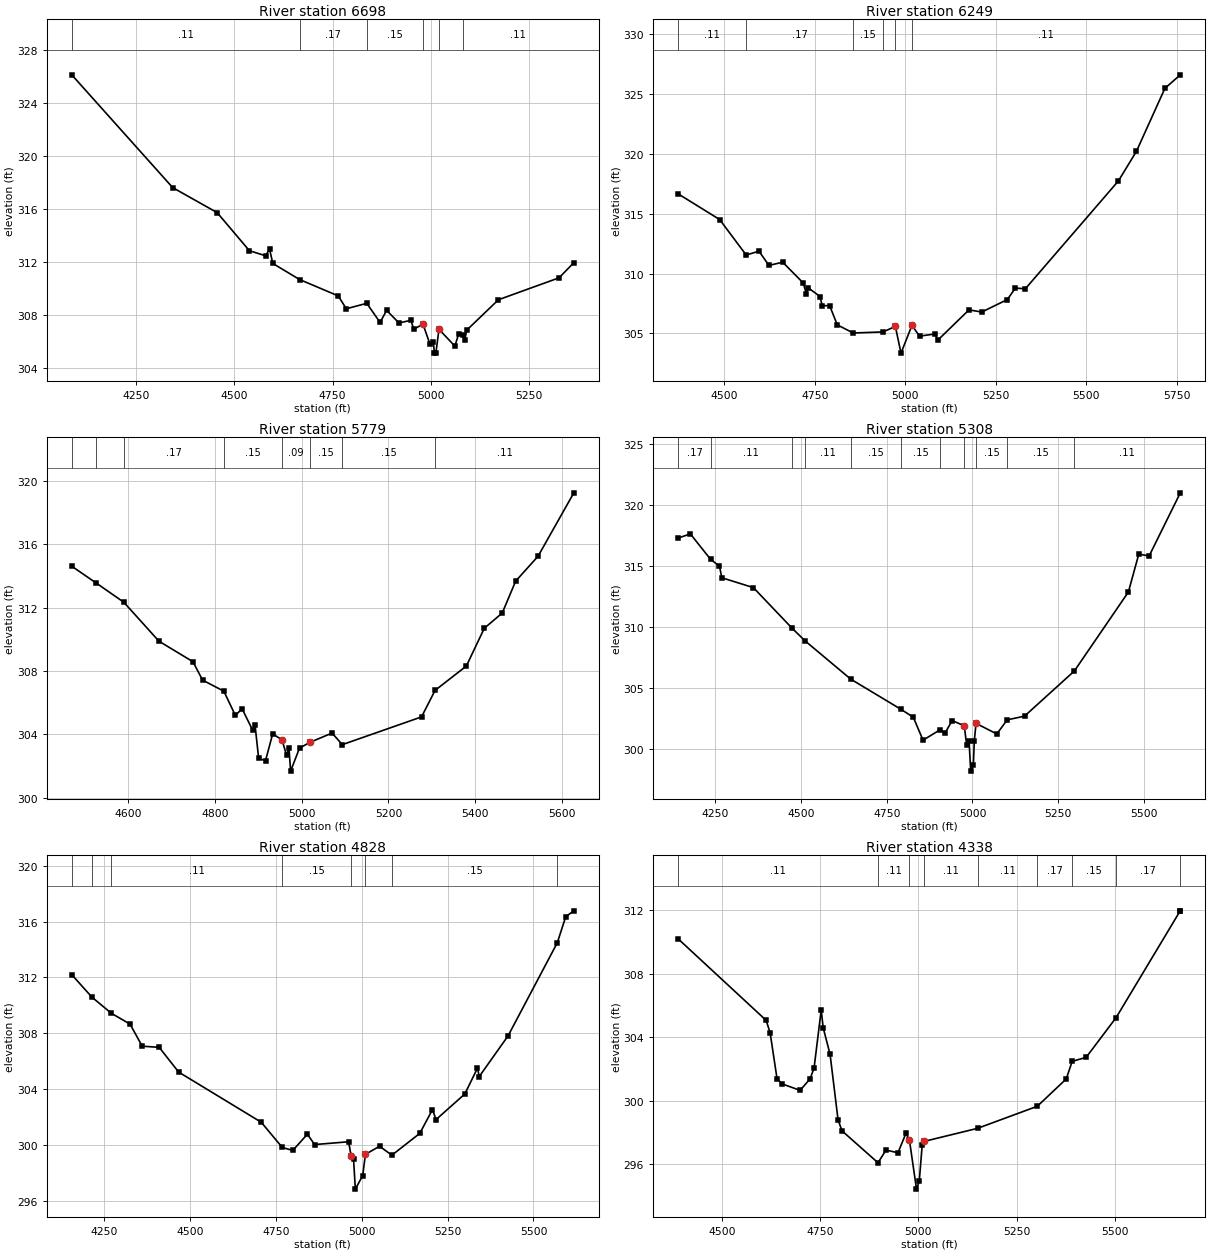
Type RM Length L Ch R = 1 ,6698    ,449,449,449
BEGIN DESCRIPTION:
WFSJR 038 7.0
END DESCRIPTION:
XS GIS Cut Line= 3
      3773617.89     10264061.08      3772728.23     10263856.84
      3772367.83     10263811.07
#Sta/Elev= 30
  4087.2   326.1  4343.7  317.61  4456.6  315.73  4538.7  312.86  4579.7  312.48
    4590  312.97  4598.2   311.9  4666.2  310.69  4764.4  309.46    4785  308.49
    4837   308.9  4870.8  307.46  4887.5  308.37  4918.8  307.42  4949.1  307.62
  4956.5  306.95  4979.9  307.33  4997.6  305.82  5005.8  306.02  5009.1  305.15
  5012.6  305.15  5020.5  306.94  5060.9  305.68  5070.9  306.62    5081  306.52
  5085.8  306.12  5091.1  306.88  5171.7  309.17  5325.8  310.82  5363.3  311.96
#Mann= 6 ,-1 , 0
  4087.2     .11       0  4666.2     .17       0    4837     .15       0
  4979.9     .09       0  5020.5     .15       0    5081     .11       0
Bank Sta=4979.9,5020.5
XS Rating Curve= 0 ,0
Exp/Cntr=0.3,0.1

Type RM Length L Ch R = 1 ,6249    ,470,470,470
BEGIN DESCRIPTION:
WFSJR 038 6.0
END DESCRIPTION:
XS GIS Cut Line= 3
      3773417.87     10263661.08      3772818.23     10263476.84
      3772217.83     10263011.05
#Sta/Elev= 30
  4372.7  316.65  4487.2  314.51  4560.4  311.55  4595.8  311.87  4623.3  310.68
  4661.3  310.95  4717.9  309.22  4726.7  308.33  4731.9  308.81  4764.7  308.08
  4770.2  307.33  4791.2  307.31  4812.1  305.72  4856.1  305.04  4938.7  305.13
  4972.6  305.59  4988.2  303.36  5018.5  305.68  5039.3  304.78  5082.8  304.96
  5089.1  304.42    5176  306.97  5211.3  306.79  5281.9  307.83  5304.2  308.79
  5331.7  308.73  5588.8  317.73  5638.6   320.2  5717.3  325.46  5759.9  326.59
#Mann= 6 ,-1 , 0
  4372.7     .11       0  4560.4     .17       0  4856.1     .15       0
  4938.7     .11       0  4972.6     .06       0  5018.5     .11       0
Bank Sta=4972.6,5018.5
XS Rating Curve= 0 ,0
Exp/Cntr=0.3,0.1

Type RM Length L Ch R = 1 ,5779    ,471,471,471
BEGIN DESCRIPTION:
WFSJR 038 5.0
END DESCRIPTION:
XS GIS Cut Line= 3
       3773467.9     10263311.09      3772975.85     10263115.21
      3772367.89     10262961.08
#Sta/Elev= 30
  4470.4  314.61  4526.8  313.55  4590.3  312.34  4671.4  309.88  4749.6  308.59
  4771.8  307.43  4820.8  306.73  4847.2  305.21  4862.9  305.62  4887.2  304.27
  4892.6  304.61    4901  302.49  4916.8  302.35  4933.3  304.04  4954.8  303.66
  4965.4  302.68  4970.8  303.16  4974.6  301.69  4995.1  303.14  5018.6   303.5
  5070.2  304.09  5093.7  303.36  5276.3  305.11  5307.4  306.78  5379.6  308.32
  5420.9   310.7  5462.2  311.66  5493.1  313.67  5544.7  315.24  5627.2  319.24
#Mann= 8 ,-1 , 0
  4470.4     .17       0  4526.8     .11       0  4590.3     .17       0
  4820.8     .15       0  4954.8     .09       0  5018.6     .15       0
  5093.7     .15       0  5307.4     .11       0
Bank Sta=4954.8,5018.6
XS Rating Curve= 0 ,0
Exp/Cntr=0.3,0.1

Type RM Length L Ch R = 1 ,5308    ,480,480,480
BEGIN DESCRIPTION:
WFSJR 038 4.0
END DESCRIPTION:
XS GIS Cut Line= 3
      3773567.86     10263361.08      3772968.23     10262746.84
      3772367.83     10262661.07
#Sta/Elev= 30
  4141.6   317.3    4177  317.64    4236  315.55  4261.9  314.99  4268.8  314.04
  4360.9  313.23  4473.7   309.9  4511.7  308.86  4644.9  305.72  4792.2  303.23
  4827.5  302.59  4855.8  300.71  4905.4  301.56  4919.5  301.26  4940.7  302.32
  4976.1  301.89  4983.1  300.32  4990.2  300.64  4994.9  298.17  5002.7  298.67
  5005.4  300.65  5010.5  302.09  5071.1  301.22  5101.4  302.38  5151.9  302.68
  5297.4  306.39    5455  312.87  5485.3  315.98  5515.6  315.83  5606.5  321.01
#Mann= 11 ,-1 , 0
  4141.6     .17       0    4236     .11       0  4473.7     .17       0
  4511.7     .11       0  4644.9     .15       0  4792.2     .15       0
  4905.4     .15       0  4976.1     .09       0  5010.5     .15       0
  5101.4     .15       0  5297.4     .11       0
Bank Sta=4976.1,5010.5
XS Rating Curve= 0 ,0
Exp/Cntr=0.3,0.1

Type RM Length L Ch R = 1 ,4828    ,490,490,490
BEGIN DESCRIPTION:
WFSJR 038 3.0
END DESCRIPTION:
XS GIS Cut Line= 3
      3773667.86     10262911.08      3773068.23     10262316.84
      3772467.81     10262461.08
#Sta/Elev= 30
  4155.8   312.2  4214.5  310.59  4270.9  309.44  4325.5  308.66  4360.9  307.08
  4410.3     307  4466.9  305.23  4707.3  301.64  4768.8  299.83  4799.3  299.62
  4841.7  300.78  4862.9  300.04  4961.9  300.24    4969  299.23  4976.1     299
  4981.4  296.85  5002.8  297.82  5010.7  299.34  5051.8  299.92  5087.7  299.28
    5169  300.84  5205.8  302.54  5216.4  301.83  5300.1  303.66  5336.9  305.51
  5342.1  304.91    5426  307.82  5569.4  314.49  5593.9  316.35  5617.5  316.77
#Mann= 8 ,-1 , 0
  4155.8     .11       0  4214.5     .15       0  4270.9     .11       0
  4768.8     .15       0    4969     .09       0  5010.7     .15       0
  5087.7     .15       0  5569.4     .11       0
Bank Sta=4969,5010.7
XS Rating Curve= 0 ,0
Exp/Cntr=0.3,0.1

Type RM Length L Ch R = 1 ,4338    ,498,498,498
BEGIN DESCRIPTION:
WFSJR 038 2.0
END DESCRIPTION:
XS GIS Cut Line= 3
      3773767.88     10261761.07      3773166.77     10261869.43
      3772567.81     10262161.09
#Sta/Elev= 30
  4389.2  310.18  4612.8  305.05  4622.9  304.27  4640.5  301.37  4653.4  301.05
  4699.2  300.64  4724.6  301.37  4734.7  302.05  4752.8   305.7  4757.9  304.58
  4775.4  302.91  4795.7  298.78  4805.8  298.09  4897.3  296.08  4917.6  296.88
  4948.1  296.71  4968.4  297.94  4977.3   297.5  4995.2  294.42  5002.2  294.92
  5009.8  297.22  5015.3  297.43  5150.6  298.25  5302.5  299.64    5376  301.36
  5391.2  302.47  5426.7  302.72  5503.1  305.23    5666  311.95  5666.2  311.95
#Mann= 9 ,-1 , 0
  4389.2     .11       0  4897.3     .11       0  4977.3     .06       0
  5015.3     .11       0  5150.6     .11       0  5302.5     .17       0
  5391.2     .15       0  5503.1     .17       0    5666     .11       0
Bank Sta=4977.3,5015.3
XS Rating Curve= 0 ,0
Exp/Cntr=0.3,0.1

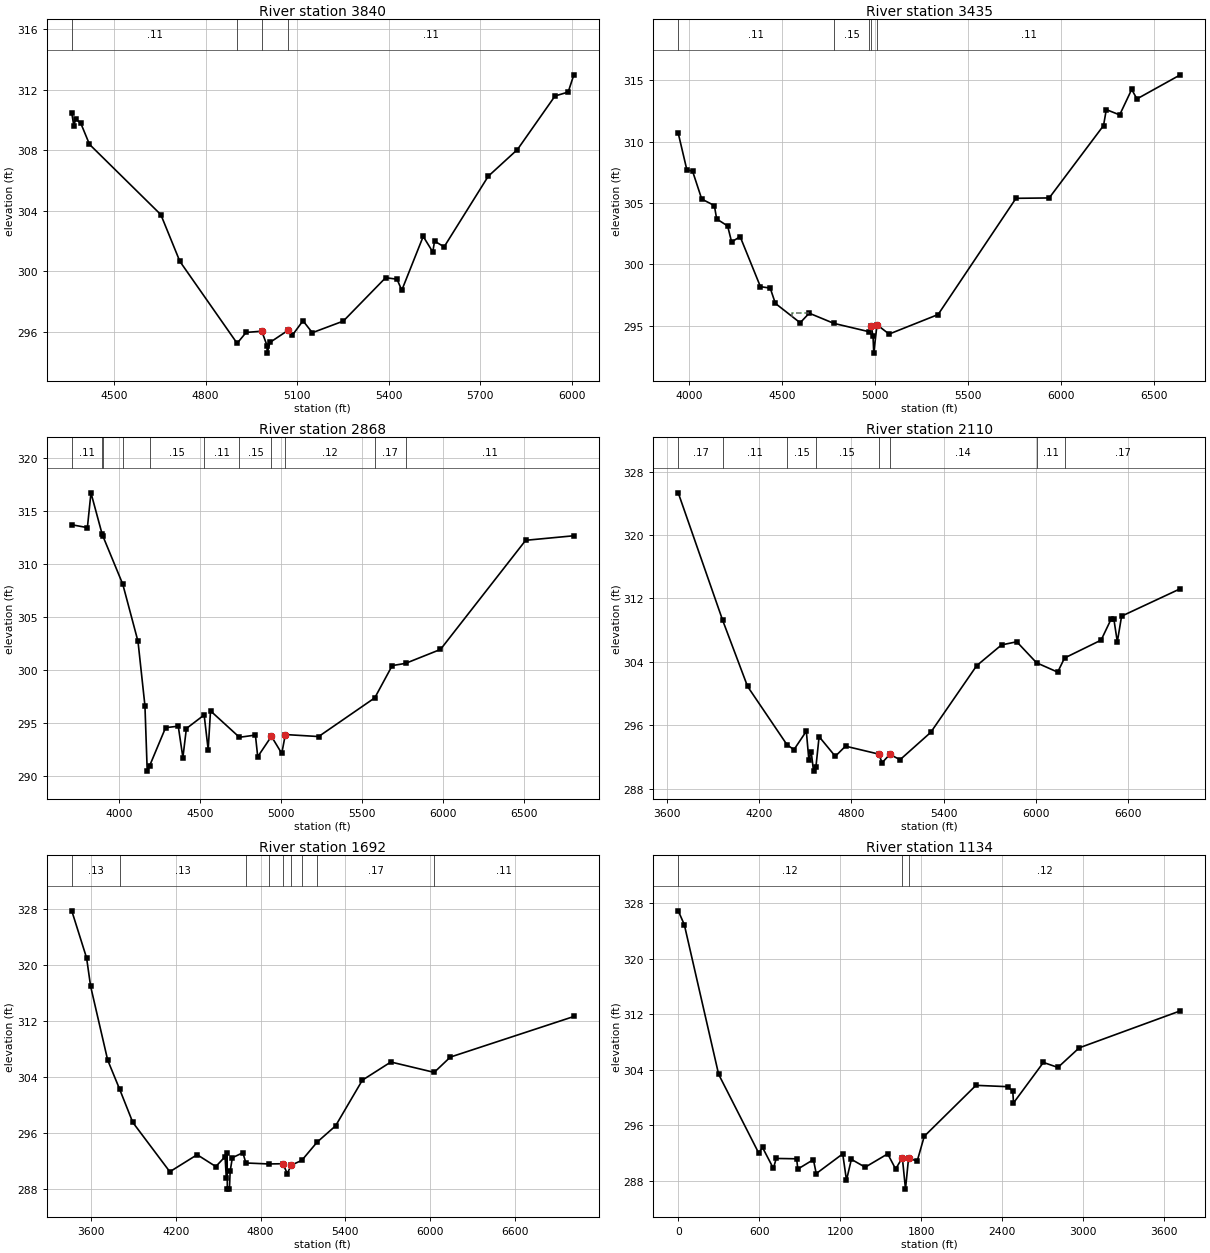
Type RM Length L Ch R = 1 ,3840    ,405,405,405
BEGIN DESCRIPTION:
Mapping XS 313f891f
END DESCRIPTION:
XS GIS Cut Line= 3
      3773758.77     10261719.16      3773191.02     10261453.52
      3772311.79     10261968.57
#Sta/Elev= 30
  4361.4  310.47  4368.3  309.58  4373.8  310.08  4391.1  309.78  4419.5  308.39
  4653.4  303.74  4715.7  300.65  4903.4  295.23    4933  295.95  4984.2  296.03
  5001.5  295.08  5001.7  294.58  5011.2  295.29  5069.8  296.08  5084.6  295.77
  5119.4  296.72  5149.9  295.93  5251.6   296.7  5390.3  299.57  5427.5  299.47
  5443.2  298.74  5513.4   302.3  5544.8  301.27  5550.6  301.99    5582  301.61
  5726.6  306.28  5822.4  308.05  5945.5  311.59  5988.6  311.85  6007.2  312.99
#Mann= 4 ,-1 , 0
  4361.4     .11       0  4903.4     .11       0  4984.2     .06       0
  5069.8     .11       0
Bank Sta=4984.2,5069.8
XS Rating Curve= 0 ,0
Exp/Cntr=0.3,0.1

Type RM Length L Ch R = 1 ,3435    ,567,567,567
BEGIN DESCRIPTION:
Mapping XS e6452b33
END DESCRIPTION:
XS GIS Cut Line= 4
      3773935.83     10261547.28      3773118.11     10261073.31
      3772206.65     10261594.14      3771810.81     10262177.48
#Sta/Elev= 30
  3942.4  310.68  3988.4  307.72  4019.9  307.57  4068.7  305.32  4136.6  304.79
  4149.1   303.7  4207.9  303.13  4229.4  301.83  4275.3  302.26  4384.3  298.19
  4437.1  298.07  4464.6  296.83    4598  295.25  4646.8  296.03  4779.6   295.2
  4969.2  294.52    4980     295  4989.8  294.15  4993.8  292.78  5011.4  295.09
  5076.2  294.33  5339.7  295.92  5758.6  305.38  5937.3  305.41  6229.4   311.3
  6244.3   312.6  6316.2  312.17  6380.8  314.24  6409.1  313.47  6642.3  315.43
#Mann= 5 ,-1 , 0
  3942.4     .11       0  4779.6     .15       0  4969.2     .11       0
    4980     .06       0  5011.4     .11       0
#XS Ineff= 1 ,-1
    4555  4646.8  296.03
Permanent Ineff=
       F
Bank Sta=4980,5011.4
XS Rating Curve= 0 ,0
Exp/Cntr=0.3,0.1

Type RM Length L Ch R = 1 ,2868    ,758,758,758
BEGIN DESCRIPTION:
Mapping XS 7bf76a0f
END DESCRIPTION:
XS GIS Cut Line= 2
      3773611.46     10259708.21      3771623.86     10262086.38
#Sta/Elev= 30
  3706.6  313.72    3803  313.45  3825.1  316.74  3893.7  312.85  3897.6  312.69
  4021.6  308.09  4115.4  302.69  4158.3   296.6  4172.4  290.42  4187.2  290.92
  4285.8  294.53  4363.9  294.67  4392.6   291.7  4414.1  294.45  4523.8  295.73
  4548.7  292.45    4563  296.12  4741.6  293.62  4840.2  293.83  4854.5  291.78
  4939.1  293.71  5002.9  292.09    5025  293.88  5230.6  293.69  5577.1  297.35
  5684.8   300.4  5766.8  300.61  5982.8  301.93  6508.6  312.25    6806  312.68
#Mann= 11 ,-1 , 0
  3706.6     .11       0  3893.7     .17       0  3897.6     .11       0
  4021.6     .15       0  4187.2     .15       0  4523.8     .11       0
  4741.6     .15       0  4939.1     .08       0    5025     .12       0
  5577.1     .17       0  5766.8     .11       0
#XS Ineff= 1 ,-1
    4140    4563  296.12
Permanent Ineff=
       F
Bank Sta=4939.1,5025
XS Rating Curve= 0 ,0
Exp/Cntr=0.3,0.1

Type RM Length L Ch R = 1 ,2110    ,418,418,418
BEGIN DESCRIPTION:
Mapping XS b03f727d
END DESCRIPTION:
XS GIS Cut Line= 3
       3773068.9     10259426.11      3772552.42     10259864.47
      3771367.53      10262164.8
#Sta/Elev= 30
  3673.8  325.31  3962.5  309.24  4124.8  300.88  4380.4  293.55  4426.2   292.9
  4506.8  295.24  4523.4  291.59  4538.6  292.63  4553.7   290.2    4569   290.7
  4589.9  294.55  4695.1  292.07  4761.6  293.35  4977.3  292.35  4999.8  291.27
  5049.8  292.31  5116.3  291.64  5315.8  295.09  5614.9  303.51    5776  306.12
  5875.3  306.52  6003.9  303.87  6141.3  302.69  6185.9  304.47  6423.8  306.73
  6490.4  309.44  6506.9  309.35  6529.1  306.51  6556.9  309.75  6938.8  313.21
#Mann= 8 ,-1 , 0
  3673.8     .17       0  3962.5     .11       0  4380.4     .15       0
    4569     .15       0  4977.3     .08       0  5049.8     .14       0
  6003.9     .11       0  6185.9     .17       0
#XS Ineff= 2 ,-1
    4284  4506.8  295.24    4508  4589.9  294.55
Permanent Ineff=
       F       F
Bank Sta=4977.3,5049.8
XS Rating Curve= 0 ,0
Exp/Cntr=0.3,0.1

Type RM Length L Ch R = 1 ,1692    ,558,558,558
BEGIN DESCRIPTION:
WFSJR 038 1.0
END DESCRIPTION:
XS GIS Cut Line= 4
      3772912.67     10259117.93      3772316.22     10259641.04
      3771840.27     10260446.78      3770864.06     10261982.51
#Sta/Elev= 30
  3465.6  327.73  3570.4  321.01  3598.8  316.97  3719.3  306.45  3804.5  302.26
  3896.8  297.56  4158.7  290.52  4351.9  292.95  4483.7  291.26  4549.3  292.67
  4557.8  289.67  4563.6  293.15  4565.2  288.04    4580  288.04  4585.1  290.59
  4600.7  292.52  4674.9  293.23  4696.3  291.77  4856.3  291.63  4957.7  291.66
    4989  290.26  5016.2  291.45  5091.4  292.14  5200.3  294.75  5330.2  297.06
  5519.7  303.58  5721.2  306.17  6027.5  304.69  6141.3  306.87  7014.5  312.66
#Mann= 9 ,-1 , 0
  3465.6     .13       0  3804.5     .13       0  4696.3     .12       0
  4856.3     .12       0  4957.7     .08       0  5016.2     .12       0
  5091.4     .12       0  5200.3     .17       0  6027.5     .11       0
#XS Ineff= 1 ,-1
    4025  4674.9  293.23
Permanent Ineff=
       T
Bank Sta=4957.7,5016.2
XS Rating Curve= 0 ,0
Exp/Cntr=0.3,0.1

Type RM Length L Ch R = 1 ,1134    ,0,0,0
XS GIS Cut Line= 4
      3772913.25      10259073.4      3771673.22     10259870.02
      3771483.56      10260193.2      3770858.56     10261958.82
#Sta/Elev= 30
       0  326.87      45  324.88   299.3  303.32   595.9  291.99   624.5  292.78
   704.9  289.77     726   291.2   877.3  291.15     886  289.67  1001.4  291.03
  1022.6  289.02  1218.8  291.86  1246.5  288.06  1282.8  291.07  1385.2  289.94
    1552  291.86  1610.7  289.68  1660.6   291.3  1683.8  286.78  1706.4  291.21
  1770.8  290.84  1822.9  294.39    2206  301.73  2440.4  301.54  2478.8  300.91
  2484.1  299.19  2705.6  305.03  2813.3  304.31  2970.8  307.13  3720.1  312.46
#Mann= 3 , 0 , 0
       0     .12       0  1660.6     .07       0  1706.4     .12       0
Bank Sta=1660.6,1706.4
XS Rating Curve= 0 ,0
Exp/Cntr=0.3,0.1

Chan Stop Cuts=-1
Use User Specified Reach Order=0
Composite Channel Slope=5