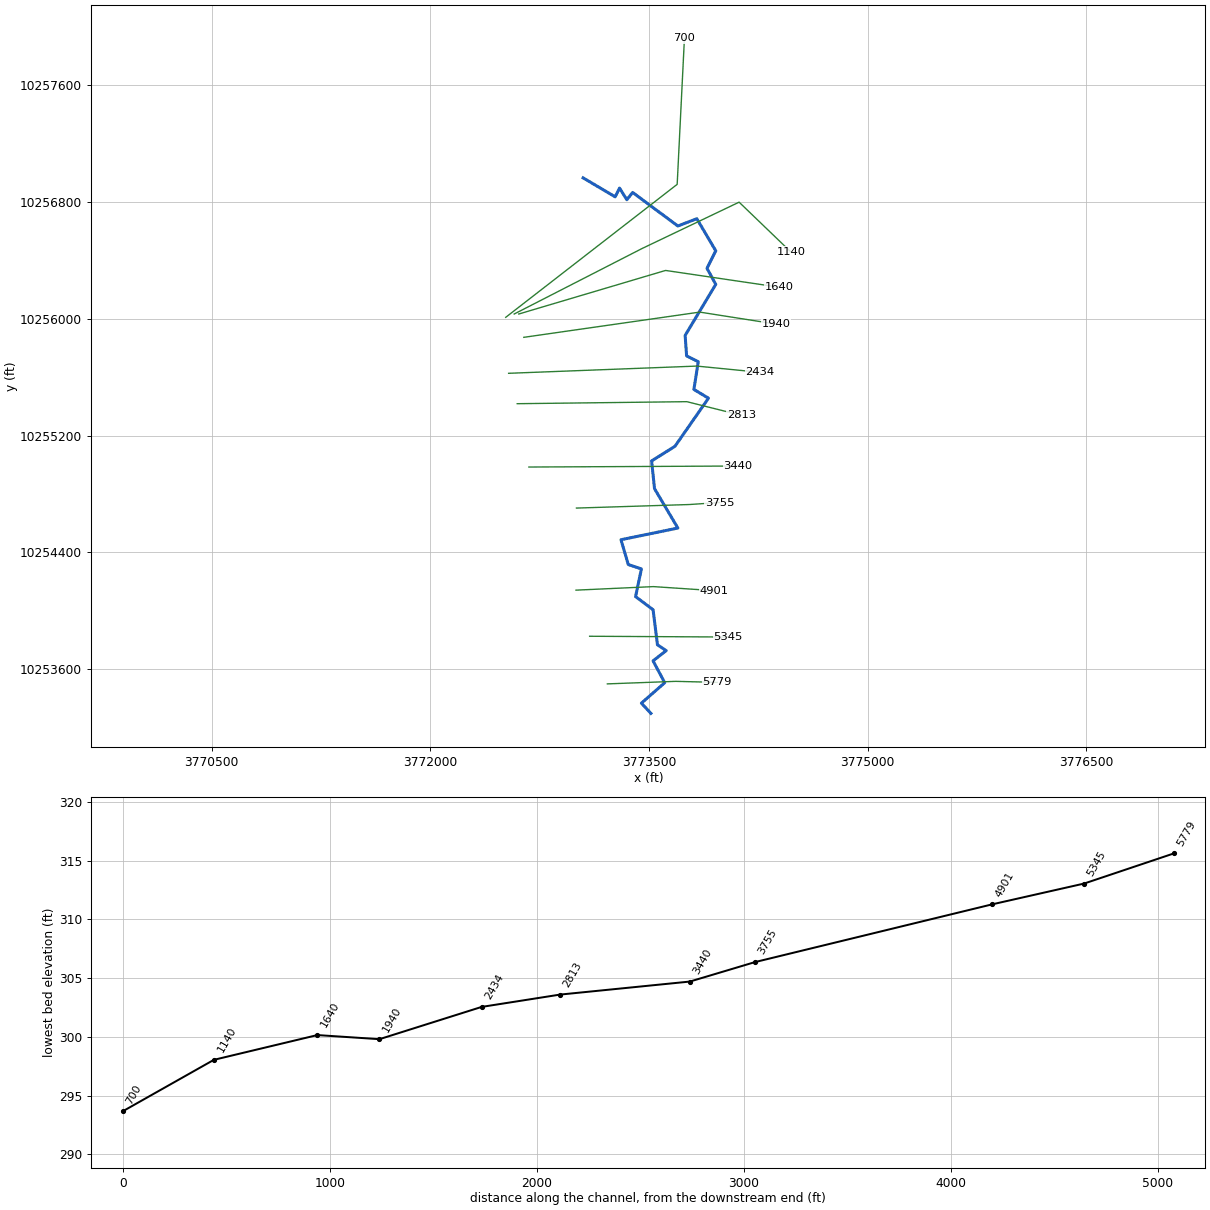
--- WFSJR 039.prj (project) ---

Proj Title=WFSJR 039 Base Level Engineering
Current Plan=p01
Default Exp/Contr=0.3,0.1
English Units
Geom File=g01
Flow File=f01
Plan File=p01
Y Axis Title=Elevation
X Axis Title(PF)=Main Channel Distance
X Axis Title(XS)=Station
BEGIN DESCRIPTION:
WFSJR 039
END DESCRIPTION:
DSS Export Rating Curves= 0
DSS Export Rating Curve Sorted= 0
DSS Export Volume Flow Curves= 0
DXF OffsetX= 0
DXF OffsetY= 0
DXF ScaleX= 1
DXF ScaleY= 10

--- WFSJR 039.p01 (plan) ---

Plan Title=Multiple Run
Program Version=4.10
Short Identifier=Multiple
Geom File=g01
Flow File=f01
Subcritical Flow
K Sum by GR= 0
Std Step Tol= 0.01
Critical Tol= 0.01
Num of Std Step Trials= 20
Max Error Tol= 0.3
Flow Tol Ratio= 0.001
Split Flow NTrial= 30
Split Flow Tol= 0.02
Split Flow Ratio= 0.02
Log Output Level= 0
Friction Slope Method= 1
Unsteady Friction Slope Method= 2
Unsteady Bridges Friction Slope Method= 1
Parabolic Critical Depth
Global Vel Dist= 1 , 1 , 1
Global Log Level= 0
CheckData=True
Encroach Param=-1 ,0,0, 0
BEGIN DESCRIPTION:
Multiple Run
END DESCRIPTION:
Computation Interval=1HOUR
Output Interval=1HOUR
Run HTab= 0
Run UNet= 0
Run PostProcess= 0
Run WQNet= 0
UNET Theta= 1
UNET Theta Warmup= 1
UNET ZTol= 0.02
UNET ZSATol= 0.05
UNET MxIter= 20
UNET MaxInSteps= 0
UNET DtIC= 0
UNET DtMin= 0
UNET MaxCRTS= 20
UNET WFStab= 2
UNET SFStab= 1
UNET WFX= 1
UNET SFX= 1
UNET DSS MLevel= 4
UNET DZMax Abort= 100
UNET Convert EG Bridges= 0
UNET Use Existing IB Tables=-1
UNET Froude Reduction=False
UNET Froude Limit= 1
UNET Froude Power= 10
UNET Time Slicing=0,0, 5
UNET Junction Losses=0
Instantaneous Interval=1HOUR
Write IC File= 0
Write IC File at Sim End=0
Echo Input=False
Echo Parameters=False
Echo Output=False
Write Detailed= 0
WQ AD Non Conservative
WQ ULTIMATE=-1
WQ Max Comp Step=1HOUR
WQ Output Interval=15MIN
WQ Output Selected Increments= 0
WQ Output face flow=0
WQ Output face velocity=0
WQ Output face area=0
WQ Output face dispersion=0
WQ Output cell volume=0
WQ Output cell surface area=0
WQ Output cell continuity=0
WQ Output cumulative cell continuity=0
WQ Output face conc=0
WQ Output face dconc_dx=0
WQ Output face courant=0
WQ Output face peclet=0
WQ Output face adv mass=0
WQ Output face disp mass=0
WQ Output cell mass=0
WQ Output cell source sink temp=0
WQ Output cell source sink nsm=0
WQ Output MaxMinRange=-1
WQ Daily Max Min Mean=-1
WQ Daily Range=0
WQ Daily Time=0
WQ Create Restart=0
WQ Fixed Restart=0
WQ System Summary=0
WQ Use Fixed Temperature=0
Sorting and Armoring Iterations= 10
XS Update Threshold= 0.02
Hydraulics Update Threshold= 0.02
Energy Slope Method= 1
Volume Change Method= 0
XS Weighting Method= 0
Number of US Weighted Cross Sections= 1
Number of DS Weighted Cross Sections= 1
Upstream XS Weight=0.25
Main XS Weight=0.5
Downstream XS Weight=0.25
Number of DS XS's Weighted with US Boundary= 1
Upstream Boundary Weight= 1
Weight of XSs Associated with US Boundary= 0
Number of US XS's Weighted with DS Boundary= 1
Downstream Boundary Weight= 0.5
Weight of XSs Associated with DS Boundary= 0.5
Sediment Output Level= 4
Mass or Volume Output= 0
Output Increment Type= 1
Profile and TS Output Increment= 10
XS Output Flag= 0
XS Output Increment= 10
Disregard all LS=0
Disregard all Conn=0
Disregard all Breaches=0
Disregard all Pumps=0

--- WFSJR 039.f01 (steady flow) ---

Flow Title=Multiple
Program Version=4.10
Number of Profiles= 7
Profile Names=10-year,25-year,50-year,1pct_min,100-year,1pct_plu,500-year
River Rch & RM=WFSJR 039,Reach-1         ,5779
     607     815    1096     485    1464    4421    2697
Boundary for River Rch & Prof#=WFSJR 039,Reach-1         , 1
Up Type= 0
Dn Type= 3
Dn Slope=0.004
Boundary for River Rch & Prof#=WFSJR 039,Reach-1         , 2
Up Type= 0
Dn Type= 3
Dn Slope=0.004
Boundary for River Rch & Prof#=WFSJR 039,Reach-1         , 3
Up Type= 0
Dn Type= 3
Dn Slope=0.004
Boundary for River Rch & Prof#=WFSJR 039,Reach-1         , 4
Up Type= 0
Dn Type= 3
Dn Slope=0.004
Boundary for River Rch & Prof#=WFSJR 039,Reach-1         , 5
Up Type= 0
Dn Type= 3
Dn Slope=0.004
Boundary for River Rch & Prof#=WFSJR 039,Reach-1         , 6
Up Type= 0
Dn Type= 3
Dn Slope=0.004
Boundary for River Rch & Prof#=WFSJR 039,Reach-1         , 7
Up Type= 0
Dn Type= 3
Dn Slope=0.004
DSS Import GetInterval= 0
DSS Import GetPeak= 0
DSS Import FillOption= 0

--- WFSJR 039.g01 (geometry) ---

Geom Title=Existing Conditions
Program Version=4.10

River Reach=WFSJR 039       ,Reach-1
Reach XY= 30
      3773513.23     10253296.84      3773448.23     10253366.84
      3773608.23     10253506.84      3773528.23     10253656.84
      3773618.23     10253726.84      3773558.23     10253766.84
      3773528.23     10254006.84      3773408.23     10254096.84
      3773448.23     10254286.84      3773358.23     10254316.84
      3773308.23     10254486.84      3773698.23     10254566.84
      3773538.23     10254836.84      3773518.23     10255026.84
      3773678.23     10255126.84      3773908.23     10255456.84
      3773808.23     10255516.84      3773838.23     10255706.84
      3773758.23     10255746.84      3773748.23     10255886.84
      3773958.23     10256236.84      3773898.23     10256346.84
      3773958.23     10256466.84      3773828.23     10256686.84
      3773698.23     10256636.84      3773388.23     10256866.84
      3773348.23     10256816.84      3773298.23     10256896.84
      3773268.23     10256836.84      3773048.23     10256966.84

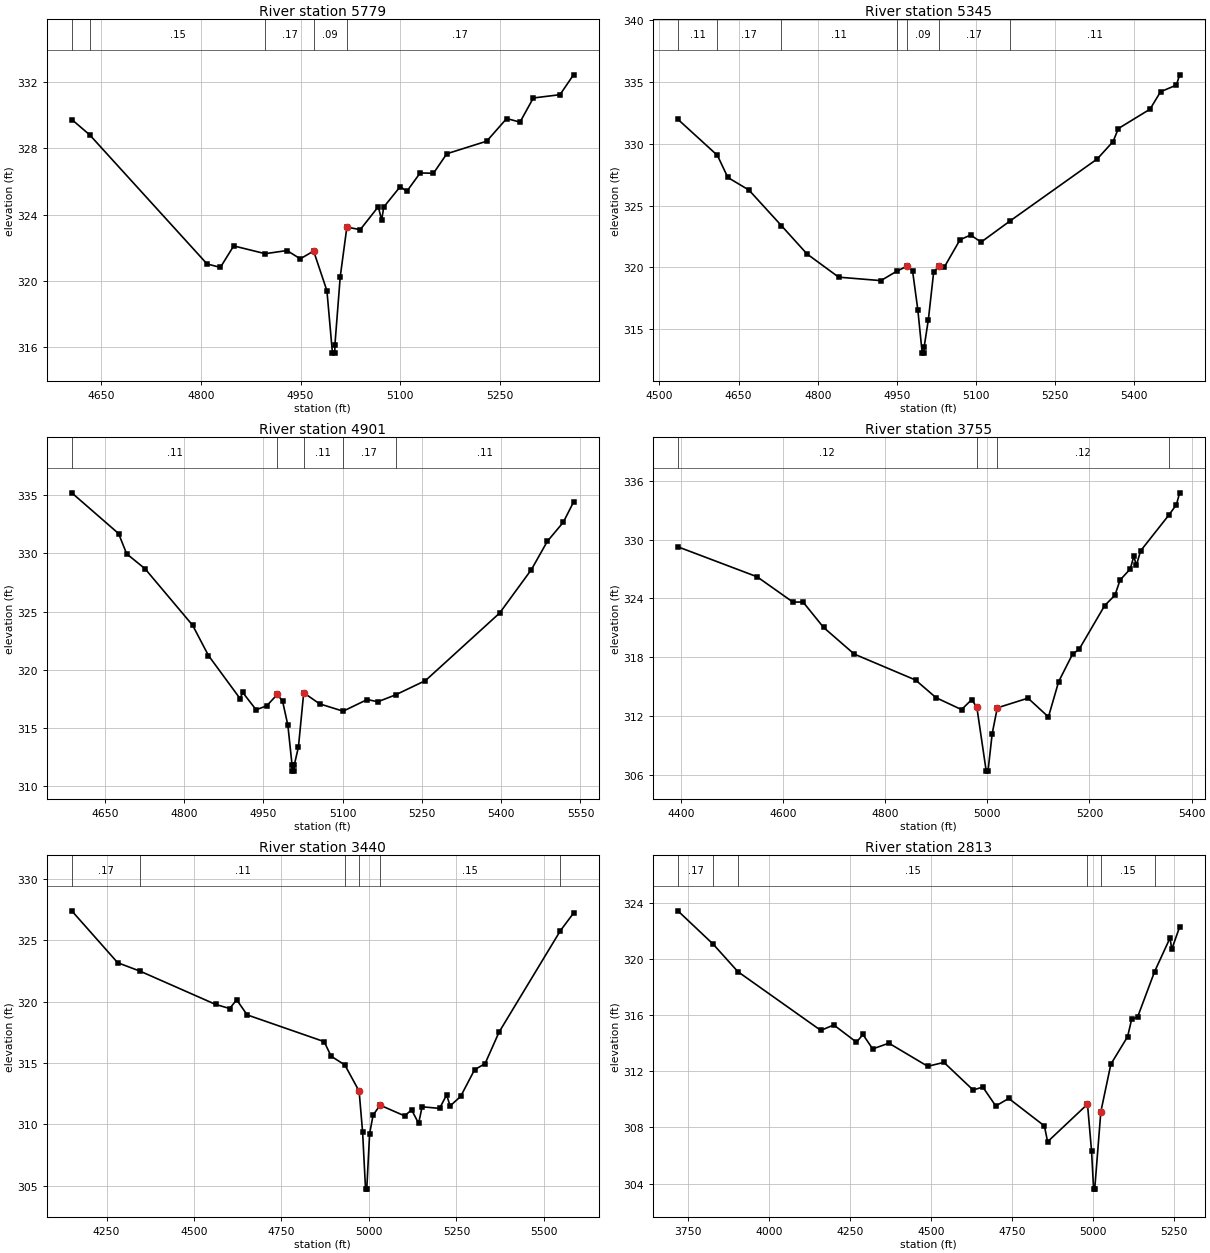
Type RM Length L Ch R = 1 ,5779    ,434,434,434
BEGIN DESCRIPTION:
WFSJR 039 7.0
END DESCRIPTION:
XS GIS Cut Line= 3
       3773214.7     10253498.94      3773683.43      10253516.3
      3773968.19     10253509.36
#Sta/Elev= 30
  4606.2  329.75  4633.2  328.82  4809.5  321.02  4829.5  320.81  4849.5  322.11
  4896.9  321.64  4929.6  321.83  4949.6  321.33  4969.6   321.8  4989.6   319.4
  4997.9  315.63  5001.4  315.63  5001.6  316.13  5009.6  320.25  5019.6  323.25
  5039.6  323.09  5066.8  324.48  5071.8  323.67    5075  324.46  5099.7  325.69
  5109.7  325.41  5129.7  326.52  5149.7   326.5  5169.7  327.68  5229.7  328.44
  5259.7  329.81  5279.7  329.59  5299.7  331.05  5339.8  331.25  5360.1  332.45
#Mann= 5 ,-1 , 0
  4606.2     .11       0  4633.2     .15       0  4896.9     .17       0
  4969.6     .09       0  5019.6     .17       0
Bank Sta=4969.6,5019.6
XS Rating Curve= 0 ,0
Exp/Cntr=0.3,0.1

Type RM Length L Ch R = 1 ,5345    ,444,444,444
BEGIN DESCRIPTION:
WFSJR 039 6.0
END DESCRIPTION:
XS GIS Cut Line= 2
      3773093.14     10253825.33      3774043.92      10253820.1
#Sta/Elev= 30
  4534.9  331.99  4609.8  329.07  4629.6  327.28  4669.6  326.26  4730.9  323.39
  4779.6  321.09  4839.6  319.21  4919.6  318.93  4949.6  319.69  4969.6  320.11
  4979.6  319.73  4989.6  316.57  4997.9  313.06  5001.4  313.06  5001.6  313.56
  5009.6  315.78  5019.6  319.61  5029.6  320.12  5039.6  320.01  5069.6  322.24
  5089.6  322.62  5109.6  322.05  5163.7  323.74  5329.6  328.78  5359.6  330.19
  5369.6  331.24  5429.6  332.81  5449.6  334.22  5479.6  334.76  5485.7  335.59
#Mann= 7 ,-1 , 0
  4534.9     .11       0  4609.8     .17       0  4730.9     .11       0
  4949.6     .17       0  4969.6     .09       0  5029.6     .17       0
  5163.7     .11       0
Bank Sta=4969.6,5029.6
XS Rating Curve= 0 ,0
Exp/Cntr=0.3,0.1

Type RM Length L Ch R = 1 ,4901    ,1146,1146,1146
BEGIN DESCRIPTION:
WFSJR 039 5.0
END DESCRIPTION:
XS GIS Cut Line= 3
      3772999.38      10254141.3      3773530.65     10254165.61
       3773947.3     10254137.83
#Sta/Elev= 30
  4587.4   335.2    4676   331.7  4691.3  329.96    4726  328.68  4816.1  323.82
  4846.1  321.22  4905.9  317.52  4910.9  318.05  4936.2  316.56  4956.3   316.9
  4976.3  317.88  4986.3   317.3  4996.3  315.24  5004.3  311.79  5004.6  311.29
  5008.1  311.29  5008.3  311.79  5016.3  313.36  5026.3  318.02  5056.4  317.07
  5100.9  316.44  5146.5  317.44  5166.5  317.25    5200  317.84  5256.7  319.07
    5397  324.87  5457.2  328.61  5487.2  331.03  5517.3  332.66  5536.8   334.4
#Mann= 5 ,-1 , 0
  4587.4     .11       0  4976.3     .06       0  5026.3     .11       0
  5100.9     .17       0    5200     .11       0
Bank Sta=4976.3,5026.3
XS Rating Curve= 0 ,0
Exp/Cntr=0.3,0.1

Type RM Length L Ch R = 1 ,3755    ,315,315,315
BEGIN DESCRIPTION:
WFSJR 039 4.0
END DESCRIPTION:
XS GIS Cut Line= 3
      3773002.83      10254703.8      3773777.18     10254728.11
      3773984.19     10254741.91
#Sta/Elev= 30
  4394.3  329.27  4549.4  326.21  4619.4  323.63  4639.4  323.63  4679.5  321.04
  4739.5  318.32  4859.6  315.67  4899.6  313.87  4949.6  312.65  4969.6  313.68
  4979.6  312.87  4997.9  306.37  5001.4  306.37  5009.6   310.2  5019.6  312.83
  5079.7  313.82  5119.7   311.9  5139.7  315.51  5166.9  318.31  5179.7   318.8
  5229.8  323.27  5249.9  324.33  5259.9  325.87    5280  327.02  5286.8  328.31
  5291.9  327.38    5300  328.85  5355.3   332.5  5370.2  333.57  5376.5  334.78
#Mann= 4 ,-1 , 0
  4394.3     .12       0  4979.6     .07       0  5019.6     .12       0
  5355.3     .11       0
Bank Sta=4979.6,5019.6
XS Rating Curve= 0 ,0
Exp/Cntr=0.3,0.1

Type RM Length L Ch R = 1 ,3440    ,627,627,627
BEGIN DESCRIPTION:
Mapping XS 5aee77b4
END DESCRIPTION:
XS GIS Cut Line= 2
      3772676.52     10254985.05       3774110.5       10254992.
#Sta/Elev= 30
  4150.6  327.39  4281.9  323.16  4346.1  322.47  4561.9  319.76  4601.9  319.43
  4621.9  320.14  4651.9  318.91  4871.9  316.73  4891.9  315.54  4931.1  314.83
  4971.9  312.69  4981.9  309.34  4990.2  304.71  4993.7  304.71  5001.9  309.23
  5011.9  310.75  5031.9  311.55  5101.9  310.68  5121.9  311.17  5141.9  310.07
  5151.9  311.42  5201.9  311.29  5221.9  312.39  5231.9  311.49  5261.9  312.26
  5301.9  314.44  5331.9  314.94  5371.9  317.51  5547.1  325.77  5584.6   327.2
#Mann= 6 ,-1 , 0
  4150.6     .17       0  4346.1     .11       0  4931.1     .15       0
  4971.9     .09       0  5031.9     .15       0  5547.1     .11       0
Bank Sta=4971.9,5031.9
XS Rating Curve= 0 ,0
Exp/Cntr=0.3,0.1

Type RM Length L Ch R = 1 ,2813    ,379,379,379
BEGIN DESCRIPTION:
Mapping XS 7d92ff8e
END DESCRIPTION:
XS GIS Cut Line= 3
      3772596.59     10255419.08      3773759.82     10255432.97
       3774133.8     10255339.48
#Sta/Elev= 30
  3717.5  323.45  3826.5  321.07  3902.8  319.11  4158.8  314.92  4198.8  315.31
  4268.8  314.08  4288.8  314.63  4318.8   313.6  4368.8  314.01  4488.8  312.36
  4538.8  312.64  4628.8  310.67  4658.8  310.88  4698.8  309.53  4738.8  310.07
  4848.8  308.11  4858.8  306.98  4981.9  309.66  4994.5  306.31  5000.7   303.6
  5004.2   303.6  5023.1  309.12    5054  312.51  5105.6  314.47  5118.2  315.71
  5136.5  315.87  5189.1  319.12  5236.8  321.52  5241.9   320.7  5266.3   322.3
#Mann= 6 ,-1 , 0
  3717.5     .17       0  3826.5     .11       0  3902.8     .15       0
  4981.9     .09       0  5023.1     .15       0  5189.1     .11       0
Bank Sta=4981.9,5023.1
XS Rating Curve= 0 ,0
Exp/Cntr=0.3,0.1

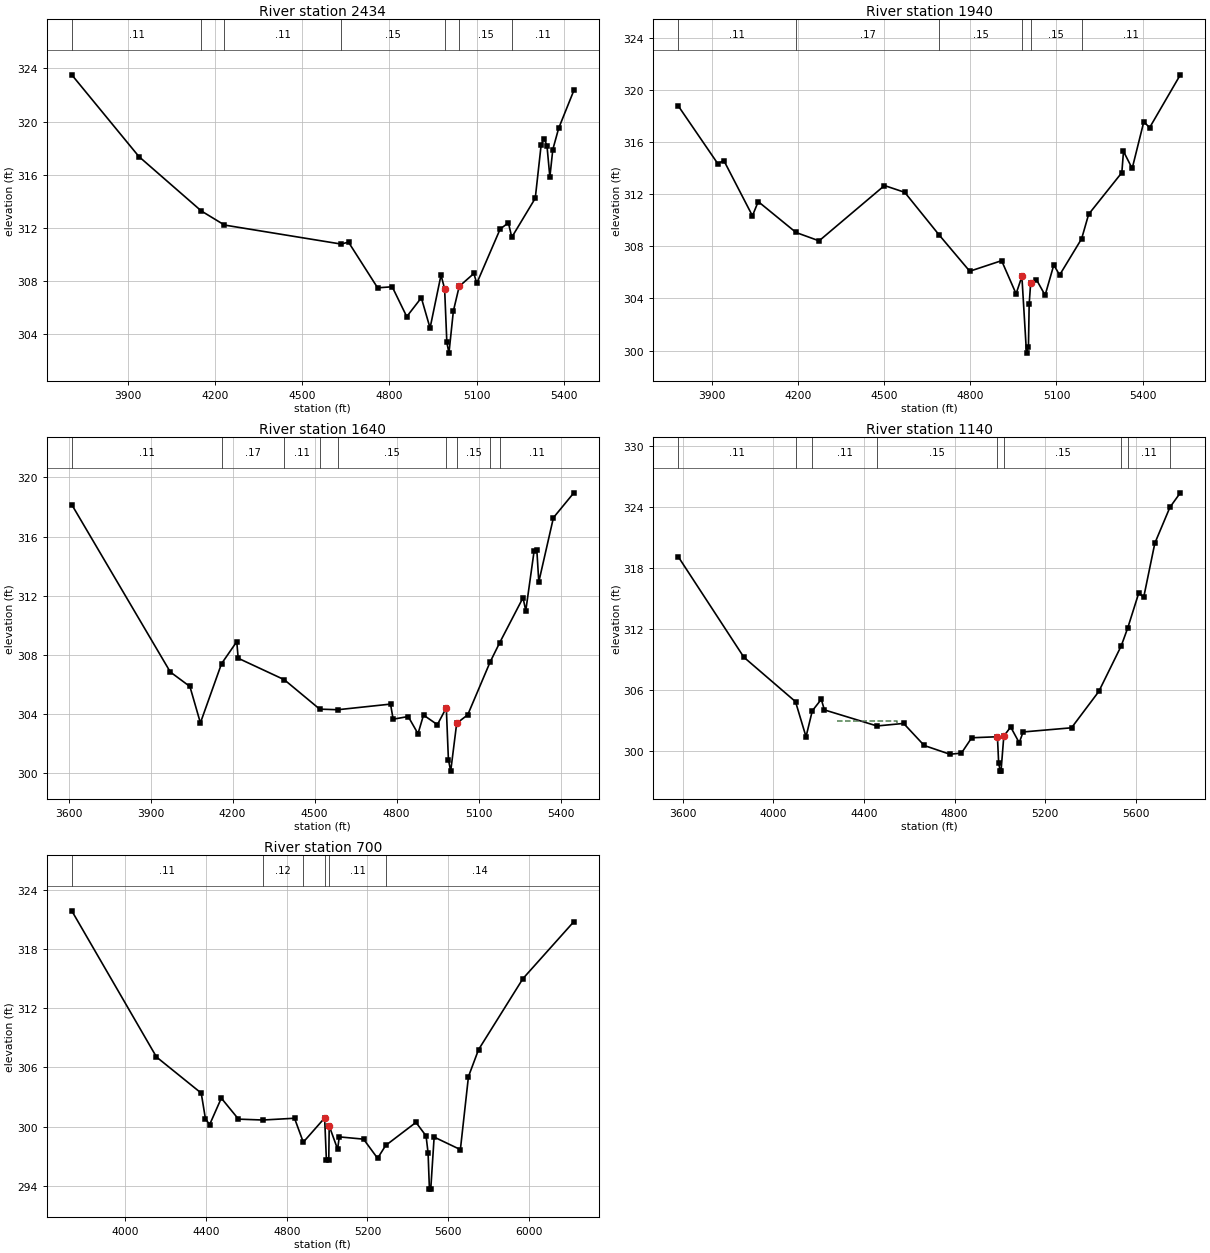
Type RM Length L Ch R = 1 ,2434    ,494,494,494
BEGIN DESCRIPTION:
WFSJR 039 3.0
END DESCRIPTION:
XS GIS Cut Line= 3
      3772537.58     10255627.42      3773828.23     10255676.84
      3774259.84     10255634.36
#Sta/Elev= 30
  3708.4  323.52  3939.2  317.36  4153.7  313.26  4233.2   312.2  4633.4  310.77
  4659.4  310.91  4759.4  307.47  4809.5  307.55  4859.5   305.3  4909.6  306.72
  4939.6  304.44  4977.2  308.43  4989.6  307.41  4997.3  303.36  5004.5  302.55
  5019.7  305.72  5039.8  307.58  5090.1  308.55  5100.1  307.81  5180.5   311.9
  5208.8  312.37  5220.4  311.28  5301.1  314.22  5321.2  318.21  5331.2  318.72
  5341.3  318.19  5351.3  315.81  5361.4  317.89  5381.5  319.49  5433.7  322.34
#Mann= 7 ,-1 , 0
  3708.4     .11       0  4153.7     .15       0  4233.2     .11       0
  4633.4     .15       0  4989.6     .09       0  5039.8     .15       0
  5220.4     .11       0
Bank Sta=4989.6,5039.8
XS Rating Curve= 0 ,0
Exp/Cntr=0.3,0.1

Type RM Length L Ch R = 1 ,1940    ,300,300,300
BEGIN DESCRIPTION:
WFSJR 039 2.0
END DESCRIPTION:
XS GIS Cut Line= 3
      3772641.76     10255873.94      3773848.23     10256046.84
      3774373.59     10255964.35
#Sta/Elev= 30
  3781.2  318.76  3918.7  314.34  3940.6  314.55  4039.9  310.33  4060.1  311.42
    4192  309.05  4272.3  308.41  4500.3  312.65  4570.9  312.13  4690.9  308.86
  4797.6  306.08  4908.7  306.89  4959.2  304.35  4979.4  305.68  4995.5   299.8
  5002.3   300.3  5004.8  303.54  5009.9  305.15    5030  305.44  5060.4  304.24
  5090.7  306.56    5111  305.79  5187.7  308.57  5212.2  310.45  5327.9  313.64
  5333.7  315.27    5364  313.96  5404.5  317.54  5424.8  317.09  5531.8  321.14
#Mann= 6 ,-1 , 0
  3781.2     .11       0    4192     .17       0  4690.9     .15       0
  4979.4     .09       0  5009.9     .15       0  5187.7     .11       0
Bank Sta=4979.4,5009.9
XS Rating Curve= 0 ,0
Exp/Cntr=0.3,0.1

Type RM Length L Ch R = 1 ,1640    ,500,500,500
BEGIN DESCRIPTION:
Mapping XS 0b2ffc76
END DESCRIPTION:
XS GIS Cut Line= 3
      3772607.08     10256033.68      3773613.98     10256332.28
      3774391.74      10256217.7
#Sta/Elev= 30
  3611.9  318.16  3972.3  306.85    4044  305.87  4082.4  303.41  4159.6  307.41
  4215.4   308.9  4220.6  307.78  4389.1  306.33  4518.8  304.34  4584.8   304.3
  4777.8  304.68  4787.4  303.66  4842.4  303.84  4878.3  302.68  4898.5  303.94
  4949.1  303.29  4981.8  304.43  4989.5  300.93  4997.9  300.15  5019.8  303.38
  5060.3  303.96  5142.2  307.53  5176.8  308.82  5262.4  311.87  5272.5  310.99
  5302.9  315.02    5313  315.07  5320.1  312.94  5373.6  317.28  5448.3  318.96
#Mann= 9 ,-1 , 0
  3611.9     .11       0  4159.6     .17       0  4389.1     .11       0
  4518.8     .17       0  4584.8     .15       0  4981.8     .09       0
  5019.8     .15       0  5142.2     .17       0  5176.8     .11       0
#XS Ineff= 1 ,-1
    3880  4215.4   308.9
Permanent Ineff=
       F
Bank Sta=4981.8,5019.8
XS Rating Curve= 0 ,0
Exp/Cntr=0.3,0.1

Type RM Length L Ch R = 1 ,1140    ,440,440,440
BEGIN DESCRIPTION:
Mapping XS 99daa15c
END DESCRIPTION:
XS GIS Cut Line= 4
      3772575.82     10256033.68      3773450.79     10256481.58
      3774118.35     10256800.25      3774473.99     10256458.34
#Sta/Elev= 30
    3580  319.12  3869.6  309.24  4097.6  304.87    4144  301.42  4171.7  303.97
  4211.4   305.1    4225  304.06  4457.3  302.48  4574.8  302.73  4665.6  300.56
    4779   299.7  4829.9  299.81  4875.3  301.32  4988.8  301.42  4994.3  298.82
  5001.2  298.04  5004.7  298.04    5017  301.48  5047.2  302.38    5085  300.83
  5102.2  301.89  5315.8   302.3  5436.2  305.87  5535.2  310.35    5564  312.12
  5612.9  315.57  5634.3  315.12  5683.6  320.45  5750.2  323.98    5796   325.4
#Mann= 9 ,-1 , 0
    3580     .11       0  4097.6     .17       0  4171.7     .11       0
  4457.3     .15       0  4988.8     .08       0    5017     .15       0
  5535.2     .17       0    5564     .11       0  5750.2     .17       0
#XS Ineff= 2 ,-1
    4000  4211.4   305.1    4280  4546.8  302.97
Permanent Ineff=
       F       F
Bank Sta=4988.8,5017
XS Rating Curve= 0 ,0
Exp/Cntr=0.3,0.1

Type RM Length L Ch R = 1 ,700     ,0,0,0
BEGIN DESCRIPTION:
WFSJR 039 1.0
END DESCRIPTION:
XS GIS Cut Line= 3
      3772517.83     10256011.05      3773693.59     10256922.36
      3773743.37     10257922.94
#Sta/Elev= 30
    3734  321.89  4154.1  307.06  4375.9   303.4  4396.7   300.8  4417.5   300.2
  4475.5  302.89  4560.6  300.76  4681.7  300.67  4838.5  300.85  4881.9  298.42
  4987.8  300.88  4996.5  296.62  5008.2  296.62  5010.5  300.07  5052.1  297.71
  5060.3  298.96  5180.7  298.73  5250.3  296.79  5290.4  298.09  5440.6  300.43
  5490.6  299.06  5500.6  297.35  5507.3  293.66  5513.9  293.66  5530.7  298.94
  5660.8  297.67  5700.9  305.08  5750.9  307.81  5971.2  315.02  6223.4  320.79
#Mann= 6 ,-1 , 0
    3734     .11       0  4681.7     .12       0  4881.9     .11       0
  4987.8     .07       0  5010.5     .11       0  5290.4     .14       0
#XS Ineff= 3 ,-1
                                                  5440.6    5700  300.43
Permanent Ineff=
       F       F       T
Bank Sta=4987.8,5010.5
XS Rating Curve= 0 ,0
Exp/Cntr=0.3,0.1

Chan Stop Cuts=-1
Use User Specified Reach Order=0
Composite Channel Slope=5