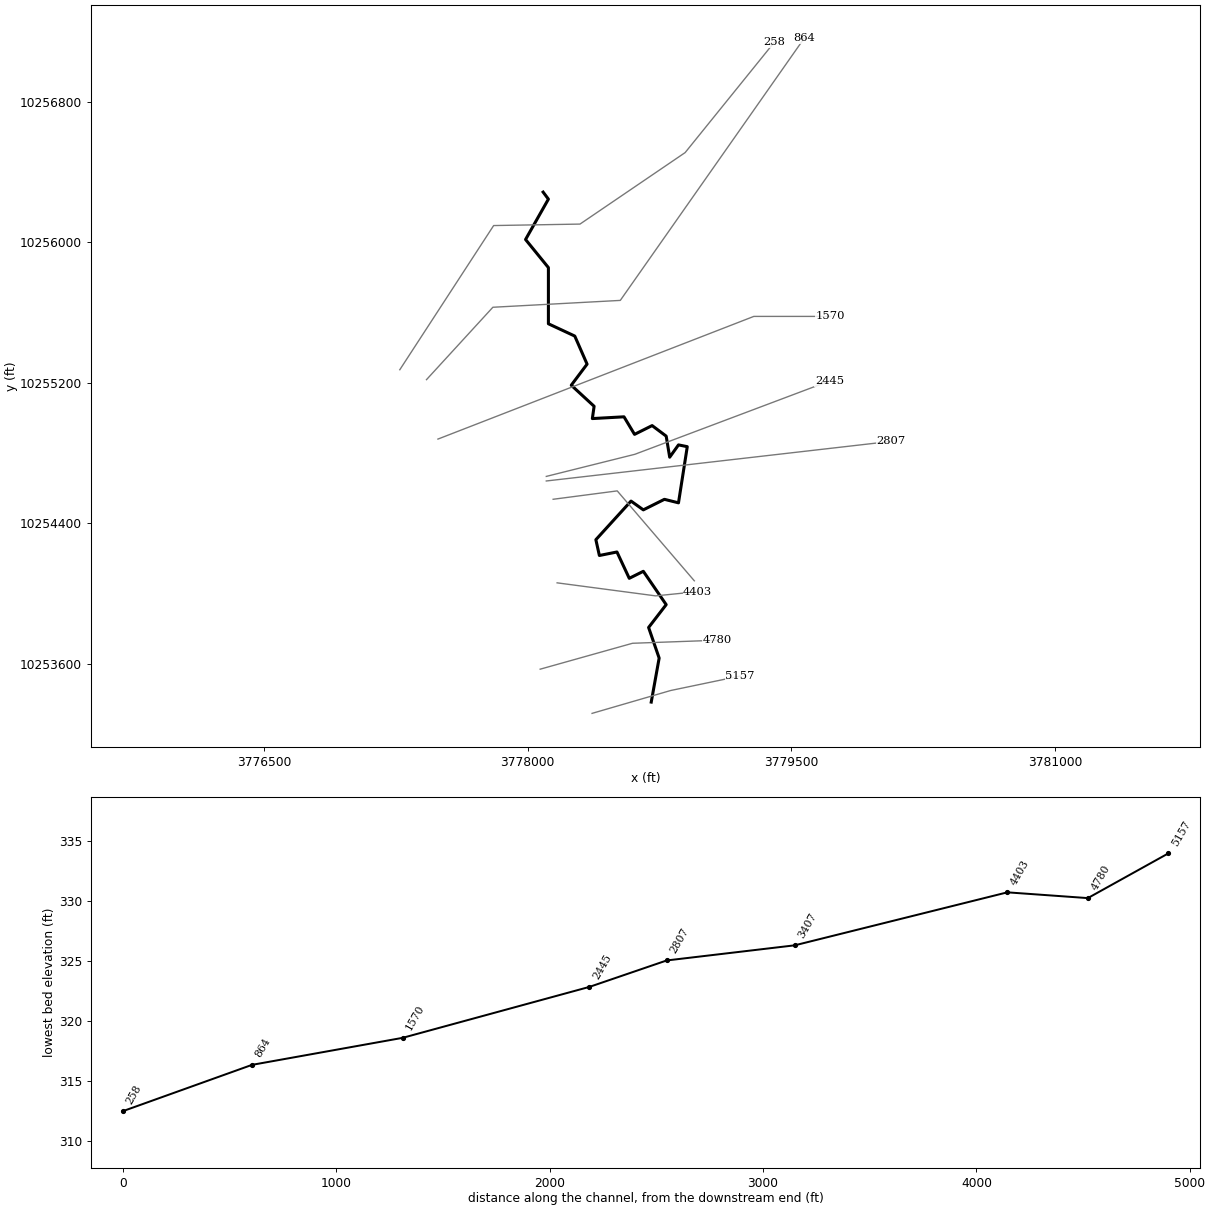
--- WFSJR 041.prj (project) ---

Proj Title=WFSJR 041 Base Level Engineering
Current Plan=p01
Default Exp/Contr=0.3,0.1
English Units
Geom File=g01
Flow File=f01
Plan File=p01
Y Axis Title=Elevation
X Axis Title(PF)=Main Channel Distance
X Axis Title(XS)=Station
BEGIN DESCRIPTION:
WFSJR 041
END DESCRIPTION:
DSS Export Rating Curves= 0
DSS Export Rating Curve Sorted= 0
DSS Export Volume Flow Curves= 0
DXF OffsetX= 0
DXF OffsetY= 0
DXF ScaleX= 1
DXF ScaleY= 10

--- WFSJR 041.p01 (plan) ---

Plan Title=Multiple Run
Program Version=4.10
Short Identifier=Multiple
Geom File=g01
Flow File=f01
Subcritical Flow
K Sum by GR= 0
Std Step Tol= 0.01
Critical Tol= 0.01
Num of Std Step Trials= 20
Max Error Tol= 0.3
Flow Tol Ratio= 0.001
Split Flow NTrial= 30
Split Flow Tol= 0.02
Split Flow Ratio= 0.02
Log Output Level= 0
Friction Slope Method= 1
Unsteady Friction Slope Method= 2
Unsteady Bridges Friction Slope Method= 1
Parabolic Critical Depth
Global Vel Dist= 1 , 1 , 1
Global Log Level= 0
CheckData=True
Encroach Param=-1 ,0,0, 0
BEGIN DESCRIPTION:
Multiple Run
END DESCRIPTION:
Computation Interval=1HOUR
Output Interval=1HOUR
Run HTab= 0
Run UNet= 0
Run PostProcess= 0
Run WQNet= 0
UNET Theta= 1
UNET Theta Warmup= 1
UNET ZTol= 0.02
UNET ZSATol= 0.05
UNET MxIter= 20
UNET MaxInSteps= 0
UNET DtIC= 0
UNET DtMin= 0
UNET MaxCRTS= 20
UNET WFStab= 2
UNET SFStab= 1
UNET WFX= 1
UNET SFX= 1
UNET DSS MLevel= 4
UNET DZMax Abort= 100
UNET Convert EG Bridges= 0
UNET Use Existing IB Tables=-1
UNET Froude Reduction=False
UNET Froude Limit= 1
UNET Froude Power= 10
UNET Time Slicing=0,0, 5
UNET Junction Losses=0
Instantaneous Interval=1HOUR
Write IC File= 0
Write IC File at Sim End=0
Echo Input=False
Echo Parameters=False
Echo Output=False
Write Detailed= 0
WQ AD Non Conservative
WQ ULTIMATE=-1
WQ Max Comp Step=1HOUR
WQ Output Interval=15MIN
WQ Output Selected Increments= 0
WQ Output face flow=0
WQ Output face velocity=0
WQ Output face area=0
WQ Output face dispersion=0
WQ Output cell volume=0
WQ Output cell surface area=0
WQ Output cell continuity=0
WQ Output cumulative cell continuity=0
WQ Output face conc=0
WQ Output face dconc_dx=0
WQ Output face courant=0
WQ Output face peclet=0
WQ Output face adv mass=0
WQ Output face disp mass=0
WQ Output cell mass=0
WQ Output cell source sink temp=0
WQ Output cell source sink nsm=0
WQ Output MaxMinRange=-1
WQ Daily Max Min Mean=-1
WQ Daily Range=0
WQ Daily Time=0
WQ Create Restart=0
WQ Fixed Restart=0
WQ System Summary=0
WQ Use Fixed Temperature=0
Sorting and Armoring Iterations= 10
XS Update Threshold= 0.02
Hydraulics Update Threshold= 0.02
Energy Slope Method= 1
Volume Change Method= 0
XS Weighting Method= 0
Number of US Weighted Cross Sections= 1
Number of DS Weighted Cross Sections= 1
Upstream XS Weight=0.25
Main XS Weight=0.5
Downstream XS Weight=0.25
Number of DS XS's Weighted with US Boundary= 1
Upstream Boundary Weight= 1
Weight of XSs Associated with US Boundary= 0
Number of US XS's Weighted with DS Boundary= 1
Downstream Boundary Weight= 0.5
Weight of XSs Associated with DS Boundary= 0.5
Sediment Output Level= 4
Mass or Volume Output= 0
Output Increment Type= 1
Profile and TS Output Increment= 10
XS Output Flag= 0
XS Output Increment= 10
Disregard all LS=0
Disregard all Conn=0
Disregard all Breaches=0
Disregard all Pumps=0

--- WFSJR 041.f01 (steady flow) ---

Flow Title=Multiple
Program Version=4.10
Number of Profiles= 7
Profile Names=10-year,25-year,50-year,1pct_min,100-year,1pct_plu,500-year
River Rch & RM=WFSJR 041,Reach-1         ,5157
     546     736     992     442    1334    4029    2485
River Rch & RM=WFSJR 041,Reach-1         ,4780
     544     726     971     427    1291    3899    2356
Boundary for River Rch & Prof#=WFSJR 041,Reach-1         , 1
Up Type= 0
Dn Type= 3
Dn Slope=0.007
Boundary for River Rch & Prof#=WFSJR 041,Reach-1         , 2
Up Type= 0
Dn Type= 3
Dn Slope=0.007
Boundary for River Rch & Prof#=WFSJR 041,Reach-1         , 3
Up Type= 0
Dn Type= 3
Dn Slope=0.007
Boundary for River Rch & Prof#=WFSJR 041,Reach-1         , 4
Up Type= 0
Dn Type= 3
Dn Slope=0.007
Boundary for River Rch & Prof#=WFSJR 041,Reach-1         , 5
Up Type= 0
Dn Type= 3
Dn Slope=0.007
Boundary for River Rch & Prof#=WFSJR 041,Reach-1         , 6
Up Type= 0
Dn Type= 3
Dn Slope=0.007
Boundary for River Rch & Prof#=WFSJR 041,Reach-1         , 7
Up Type= 0
Dn Type= 3
Dn Slope=0.007
DSS Import GetInterval= 0
DSS Import GetPeak= 0
DSS Import FillOption= 0

--- WFSJR 041.g01 (geometry) ---

Geom Title=Existing Conditions
Program Version=4.10

River Reach=WFSJR 041       ,Reach-1
Reach XY= 30
      3778703.23     10253381.84      3778748.23     10253632.51
      3778688.23     10253806.84      3778788.23     10253936.84
      3778658.23     10254126.84      3778578.23     10254086.84
      3778508.23     10254236.84      3778408.23     10254216.84
      3778388.23     10254306.84      3778588.23     10254526.84
      3778658.23     10254476.84      3778778.23     10254536.84
      3778858.23     10254516.84      3778908.23     10254836.84
      3778858.23     10254846.84      3778808.23     10254776.84
      3778788.23     10254896.84      3778708.23     10254956.84
      3778608.23     10254906.84      3778548.23     10255006.84
      3778368.23     10254996.84      3778378.23     10255066.84
      3778248.23     10255186.84      3778338.23     10255306.84
      3778268.23     10255466.84      3778118.23     10255536.84
      3778118.23     10255856.84      3777988.23     10256016.84
      3778118.23     10256246.84      3778088.23     10256286.84

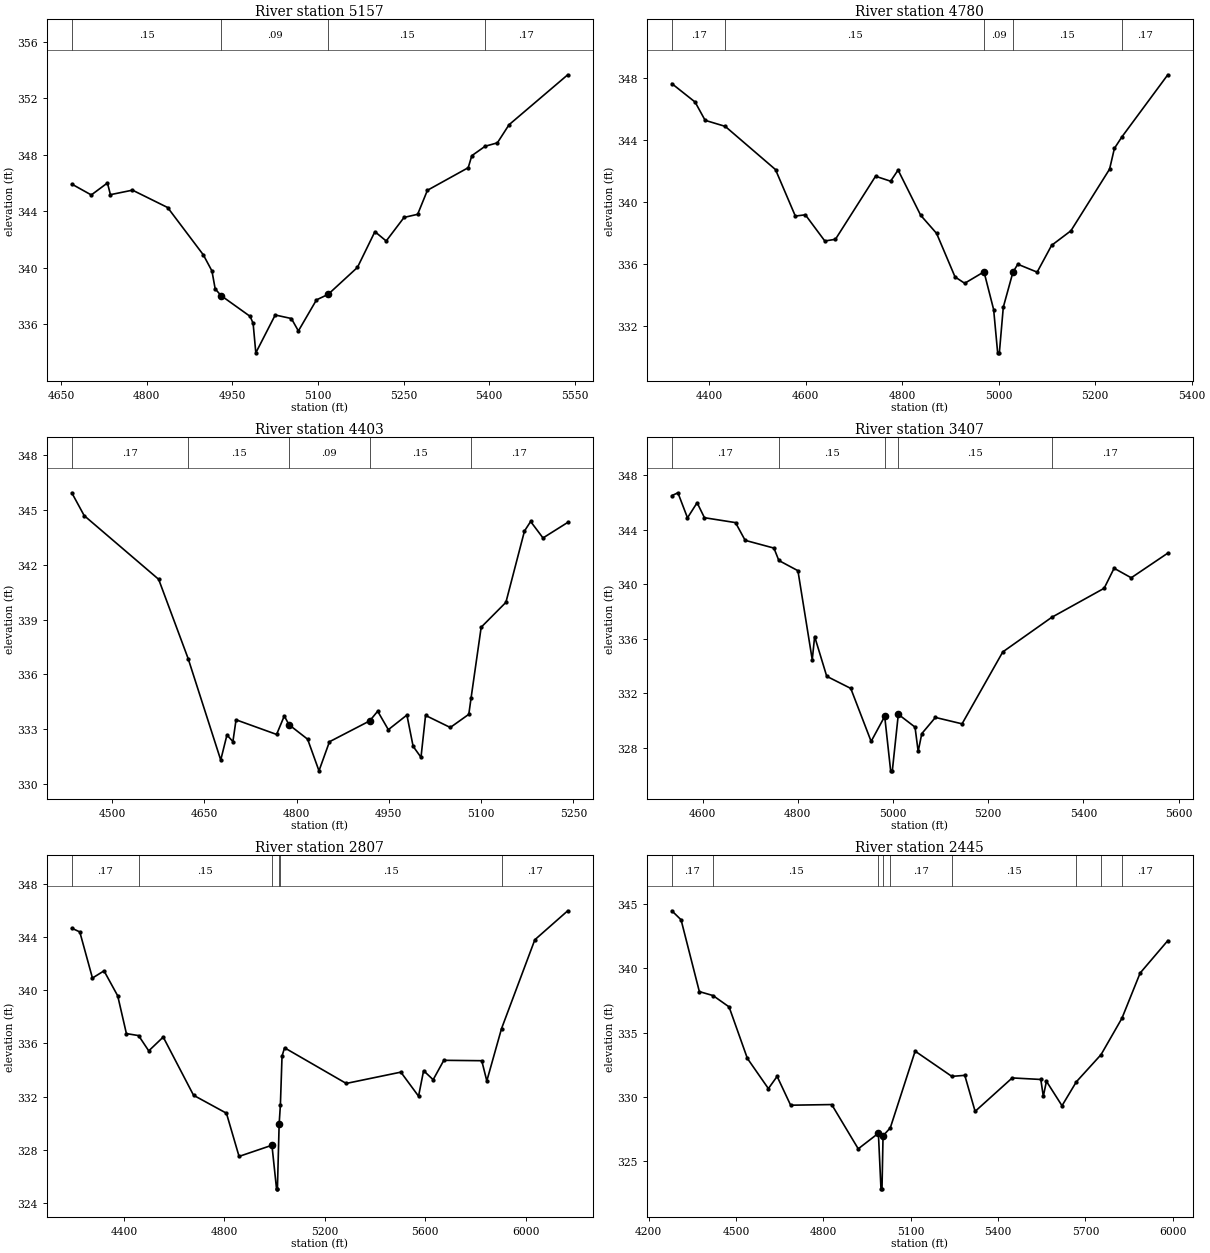
Type RM Length L Ch R = 1 ,5157    ,377,377,377
BEGIN DESCRIPTION:
WFSJR 041 5.0
END DESCRIPTION:
XS GIS Cut Line= 3
      3778366.58     10253317.52      3778813.63     10253447.73
      3779208.59     10253530.19
#Sta/Elev= 30
  4668.5  345.92  4702.7  345.15    4731     346  4736.2  345.17  4774.9  345.49
  4836.5  344.26    4899  340.91  4914.1  339.77  4919.8   338.5  4930.2  338.02
  4981.1  336.55  4986.3  336.05    4991  333.97    5025  336.65  5053.3   336.4
  5065.6  335.52  5097.3  337.72  5117.7  338.11  5169.1  340.02  5199.7  342.55
  5219.5  341.89  5250.8  343.56  5274.6  343.78  5291.7  345.48  5363.2  347.08
  5369.5  347.93  5392.9   348.6  5414.3  348.84  5434.7  350.12  5537.6  353.66
#Mann= 4 ,-1 , 0
  4668.5     .15       0  4930.2     .09       0  5117.7     .15       0
  5392.9     .17       0
Bank Sta=4930.2,5117.7
XS Rating Curve= 0 ,0
Exp/Cntr=0.3,0.1

Type RM Length L Ch R = 1 ,4780    ,377,377,377
BEGIN DESCRIPTION:
Mapping XS f4118d57
END DESCRIPTION:
XS GIS Cut Line= 3
      3778071.45     10253569.26      3778596.62     10253716.83
       3779078.4     10253734.19
#Sta/Elev= 30
  4322.8  347.63    4371  346.44  4391.8  345.26  4433.4  344.87  4537.6  342.08
  4578.7  339.08  4599.5  339.16  4639.8  337.47  4661.8  337.58  4744.9  341.65
  4776.1  341.33  4791.6  342.05  4838.4  339.13  4871.4  337.96  4909.6  335.15
  4929.6  334.74  4969.6  335.48  4989.6  333.04  4997.9  330.25  5001.4  330.25
  5009.6   333.2  5029.6  335.46  5039.6  335.97  5079.7  335.46  5109.7  337.19
  5149.7  338.13  5229.8  342.11  5239.8  343.45  5255.3  344.19  5350.4   348.2
#Mann= 5 ,-1 , 0
  4322.8     .17       0  4433.4     .15       0  4969.6     .09       0
  5029.6     .15       0  5255.3     .17       0
Bank Sta=4969.6,5029.6
XS Rating Curve= 0 ,0
Exp/Cntr=0.3,0.1

Type RM Length L Ch R = 1 ,4403    ,996,996,996
BEGIN DESCRIPTION:
WFSJR 041 4.0
END DESCRIPTION:
XS GIS Cut Line= 3
      3778167.82     10254061.08      3778728.23     10253986.84
      3778967.81     10254011.07
#Sta/Elev= 30
  4434.7  345.93  4454.9  344.68  4575.9   341.2  4623.8  336.87  4676.8  331.32
  4686.9  332.69  4696.6  332.33  4701.7  333.52  4767.6  332.72  4780.1  333.73
  4787.8  333.25    4818  332.46  4836.5  330.73  4853.5  332.32  4918.9  333.46
  4931.9  333.99  4949.2  332.98  4979.4  333.78  4989.5  332.07  5002.3  331.47
  5009.7  333.76  5049.9   333.1    5080  333.82  5083.6  334.69  5100.1  338.58
  5140.3  339.94  5170.5  343.84  5180.5  344.36  5200.6  343.46  5240.8  344.31
#Mann= 5 ,-1 , 0
  4434.7     .17       0  4623.8     .15       0  4787.8     .09       0
  4918.9     .15       0  5083.6     .17       0
Bank Sta=4787.8,4918.9
XS Rating Curve= 0 ,0
Exp/Cntr=0.3,0.1

Type RM Length L Ch R = 1 ,3407    ,600,600,600
BEGIN DESCRIPTION:
WFSJR 041 3.0
END DESCRIPTION:
XS GIS Cut Line= 3
       3778145.2     10254537.13      3778509.82     10254584.88
      3778948.21      10254072.7
#Sta/Elev= 30
  4535.5  346.52  4548.3  346.73  4568.4  344.89  4588.6     346    4604   344.9
  4669.3  344.54  4689.5  343.24    4750  342.67  4760.3  341.76  4800.4  341.01
  4830.5  334.47  4835.5  336.18  4860.9  333.26  4911.4  332.37  4954.2  328.48
  4982.7  330.32  4995.2  326.32  4998.7  326.32  5011.3  330.47  5046.4  329.53
    5053  327.74  5060.6  329.05  5089.2  330.24  5145.2  329.77  5230.8  335.05
  5333.7  337.59  5443.7  339.72  5464.6  341.19  5500.6  340.49  5577.4   342.3
#Mann= 5 ,-1 , 0
  4535.5     .17       0  4760.3     .15       0  4982.7     .09       0
  5011.3     .15       0  5333.7     .17       0
Bank Sta=4982.7,5011.3
XS Rating Curve= 0 ,0
Exp/Cntr=0.3,0.1

Type RM Length L Ch R = 1 ,2807    ,362,362,362
BEGIN DESCRIPTION:
Mapping XS b98fa1fc
END DESCRIPTION:
XS GIS Cut Line= 2
      3778106.12      10254641.3      3780067.98       10254867.
#Sta/Elev= 30
  4192.6  344.67  4224.5  344.39  4274.9  340.92    4321  341.46  4375.5  339.58
  4410.1  336.74  4458.6  336.59  4499.1  335.44  4556.7  336.48  4677.5   332.1
  4808.4  330.75  4858.7   327.5  4989.6  328.34  5007.9  325.06  5011.4  325.06
  5018.3  329.93  5023.3  331.39  5029.8  335.05  5039.9  335.67  5285.4  332.99
  5502.9  333.84  5573.4  332.03  5593.5  333.95  5631.5  333.27    5674  334.73
    5825   334.7  5845.2  333.18  5903.7  337.11  6036.4   343.8  6167.4  345.98
#Mann= 6 ,-1 , 0
  4192.6     .17       0  4458.6     .15       0  4989.6     .09       0
  5018.3     .12       0  5023.3     .15       0  5903.7     .17       0
Bank Sta=4989.6,5018.3
XS Rating Curve= 0 ,0
Exp/Cntr=0.3,0.1

Type RM Length L Ch R = 1 ,2445    ,875,875,875
BEGIN DESCRIPTION:
WFSJR 041 2.0
END DESCRIPTION:
XS GIS Cut Line= 3
      3778106.19     10254667.35      3778609.64     10254793.21
      3779717.83     10255211.06
#Sta/Elev= 30
  4279.5  344.47  4311.2  343.77    4374  338.19    4421  337.88  4476.1     337
  4538.9     333  4611.1  330.65  4641.1   331.6  4687.5  329.36  4828.6  329.41
  4919.7  325.97  4988.9  327.18  4997.8  322.86  5001.3  322.86  5004.9  326.98
  5029.8   327.6  5115.1  333.56  5241.1   331.6  5285.6  331.68  5321.1  328.88
  5448.5  331.48  5546.7  331.36  5555.3  330.05    5566  331.22  5619.5  329.32
  5668.8  331.18  5753.6  333.29  5825.4  336.12  5887.8  339.63  5982.8  342.15
#Mann= 9 ,-1 , 0
  4279.5     .17       0    4421     .15       0  4988.9     .09       0
  5004.9     .15       0  5029.8     .17       0  5241.1     .15       0
  5668.8     .17       0  5753.6     .15       0  5825.4     .17       0
#XS Ineff= 1 ,-1
  5115.1    5780  333.56
Permanent Ineff=
       F
Bank Sta=4988.9,5004.9
XS Rating Curve= 0 ,0
Exp/Cntr=0.3,0.1

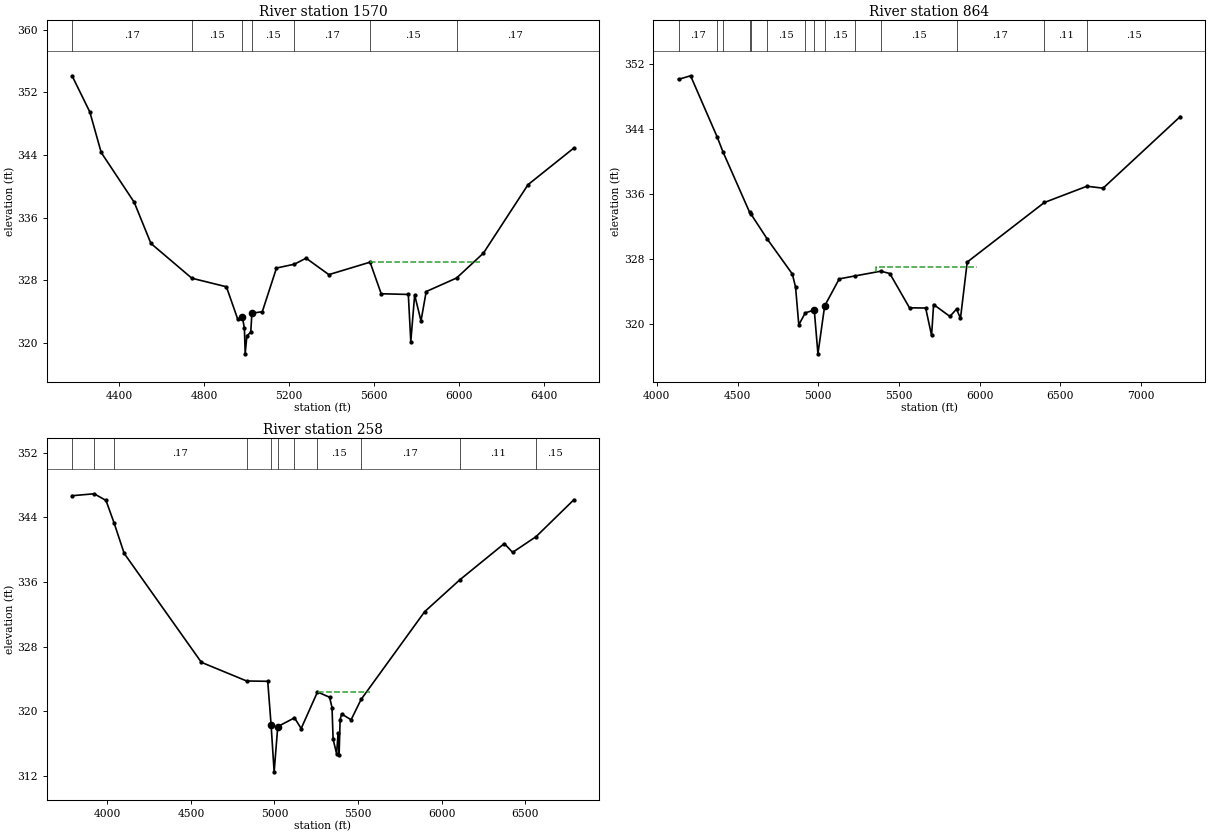
Type RM Length L Ch R = 1 ,1570    ,706,706,706
BEGIN DESCRIPTION:
Mapping XS c59c4124
END DESCRIPTION:
XS GIS Cut Line= 3
      3777489.85     10254880.02      3779286.73      10255578.8
      3779723.96      10255578.8
#Sta/Elev= 30
  4177.1  354.11  4260.8  349.49  4314.4  344.32  4469.9  337.97  4548.8  332.71
  4741.7  328.27  4904.6  327.18  4958.2  323.02  4979.7  323.31  4989.5  321.86
  4993.1  318.62  5001.1  320.91  5019.4  321.39  5024.7   323.8  5073.8     324
  5140.6  329.57  5224.9  330.06  5280.1  330.83  5387.4  328.73  5581.7  330.32
  5634.2  326.29    5762   326.2  5773.7  320.19  5791.9  326.13  5821.8  322.82
  5846.3  326.57  5989.7   328.3  6116.2  331.48  6326.2  340.21  6542.3  344.89
#Mann= 7 ,-1 , 0
  4177.1     .17       0  4741.7     .15       0  4979.7     .09       0
  5024.7     .15       0  5224.9     .17       0  5581.7     .15       0
  5989.7     .17       0
#XS Ineff= 1 ,-1
  5580.5    6100  330.37
Permanent Ineff=
       F
Bank Sta=4979.7,5024.7
XS Rating Curve= 0 ,0
Exp/Cntr=0.3,0.1

Type RM Length L Ch R = 1 ,864     ,606,606,606
BEGIN DESCRIPTION:
Mapping XS 00cc3dd5
END DESCRIPTION:
XS GIS Cut Line= 4
      3777424.77     10255218.58      3777802.35     10255630.89
      3778527.18     10255669.95      3779573.03     10257162.79
#Sta/Elev= 30
  4134.6  350.14  4209.2  350.58  4373.7  343.06  4410.3   341.2  4575.1  333.77
  4583.4  333.56  4684.9  330.47  4839.4  326.19  4859.4  324.57  4879.4  319.94
  4919.5  321.41  4975.2  321.76  4997.9  316.37  5039.7  322.27  5129.8  325.59
  5228.6  325.96  5387.8  326.54  5443.1  326.25  5565.1  322.03  5665.1  322.01
  5701.8  318.63  5714.2  322.44  5815.3  320.97  5856.2  321.88  5880.7  320.74
  5922.5  327.66  6400.2  334.99  6663.8  336.99    6764  336.75  7242.3  345.57
#Mann= 14 ,-1 , 0
  4134.6     .17       0  4373.7     .15       0  4410.3     .17       0
  4575.1     .15       0  4583.4     .17       0  4684.9     .15       0
  4919.5     .15       0  4975.2     .09       0  5039.7     .15       0
  5228.6     .17       0  5387.8     .15       0  5856.2     .17       0
  6400.2     .11       0  6663.8     .15       0
#XS Ineff= 1 ,-1
  5360.1    5980  327.01
Permanent Ineff=
       F
Bank Sta=4975.2,5039.7
XS Rating Curve= 0 ,0
Exp/Cntr=0.3,0.1

Type RM Length L Ch R = 1 ,258     ,0,0,0
BEGIN DESCRIPTION:
WFSJR 041 1.0
END DESCRIPTION:
XS GIS Cut Line= 5
      3777272.86     10255275.03      3777806.75     10256096.33
      3778297.93     10256104.71       3778896.1     10256511.96
      3779403.38     10257140.64
#Sta/Elev= 30
  3788.9  346.67  3920.9  346.91  3991.8  346.09    4041  343.26  4100.5  339.54
  4562.5  326.06  4833.4  323.75  4959.6  323.71  4979.6  318.36  4997.9  312.51
  5019.6  318.11  5119.6  319.19  5159.6  317.87  5257.2  322.39  5329.7  321.74
  5344.3  320.46  5350.7  316.55  5371.7  314.75  5380.6  317.31  5386.6   314.6
  5392.7  318.96  5401.5  319.67  5458.4  318.95    5518  321.46  5898.3  332.32
  6107.9  336.25  6375.2  340.75  6424.8  339.66  6565.3  341.61  6791.2  346.17
#Mann= 11 ,-1 , 0
  3788.9     .17       0  3920.9     .15       0    4041     .17       0
  4833.4     .15       0  4979.6     .08       0  5019.6     .15       0
  5119.6     .15       0  5257.2     .15       0    5518     .17       0
  6107.9     .11       0  6565.3     .15       0
#XS Ineff= 1 ,-1
  5259.7    5571  322.39
Permanent Ineff=
       T
Bank Sta=4979.6,5019.6
XS Rating Curve= 0 ,0
Exp/Cntr=0.3,0.1

Chan Stop Cuts=-1
Use User Specified Reach Order=0
Composite Channel Slope=5