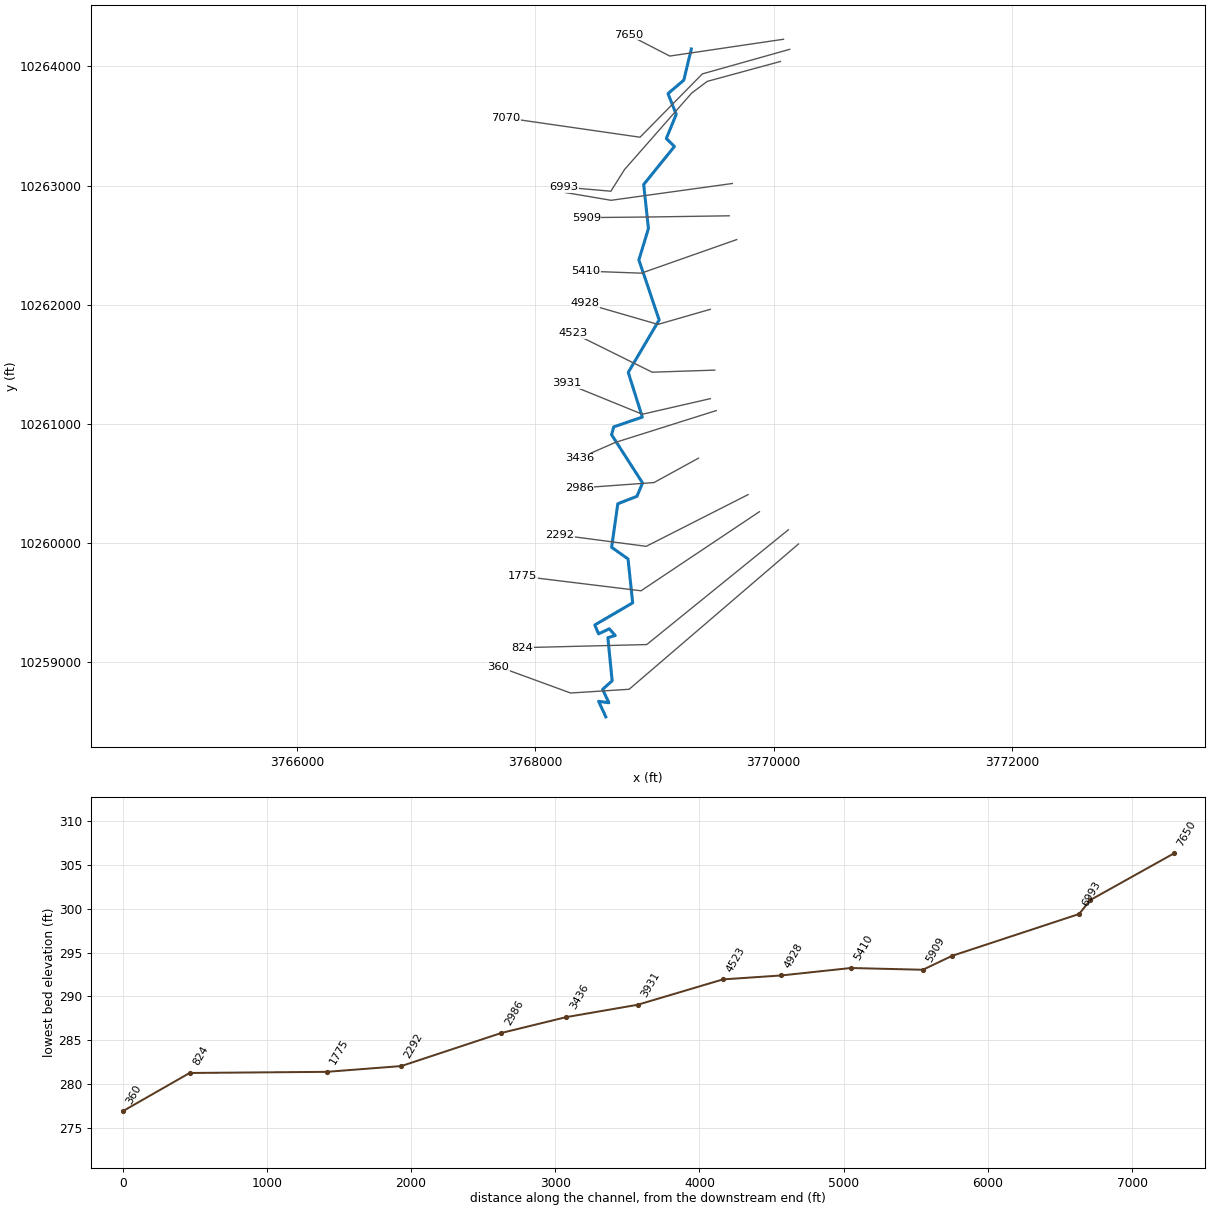
--- WFSJR 042.prj (project) ---

Proj Title=WFSJR 042 Base Level Engineering
Current Plan=p01
Default Exp/Contr=0.3,0.1
English Units
Geom File=g01
Flow File=f01
Plan File=p01
Y Axis Title=Elevation
X Axis Title(PF)=Main Channel Distance
X Axis Title(XS)=Station
BEGIN DESCRIPTION:
WFSJR 042
END DESCRIPTION:
DSS Export Rating Curves= 0
DSS Export Rating Curve Sorted= 0
DSS Export Volume Flow Curves= 0
DXF OffsetX= 0
DXF OffsetY= 0
DXF ScaleX= 1
DXF ScaleY= 10

--- WFSJR 042.p01 (plan) ---

Plan Title=Multiple Run
Program Version=4.10
Short Identifier=Multiple
Geom File=g01
Flow File=f01
Subcritical Flow
K Sum by GR= 0
Std Step Tol= 0.01
Critical Tol= 0.01
Num of Std Step Trials= 20
Max Error Tol= 0.3
Flow Tol Ratio= 0.001
Split Flow NTrial= 30
Split Flow Tol= 0.02
Split Flow Ratio= 0.02
Log Output Level= 0
Friction Slope Method= 1
Unsteady Friction Slope Method= 2
Unsteady Bridges Friction Slope Method= 1
Parabolic Critical Depth
Global Vel Dist= 1 , 1 , 1
Global Log Level= 0
CheckData=True
Encroach Param=-1 ,0,0, 0
BEGIN DESCRIPTION:
Multiple Run
END DESCRIPTION:
Computation Interval=1HOUR
Output Interval=1HOUR
Run HTab= 0
Run UNet= 0
Run PostProcess= 0
Run WQNet= 0
UNET Theta= 1
UNET Theta Warmup= 1
UNET ZTol= 0.02
UNET ZSATol= 0.05
UNET MxIter= 20
UNET MaxInSteps= 0
UNET DtIC= 0
UNET DtMin= 0
UNET MaxCRTS= 20
UNET WFStab= 2
UNET SFStab= 1
UNET WFX= 1
UNET SFX= 1
UNET DSS MLevel= 4
UNET DZMax Abort= 100
UNET Convert EG Bridges= 0
UNET Use Existing IB Tables=-1
UNET Froude Reduction=False
UNET Froude Limit= 1
UNET Froude Power= 10
UNET Time Slicing=0,0, 5
UNET Junction Losses=0
Instantaneous Interval=1HOUR
Write IC File= 0
Write IC File at Sim End=0
Echo Input=False
Echo Parameters=False
Echo Output=False
Write Detailed= 0
WQ AD Non Conservative
WQ ULTIMATE=-1
WQ Max Comp Step=1HOUR
WQ Output Interval=15MIN
WQ Output Selected Increments= 0
WQ Output face flow=0
WQ Output face velocity=0
WQ Output face area=0
WQ Output face dispersion=0
WQ Output cell volume=0
WQ Output cell surface area=0
WQ Output cell continuity=0
WQ Output cumulative cell continuity=0
WQ Output face conc=0
WQ Output face dconc_dx=0
WQ Output face courant=0
WQ Output face peclet=0
WQ Output face adv mass=0
WQ Output face disp mass=0
WQ Output cell mass=0
WQ Output cell source sink temp=0
WQ Output cell source sink nsm=0
WQ Output MaxMinRange=-1
WQ Daily Max Min Mean=-1
WQ Daily Range=0
WQ Daily Time=0
WQ Create Restart=0
WQ Fixed Restart=0
WQ System Summary=0
WQ Use Fixed Temperature=0
Sorting and Armoring Iterations= 10
XS Update Threshold= 0.02
Hydraulics Update Threshold= 0.02
Energy Slope Method= 1
Volume Change Method= 0
XS Weighting Method= 0
Number of US Weighted Cross Sections= 1
Number of DS Weighted Cross Sections= 1
Upstream XS Weight=0.25
Main XS Weight=0.5
Downstream XS Weight=0.25
Number of DS XS's Weighted with US Boundary= 1
Upstream Boundary Weight= 1
Weight of XSs Associated with US Boundary= 0
Number of US XS's Weighted with DS Boundary= 1
Downstream Boundary Weight= 0.5
Weight of XSs Associated with DS Boundary= 0.5
Sediment Output Level= 4
Mass or Volume Output= 0
Output Increment Type= 1
Profile and TS Output Increment= 10
XS Output Flag= 0
XS Output Increment= 10
Disregard all LS=0
Disregard all Conn=0
Disregard all Breaches=0
Disregard all Pumps=0

--- WFSJR 042.f01 (steady flow) ---

Flow Title=Multiple
Program Version=4.10
Number of Profiles= 7
Profile Names=10-year,25-year,50-year,1pct_min,100-year,1pct_plu,500-year
River Rch & RM=WFSJR 042,Reach-1         ,7650
     653     880    1186     525    1586    4790    2931
Boundary for River Rch & Prof#=WFSJR 042,Reach-1         , 1
Up Type= 0
Dn Type= 3
Dn Slope=0.009
Boundary for River Rch & Prof#=WFSJR 042,Reach-1         , 2
Up Type= 0
Dn Type= 3
Dn Slope=0.009
Boundary for River Rch & Prof#=WFSJR 042,Reach-1         , 3
Up Type= 0
Dn Type= 3
Dn Slope=0.009
Boundary for River Rch & Prof#=WFSJR 042,Reach-1         , 4
Up Type= 0
Dn Type= 3
Dn Slope=0.009
Boundary for River Rch & Prof#=WFSJR 042,Reach-1         , 5
Up Type= 0
Dn Type= 3
Dn Slope=0.009
Boundary for River Rch & Prof#=WFSJR 042,Reach-1         , 6
Up Type= 0
Dn Type= 3
Dn Slope=0.009
Boundary for River Rch & Prof#=WFSJR 042,Reach-1         , 7
Up Type= 0
Dn Type= 3
Dn Slope=0.009
DSS Import GetInterval= 0
DSS Import GetPeak= 0
DSS Import FillOption= 0

--- WFSJR 042.g01 (geometry) ---

Geom Title=Existing Conditions
Program Version=4.10

River Reach=WFSJR 042       ,Reach-1
Reach XY= 30
      3769308.23     10264146.84      3769245.27     10263885.17
      3769112.47     10263771.77      3769181.48     10263598.59
      3769098.47     10263394.72      3769166.28     10263327.83
      3768908.37     10263008.93      3768948.16     10262639.18
      3768868.16     10262375.96      3769038.32     10261871.85
      3768778.69     10261431.56      3768897.05     10261056.29
      3768657.41     10260974.34      3768638.58     10260908.78
      3768898.85     10260503.35      3768852.05     10260391.45
      3768690.99     10260328.43      3768639.46     10259962.77
      3768776.87     10259865.37      3768815.99     10259496.93
      3768497.61     10259310.75      3768529.64      10259236.7
      3768619.71     10259278.73      3768669.75     10259222.69
       3768607.7     10259204.67      3768643.73      10258842.4
      3768563.66     10258770.34       3768615.7     10258658.26
      3768529.64     10258670.27      3768590.66     10258539.82

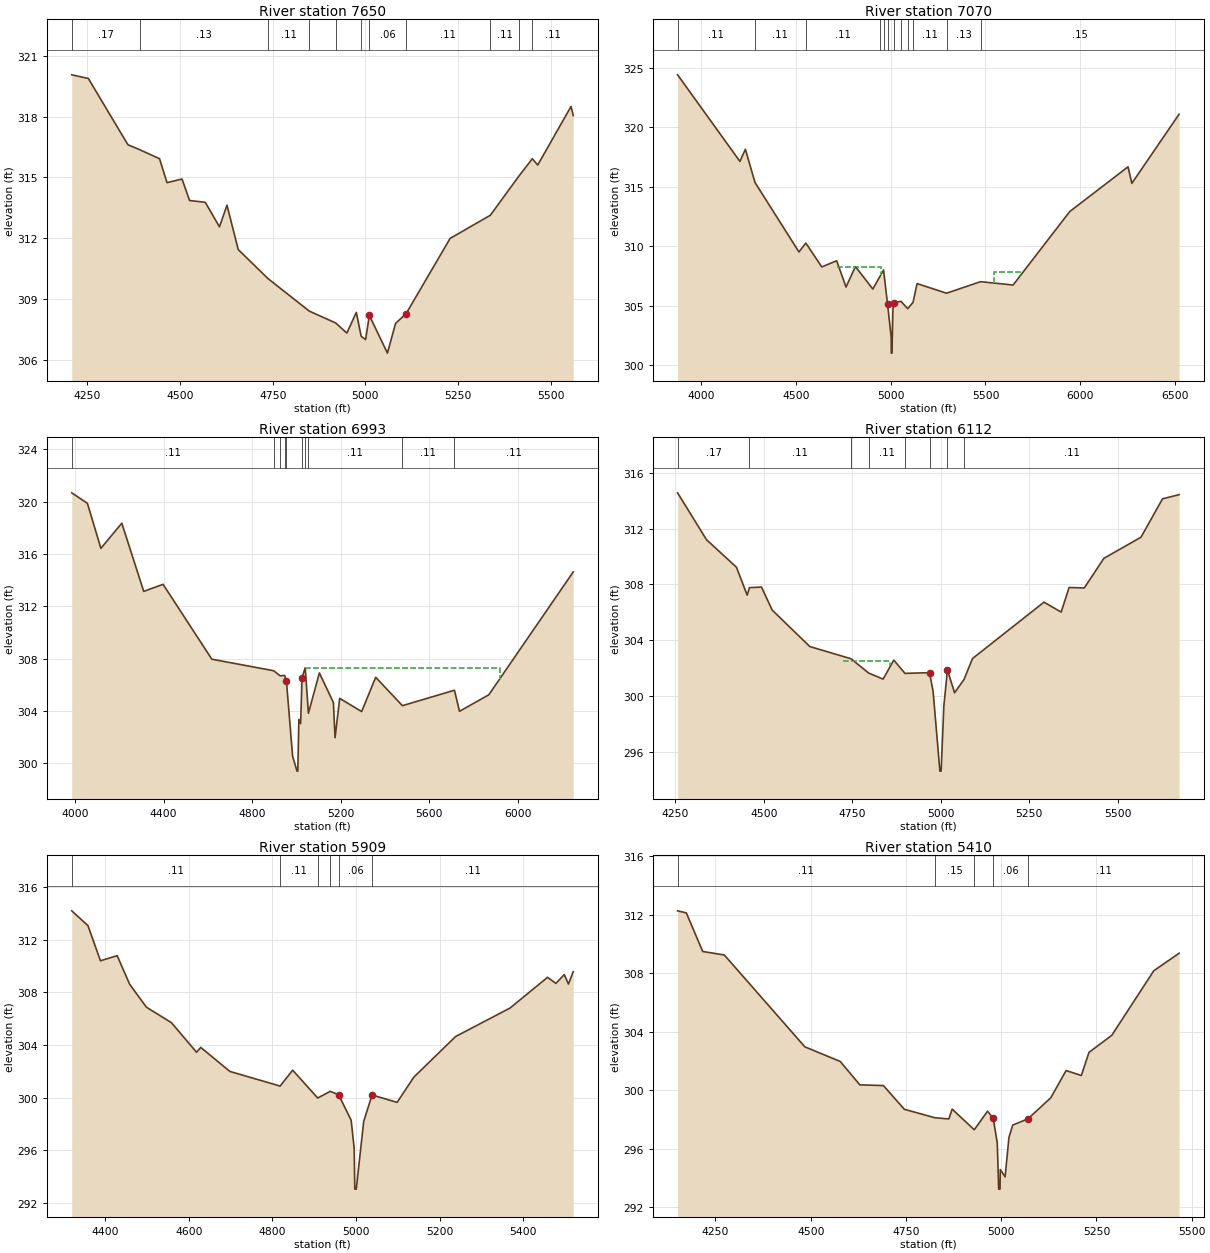
Type RM Length L Ch R = 1 ,7650    ,580,580,580
BEGIN DESCRIPTION:
WFSJR 042 11.0
END DESCRIPTION:
XS GIS Cut Line= 3
      3770082.21     10264228.31      3769127.35     10264087.25
      3768782.62     10264265.04
#Sta/Elev= 30
  4207.8  320.06  4252.6  319.88  4359.4  316.61  4390.7  316.37  4444.7  315.92
  4464.9  314.74  4505.4  314.92  4525.6  313.86  4568.2  313.77  4606.4  312.56
  4626.7  313.63    4657  311.44  4737.8     310    4849   308.4  4919.8  307.82
  4950.1  307.32  4975.6  308.34  4988.7  307.16  5000.7     307  5010.8  308.19
  5059.6  306.33  5081.5   307.8  5109.7  308.27  5228.7  311.99  5337.1  313.13
  5414.1  315.06  5450.5  315.92    5465  315.61    5555   318.5  5560.9  318.05
#Mann= 11 ,-1 , 0
  4207.8     .17       0  4390.7     .13       0  4737.8     .11       0
    4849     .11       0  4919.8     .11       0  4988.7     .11       0
  5010.8     .06       0  5109.7     .11       0  5337.1     .11       0
  5414.1     .17       0  5450.5     .11       0
Bank Sta=5010.8,5109.7
XS Rating Curve= 0 ,0
Exp/Cntr=0.3,0.1

Type RM Length L Ch R = 1 ,7070    ,77,77,77
BEGIN DESCRIPTION:
Mapping XS 1f6553a3
END DESCRIPTION:
XS GIS Cut Line= 4
      3770134.25     10264143.67      3769400.79     10263937.51
      3768877.78     10263405.83      3767751.13     10263568.33
#Sta/Elev= 30
  3875.5  324.41  4204.3  317.13  4233.2  318.15    4284  315.35  4515.8  309.51
    4552  310.26  4636.3  308.25  4714.8  308.77  4764.2  306.56  4813.8  308.28
  4905.7  306.39  4940.9  307.39  4962.2  307.99  4983.4  305.11  5002.7  302.31
  5002.9     301  5006.4     301  5011.7  304.72  5018.8  305.25  5054.1  305.36
  5089.5  304.74  5117.8  305.27    5139  306.85  5294.5  306.04    5474  307.01
  5645.8  306.73  5944.6  312.91    6252  316.67  6272.2  315.28  6521.5   321.1
#Mann= 12 ,-1 , 0
  3875.5     .11       0    4284     .11       0    4552     .11       0
  4940.9     .11       0  4962.2     .11       0  4983.4     .06       0
  5018.8     .11       0  5054.1     .11       0  5089.5     .11       0
  5117.8     .11       0  5294.5     .13       0    5474     .15       0
#XS Ineff= 3 ,-1
    4717  4948.1  308.27    5139    5468  306.85  5544.8    5680  307.82
Permanent Ineff=
       T       T       T
Bank Sta=4983.4,5018.8
XS Rating Curve= 0 ,0
Exp/Cntr=0.3,0.1

Type RM Length L Ch R = 1 ,6993    ,881,881,881
BEGIN DESCRIPTION:
WFSJR 042 10.0
END DESCRIPTION:
XS GIS Cut Line= 6
      3770056.19     10264041.69      3769442.02     10263874.58
      3769311.81     10263776.92      3768747.58     10263134.56
      3768632.85     10262952.56      3768237.59     10262986.99
#Sta/Elev= 30
  3985.2  320.67    4056  319.87  4116.9  316.43  4211.5  318.35  4310.6  313.14
    4398  313.68  4618.4  307.96  4897.9  307.08  4926.8  306.69  4947.6  306.72
  4955.6  306.28  4983.4  300.56  5003.5  299.41    5007  299.41  5011.7  303.36
  5019.7  303.04  5026.1  306.54  5040.5  307.31  5054.9  303.83  5104.4  306.91
  5167.9  304.65  5175.3  301.96  5196.3  304.97  5295.5  303.96    5359  306.58
  5479.7  304.41    5715  305.59  5737.7  303.98  5870.2  305.24  6251.9  314.63
#Mann= 10 ,-1 , 0
  3985.2     .11       0  4897.9     .11       0  4926.8     .11       0
  4947.6     .11       0  4955.6     .06       0  5026.1     .11       0
  5040.5     .11       0  5054.9     .11       0  5479.7     .11       0
    5715     .11       0
#XS Ineff= 1 ,-1
  5040.5    5920  307.31
Permanent Ineff=
       T
Bank Sta=4955.6,5026.1
XS Rating Curve= 0 ,0
Exp/Cntr=0.3,0.1

Type RM Length L Ch R = 1 ,6112    ,203,203,203
BEGIN DESCRIPTION:
WFSJR 042 9.0
END DESCRIPTION:
XS GIS Cut Line= 3
      3769652.53     10263017.38      3768634.73     10262876.32
      3768251.72     10262941.23
#Sta/Elev= 30
  4256.9  314.56  4338.3  311.21  4423.2  309.23  4453.4  307.23  4459.7  307.77
  4493.8  307.81  4524.1  306.16  4630.4  303.55  4746.2  302.68  4796.7  301.65
  4837.1  301.22  4867.4  302.58  4898.9  301.63  4968.3  301.68  4978.4  300.33
  4997.5  294.63    5001  294.63  5008.7   299.3  5018.8  301.87    5039  300.24
    5066  301.21  5089.5  302.69  5291.4  306.73  5339.9  306.02  5362.4  307.78
  5405.3  307.75  5460.6  309.87  5565.3  311.38  5626.1  314.13  5672.9  314.43
#Mann= 8 ,-1 , 0
  4256.9     .17       0  4459.7     .11       0  4746.2     .11       0
  4796.7     .11       0  4898.9     .11       0  4968.3     .06       0
  5018.8     .17       0    5066     .11       0
#XS Ineff= 1 ,-1
    4725  4857.3  302.53
Permanent Ineff=
       F
Bank Sta=4968.3,5018.8
XS Rating Curve= 0 ,0
Exp/Cntr=0.3,0.1

Type RM Length L Ch R = 1 ,5909    ,499,499,499
BEGIN DESCRIPTION:
WFSJR 042 8.0
END DESCRIPTION:
XS GIS Cut Line= 3
       3769626.5     10262746.11      3768946.28     10262736.04
       3768426.4     10262730.92
#Sta/Elev= 30
  4319.7  314.21  4358.4  313.09  4388.4  310.41  4428.4   310.8  4458.4  308.62
  4498.4  306.88  4558.4   305.7  4618.4  303.45  4628.4  303.82  4698.4  301.99
  4818.4  300.88  4848.4  302.09  4908.4  299.97  4938.4  300.48  4958.4  300.22
  4988.4  298.28  4995.6  296.15  4997.1  293.04  5000.6  293.04  5018.4  298.19
  5038.4   300.2  5098.4  299.64  5138.4  301.56  5238.4  304.65  5368.4  306.81
  5458.4  309.15  5478.4  308.69  5498.4  309.36  5508.4  308.64  5519.9  309.58
#Mann= 6 ,-1 , 0
  4319.7     .11       0  4818.4     .11       0  4908.4     .15       0
  4938.4     .11       0  4958.4     .06       0  5038.4     .11       0
#XS Ineff= 1 ,-1
    4650  4848.4  302.09
Permanent Ineff=
       F
Bank Sta=4958.4,5038.4
XS Rating Curve= 0 ,0
Exp/Cntr=0.3,0.1

Type RM Length L Ch R = 1 ,5410    ,482,482,482
BEGIN DESCRIPTION:
WFSJR 042 7.0
END DESCRIPTION:
XS GIS Cut Line= 3
      3769689.45     10262546.47      3768888.19     10262264.56
      3768421.41     10262281.64
#Sta/Elev= 30
  4150.6  312.27  4173.5  312.13  4216.6  309.49  4273.3  309.25  4484.7  302.97
  4577.6  301.97    4629  300.37  4690.9  300.32  4745.9   298.7  4826.2  298.12
  4862.6  298.04  4871.4  298.71  4929.4   297.3  4964.3  298.57  4979.2  298.08
  4989.8   296.4  4993.5  293.24    4997  293.24  4997.7  294.58  5010.4  294.08
  5020.4  296.77  5030.4  297.62  5070.4  298.05  5130.4  299.49  5170.5  301.35
  5210.5  301.01  5230.5  302.59  5290.5  303.76  5400.6  308.17  5467.1  309.37
#Mann= 5 ,-1 , 0
  4150.6     .11       0  4826.2     .15       0  4929.4     .11       0
  4979.2     .06       0  5070.4     .11       0
Bank Sta=4979.2,5070.4
XS Rating Curve= 0 ,0
Exp/Cntr=0.3,0.1

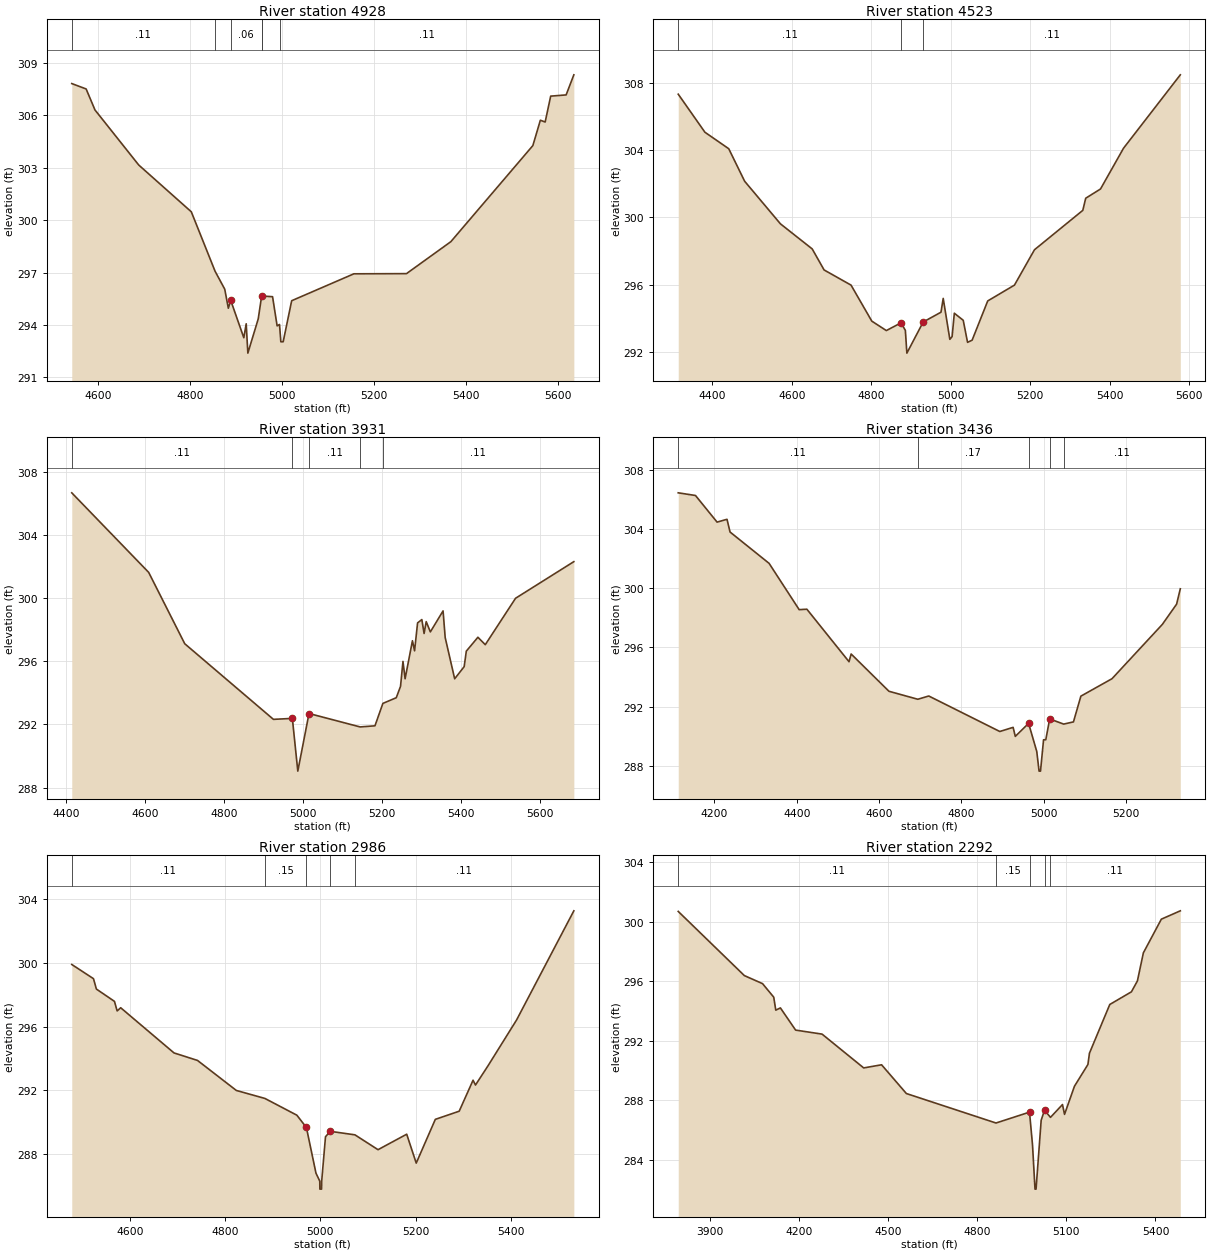
Type RM Length L Ch R = 1 ,4928    ,405,405,405
BEGIN DESCRIPTION:
WFSJR 042 6.0
END DESCRIPTION:
XS GIS Cut Line= 3
      3769467.88     10261961.08      3769028.34     10261834.51
      3768417.86     10262011.07
#Sta/Elev= 30
  4542.6  307.82  4573.9  307.51  4593.1  306.31  4688.3  303.16  4802.8  300.48
  4854.5  297.08  4875.6  296.05  4883.4  294.96  4888.6  295.41  4917.1  293.27
  4922.3  294.07  4925.9  292.39  4948.5  294.35    4956  295.67  4956.2  295.66
  4979.7  295.62  4989.6  293.95  4994.8  294.03  4997.7  293.04  5002.8  293.04
  5021.3  295.39  5156.7  296.93  5271.2  296.94  5367.8  298.77  5546.3  304.27
  5562.6  305.72  5573.1  305.62  5585.1   307.1  5618.7  307.17  5635.5  308.32
#Mann= 6 ,-1 , 0
  4542.6     .11       0  4854.5     .15       0  4888.6     .06       0
    4956     .11       0  4956.2     .15       0  4994.8     .11       0
Bank Sta=4888.6,4956
XS Rating Curve= 0 ,0
Exp/Cntr=0.3,0.1

Type RM Length L Ch R = 1 ,4523    ,592,592,592
BEGIN DESCRIPTION:
WFSJR 042 5.0
END DESCRIPTION:
XS GIS Cut Line= 3
        3769505.     10261450.54      3768979.78     10261433.17
      3768317.85     10261761.07
#Sta/Elev= 30
  4313.9  307.32  4381.1  305.06  4441.1  304.08  4481.1  302.15  4571.2  299.62
  4651.2  298.13  4681.2  296.88    4749  295.98  4801.3  293.84  4837.9  293.28
    4875  293.74  4885.8  293.29  4889.6  291.94  4930.7  293.79  4975.5  294.37
  4981.1  295.19  4997.8  292.76  5003.5  292.92  5009.1  294.31  5031.5  293.89
  5042.4  292.58  5053.9  292.71  5093.2  295.04  5160.5  295.98  5210.9  298.08
  5332.6  300.42  5339.9  301.14  5377.2  301.69  5435.1  304.11  5578.1  308.47
#Mann= 3 , 0 , 0
  4313.9     .11       0    4875     .06       0  4930.7     .11       0
Bank Sta=4875,4930.7
XS Rating Curve= 0 ,0
Exp/Cntr=0.3,0.1

Type RM Length L Ch R = 1 ,3931    ,495,495,495
BEGIN DESCRIPTION:
WFSJR 042 4.0
END DESCRIPTION:
XS GIS Cut Line= 3
      3769467.81     10261211.06      3768897.05     10261080.08
      3768261.09     10261339.13
#Sta/Elev= 30
  4414.4  306.67  4609.3  301.63  4700.7  297.11  4925.4  292.32  4973.4  292.38
  4987.2  289.04  5015.6  292.69  5145.1  291.84  5182.7  291.91  5202.8  293.33
  5236.7  293.69  5247.5  294.41  5253.7  295.99  5259.1  294.89  5277.7   297.3
  5283.1  296.66  5290.7  298.43  5301.5  298.64  5307.2  297.76  5312.6  298.51
  5323.1  297.86  5355.3  299.19  5360.7   297.5  5384.7  294.89  5408.8  295.66
  5414.2  296.64  5443.6  297.52  5462.3  297.05    5539  299.99  5686.7  302.31
#Mann= 5 ,-1 , 0
  4414.4     .11       0  4973.4     .06       0  5015.6     .11       0
  5145.1     .17       0  5202.8     .11       0
Bank Sta=4973.4,5015.6
XS Rating Curve= 0 ,0
Exp/Cntr=0.3,0.1

Type RM Length L Ch R = 1 ,3436    ,450,450,450
BEGIN DESCRIPTION:
WFSJR 042 3.0
END DESCRIPTION:
XS GIS Cut Line= 3
      3769517.81     10261111.06      3768671.42     10260843.72
      3768367.84     10260711.07
#Sta/Elev= 30
  4112.4  306.45  4154.3  306.27  4206.7  304.47  4230.8  304.66  4238.2   303.8
    4333  301.68    4406  298.55  4424.7  298.58    4527  295.03  4532.2  295.55
    4624  293.03    4694  292.49  4720.6  292.71  4893.1  290.31  4925.4  290.59
  4930.7  289.98    4963  290.86  4982.8  288.96  4988.4  287.63  4991.9  287.63
  4999.3  289.75  5004.7  289.75  5014.2  291.16  5048.2  290.81  5071.9  290.96
  5089.9   292.7  5165.5  293.88  5287.6  297.55  5322.3  298.92  5331.3  299.96
#Mann= 5 ,-1 , 0
  4112.4     .11       0    4694     .17       0    4963     .09       0
  5014.2     .17       0  5048.2     .11       0
Bank Sta=4963,5014.2
XS Rating Curve= 0 ,0
Exp/Cntr=0.3,0.1

Type RM Length L Ch R = 1 ,2986    ,694,694,694
BEGIN DESCRIPTION:
WFSJR 042 2.0
END DESCRIPTION:
XS GIS Cut Line= 3
      3769367.86     10260711.08      3768994.97     10260506.52
      3768367.83     10260461.07
#Sta/Elev= 30
  4478.2  299.89  4523.8     299  4529.9  298.35  4567.8  297.58  4573.5  296.98
  4580.9  297.18  4692.9  294.35  4742.2  293.88  4823.7     292  4883.7   291.5
  4950.8  290.45  4970.8  289.68  4990.9  286.82  4998.9  286.32  4999.1  285.82
  5002.6  285.82  5002.9  286.32  5010.9   289.1  5020.9  289.44  5072.7  289.22
  5121.2  288.29  5181.4  289.26  5201.4  287.45  5241.5  290.19  5291.6   290.7
  5320.7  292.64  5325.8  292.34  5351.8  293.53    5412  296.41  5532.3  303.25
#Mann= 5 ,-1 , 0
  4478.2     .11       0  4883.7     .15       0  4970.8     .09       0
  5020.9     .15       0  5072.7     .11       0
Bank Sta=4970.8,5020.9
XS Rating Curve= 0 ,0
Exp/Cntr=0.3,0.1

Type RM Length L Ch R = 1 ,2292    ,517,517,517
BEGIN DESCRIPTION:
Mapping XS 6f5d9083
END DESCRIPTION:
XS GIS Cut Line= 3
      3769784.53     10260405.24      3768929.51     10259971.22
      3768204.64     10260066.71
#Sta/Elev= 30
  3793.7  300.69  4016.3  296.38  4077.5  295.84  4115.2  294.93    4122  294.06
  4137.6  294.21  4188.8  292.72  4277.9  292.45    4418  290.18  4478.2  290.39
  4561.6  288.46  4863.3  286.48  4976.1  287.21  4986.2  285.02  4994.6  282.04
  4998.1  282.04  5015.4  286.67  5026.6  287.34  5046.7  286.86  5087.1  287.72
    5094  287.06  5127.4  288.95  5172.7  290.41  5177.9  291.17  5246.3  294.44
  5319.1  295.29  5339.3  296.02  5359.4  297.91  5419.9  300.17  5483.7  300.73
#Mann= 5 ,-1 , 0
  3793.7     .11       0  4863.3     .15       0  4976.1     .09       0
  5026.6     .15       0  5046.7     .11       0
Bank Sta=4976.1,5026.6
XS Rating Curve= 0 ,0
Exp/Cntr=0.3,0.1

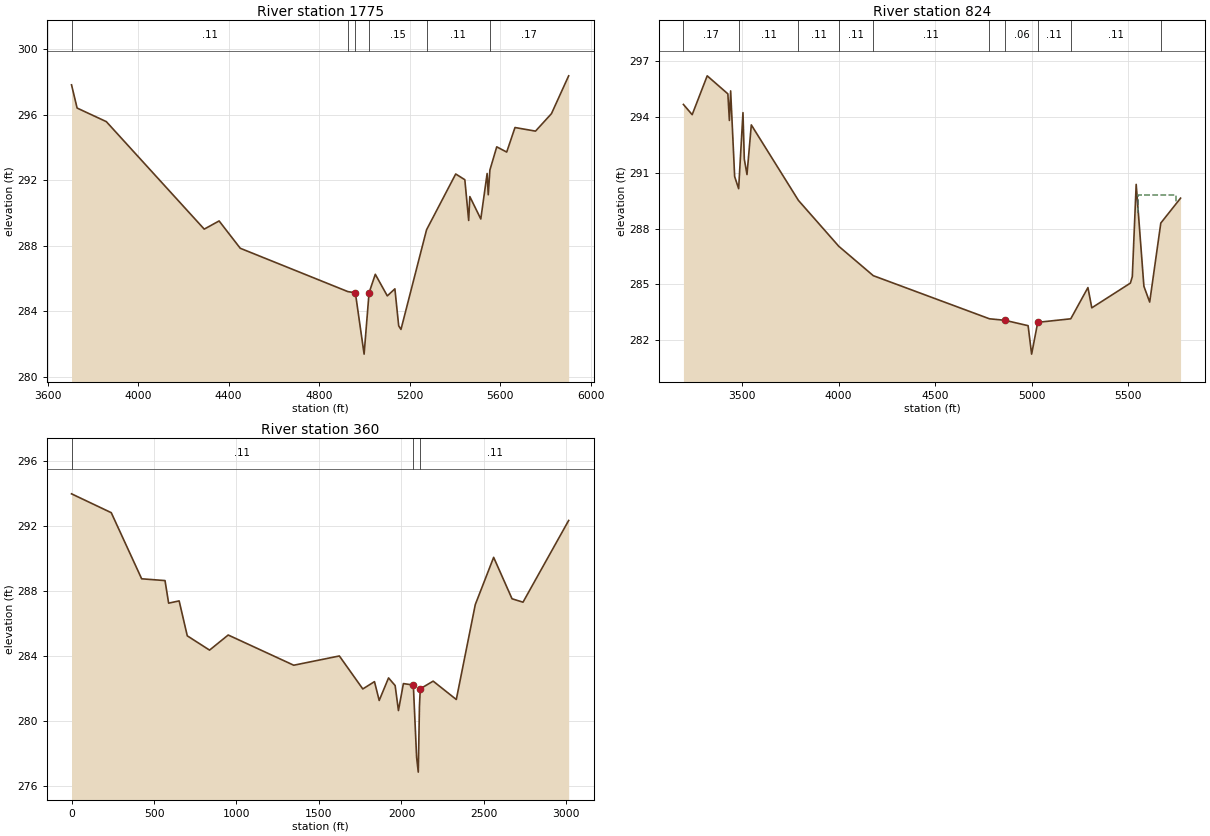
Type RM Length L Ch R = 1 ,1775    ,951,951,951
BEGIN DESCRIPTION:
Mapping XS f944fbe2
END DESCRIPTION:
XS GIS Cut Line= 3
      3769880.01     10260262.01       3768886.1     10259597.96
      3767892.53     10259719.44
#Sta/Elev= 30
  3706.1  297.84  3730.8  296.42  3859.9  295.59  4292.4  289.02  4358.1  289.52
  4451.6  287.85  4927.2   285.2  4960.1  285.13  4998.7  281.38  5020.6  285.13
  5048.2  286.26  5101.2  284.94  5134.7  285.37  5151.5  283.11  5161.6  282.89
  5274.6  288.98  5403.4  292.39  5443.7  292.04  5460.7  289.55  5465.8  291.01
  5514.2  289.64  5542.2  292.42  5547.2  291.12  5554.4  292.63  5584.7  294.05
  5628.7  293.73  5665.3  295.23    5756  295.01  5826.5  296.08  5902.4  298.39
#Mann= 6 ,-1 , 0
  3706.1     .11       0  4927.2     .15       0  4960.1     .09       0
  5020.6     .15       0  5274.6     .11       0  5554.4     .17       0
Bank Sta=4960.1,5020.6
XS Rating Curve= 0 ,0
Exp/Cntr=0.3,0.1

Type RM Length L Ch R = 1 ,824     ,464,464,464
BEGIN DESCRIPTION:
WFSJR 042 1.0
END DESCRIPTION:
XS GIS Cut Line= 3
       3770123.1     10260110.13      3768933.85     10259146.57
      3767887.88     10259120.53
#Sta/Elev= 30
  3195.2  294.68  3240.6  294.13  3318.5  296.22  3425.6  295.25  3433.5  293.82
    3440  295.41  3460.8   290.8  3481.5  290.15  3503.9  294.24  3510.8  291.74
  3524.7  290.91  3547.1  293.58  3791.3  289.52  4000.6  287.05  4179.4  285.47
  4781.7  283.15  4861.8  283.07  4981.9  282.78  5000.1  281.25  5031.9  282.96
    5203  283.15    5292  284.83    5312  283.74    5512  285.07    5522  285.42
  5542.1  290.38  5582.1   284.9  5612.1  284.05  5669.7   288.3  5772.1  289.64
#Mann= 10 ,-1 , 0
  3195.2     .17       0  3481.5     .11       0  3791.3     .11       0
  4000.6     .11       0  4179.4     .11       0  4781.7     .11       0
  4861.8     .06       0  5031.9     .11       0    5203     .11       0
  5669.7     .11       0
#XS Ineff= 1 ,-1
  5553.3    5750  289.81
Permanent Ineff=
       T
Bank Sta=4861.8,5031.9
XS Rating Curve= 0 ,0
Exp/Cntr=0.3,0.1

Type RM Length L Ch R = 1 ,360     ,0,0,0
XS GIS Cut Line= 4
      3770207.89     10259990.91      3768786.45      10258771.3
      3768294.91     10258739.83      3767686.19     10258962.27
#Sta/Elev= 30
       0  294.01   240.8  292.85   425.2  288.78   566.8  288.67   588.7  287.28
   652.4  287.42   701.7  285.27   836.7  284.39   949.8  285.32  1347.1  283.46
  1623.6  284.03  1765.7     282  1836.5  282.45  1865.1  281.29  1921.7  282.68
  1961.7  282.21  1981.8  280.67  2011.8  282.33    2072  282.24    2092  277.78
    2102  276.88  2109.1  280.93  2114.1  282.01  2192.2  282.48  2332.5  281.35
  2447.5  287.19  2558.9   290.1  2670.4  287.55  2736.8  287.34  3013.6  292.37
#Mann= 3 , 0 , 0
       0     .11       0    2072     .06       0  2114.1     .11       0
Bank Sta=2072,2114.1
XS Rating Curve= 0 ,0
Exp/Cntr=0.3,0.1

Chan Stop Cuts=-1
Use User Specified Reach Order=0
Composite Channel Slope=5