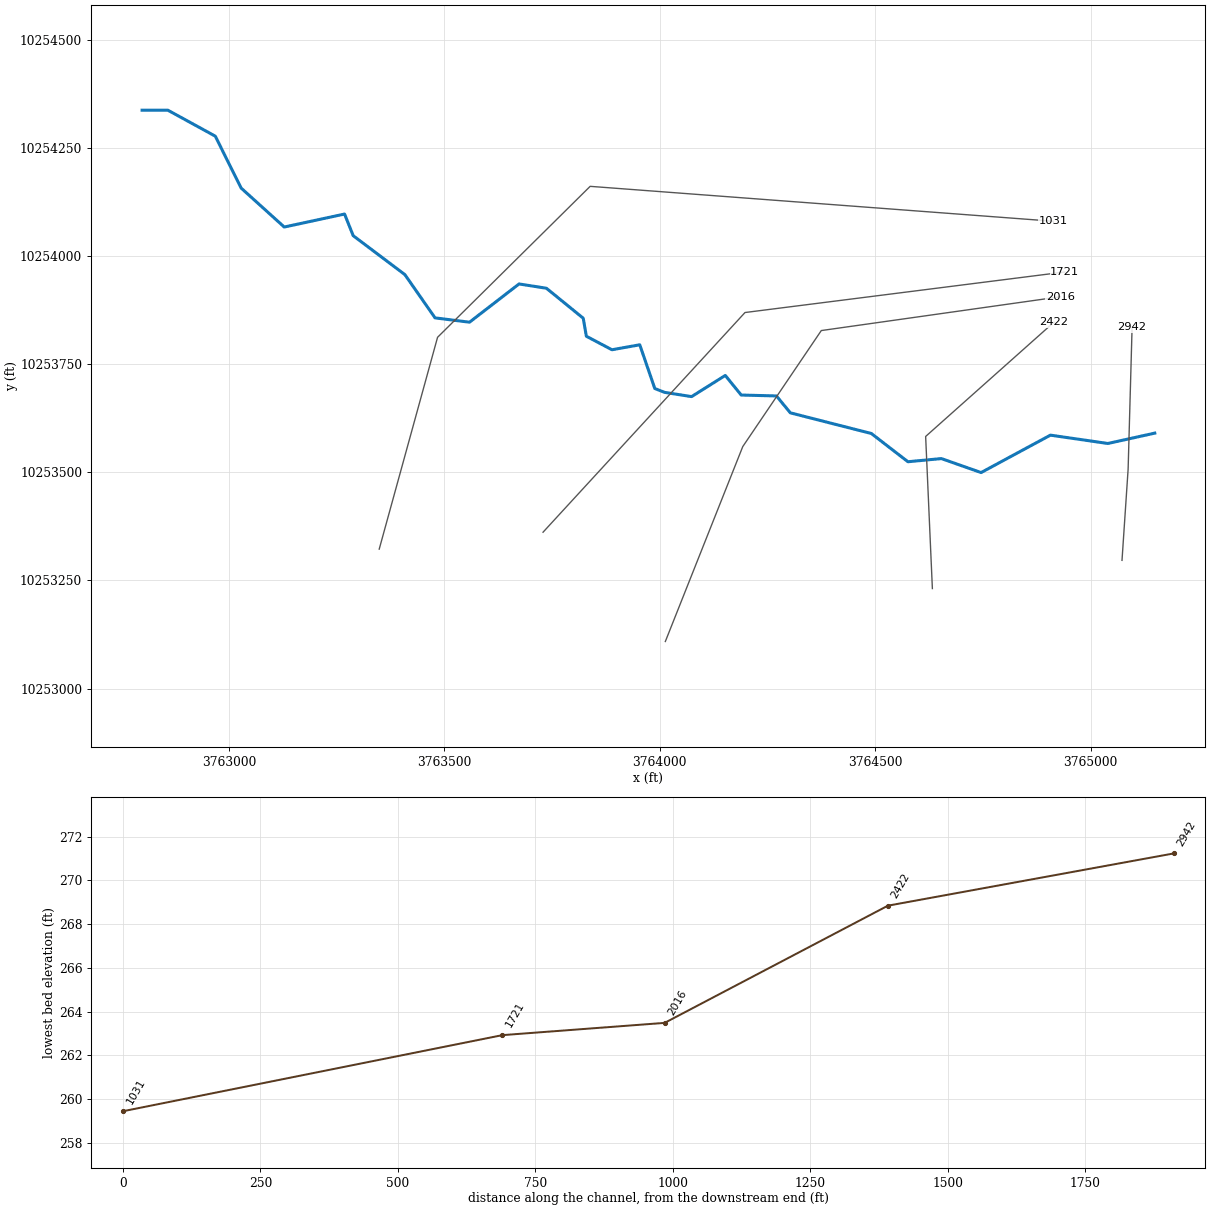
--- WFSJR 043.prj (project) ---

Proj Title=WFSJR 043 Base Level Engineering
Current Plan=p01
Default Exp/Contr=0.3,0.1
English Units
Geom File=g01
Flow File=f01
Plan File=p01
Y Axis Title=Elevation
X Axis Title(PF)=Main Channel Distance
X Axis Title(XS)=Station
BEGIN DESCRIPTION:
WFSJR 043
END DESCRIPTION:
DSS Export Rating Curves= 0
DSS Export Rating Curve Sorted= 0
DSS Export Volume Flow Curves= 0
DXF OffsetX= 0
DXF OffsetY= 0
DXF ScaleX= 1
DXF ScaleY= 10

--- WFSJR 043.p01 (plan) ---

Plan Title=Multiple Run
Program Version=4.10
Short Identifier=Multiple
Geom File=g01
Flow File=f01
Subcritical Flow
K Sum by GR= 0
Std Step Tol= 0.01
Critical Tol= 0.01
Num of Std Step Trials= 20
Max Error Tol= 0.3
Flow Tol Ratio= 0.001
Split Flow NTrial= 30
Split Flow Tol= 0.02
Split Flow Ratio= 0.02
Log Output Level= 0
Friction Slope Method= 1
Unsteady Friction Slope Method= 2
Unsteady Bridges Friction Slope Method= 1
Parabolic Critical Depth
Global Vel Dist= 1 , 1 , 1
Global Log Level= 0
CheckData=True
Encroach Param=-1 ,0,0, 0
BEGIN DESCRIPTION:
Multiple Run
END DESCRIPTION:
Computation Interval=1HOUR
Output Interval=1HOUR
Run HTab= 0
Run UNet= 0
Run PostProcess= 0
Run WQNet= 0
UNET Theta= 1
UNET Theta Warmup= 1
UNET ZTol= 0.02
UNET ZSATol= 0.05
UNET MxIter= 20
UNET MaxInSteps= 0
UNET DtIC= 0
UNET DtMin= 0
UNET MaxCRTS= 20
UNET WFStab= 2
UNET SFStab= 1
UNET WFX= 1
UNET SFX= 1
UNET DSS MLevel= 4
UNET DZMax Abort= 100
UNET Convert EG Bridges= 0
UNET Use Existing IB Tables=-1
UNET Froude Reduction=False
UNET Froude Limit= 1
UNET Froude Power= 10
UNET Time Slicing=0,0, 5
UNET Junction Losses=0
Instantaneous Interval=1HOUR
Write IC File= 0
Write IC File at Sim End=0
Echo Input=False
Echo Parameters=False
Echo Output=False
Write Detailed= 0
WQ AD Non Conservative
WQ ULTIMATE=-1
WQ Max Comp Step=1HOUR
WQ Output Interval=15MIN
WQ Output Selected Increments= 0
WQ Output face flow=0
WQ Output face velocity=0
WQ Output face area=0
WQ Output face dispersion=0
WQ Output cell volume=0
WQ Output cell surface area=0
WQ Output cell continuity=0
WQ Output cumulative cell continuity=0
WQ Output face conc=0
WQ Output face dconc_dx=0
WQ Output face courant=0
WQ Output face peclet=0
WQ Output face adv mass=0
WQ Output face disp mass=0
WQ Output cell mass=0
WQ Output cell source sink temp=0
WQ Output cell source sink nsm=0
WQ Output MaxMinRange=-1
WQ Daily Max Min Mean=-1
WQ Daily Range=0
WQ Daily Time=0
WQ Create Restart=0
WQ Fixed Restart=0
WQ System Summary=0
WQ Use Fixed Temperature=0
Sorting and Armoring Iterations= 10
XS Update Threshold= 0.02
Hydraulics Update Threshold= 0.02
Energy Slope Method= 1
Volume Change Method= 0
XS Weighting Method= 0
Number of US Weighted Cross Sections= 1
Number of DS Weighted Cross Sections= 1
Upstream XS Weight=0.25
Main XS Weight=0.5
Downstream XS Weight=0.25
Number of DS XS's Weighted with US Boundary= 1
Upstream Boundary Weight= 1
Weight of XSs Associated with US Boundary= 0
Number of US XS's Weighted with DS Boundary= 1
Downstream Boundary Weight= 0.5
Weight of XSs Associated with DS Boundary= 0.5
Sediment Output Level= 4
Mass or Volume Output= 0
Output Increment Type= 1
Profile and TS Output Increment= 10
XS Output Flag= 0
XS Output Increment= 10
Disregard all LS=0
Disregard all Conn=0
Disregard all Breaches=0
Disregard all Pumps=0

--- WFSJR 043.f01 (steady flow) ---

Flow Title=Multiple
Program Version=4.10
Number of Profiles= 7
Profile Names=10-year,25-year,50-year,1pct_min,100-year,1pct_plu,500-year
River Rch & RM=WFSJR 043,Reach-1         ,2942
     440     584     780     343    1037    3132    1894
Boundary for River Rch & Prof#=WFSJR 043,Reach-1         , 1
Up Type= 0
Dn Type= 3
Dn Slope=0.005
Boundary for River Rch & Prof#=WFSJR 043,Reach-1         , 2
Up Type= 0
Dn Type= 3
Dn Slope=0.005
Boundary for River Rch & Prof#=WFSJR 043,Reach-1         , 3
Up Type= 0
Dn Type= 3
Dn Slope=0.005
Boundary for River Rch & Prof#=WFSJR 043,Reach-1         , 4
Up Type= 0
Dn Type= 3
Dn Slope=0.005
Boundary for River Rch & Prof#=WFSJR 043,Reach-1         , 5
Up Type= 0
Dn Type= 3
Dn Slope=0.005
Boundary for River Rch & Prof#=WFSJR 043,Reach-1         , 6
Up Type= 0
Dn Type= 3
Dn Slope=0.005
Boundary for River Rch & Prof#=WFSJR 043,Reach-1         , 7
Up Type= 0
Dn Type= 3
Dn Slope=0.005
DSS Import GetInterval= 0
DSS Import GetPeak= 0
DSS Import FillOption= 0

--- WFSJR 043.g01 (geometry) ---

Geom Title=Existing Conditions
Program Version=4.10

River Reach=WFSJR 043       ,Reach-1
Reach XY= 30
       3765148.7     10253590.45      3765039.85      10253566.5
      3764906.51     10253585.77      3764745.58     10253499.31
      3764653.39      10253531.6      3764575.78     10253524.31
      3764490.85     10253589.59      3764302.87     10253637.33
      3764270.58     10253676.39      3764188.81     10253678.48
      3764151.83     10253723.79       3764073.7     10253674.83
      3764010.68     10253684.73      3763988.28     10253693.58
      3763953.39     10253794.62      3763888.81     10253783.16
      3763829.43     10253814.41      3763822.14     10253856.08
      3763736.72     10253925.35      3763673.18     10253935.25
      3763558.23     10253846.84      3763478.23     10253856.84
      3763408.23     10253956.84      3763288.23     10254046.84
      3763268.23     10254096.84      3763128.23     10254066.84
      3763028.23     10254156.84      3762968.23     10254276.84
      3762858.23     10254336.84      3762798.23     10254336.84

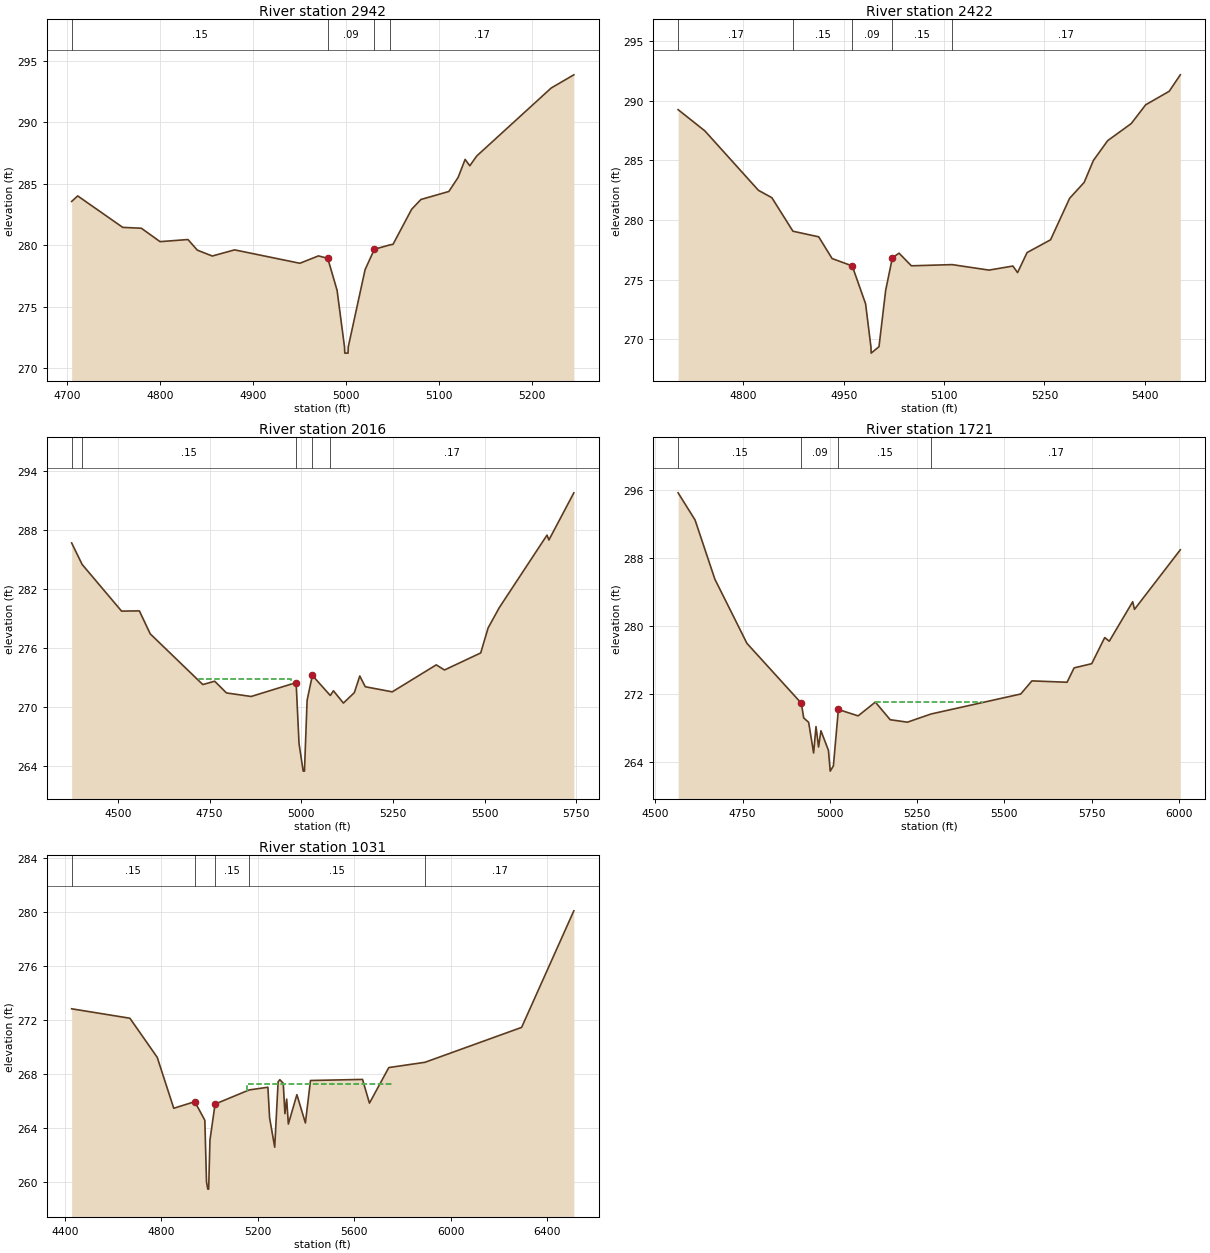
Type RM Length L Ch R = 1 ,2942    ,520,520,520
BEGIN DESCRIPTION:
WFSJR 043 2.0
END DESCRIPTION:
XS GIS Cut Line= 3
      3765072.63     10253296.34      3765086.84     10253507.34
      3765096.06     10253835.33
#Sta/Elev= 30
    4705  283.57  4711.5  284.02  4759.9  281.46  4779.9  281.39    4800   280.3
    4830  280.47    4840  279.61  4856.1  279.13  4880.1  279.63  4950.2  278.54
  4970.2  279.14  4980.2  278.94  4990.2  276.34  4998.2  271.73  4998.5  271.23
    5002  271.23  5002.2  271.73  5020.3  278.02  5030.3  279.68  5046.7  280.03
  5050.3  280.08  5070.3  282.93  5080.3  283.73  5110.3  284.38  5120.3  285.53
  5127.8  286.99  5132.8  286.47  5140.3  287.27  5220.3   292.8  5244.6  293.87
#Mann= 4 ,-1 , 0
    4705     .15       0  4980.2     .09       0  5030.3     .15       0
  5046.7     .17       0
Bank Sta=4980.2,5030.3
XS Rating Curve= 0 ,0
Exp/Cntr=0.3,0.1

Type RM Length L Ch R = 1 ,2422    ,406,406,406
BEGIN DESCRIPTION:
Mapping XS 0f974487
END DESCRIPTION:
XS GIS Cut Line= 3
      3764632.52     10253231.15       3764616.9     10253582.75
      3764915.07     10253847.21
#Sta/Elev= 30
  4702.6  289.25  4742.6  287.47  4822.6  282.49  4842.7  281.87  4874.2  279.06
  4912.7  278.59  4932.7  276.77  4962.8  276.15  4982.8  272.97  4990.8  269.34
  4991.1  268.84  5002.8  269.38  5012.8  274.11  5022.8  276.83  5032.8  277.22
  5051.2  276.16  5112.1  276.26  5167.2   275.8  5202.9  276.14  5209.9  275.59
  5224.1  277.27  5259.2  278.34  5287.7  281.82  5309.4  283.15  5323.2  284.99
  5344.5  286.65  5379.7  288.08  5401.4  289.66  5436.5  290.79  5453.1  292.17
#Mann= 5 ,-1 , 0
  4702.6     .17       0  4874.2     .15       0  4962.8     .09       0
  5022.8     .15       0  5112.1     .17       0
#XS Ineff= 1 ,-1
  5032.8    5235  277.22
Permanent Ineff=
       F
Bank Sta=4962.8,5022.8
XS Rating Curve= 0 ,0
Exp/Cntr=0.3,0.1

Type RM Length L Ch R = 1 ,2016    ,295,295,295
BEGIN DESCRIPTION:
Mapping XS 33c4bd72
END DESCRIPTION:
XS GIS Cut Line= 4
      3764012.74     10253108.81      3764192.42     10253559.31
      3764374.71     10253827.54      3764929.41     10253905.67
#Sta/Elev= 30
    4374  286.65  4402.6  284.47  4510.1  279.73  4558.7  279.75  4588.3  277.42
  4731.7  272.27    4764  272.61  4796.3  271.42  4863.5  271.06  4986.2  272.47
  4994.1  266.28  5005.4  263.48  5008.9  263.48  5016.1  270.67  5030.4   273.2
  5079.4  271.16  5087.9  271.64  5115.1  270.39  5144.9  271.45  5159.8  273.14
  5174.7  272.05  5248.3  271.53  5368.3  274.27  5390.7  273.75  5489.5  275.48
  5509.7  278.02    5540  280.07  5670.4  287.45  5675.5  286.95  5743.5  291.74
#Mann= 5 ,-1 , 0
    4374     .11       0  4402.6     .15       0  4986.2     .09       0
  5030.4     .15       0  5079.4     .17       0
#XS Ineff= 2 ,-1
    4720  4971.3  272.83  5030.4    5335   273.2
Permanent Ineff=
       F       F
Bank Sta=4986.2,5030.4
XS Rating Curve= 0 ,0
Exp/Cntr=0.3,0.1

Type RM Length L Ch R = 1 ,1721    ,690,690,690
BEGIN DESCRIPTION:
Mapping XS 40ec504f
END DESCRIPTION:
XS GIS Cut Line= 3
      3763728.89     10253361.41      3764197.63     10253869.21
      3764939.77     10253962.95
#Sta/Elev= 30
  4565.2  295.61  4613.8  292.42  4670.5  285.47  4762.4  277.93  4918.3   270.9
  4925.1  269.17  4939.3  268.65  4953.5  265.05  4960.3  268.15  4967.7  265.76
  4974.5  267.66    4996  265.36  5001.1  262.92  5010.2  263.54  5024.4  270.16
  5081.1  269.41  5130.4  271.03  5172.9  268.96  5222.3  268.67    5290  269.63
  5547.1  271.98    5579  273.52  5679.8  273.36    5700  275.05  5750.4  275.54
  5787.7  278.61  5800.8  278.18  5867.9  282.82    5873  281.92  6004.3  288.92
#Mann= 4 ,-1 , 0
  4565.2     .15       0  4918.3     .09       0  5024.4     .15       0
    5290     .17       0
#XS Ineff= 1 ,-1
  5130.4    5435  271.03
Permanent Ineff=
       F
Bank Sta=4918.3,5024.4
XS Rating Curve= 0 ,0
Exp/Cntr=0.3,0.1

Type RM Length L Ch R = 1 ,1031    ,0,0,0
BEGIN DESCRIPTION:
WFSJR 043 1.0
END DESCRIPTION:
XS GIS Cut Line= 4
      3763348.66     10253322.31      3763484.08     10253811.92
      3763838.25     10254160.88      3764913.34     10254080.18
#Sta/Elev= 30
    4428  272.82  4669.7  272.12    4783  269.22  4851.6  265.44  4938.9  265.93
  4980.5  264.55  4987.5  259.96  4992.9  259.44  4996.4  259.44  5001.7  263.07
  5022.9  265.75  5164.4   266.8  5242.1     267  5249.2  264.73  5270.4  262.55
  5284.5   267.4  5291.7  267.56  5305.8  267.29  5312.8  265.04    5320  266.12
    5327  264.27  5362.4  266.45  5397.7  264.35  5418.8   267.5  5634.7  267.58
  5663.4  265.82  5743.7  268.46  5893.6  268.85  6294.6  271.44  6511.3  280.09
#Mann= 5 ,-1 , 0
    4428     .15       0  4938.9     .09       0  5022.9     .15       0
  5164.4     .15       0  5893.6     .17       0
#XS Ineff= 1 ,-1
  5157.3    5760  267.23
Permanent Ineff=
       T
Bank Sta=4938.9,5022.9
XS Rating Curve= 0 ,0
Exp/Cntr=0.3,0.1

Chan Stop Cuts=-1
Use User Specified Reach Order=0
Composite Channel Slope=5