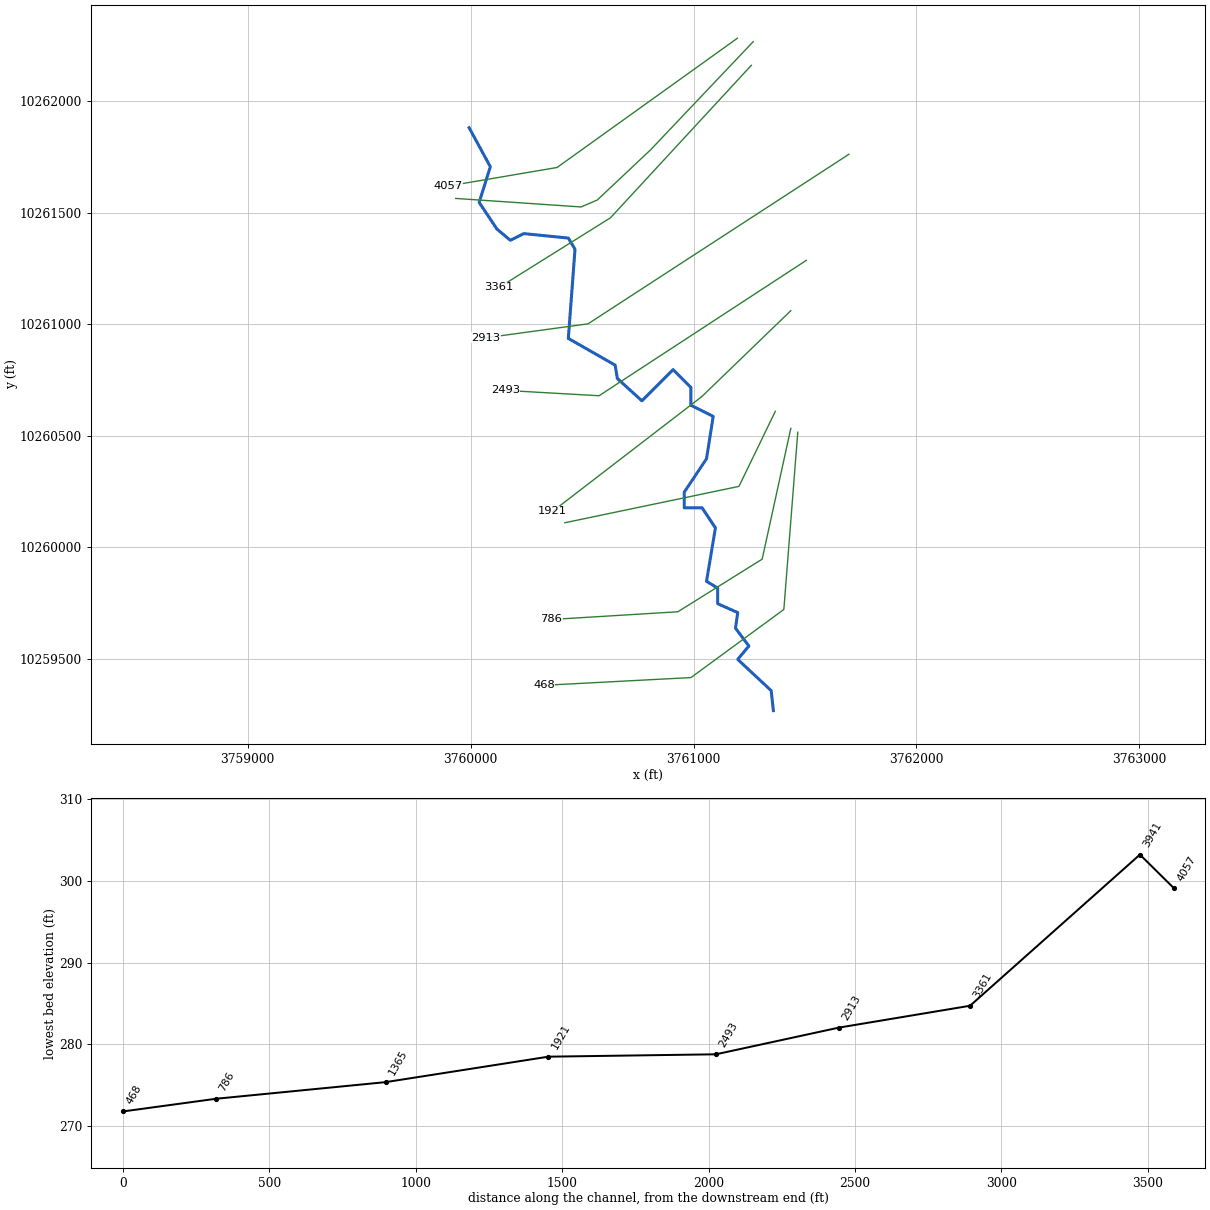
--- WFSJR 045.prj (project) ---

Proj Title=WFSJR 045 Base Level Engineering
Current Plan=p01
Default Exp/Contr=0.3,0.1
English Units
Geom File=g01
Flow File=f01
Plan File=p01
Y Axis Title=Elevation
X Axis Title(PF)=Main Channel Distance
X Axis Title(XS)=Station
BEGIN DESCRIPTION:
WFSJR 045
END DESCRIPTION:
DSS Export Rating Curves= 0
DSS Export Rating Curve Sorted= 0
DSS Export Volume Flow Curves= 0
DXF OffsetX= 0
DXF OffsetY= 0
DXF ScaleX= 1
DXF ScaleY= 10

--- WFSJR 045.p01 (plan) ---

Plan Title=Multiple Run
Program Version=4.10
Short Identifier=Multiple
Geom File=g01
Flow File=f01
Subcritical Flow
K Sum by GR= 0
Std Step Tol= 0.01
Critical Tol= 0.01
Num of Std Step Trials= 20
Max Error Tol= 0.3
Flow Tol Ratio= 0.001
Split Flow NTrial= 30
Split Flow Tol= 0.02
Split Flow Ratio= 0.02
Log Output Level= 0
Friction Slope Method= 1
Unsteady Friction Slope Method= 2
Unsteady Bridges Friction Slope Method= 1
Parabolic Critical Depth
Global Vel Dist= 1 , 1 , 1
Global Log Level= 0
CheckData=True
Encroach Param=-1 ,0,0, 0
BEGIN DESCRIPTION:
Multiple Run
END DESCRIPTION:
Computation Interval=1HOUR
Output Interval=1HOUR
Run HTab= 0
Run UNet= 0
Run PostProcess= 0
Run WQNet= 0
UNET Theta= 1
UNET Theta Warmup= 1
UNET ZTol= 0.02
UNET ZSATol= 0.05
UNET MxIter= 20
UNET MaxInSteps= 0
UNET DtIC= 0
UNET DtMin= 0
UNET MaxCRTS= 20
UNET WFStab= 2
UNET SFStab= 1
UNET WFX= 1
UNET SFX= 1
UNET DSS MLevel= 4
UNET DZMax Abort= 100
UNET Convert EG Bridges= 0
UNET Use Existing IB Tables=-1
UNET Froude Reduction=False
UNET Froude Limit= 1
UNET Froude Power= 10
UNET Time Slicing=0,0, 5
UNET Junction Losses=0
Instantaneous Interval=1HOUR
Write IC File= 0
Write IC File at Sim End=0
Echo Input=False
Echo Parameters=False
Echo Output=False
Write Detailed= 0
WQ AD Non Conservative
WQ ULTIMATE=-1
WQ Max Comp Step=1HOUR
WQ Output Interval=15MIN
WQ Output Selected Increments= 0
WQ Output face flow=0
WQ Output face velocity=0
WQ Output face area=0
WQ Output face dispersion=0
WQ Output cell volume=0
WQ Output cell surface area=0
WQ Output cell continuity=0
WQ Output cumulative cell continuity=0
WQ Output face conc=0
WQ Output face dconc_dx=0
WQ Output face courant=0
WQ Output face peclet=0
WQ Output face adv mass=0
WQ Output face disp mass=0
WQ Output cell mass=0
WQ Output cell source sink temp=0
WQ Output cell source sink nsm=0
WQ Output MaxMinRange=-1
WQ Daily Max Min Mean=-1
WQ Daily Range=0
WQ Daily Time=0
WQ Create Restart=0
WQ Fixed Restart=0
WQ System Summary=0
WQ Use Fixed Temperature=0
Sorting and Armoring Iterations= 10
XS Update Threshold= 0.02
Hydraulics Update Threshold= 0.02
Energy Slope Method= 1
Volume Change Method= 0
XS Weighting Method= 0
Number of US Weighted Cross Sections= 1
Number of DS Weighted Cross Sections= 1
Upstream XS Weight=0.25
Main XS Weight=0.5
Downstream XS Weight=0.25
Number of DS XS's Weighted with US Boundary= 1
Upstream Boundary Weight= 1
Weight of XSs Associated with US Boundary= 0
Number of US XS's Weighted with DS Boundary= 1
Downstream Boundary Weight= 0.5
Weight of XSs Associated with DS Boundary= 0.5
Sediment Output Level= 4
Mass or Volume Output= 0
Output Increment Type= 1
Profile and TS Output Increment= 10
XS Output Flag= 0
XS Output Increment= 10
Disregard all LS=0
Disregard all Conn=0
Disregard all Breaches=0
Disregard all Pumps=0

--- WFSJR 045.f01 (steady flow) ---

Flow Title=Multiple
Program Version=4.10
Number of Profiles= 7
Profile Names=10-year,25-year,50-year,1pct_min,100-year,1pct_plu,500-year
River Rch & RM=WFSJR 045,Reach-1         ,4057
     481     634     841     367    1108    3346    1988
Boundary for River Rch & Prof#=WFSJR 045,Reach-1         , 1
Up Type= 0
Dn Type= 3
Dn Slope=0.005
Boundary for River Rch & Prof#=WFSJR 045,Reach-1         , 2
Up Type= 0
Dn Type= 3
Dn Slope=0.005
Boundary for River Rch & Prof#=WFSJR 045,Reach-1         , 3
Up Type= 0
Dn Type= 3
Dn Slope=0.005
Boundary for River Rch & Prof#=WFSJR 045,Reach-1         , 4
Up Type= 0
Dn Type= 3
Dn Slope=0.005
Boundary for River Rch & Prof#=WFSJR 045,Reach-1         , 5
Up Type= 0
Dn Type= 3
Dn Slope=0.005
Boundary for River Rch & Prof#=WFSJR 045,Reach-1         , 6
Up Type= 0
Dn Type= 3
Dn Slope=0.005
Boundary for River Rch & Prof#=WFSJR 045,Reach-1         , 7
Up Type= 0
Dn Type= 3
Dn Slope=0.005
DSS Import GetInterval= 0
DSS Import GetPeak= 0
DSS Import FillOption= 0

--- WFSJR 045.g01 (geometry) ---

Geom Title=Existing Conditions
Program Version=4.10

River Reach=WFSJR 045       ,Reach-1
Reach XY= 30
      3759993.23     10261881.84      3760088.23     10261706.84
      3760038.23     10261546.84      3760118.23     10261426.84
      3760178.23     10261376.84      3760238.23     10261406.84
      3760438.23     10261386.84      3760468.23     10261336.84
      3760438.23     10260936.84      3760648.23     10260816.84
      3760658.23     10260756.84      3760768.23     10260656.84
      3760908.23     10260796.84      3760988.23     10260716.84
      3760988.23     10260636.84      3761088.23     10260586.84
      3761058.23     10260396.84      3760958.23     10260246.84
      3760958.23     10260176.84      3761038.23     10260176.84
      3761098.23     10260086.84      3761058.23     10259846.84
      3761108.23     10259816.84      3761108.23     10259746.84
      3761198.23     10259706.84      3761188.23     10259636.84
      3761248.23     10259556.84      3761198.23     10259496.84
      3761348.23     10259356.84      3761358.23     10259266.84

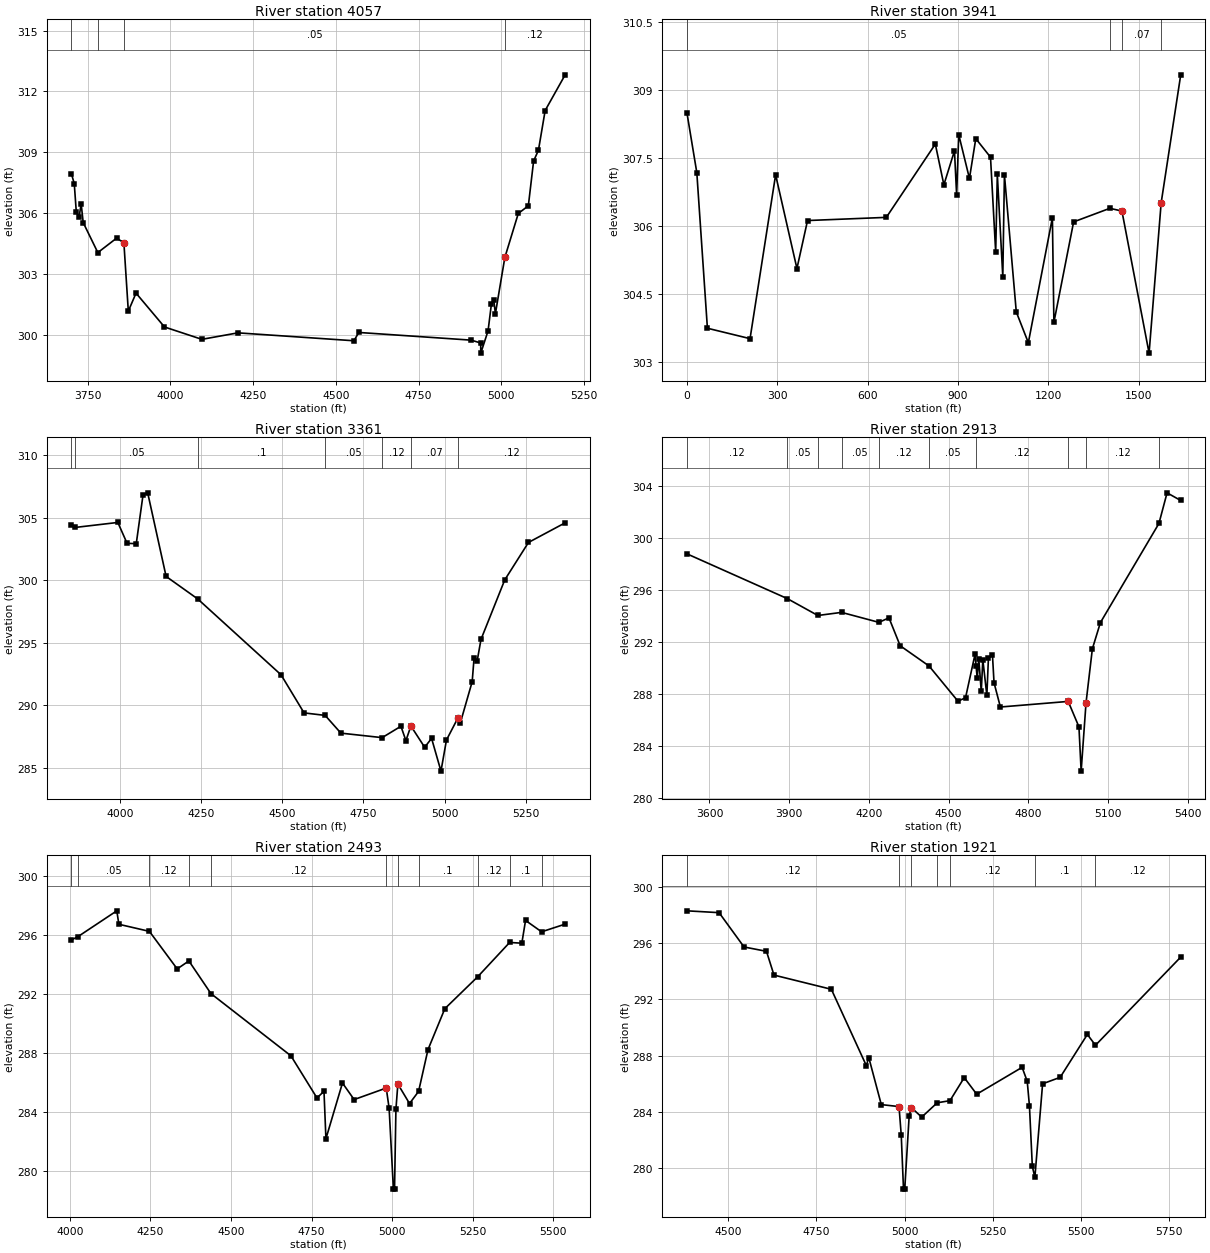
Type RM Length L Ch R = 1 ,4057    ,116,116,116
BEGIN DESCRIPTION:
WFSJR 045 6.0
END DESCRIPTION:
XS GIS Cut Line= 3
      3761196.87     10262283.39      3760387.82     10261703.52
      3759898.26     10261620.19
#Sta/Elev= 30
  3700.7  307.95  3709.5  307.45  3715.6  306.06  3724.1  305.81  3730.3  306.46
  3736.5  305.53  3780.7  304.05  3837.2  304.76  3859.4  304.54  3872.8  301.16
  3896.1  302.05  3982.1  300.38  4095.1  299.77  4203.9  300.09  4554.5   299.7
  4569.2  300.11  4909.1  299.73  4937.5  299.59  4937.8  299.09  4959.8  300.19
    4970  301.53  4976.9  301.71    4982  301.04  5010.5  303.81  5051.1  305.98
  5081.5  306.36  5097.4  308.57    5112   309.1  5132.3  311.06  5192.7  312.82
#Mann= 4 ,-1 , 0
  3700.7     .05       0  3780.7     .05       0  3859.4     .05       0
  5010.5     .12       0
Bank Sta=3859.4,5010.5
XS Rating Curve= 0 ,0
Exp/Cntr=0.3,0.1

Type RM Length L Ch R = 1 ,3941    ,580,580,580
XS GIS Cut Line= 5
      3761267.48     10262267.69      3760807.96     10261783.38
      3760568.38     10261557.68      3760495.46     10261526.43
      3759932.96     10261564.63
#Sta/Elev= 30
       0   308.5    32.8  307.18      68  303.74   209.6  303.51   294.5  307.13
   365.3  305.06   400.5  306.12   662.2  306.19   824.9  307.81   853.3  306.91
   888.5  307.66   895.7  306.68   902.6  308.02   938.2  307.05   959.3  307.93
  1008.2  307.52  1025.4  305.42  1030.8  307.14    1049  304.88  1054.4  307.13
  1093.8   304.1  1133.8  303.42  1213.7  306.18  1218.7  303.87  1284.2  306.09
  1404.5  306.39  1444.6  306.33  1534.8  303.19  1574.9  306.51  1639.9  309.34
#Mann= 4 ,-1 , 0
       0     .05       0  1404.5     .12       0  1444.6     .07       0
  1574.9     .12       0
#XS Ineff= 2 ,-1
       5   902.6  308.02     995  1404.5  306.39
Permanent Ineff=
       T       T
Bank Sta=1444.6,1574.9
XS Rating Curve= 0 ,0
Exp/Cntr=0.3,0.1

Type RM Length L Ch R = 1 ,3361    ,448,448,448
BEGIN DESCRIPTION:
WFSJR 045 5.0
END DESCRIPTION:
XS GIS Cut Line= 3
      3761259.36     10262161.87      3760627.41     10261477.82
        3760128.      10261165.7
#Sta/Elev= 30
  3850.9  304.42  3862.7  304.23    3994  304.63  4022.4  302.96  4050.7  302.93
  4071.7  306.86  4085.9     307  4142.6  300.31  4239.8  298.51  4496.4  292.44
  4567.3  289.39  4632.2  289.19  4680.7  287.77  4807.7  287.41  4865.5  288.32
  4880.9  287.17  4896.2  288.34  4938.6  286.64  4959.9  287.35  4988.8  284.73
  5005.7  287.22  5041.1  288.99  5048.3  288.58  5084.9  291.89  5090.8  293.82
  5100.1  293.53    5112  295.27  5185.1  300.03  5258.2  303.03  5371.1   304.6
#Mann= 7 ,-1 , 0
  3850.9     .12       0  3862.7     .05       0  4239.8      .1       0
  4632.2     .05       0  4807.7     .12       0  4896.2     .07       0
  5041.1     .12       0
Bank Sta=4896.2,5041.1
XS Rating Curve= 0 ,0
Exp/Cntr=0.3,0.1

Type RM Length L Ch R = 1 ,2913    ,420,420,420
BEGIN DESCRIPTION:
WFSJR 045 4.0
END DESCRIPTION:
XS GIS Cut Line= 3
      3761696.84     10261762.54      3760526.71     10261002.13
      3760068.35     10260939.62
#Sta/Elev= 30
  3515.2   298.8    3893  295.35  4007.9  294.05    4097  294.29  4237.7  293.52
  4275.4  293.87  4317.6  291.72  4426.2  290.16    4535  287.45  4563.5  287.71
  4599.3  291.06  4603.2  290.18  4607.5  289.21  4613.5   290.7  4622.7   288.2
  4628.6  290.65  4643.8  287.89  4649.7  290.77  4664.9  290.99  4670.8  288.87
  4694.7     287  4949.9  287.43  4990.3  285.47  4998.6  282.06    5017 287.332
  5040.8  291.48    5071   293.5  5291.3  301.14  5321.9   303.5  5373.3  302.91
#Mann= 10 ,-1 , 0
  3515.2     .12       0    3893     .05       0  4007.9     .12       0
    4097     .05       0  4237.7     .12       0  4426.2     .05       0
  4603.2     .12       0  4949.9     .07       0    5017     .12       0
  5291.3     .05       0
#XS Ineff= 1 ,-1
    4330  4664.9  290.99
Permanent Ineff=
       F
Bank Sta=4949.9,5017
XS Rating Curve= 0 ,0
Exp/Cntr=0.3,0.1

Type RM Length L Ch R = 1 ,2493    ,572,572,572
BEGIN DESCRIPTION:
WFSJR 045 3.0
END DESCRIPTION:
XS GIS Cut Line= 3
      3761505.92     10261286.88      3760576.12     10260679.54
      3760155.18     10260703.52
#Sta/Elev= 30
  4004.6  295.66  4024.1  295.87  4145.6  297.63    4152  296.72  4246.8  296.24
    4333   293.7  4369.3  294.24  4437.7  292.03  4685.9  287.82  4766.7  284.97
  4788.5  285.42  4794.5  282.21  4845.8  285.98    4882  284.86  4981.7  285.64
  4990.6  284.27  5003.9   278.8  5007.4   278.8  5011.7   284.2  5017.7  285.91
  5053.9  284.59    5082  285.41  5111.2  288.24  5163.5  291.01  5265.5  293.17
  5364.6  295.49  5402.4  295.44  5413.9  296.98  5463.7  296.21  5536.8  296.73
#Mann= 11 ,-1 , 0
  4004.6     .12       0  4024.1     .05       0  4246.8     .12       0
  4369.3     .05       0  4437.7     .12       0  4981.7     .07       0
  5017.7     .12       0    5082      .1       0  5265.5     .12       0
  5364.6      .1       0  5463.7     .05       0
Bank Sta=4981.7,5017.7
XS Rating Curve= 0 ,0
Exp/Cntr=0.3,0.1

Type RM Length L Ch R = 1 ,1921    ,556,556,556
BEGIN DESCRIPTION:
WFSJR 045 2.0
END DESCRIPTION:
XS GIS Cut Line= 3
      3761436.47     10261061.19      3761037.13     10260675.74
      3760367.85     10260161.07
#Sta/Elev= 30
  4383.3   298.3  4474.4  298.17  4545.1  295.73  4608.7  295.42    4630  293.73
  4792.6  292.72  4891.7  287.29  4898.6  287.87  4934.1  284.52  4984.3  284.38
  4990.6  282.35    4997  278.51  5000.5  278.51  5013.1  283.73  5019.6   284.3
  5048.6  283.63  5092.5  284.65  5128.7   284.8  5169.1  286.44  5204.4  285.26
  5333.1  287.17  5347.6  286.18  5353.9  284.43  5362.1  280.12  5369.3  279.35
  5391.2     286    5441  286.46    5518  289.51    5541  288.74  5782.6  295.01
#Mann= 7 ,-1 , 0
  4383.3     .12       0  4984.3     .07       0  5019.6     .12       0
  5092.5      .1       0  5128.7     .12       0  5369.3      .1       0
    5541     .12       0
#XS Ineff= 2 ,-1
  5169.1    5305  286.44  5333.1    5480  287.17
Permanent Ineff=
       F       F
Bank Sta=4984.3,5019.6
XS Rating Curve= 0 ,0
Exp/Cntr=0.3,0.1

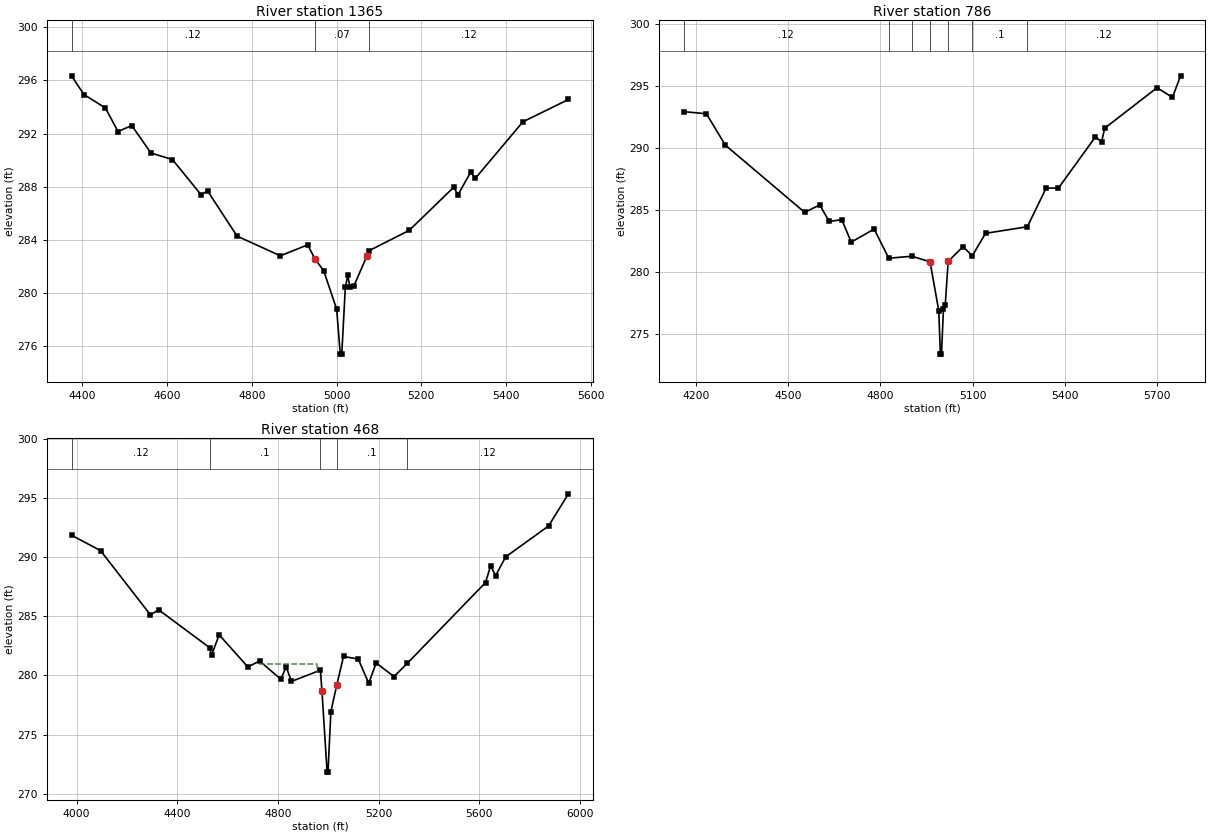
Type RM Length L Ch R = 1 ,1365    ,579,579,579
BEGIN DESCRIPTION:
Mapping XS 5b812540
END DESCRIPTION:
XS GIS Cut Line= 3
      3761366.98     10260609.75      3761203.79     10260272.96
      3760422.69      10260109.8
#Sta/Elev= 30
  4374.9  296.34  4404.3  294.93    4455  293.92  4484.5  292.15  4517.1   292.6
  4562.3  290.53    4613  290.04  4680.8  287.38  4695.7  287.69  4765.4  284.28
  4867.6   282.8  4931.8  283.62  4949.3  282.56  4969.7  281.68  5000.4  278.78
  5008.9   275.4  5012.4   275.4  5020.8  280.43  5026.6  281.33  5031.7  280.42
  5041.2  280.55  5071.5  282.76  5076.6  283.18  5171.5  284.71  5276.6  287.96
  5286.4  287.38  5316.4  289.09  5327.3  288.62  5439.7  292.88  5547.1  294.56
#Mann= 3 ,-1 , 0
  4374.9     .12       0  4949.3     .07       0  5076.6     .12       0
Bank Sta=4949.3,5071.5
XS Rating Curve= 0 ,0
Exp/Cntr=0.3,0.1

Type RM Length L Ch R = 1 ,786     ,318,318,318
BEGIN DESCRIPTION:
Mapping XS eb47bfb1
END DESCRIPTION:
XS GIS Cut Line= 4
      3761436.43     10260533.34      3761307.96     10259946.57
      3760929.49     10259710.46       3760361.5     10259675.83
#Sta/Elev= 30
  4160.2  292.94  4234.2  292.77  4295.6  290.24  4553.8  284.81  4602.8  285.41
  4633.4  284.08  4674.4  284.22  4705.1  282.41  4779.7  283.46  4827.2  281.11
  4902.4  281.27  4961.4  280.82  4989.7  276.88    4995  273.37  4998.5  273.37
    5005  276.98  5010.9  277.36  5020.3  280.85  5068.7  282.05  5098.6   281.3
  5141.9  283.12  5277.8  283.65  5338.8  286.77  5378.9  286.77  5499.1   290.9
  5519.2   290.5  5529.2   291.6  5699.5  294.87  5749.6  294.09    5776  295.83
#Mann= 7 ,-1 , 0
  4160.2     .12       0  4827.2      .1       0  4902.4     .12       0
  4961.4     .07       0  5020.3     .12       0  5098.6      .1       0
  5277.8     .12       0
Bank Sta=4961.4,5020.3
XS Rating Curve= 0 ,0
Exp/Cntr=0.3,0.1

Type RM Length L Ch R = 1 ,468     ,0,0,0
BEGIN DESCRIPTION:
WFSJR 045 1.0
END DESCRIPTION:
XS GIS Cut Line= 4
      3761467.68     10260516.04      3761405.18     10259720.88
      3760988.52     10259415.32      3760328.84      10259380.6
#Sta/Elev= 30
  3979.9  291.85  4095.2  290.55  4293.8  285.11  4325.9  285.55  4528.4  282.35
  4536.6  281.72  4566.7  283.43  4680.8  280.71  4727.2  281.22  4811.4  279.68
  4833.2  280.71    4854  279.49    4969  280.44  4975.2  278.68  4995.7  271.82
  4999.2  271.82  5010.7  276.94  5033.9  279.17  5060.9   281.6  5119.5  281.38
  5161.2  279.33  5190.6  281.05  5261.6   279.9    5314  281.01  5625.3  287.85
  5645.4  289.26  5665.4  288.43  5705.4  290.02  5875.7  292.63  5954.8  295.35
#Mann= 5 ,-1 , 0
  3979.9     .12       0  4528.4      .1       0    4969     .07       0
  5033.9      .1       0    5314     .12       0
#XS Ineff= 2 ,-1
    4725  4954.4  280.95  5060.9    5400   281.6
Permanent Ineff=
       F       F
Bank Sta=4975.2,5033.9
XS Rating Curve= 0 ,0
Exp/Cntr=0.3,0.1

Chan Stop Cuts=-1
Use User Specified Reach Order=0
Composite Channel Slope=5