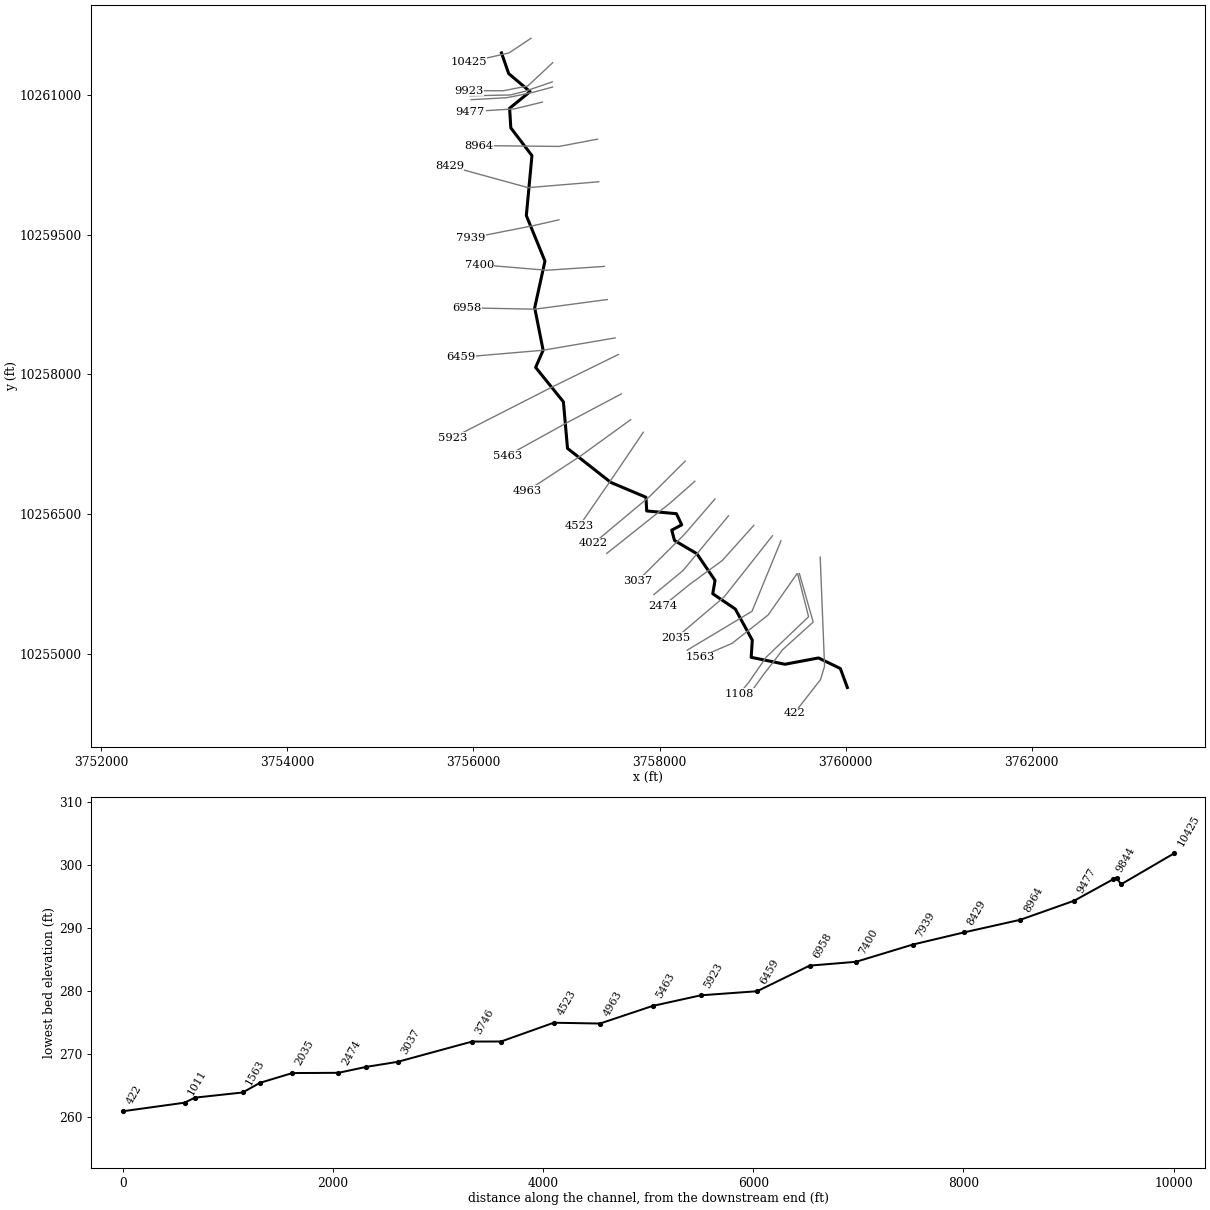
--- WFSJR 046.prj (project) ---

Proj Title=WFSJR 046 Base Level Engineering
Current Plan=p01
Default Exp/Contr=0.3,0.1
English Units
Geom File=g01
Flow File=f01
Plan File=p01
Y Axis Title=Elevation
X Axis Title(PF)=Main Channel Distance
X Axis Title(XS)=Station
BEGIN DESCRIPTION:
WFSJR 046
END DESCRIPTION:
DSS Export Rating Curves= 0
DSS Export Rating Curve Sorted= 0
DSS Export Volume Flow Curves= 0
DXF OffsetX= 0
DXF OffsetY= 0
DXF ScaleX= 1
DXF ScaleY= 10

--- WFSJR 046.p01 (plan) ---

Plan Title=Multiple Run
Program Version=4.10
Short Identifier=Multiple
Geom File=g01
Flow File=f01
Subcritical Flow
K Sum by GR= 0
Std Step Tol= 0.01
Critical Tol= 0.01
Num of Std Step Trials= 20
Max Error Tol= 0.3
Flow Tol Ratio= 0.001
Split Flow NTrial= 30
Split Flow Tol= 0.02
Split Flow Ratio= 0.02
Log Output Level= 0
Friction Slope Method= 1
Unsteady Friction Slope Method= 2
Unsteady Bridges Friction Slope Method= 1
Parabolic Critical Depth
Global Vel Dist= 1 , 1 , 1
Global Log Level= 0
CheckData=True
Encroach Param=-1 ,0,0, 0
BEGIN DESCRIPTION:
Multiple Run
END DESCRIPTION:
Computation Interval=1HOUR
Output Interval=1HOUR
Run HTab= 0
Run UNet= 0
Run PostProcess= 0
Run WQNet= 0
UNET Theta= 1
UNET Theta Warmup= 1
UNET ZTol= 0.02
UNET ZSATol= 0.05
UNET MxIter= 20
UNET MaxInSteps= 0
UNET DtIC= 0
UNET DtMin= 0
UNET MaxCRTS= 20
UNET WFStab= 2
UNET SFStab= 1
UNET WFX= 1
UNET SFX= 1
UNET DSS MLevel= 4
UNET DZMax Abort= 100
UNET Convert EG Bridges= 0
UNET Use Existing IB Tables=-1
UNET Froude Reduction=False
UNET Froude Limit= 1
UNET Froude Power= 10
UNET Time Slicing=0,0, 5
UNET Junction Losses=0
Instantaneous Interval=1HOUR
Write IC File= 0
Write IC File at Sim End=0
Echo Input=False
Echo Parameters=False
Echo Output=False
Write Detailed= 0
WQ AD Non Conservative
WQ ULTIMATE=-1
WQ Max Comp Step=1HOUR
WQ Output Interval=15MIN
WQ Output Selected Increments= 0
WQ Output face flow=0
WQ Output face velocity=0
WQ Output face area=0
WQ Output face dispersion=0
WQ Output cell volume=0
WQ Output cell surface area=0
WQ Output cell continuity=0
WQ Output cumulative cell continuity=0
WQ Output face conc=0
WQ Output face dconc_dx=0
WQ Output face courant=0
WQ Output face peclet=0
WQ Output face adv mass=0
WQ Output face disp mass=0
WQ Output cell mass=0
WQ Output cell source sink temp=0
WQ Output cell source sink nsm=0
WQ Output MaxMinRange=-1
WQ Daily Max Min Mean=-1
WQ Daily Range=0
WQ Daily Time=0
WQ Create Restart=0
WQ Fixed Restart=0
WQ System Summary=0
WQ Use Fixed Temperature=0
Sorting and Armoring Iterations= 10
XS Update Threshold= 0.02
Hydraulics Update Threshold= 0.02
Energy Slope Method= 1
Volume Change Method= 0
XS Weighting Method= 0
Number of US Weighted Cross Sections= 1
Number of DS Weighted Cross Sections= 1
Upstream XS Weight=0.25
Main XS Weight=0.5
Downstream XS Weight=0.25
Number of DS XS's Weighted with US Boundary= 1
Upstream Boundary Weight= 1
Weight of XSs Associated with US Boundary= 0
Number of US XS's Weighted with DS Boundary= 1
Downstream Boundary Weight= 0.5
Weight of XSs Associated with DS Boundary= 0.5
Sediment Output Level= 4
Mass or Volume Output= 0
Output Increment Type= 1
Profile and TS Output Increment= 10
XS Output Flag= 0
XS Output Increment= 10
Disregard all LS=0
Disregard all Conn=0
Disregard all Breaches=0
Disregard all Pumps=0

--- WFSJR 046.f01 (steady flow) ---

Flow Title=Multiple
Program Version=4.10
Number of Profiles= 7
Profile Names=10-year,25-year,50-year,1pct_min,100-year,1pct_plu,500-year
River Rch & RM=WFSJR 046,Reach-1         ,10425
     337     432     564     242     731    2208    1266
River Rch & RM=WFSJR 046,Reach-1         ,8429
     727     979    1318     582    1758    5309    3234
Boundary for River Rch & Prof#=WFSJR 046,Reach-1         , 1
Up Type= 0
Dn Type= 3
Dn Slope=0.0035
Boundary for River Rch & Prof#=WFSJR 046,Reach-1         , 2
Up Type= 0
Dn Type= 3
Dn Slope=0.0035
Boundary for River Rch & Prof#=WFSJR 046,Reach-1         , 3
Up Type= 0
Dn Type= 3
Dn Slope=0.0035
Boundary for River Rch & Prof#=WFSJR 046,Reach-1         , 4
Up Type= 0
Dn Type= 3
Dn Slope=0.0035
Boundary for River Rch & Prof#=WFSJR 046,Reach-1         , 5
Up Type= 0
Dn Type= 3
Dn Slope=0.0035
Boundary for River Rch & Prof#=WFSJR 046,Reach-1         , 6
Up Type= 0
Dn Type= 3
Dn Slope=0.0035
Boundary for River Rch & Prof#=WFSJR 046,Reach-1         , 7
Up Type= 0
Dn Type= 3
Dn Slope=0.0035
DSS Import GetInterval= 0
DSS Import GetPeak= 0
DSS Import FillOption= 0

--- WFSJR 046.g01 (geometry) ---

Geom Title=Existing Conditions
Program Version=4.10

River Reach=WFSJR 046       ,Reach-1
Reach XY= 30
      3756301.39      10261454.3      3756378.63     10261232.22
      3756608.49     10261038.47      3756388.35       10260860.
      3756401.55     10260648.89      3756628.63     10260350.97
      3756568.23     10259706.84      3756768.27     10259217.79
      3756658.16     10258716.33      3756748.74     10258260.21
      3756668.23     10258075.93      3756966.52     10257706.02
      3757010.81     10257205.85      3757475.84     10256840.39
      3757853.75     10256681.07      3757861.89     10256533.52
      3758181.24     10256504.24      3758238.28     10256384.73
      3758130.64     10256327.65      3758160.82     10256216.25
      3758400.77     10256074.62      3758596.31     10255786.87
      3758571.64     10255644.59      3758814.15     10255480.01
      3758996.56      10255145.2      3758984.61     10254961.43
      3759347.19     10254886.72      3759708.14     10254954.63
        3759943.     10254840.99      3760018.23     10254636.84

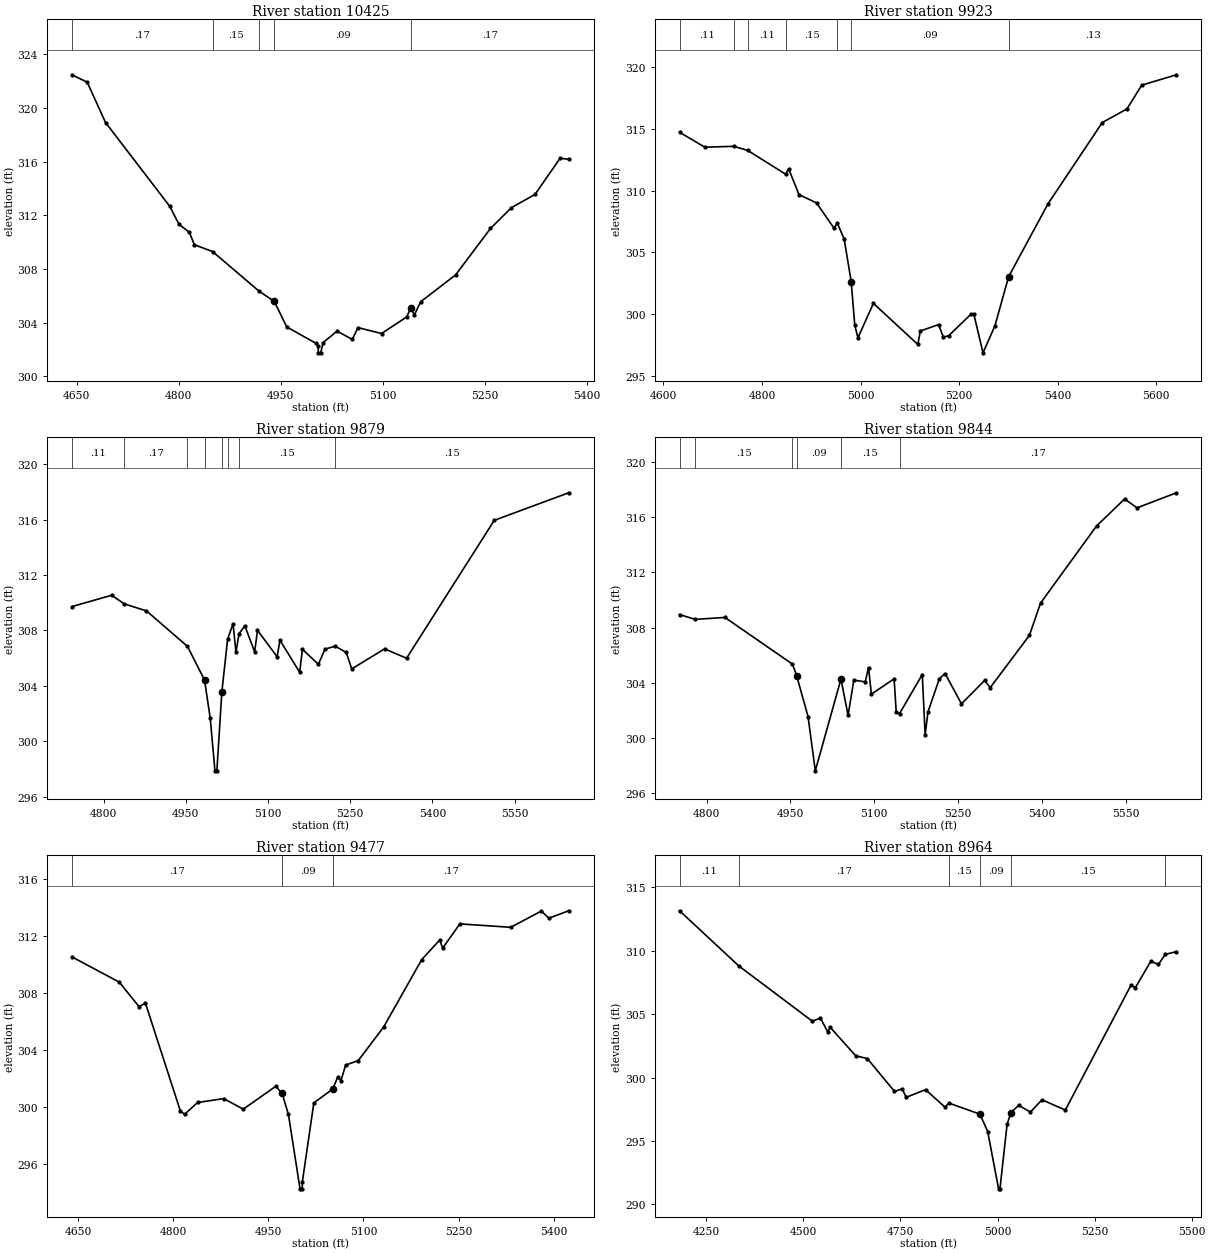
Type RM Length L Ch R = 1 ,10425   ,502,502,502
BEGIN DESCRIPTION:
WFSJR 046 20.0
END DESCRIPTION:
XS GIS Cut Line= 3
      3756617.88     10261611.09       3756381.4     10261453.81
       3755945.6     10261354.84
#Sta/Elev= 30
  4642.9  322.48  4665.5  321.93  4692.5  318.92    4787  312.67  4800.7  311.32
  4815.8  310.74  4823.1  309.81    4850   309.3    4918  306.36  4940.8  305.58
    4959  303.68  5002.1  302.46  5005.2  302.25  5005.5  301.75    5009  301.75
  5012.6  302.52  5033.1  303.37  5055.4  302.75  5063.9  303.63  5098.5  303.19
  5135.6  304.43  5141.6  305.13  5146.7  304.57  5156.1  305.56  5207.4  307.56
  5258.7  311.02  5289.5  312.57  5324.2  313.56  5361.2  316.26  5373.8  316.18
#Mann= 5 ,-1 , 0
  4642.9     .17       0    4850     .15       0    4918     .17       0
  4940.8     .09       0  5141.6     .17       0
Bank Sta=4940.8,5141.6
XS Rating Curve= 0 ,0
Exp/Cntr=0.3,0.1

Type RM Length L Ch R = 1 ,9923    ,44,44,44
BEGIN DESCRIPTION:
WFSJR 046 19.0
END DESCRIPTION:
XS GIS Cut Line= 4
      3756851.88     10261349.64      3756583.49     10261098.89
       3756318.9     10261047.56      3755947.33     10261049.29
#Sta/Elev= 30
  4632.7  314.74    4684  313.53  4742.5   313.6  4770.9  313.27    4848  311.34
    4854  311.78    4875  309.69  4910.7  309.01  4945.8  306.98    4953  307.36
  4966.8  306.08    4981  302.63  4988.3  299.09  4994.7  298.08  5026.1  300.87
  5116.2  297.54  5121.3  298.63  5158.5  299.15    5168  298.13  5178.9  298.25
  5224.8  300.02  5229.9  299.99  5248.5  296.86  5272.5  299.03  5300.6  303.04
  5380.6  308.95  5490.6  315.53  5540.6  316.63  5570.6  318.56  5641.1   319.4
#Mann= 7 ,-1 , 0
  4632.7     .11       0  4742.5     .17       0  4770.9     .11       0
    4848     .15       0    4953     .15       0    4981     .09       0
  5300.6     .13       0
Bank Sta=4981,5300.6
XS Rating Curve= 0 ,0
Exp/Cntr=0.3,0.1

Type RM Length L Ch R = 1 ,9879    ,35,35,35
BEGIN DESCRIPTION:
Mapping XS c3005005
END DESCRIPTION:
XS GIS Cut Line= 4
      3756846.64     10261143.03      3756553.27     10261042.35
      3756395.29     10261002.42      3755962.09     10260993.75
#Sta/Elev= 30
  4742.1  309.72  4814.8  310.54  4837.5  309.92  4878.3  309.41    4953  306.85
  4984.2  304.42  4994.6  301.65  5003.2  297.86  5006.7  297.86  5015.7  303.52
  5026.3  307.38  5036.2  308.48  5041.5  306.43  5047.2  307.77  5057.8  308.33
  5075.6  306.45  5080.8  308.01  5116.6   306.1  5121.8  307.29  5157.7  304.98
  5162.8  306.64  5191.9  305.55  5203.9  306.65  5222.6  306.86  5242.7  306.41
  5252.7  305.22  5312.7  306.67  5352.7  305.99  5512.7  315.95  5648.5  317.94
#Mann= 8 ,-1 , 0
  4742.1     .11       0  4837.5     .17       0    4953     .13       0
  4984.2     .09       0  5015.7     .13       0  5026.3     .17       0
  5047.2     .15       0  5222.6     .15       0
#XS Ineff= 1 ,-1
  5036.2    5400  308.48
Permanent Ineff=
       F
Bank Sta=4984.2,5015.7
XS Rating Curve= 0 ,0
Exp/Cntr=0.3,0.1

Type RM Length L Ch R = 1 ,9844    ,367,367,367
BEGIN DESCRIPTION:
WFSJR 046 18.0
END DESCRIPTION:
XS GIS Cut Line= 5
      3756850.16     10261087.49      3756657.44      10261035.4
      3756480.36     10260997.21      3756355.36      10260972.9
      3755975.16     10260952.07
#Sta/Elev= 30
  4751.7  308.94  4779.6  308.59  4832.8  308.73  4953.7  305.35  4961.1  304.52
  4981.6  301.55  4994.5  297.63  5040.4  304.27  5053.2  301.64  5063.4  304.19
  5083.9  304.07  5089.7   305.1  5094.9  303.18  5135.5  304.29  5139.3  301.87
  5145.2  301.77  5185.9   304.6    5191  300.25  5196.2  301.91  5216.5   304.3
  5226.7  304.67    5256  302.48  5297.4  304.17  5307.4  303.65  5377.5  307.43
  5397.5  309.77  5497.7  315.35  5547.8   317.3  5570.1  316.66  5640.6  317.75
#Mann= 6 ,-1 , 0
  4751.7     .11       0  4779.6     .15       0  4953.7     .15       0
  4961.1     .09       0  5040.4     .15       0  5145.2     .17       0
#XS Ineff= 1 ,-1
  5089.7    5350   305.1
Permanent Ineff=
       F
Bank Sta=4961.1,5040.4
XS Rating Curve= 0 ,0
Exp/Cntr=0.3,0.1

Type RM Length L Ch R = 1 ,9477    ,513,513,513
BEGIN DESCRIPTION:
Mapping XS fc304941
END DESCRIPTION:
XS GIS Cut Line= 3
      3756740.75     10260926.02      3756440.43     10260853.11
      3755966.49      10260823.6
#Sta/Elev= 30
  4639.9  310.54  4714.9  308.76  4745.8  307.05  4756.1  307.28    4811  299.74
  4817.8  299.49  4838.4  300.32  4879.6  300.59  4910.4  299.85  4961.5  301.45
  4971.6  300.97  4981.6  299.48  4999.9  294.26  5003.4  294.26  5003.6  294.76
  5021.7  300.29  5051.7  301.27  5059.5  302.12  5064.5  301.85  5071.8  302.94
  5091.8  303.26  5131.9  305.62    5192  310.35  5220.1  311.71  5225.1  311.16
  5252.1  312.85  5332.3  312.61  5380.7  313.75  5392.4  313.25  5423.8  313.77
#Mann= 3 ,-1 , 0
  4639.9     .17       0  4971.6     .09       0  5051.7     .17       0
#XS Ineff= 1 ,-1
    4780  4961.5  301.45
Permanent Ineff=
       F
Bank Sta=4971.6,5051.7
XS Rating Curve= 0 ,0
Exp/Cntr=0.3,0.1

Type RM Length L Ch R = 1 ,8964    ,535,535,535
BEGIN DESCRIPTION:
WFSJR 046 17.0
END DESCRIPTION:
XS GIS Cut Line= 3
      3757334.09     10260528.02      3756921.76      10260449.9
      3756061.57     10260458.57
#Sta/Elev= 30
    4181  313.15  4333.7   308.8  4523.2  304.44  4543.6   304.7  4563.2  303.57
  4568.3  303.99  4634.6  301.72  4664.6   301.5  4734.6  298.91  4754.6  299.11
  4764.6  298.44  4814.6  299.05  4864.6  297.67  4874.6  297.99  4954.6  297.12
  4974.6  295.75  5002.8  291.23  5006.3  291.23  5024.6  296.31  5034.6  297.24
  5054.6  297.82  5084.6  297.28  5114.6  298.25  5174.6  297.44  5344.6  307.33
  5354.6  307.07  5394.6  309.16  5414.6  308.93    5432  309.71  5460.9  309.93
#Mann= 6 ,-1 , 0
    4181     .11       0  4333.7     .17       0  4874.6     .15       0
  4954.6     .09       0  5034.6     .15       0    5432     .11       0
Bank Sta=4954.6,5034.6
XS Rating Curve= 0 ,0
Exp/Cntr=0.3,0.1

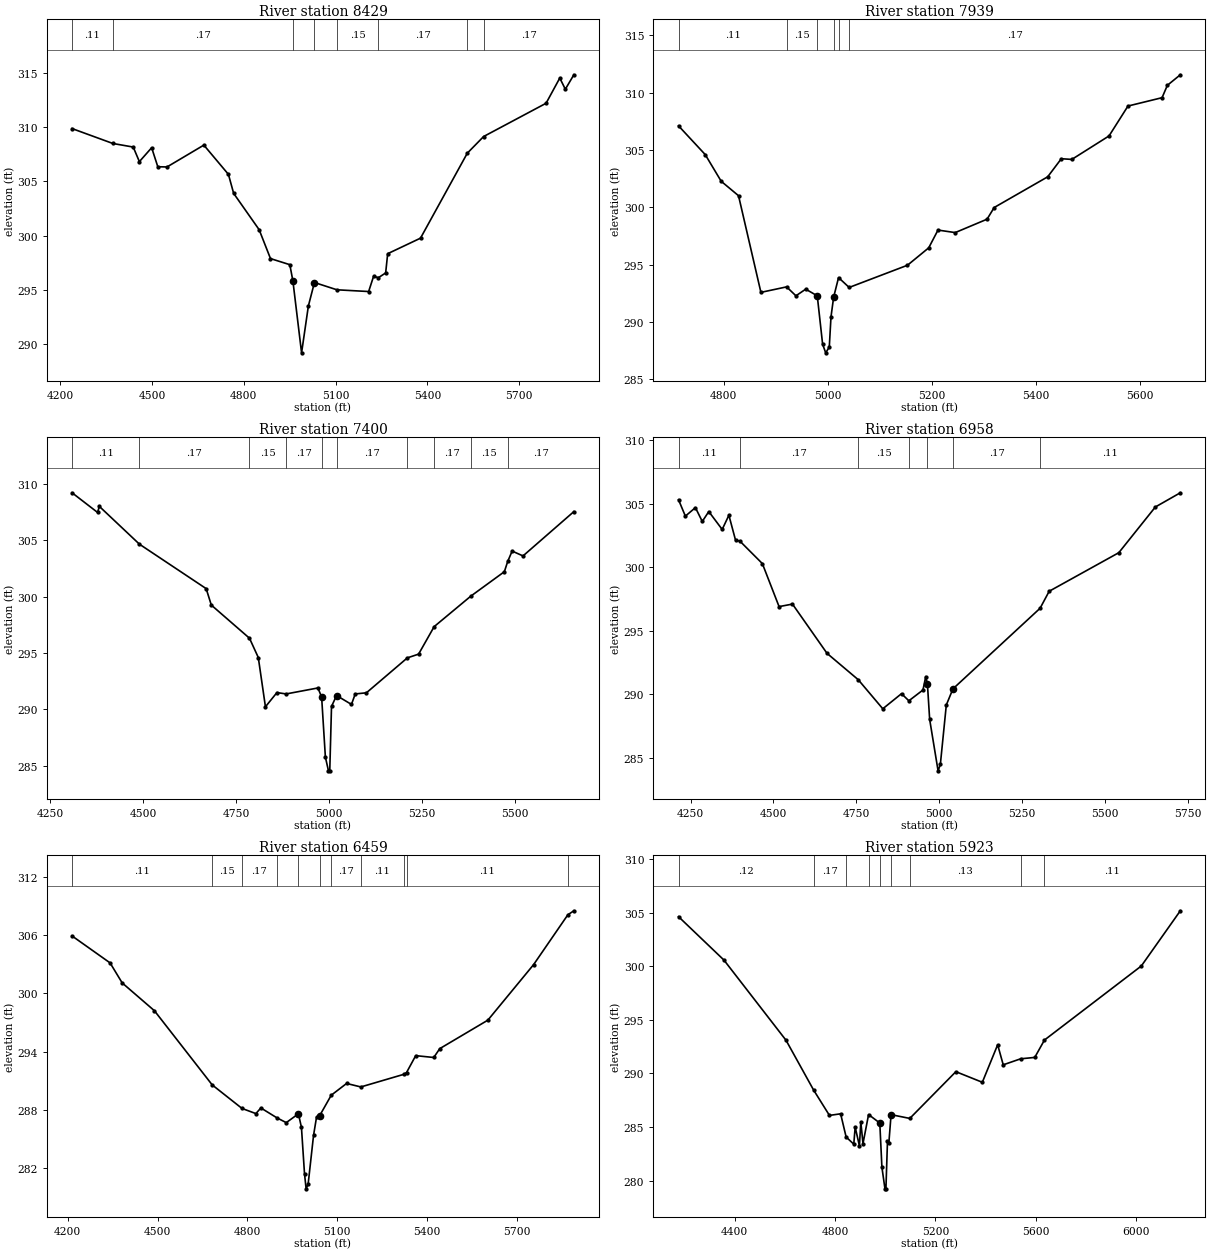
Type RM Length L Ch R = 1 ,8429    ,490,490,490
BEGIN DESCRIPTION:
WFSJR 046 16.0
END DESCRIPTION:
XS GIS Cut Line= 3
       3757347.1     10260070.12      3756588.23     10260006.84
      3755740.93     10260238.88
#Sta/Elev= 30
  4238.5  309.86  4371.8  308.49  4438.4  308.16  4458.5  306.82  4498.6   308.1
  4518.7  306.35  4548.8  306.33  4669.2  308.34  4749.5  305.65  4766.6   303.9
  4849.9  300.56    4887   297.9  4950.2  297.34  4960.2  295.85  4988.6  289.23
  5010.8  293.54  5030.6   295.7  5104.1  295.03  5207.8  294.87  5223.8  296.26
    5240  296.15  5263.4  296.58    5270  298.35  5377.3  299.78  5530.3   307.6
  5583.6  309.13  5787.7  312.19  5832.5  314.51  5850.6  313.48  5878.5  314.81
#Mann= 8 ,-1 , 0
  4238.5     .11       0  4371.8     .17       0  4960.2     .09       0
  5030.6     .17       0  5104.1     .15       0    5240     .17       0
  5530.3     .11       0  5583.6     .17       0
Bank Sta=4960.2,5030.6
XS Rating Curve= 0 ,0
Exp/Cntr=0.3,0.1

Type RM Length L Ch R = 1 ,7939    ,539,539,539
BEGIN DESCRIPTION:
WFSJR 046 15.0
END DESCRIPTION:
XS GIS Cut Line= 3
      3756917.85     10259661.07      3756637.91     10259597.34
      3755973.41     10259466.83
#Sta/Elev= 30
  4712.9  307.11  4764.2   304.6  4794.9  302.27  4828.2  301.01  4871.2  292.57
  4920.6  293.05  4938.5  292.27  4957.3  292.85  4979.5  292.27  4989.8  288.04
  4995.7  287.29  5002.6  287.79  5005.9  290.44    5011  292.16  5020.4  293.86
  5040.8     293  5152.9  294.94  5193.7  296.46  5211.5  298.01  5244.6  297.79
  5305.8  298.96  5319.5  299.98  5422.3  302.66  5448.5  304.24  5468.7  304.18
  5540.2  306.23  5576.6  308.84  5642.1  309.57  5652.3  310.65  5677.2  311.57
#Mann= 6 ,-1 , 0
  4712.9     .11       0  4920.6     .15       0  4979.5     .09       0
    5011     .12       0  5020.4     .15       0  5040.8     .17       0
Bank Sta=4979.5,5011
XS Rating Curve= 0 ,0
Exp/Cntr=0.3,0.1

Type RM Length L Ch R = 1 ,7400    ,442,442,442
BEGIN DESCRIPTION:
WFSJR 046 14.0
END DESCRIPTION:
XS GIS Cut Line= 3
      3757407.85     10259160.84      3756787.21      10259119.6
      3756061.55     10259180.26
#Sta/Elev= 30
  4308.8  309.22  4377.3  307.48  4382.3  308.01  4490.1  304.66  4669.6  300.72
  4683.5  299.26  4786.2  296.32  4809.9  294.61  4829.1  290.24    4860   291.5
  4884.9  291.38  4970.3  291.91  4980.3  291.11  4990.4  285.78  4998.7  284.56
  5002.2  284.56  5006.9  290.27  5020.5  291.24  5060.6  290.45  5070.7  291.38
  5100.8  291.48    5211  294.58  5241.2  294.91  5283.1  297.35  5381.6  300.05
    5472  302.22    5481  303.13  5492.9  304.05  5522.2  303.62    5659  307.55
#Mann= 10 ,-1 , 0
  4308.8     .11       0  4490.1     .17       0  4786.2     .15       0
  4884.9     .17       0  4980.3     .09       0  5020.5     .17       0
    5211     .15       0  5283.1     .17       0  5381.6     .15       0
    5481     .17       0
Bank Sta=4980.3,5020.5
XS Rating Curve= 0 ,0
Exp/Cntr=0.3,0.1

Type RM Length L Ch R = 1 ,6958    ,499,499,499
BEGIN DESCRIPTION:
WFSJR 046 13.0
END DESCRIPTION:
XS GIS Cut Line= 3
       3757438.3     10258804.94      3756658.98     10258701.12
      3755932.53     10258715.95
#Sta/Elev= 30
  4213.8  305.31  4234.4  304.02  4264.7  304.69  4285.4   303.6    4305  304.38
  4345.4  302.97  4365.6  304.09  4385.8  302.11  4398.5  302.06  4466.5  300.28
  4516.9  296.89  4557.3  297.09  4661.4  293.21  4755.6  291.13  4829.6  288.84
    4886  290.03  4908.2  289.47  4950.7  290.32  4959.1  291.38  4964.2  290.77
  4970.9     288  4996.3  283.95  5003.1  284.45  5021.1  289.14  5041.1  290.41
  5303.8  296.76  5331.2   298.1  5541.2  301.14  5651.3  304.74  5726.6  305.86
#Mann= 7 ,-1 , 0
  4213.8     .11       0  4398.5     .17       0  4755.6     .15       0
  4908.2     .17       0  4964.2     .09       0  5041.1     .17       0
  5303.8     .11       0
Bank Sta=4964.2,5041.1
XS Rating Curve= 0 ,0
Exp/Cntr=0.3,0.1

Type RM Length L Ch R = 1 ,6459    ,536,536,536
BEGIN DESCRIPTION:
WFSJR 046 12.0
END DESCRIPTION:
XS GIS Cut Line= 3
       3757522.9     10258392.61      3756748.74     10258260.21
      3755861.68     10258184.37
#Sta/Elev= 30
  4214.6   305.9  4341.5  303.13    4382  301.07  4489.6  298.21  4682.6  290.58
  4782.1  288.16  4828.4  287.63  4845.1  288.21  4898.9  287.19  4929.9   286.7
  4970.5  287.61  4980.6  286.21  4990.8  281.45  4996.2  279.89    5003  280.39
    5021  285.39    5031  287.27    5041  287.39  5080.1  289.52  5131.4  290.73
  5178.9  290.37  5322.7  291.67  5331.5  291.85  5362.2  293.59  5422.4   293.4
  5442.5  294.31  5603.1  297.24  5755.8  302.95  5870.3  308.08  5890.3  308.49
#Mann= 11 ,-1 , 0
  4214.6     .11       0  4682.6     .15       0  4782.1     .17       0
  4898.9     .15       0  4970.5     .09       0    5041     .15       0
  5080.1     .17       0  5178.9     .11       0  5322.7     .17       0
  5331.5     .11       0  5870.3     .17       0
Bank Sta=4970.5,5041
XS Rating Curve= 0 ,0
Exp/Cntr=0.3,0.1

Type RM Length L Ch R = 1 ,5923    ,460,460,460
BEGIN DESCRIPTION:
WFSJR 046 11.0
END DESCRIPTION:
XS GIS Cut Line= 3
      3757557.62     10258214.66      3756854.49      10257869.6
      3755771.17     10257317.11
#Sta/Elev= 30
  4176.9  304.63  4357.9  300.58  4605.2   293.1    4715  288.46  4778.2  286.09
  4822.7  286.24  4844.7  284.07  4875.1  283.41  4880.7     285  4897.6  283.25
  4903.2  285.48  4911.8  283.46  4934.1  286.17  4978.8  285.38  4987.2  281.26
  4999.4  279.24  5003.2  279.24  5009.4  283.67    5015  283.55  5023.7  286.16
  5098.3  285.81  5281.9  290.17  5387.3  289.18  5448.4  292.68  5470.6  290.81
  5539.9  291.37  5596.2   291.5  5634.8  293.12  6020.8  300.03  6176.2  305.18
#Mann= 9 ,-1 , 0
  4176.9     .12       0    4715     .17       0  4844.7     .15       0
  4934.1     .11       0  4978.8     .06       0  5023.7     .11       0
  5098.3     .13       0  5539.9     .17       0  5634.8     .11       0
Bank Sta=4978.8,5023.7
XS Rating Curve= 0 ,0
Exp/Cntr=0.3,0.1

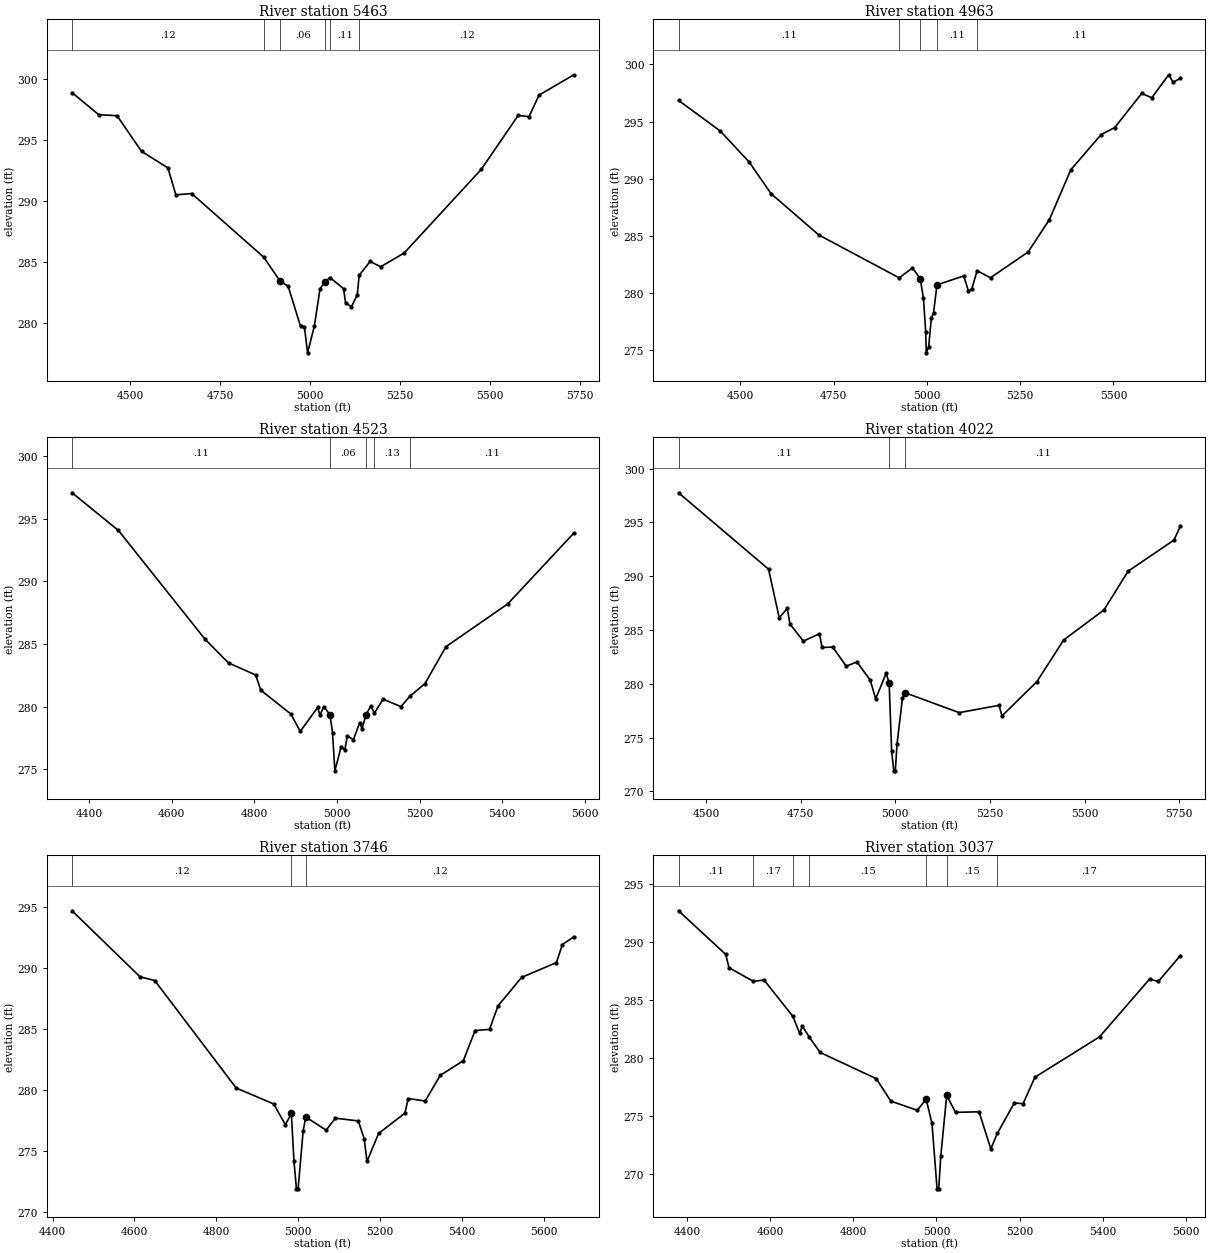
Type RM Length L Ch R = 1 ,5463    ,500,500,500
BEGIN DESCRIPTION:
WFSJR 046 10.0
END DESCRIPTION:
XS GIS Cut Line= 3
      3757588.42     10257790.61      3757003.84     10257481.23
      3756362.34     10257126.81
#Sta/Elev= 30
  4338.6  298.89  4412.6  297.09  4463.7     297  4531.6  294.08    4605  292.72
    4627  290.51    4671  290.62    4871   285.4  4916.3  283.45  4938.9  283.02
  4973.4  279.73  4984.1   279.7    4993  277.55  5011.6  279.72  5027.7  282.81
  5041.1  283.36  5055.1  283.73    5093  282.81  5098.7  281.64  5114.7  281.33
  5130.8  282.28  5136.5  283.91  5166.8  285.05  5196.1  284.61  5261.4  285.74
  5475.3  292.59  5578.1  297.02  5608.5  296.93    5636  298.69  5732.9  300.36
#Mann= 6 ,-1 , 0
  4338.6     .12       0    4871     .11       0  4916.3     .06       0
  5041.1     .11       0  5055.1     .11       0  5136.5     .12       0
Bank Sta=4916.3,5041.1
XS Rating Curve= 0 ,0
Exp/Cntr=0.3,0.1

Type RM Length L Ch R = 1 ,4963    ,440,440,440
BEGIN DESCRIPTION:
WFSJR 046 9.0
END DESCRIPTION:
XS GIS Cut Line= 3
      3757690.01     10257514.58      3757150.46     10257123.97
      3756581.74     10256752.29
#Sta/Elev= 30
  4333.9  296.85  4446.1  294.16  4523.4  291.45  4582.2  288.68  4709.8  285.08
  4925.6  281.32  4961.2  282.19    4982  281.24  4990.6  279.54  4996.7  276.59
  4998.1  274.76  5004.5  275.26  5011.8  277.81  5017.7  278.27  5026.9  280.71
  5098.7  281.49  5111.2  280.16  5120.4  280.37  5134.5  281.94  5170.4  281.33
  5271.1  283.58  5328.4  286.42  5385.7  290.78  5467.2  293.86  5503.4  294.47
  5575.8  297.46  5602.9  297.08  5648.2  299.09  5660.2  298.44  5679.4  298.77
#Mann= 5 ,-1 , 0
  4333.9     .11       0  4925.6     .11       0    4982     .06       0
  5026.9     .11       0  5134.5     .11       0
Bank Sta=4982,5026.9
XS Rating Curve= 0 ,0
Exp/Cntr=0.3,0.1

Type RM Length L Ch R = 1 ,4523    ,501,501,501
BEGIN DESCRIPTION:
WFSJR 046 8.0
END DESCRIPTION:
XS GIS Cut Line= 3
      3757825.39     10257379.12      3757486.87     10256879.15
       3757140.5     10256376.53
#Sta/Elev= 30
  4359.3  297.06  4471.3  294.06  4680.9  285.39  4737.9  283.49  4803.7  282.53
  4815.9  281.32  4888.3  279.43  4911.6  278.04  4953.6  279.95  4958.9  279.33
  4968.5  280.01  4983.4  279.36  4989.5  277.94  4995.2  274.89  5010.4  276.81
  5019.2  276.54  5025.3  277.67  5040.2  277.38  5055.1  278.72  5061.1  278.25
    5070  279.33  5082.2  280.06  5090.9  279.49  5111.9   280.6  5155.1  280.01
  5176.5  280.83  5213.3  281.85    5264  284.79  5413.5   288.2  5573.5  293.85
#Mann= 5 ,-1 , 0
  4359.3     .11       0  4983.4     .06       0    5070     .11       0
  5090.9     .13       0  5176.5     .11       0
Bank Sta=4983.4,5070
XS Rating Curve= 0 ,0
Exp/Cntr=0.3,0.1

Type RM Length L Ch R = 1 ,4022    ,276,276,276
BEGIN DESCRIPTION:
WFSJR 046 7.0
END DESCRIPTION:
XS GIS Cut Line= 3
       3758275.9     10257069.23      3757893.12     10256689.05
       3757290.3     10256184.97
#Sta/Elev= 30
  4427.5  297.76  4665.2  290.66  4693.5  286.13  4714.7  287.02  4721.8  285.56
  4757.2  283.97  4799.6  284.65  4806.6  283.38  4834.9  283.41  4870.3  281.64
  4898.6  282.03  4933.9  280.34  4948.1   278.6    4976  280.99  4983.8  280.04
  4990.3  273.76  4996.1  271.91  5000.1  271.91  5004.6  274.43  5018.9  278.65
    5026  279.17  5168.6  277.32    5274     278  5281.8  277.02  5374.2  280.21
  5444.5  284.07  5551.2  286.87  5614.9  290.47    5736  293.36  5752.8  294.64
#Mann= 3 , 0 , 0
  4427.5     .11       0  4983.8     .06       0    5026     .11       0
#XS Ineff= 1 ,-1
    4900    4976  280.99
Permanent Ineff=
       F
Bank Sta=4983.8,5026
XS Rating Curve= 0 ,0
Exp/Cntr=0.3,0.1

Type RM Length L Ch R = 1 ,3746    ,709,709,709
BEGIN DESCRIPTION:
WFSJR 046 6.0
END DESCRIPTION:
XS GIS Cut Line= 3
      3758380.11     10256853.12      3758117.08     10256621.34
      3757432.49     10256077.32
#Sta/Elev= 30
  4447.7  294.66  4613.5  289.26  4649.5  288.95  4848.4  280.15  4939.8  278.85
  4968.6  277.14    4983  278.08  4989.4  274.17  4995.5   271.9  4999.5   271.9
  5011.9  276.66  5018.3  277.78  5067.9   276.7  5090.4  277.68  5146.4  277.46
  5160.8  276.01  5167.7  274.14  5196.1  276.44  5260.2  278.09  5268.2  279.29
  5309.8  279.09  5346.5  281.19  5402.7  282.38  5431.6  284.86  5466.8  284.95
  5487.6  286.88  5545.3  289.21  5630.2  290.42  5644.6  291.89  5672.7  292.53
#Mann= 3 , 0 , 0
  4447.7     .12       0    4983     .07       0  5018.3     .12       0
Bank Sta=4983,5018.3
XS Rating Curve= 0 ,0
Exp/Cntr=0.3,0.1

Type RM Length L Ch R = 1 ,3037    ,299,299,299
BEGIN DESCRIPTION:
WFSJR 046 5.0
END DESCRIPTION:
XS GIS Cut Line= 3
      3758596.27     10256663.04      3758268.12      10256282.8
      3757768.42      10255785.7
#Sta/Elev= 30
  4379.7  292.68  4493.3  288.91    4501  287.77  4559.7  286.59  4585.5   286.7
  4654.6  283.57    4671  282.11  4677.6  282.72    4694  281.79  4720.4  280.45
  4855.3  278.19  4890.4  276.25  4954.1  275.46  4975.3  276.42  4989.4  274.33
  5001.6  268.68  5005.6  268.68  5010.6  271.53  5024.8  276.75    5046  275.28
  5102.6  275.33  5130.9  272.13  5146.7  273.47  5187.4  276.09  5208.6  276.03
  5236.9  278.31  5392.5   281.8  5512.7  286.78  5533.9  286.58  5586.8  288.81
#Mann= 7 ,-1 , 0
  4379.7     .11       0  4559.7     .17       0  4654.6     .11       0
    4694     .15       0  4975.3     .09       0  5024.8     .15       0
  5146.7     .17       0
Bank Sta=4975.3,5024.8
XS Rating Curve= 0 ,0
Exp/Cntr=0.3,0.1

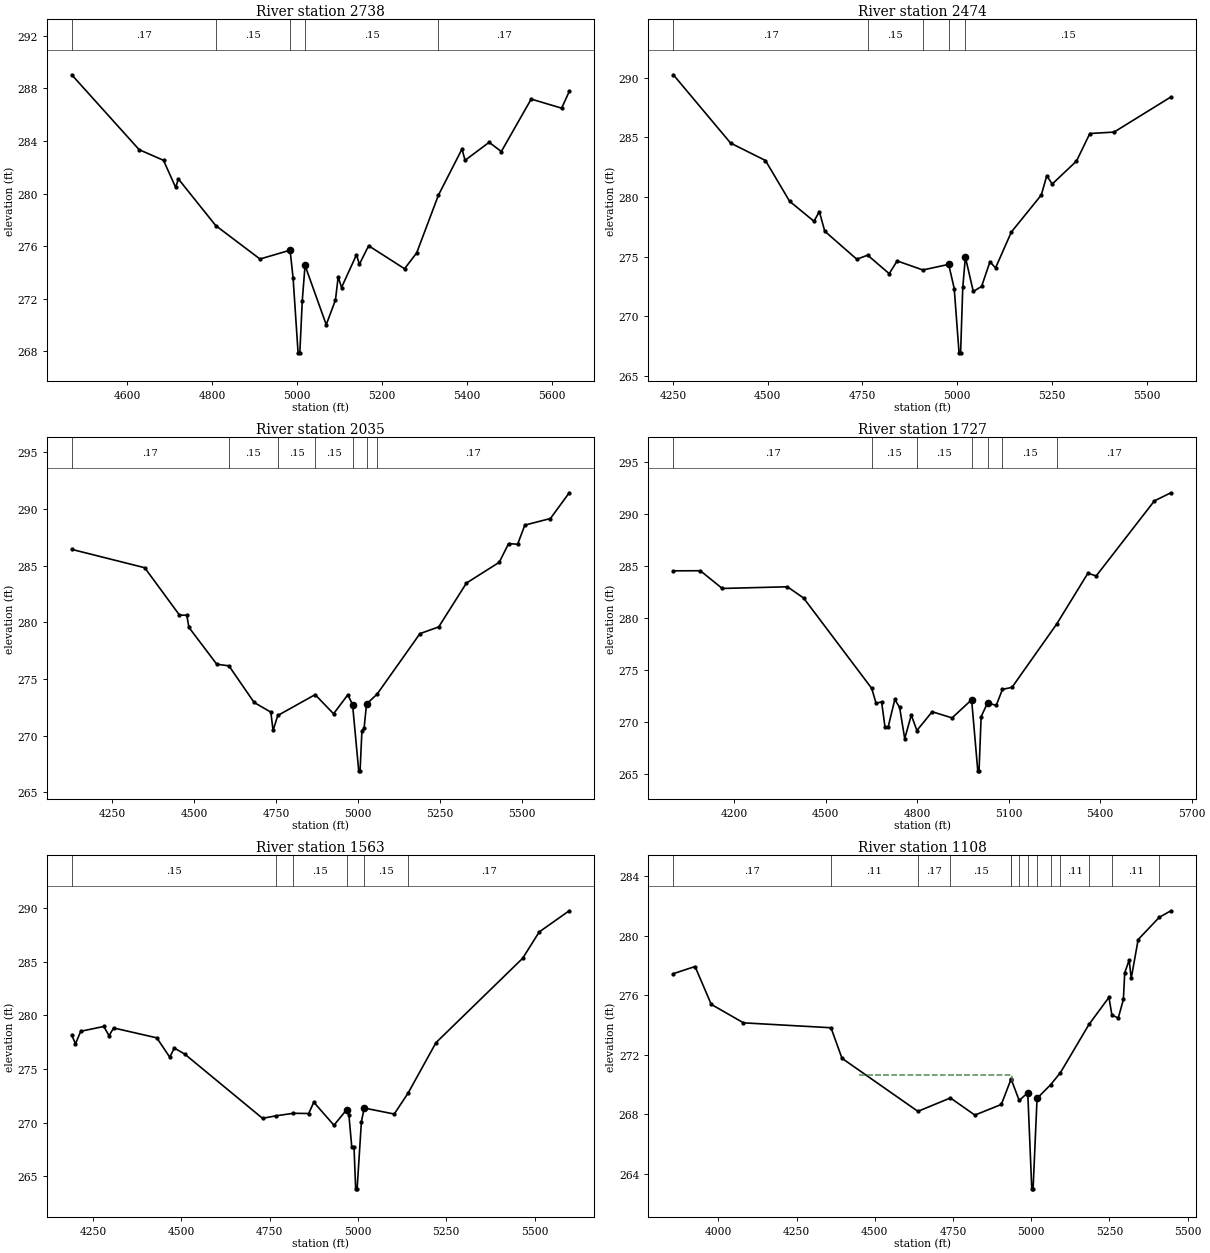
Type RM Length L Ch R = 1 ,2738    ,264,264,264
BEGIN DESCRIPTION:
WFSJR 046 4.0
END DESCRIPTION:
XS GIS Cut Line= 3
      3758741.28      10256481.9      3758251.35     10255892.73
      3757938.44     10255635.23
#Sta/Elev= 30
  4468.9  289.04  4627.7  283.34    4685  282.53  4713.6  280.47  4720.1  281.11
  4808.1  277.56  4912.2  275.02  4983.1  275.69  4990.2  273.56  5001.9  267.88
    5006  267.88  5011.8  271.86  5018.3  274.53  5068.2  270.02  5089.9   271.9
  5096.4  273.68  5104.2  272.85  5139.4  275.34  5146.3  274.62    5168  276.03
  5252.6  274.28  5281.1  275.48  5332.4  279.88  5387.9  283.39  5395.1  282.53
  5451.8   283.9  5480.5   283.2  5550.8  287.19  5622.5   286.5  5640.4  287.77
#Mann= 5 ,-1 , 0
  4468.9     .17       0  4808.1     .15       0  4983.1     .09       0
  5018.3     .15       0  5332.4     .17       0
Bank Sta=4983.1,5018.3
XS Rating Curve= 0 ,0
Exp/Cntr=0.3,0.1

Type RM Length L Ch R = 1 ,2474    ,439,439,439
BEGIN DESCRIPTION:
Mapping XS ddad36d9
END DESCRIPTION:
XS GIS Cut Line= 4
      3759012.92     10256379.17      3758674.37     10256001.55
      3758325.41     10255746.34      3758036.37     10255511.98
#Sta/Elev= 30
  4251.4  290.23  4402.3  284.51  4494.2  283.05  4557.8  279.64  4622.1  277.96
  4636.3  278.77  4650.5  277.13    4735  274.78  4763.7  275.12  4820.5  273.57
  4841.4  274.64  4909.2  273.88  4977.3  274.35  4991.9  272.32  5004.6  266.94
  5008.7  266.94  5014.4  272.42  5021.3  274.96  5042.1  272.08    5064   272.5
  5086.1  274.57  5100.8  274.05  5142.5  277.06  5221.5  280.16  5235.9  281.78
  5250.2  281.08  5314.2     283  5349.4  285.31  5413.3  285.43    5563  288.37
#Mann= 5 ,-1 , 0
  4251.4     .17       0  4763.7     .15       0  4909.2     .15       0
  4977.3     .09       0  5021.3     .15       0
Bank Sta=4977.3,5021.3
XS Rating Curve= 0 ,0
Exp/Cntr=0.3,0.1

Type RM Length L Ch R = 1 ,2035    ,308,308,308
BEGIN DESCRIPTION:
WFSJR 046 3.0
END DESCRIPTION:
XS GIS Cut Line= 3
      3759213.45      10256267.2       3758695.2     10255610.92
      3758176.99     10255170.84
#Sta/Elev= 30
  4127.4  286.43  4349.9  284.81  4455.6  280.64  4478.1  280.62  4484.5  279.55
  4569.4   276.3  4606.4  276.16  4683.2  272.93  4734.1  272.08    4741  270.46
  4755.3  271.78  4869.2  273.62  4925.3  271.93  4968.9  273.61  4983.2  272.74
    5002   266.9  5006.1   266.9  5011.8  270.45  5018.3  270.65  5025.8  272.79
  5057.9  273.66  5188.6     279  5245.7  279.59  5330.3  283.46  5430.2  285.29
  5458.7  286.94  5486.2  286.88  5508.2  288.57  5586.2  289.15  5643.5  291.42
#Mann= 7 ,-1 , 0
  4127.4     .17       0  4606.4     .15       0  4755.3     .15       0
  4869.2     .15       0  4983.2     .09       0  5025.8     .15       0
  5057.9     .17       0
Bank Sta=4983.2,5025.8
XS Rating Curve= 0 ,0
Exp/Cntr=0.3,0.1

Type RM Length L Ch R = 1 ,1727    ,164,164,164
BEGIN DESCRIPTION:
WFSJR 046 2.0
END DESCRIPTION:
XS GIS Cut Line= 3
      3759304.57     10256212.47       3758993.5     10255455.49
       3758296.8     10255038.03
#Sta/Elev= 30
  4001.2  284.54  4089.6  284.55  4161.5  282.85  4374.9  283.01  4428.2  281.93
  4651.4  273.26  4665.5  271.84  4683.8  271.96  4694.9  269.54  4705.5  269.59
  4727.1   272.2  4742.8  271.44  4759.5  268.44  4781.1   270.7  4799.4  269.22
  4849.5  271.02  4914.7  270.43  4978.8  272.17    4999  265.35  5003.1  265.35
    5010  270.55  5031.3  271.89  5059.3  271.62  5079.9  273.17  5111.1  273.36
  5257.5  279.43  5359.9  284.31  5387.1  284.05  5577.7  291.25  5631.8  292.03
#Mann= 7 ,-1 , 0
  4001.2     .17       0  4651.4     .15       0  4799.4     .15       0
  4978.8     .09       0  5031.3     .15       0  5079.9     .15       0
  5257.5     .17       0
Bank Sta=4978.8,5031.3
XS Rating Curve= 0 ,0
Exp/Cntr=0.3,0.1

Type RM Length L Ch R = 1 ,1563    ,455,455,455
BEGIN DESCRIPTION:
Mapping XS ee2ca9fc
END DESCRIPTION:
XS GIS Cut Line= 4
      3759476.44     10255858.31      3759166.55     10255415.61
      3758778.53     10255110.92      3758434.75     10254962.47
#Sta/Elev= 30
  4190.1  278.15  4200.7  277.33  4215.5   278.5  4280.9  278.95  4295.7  278.09
  4308.8  278.81  4430.9  277.89  4467.5  276.09  4480.6  276.94  4510.2  276.37
  4730.2  270.39  4767.7  270.62  4817.5  270.86  4860.8  270.84  4875.3  271.89
  4932.3  269.75  4968.3  271.19  4974.7  270.67  4982.8  267.72  4989.1  267.71
  4993.8  263.82  4997.9  263.82    5010  270.07    5018  271.35    5103  270.79
  5142.5  272.76  5221.1  277.44  5466.4   285.3  5513.4  287.76  5598.3  289.73
#Mann= 6 ,-1 , 0
  4190.1     .15       0  4767.7     .15       0  4817.5     .15       0
  4968.3     .09       0    5018     .15       0  5142.5     .17       0
Bank Sta=4968.3,5018
XS Rating Curve= 0 ,0
Exp/Cntr=0.3,0.1

Type RM Length L Ch R = 1 ,1108    ,97,97,97
BEGIN DESCRIPTION:
Mapping XS f0f4de82
END DESCRIPTION:
XS GIS Cut Line= 5
      3759484.26     10255858.32      3759601.45     10255397.38
      3759145.72     10254962.49      3758958.22     10254691.65
      3758859.28     10254571.88
#Sta/Elev= 30
  3855.9  277.44  3925.3  277.92    3977  275.38  4080.1  274.14  4359.8  273.81
    4395  271.76  4637.6   268.2  4741.6   269.1  4819.6  267.95  4904.2  268.66
  4934.1  270.29  4935.5  270.37  4961.4  268.93  4988.8  269.45  5001.6     263
  5005.8     263  5018.5  269.07  5061.6  269.98  5093.3   270.8  5184.4  274.03
  5248.3  275.85  5257.7  274.67    5278  274.46  5294.5  275.71  5298.7   277.5
    5313  278.35  5319.5  277.12  5341.7  279.73  5409.1  281.22  5446.2  281.66
#Mann= 14 ,-1 , 0
  3855.9     .17       0  4359.8     .11       0  4637.6     .17       0
  4741.6     .15       0  4934.1     .15       0  4935.5     .14       0
  4961.4     .13       0  4988.8     .09       0  5018.5     .13       0
  5061.6     .15       0  5093.3     .11       0  5184.4     .15       0
  5257.7     .11       0  5409.1     .17       0
#XS Ineff= 1 ,-1
    4450  4939.8  270.63
Permanent Ineff=
       T
Bank Sta=4988.8,5018.5
XS Rating Curve= 0 ,0
Exp/Cntr=0.3,0.1

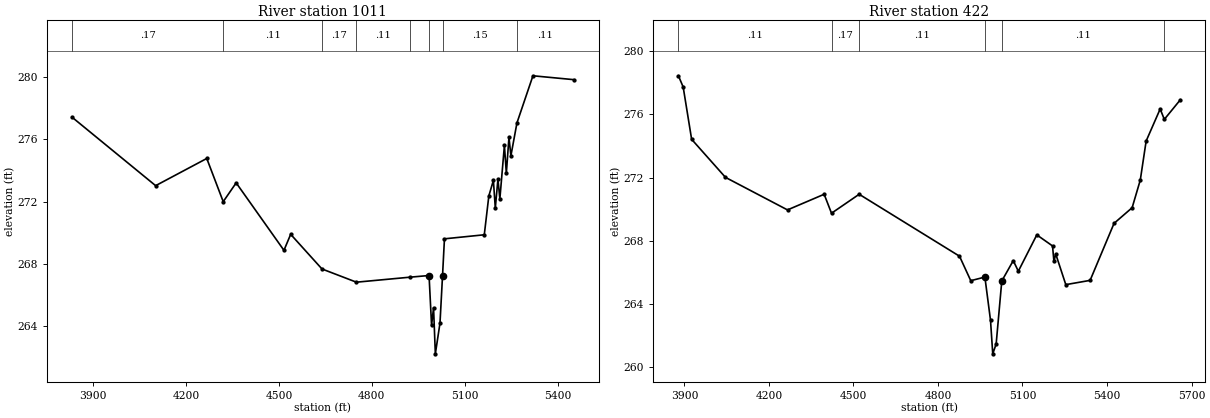
Type RM Length L Ch R = 1 ,1011    ,589,589,589
BEGIN DESCRIPTION:
Mapping XS 9e3e0b2e
END DESCRIPTION:
XS GIS Cut Line= 6
      3759502.49     10255860.94      3759650.93     10255340.09
      3759321.41     10255042.52      3759238.54     10254931.52
      3759122.28      10254782.8      3758942.74       10254533.
#Sta/Elev= 30
  3831.7  277.43  4101.9  273.02    4267  274.77  4320.1  271.99  4361.9   273.2
  4516.2  268.86  4537.9  269.89    4639  267.66  4750.2  266.81    4922  267.13
  4984.7  267.24  4992.8  264.03  4999.2  265.17    5005   262.2    5020  264.18
  5028.1  267.19  5034.4   269.6    5163  269.86  5177.7  272.36  5192.4  273.36
  5198.6  271.58  5207.1  273.44  5213.3  272.17    5228  275.61  5234.2  273.82
  5242.7  276.13  5248.9  274.94  5268.5  277.06  5320.1  280.09  5452.2  279.84
#Mann= 8 ,-1 , 0
  3831.7     .17       0  4320.1     .11       0    4639     .17       0
  4750.2     .11       0    4922     .15       0  4984.7     .08       0
  5028.1     .15       0  5268.5     .11       0
Bank Sta=4984.7,5028.1
XS Rating Curve= 0 ,0
Exp/Cntr=0.3,0.1

Type RM Length L Ch R = 1 ,422     ,0,0,0
BEGIN DESCRIPTION:
WFSJR 046 1.0
END DESCRIPTION:
XS GIS Cut Line= 4
      3759726.45     10256037.98      3759773.33     10254866.13
      3759729.05      10254720.3      3759447.82     10254360.95
#Sta/Elev= 30
  3878.8  278.44  3895.7  277.73  3925.7  274.42  4045.8  272.01    4266  269.95
  4396.1  270.94  4422.2  269.74  4520.4  270.94  4876.5  267.02  4916.5  265.47
  4966.6   265.7  4986.6  262.96  4994.5  260.84  5006.6  261.46  5026.6  265.45
  5067.3  266.74  5085.3  266.07  5150.9  268.37  5206.7  267.67  5211.7  266.69
  5218.1  267.16  5253.8  265.22  5340.1  265.49  5425.1   269.1  5489.3  270.09
  5518.2  271.84    5539  274.31  5588.8  276.34  5603.5  275.68  5660.3  276.92
#Mann= 6 ,-1 , 0
  3878.8     .11       0  4422.2     .17       0  4520.4     .11       0
  4966.6     .07       0  5026.6     .11       0  5603.5     .17       0
Bank Sta=4966.6,5026.6
XS Rating Curve= 0 ,0
Exp/Cntr=0.3,0.1

Chan Stop Cuts=-1
Use User Specified Reach Order=0
Composite Channel Slope=5