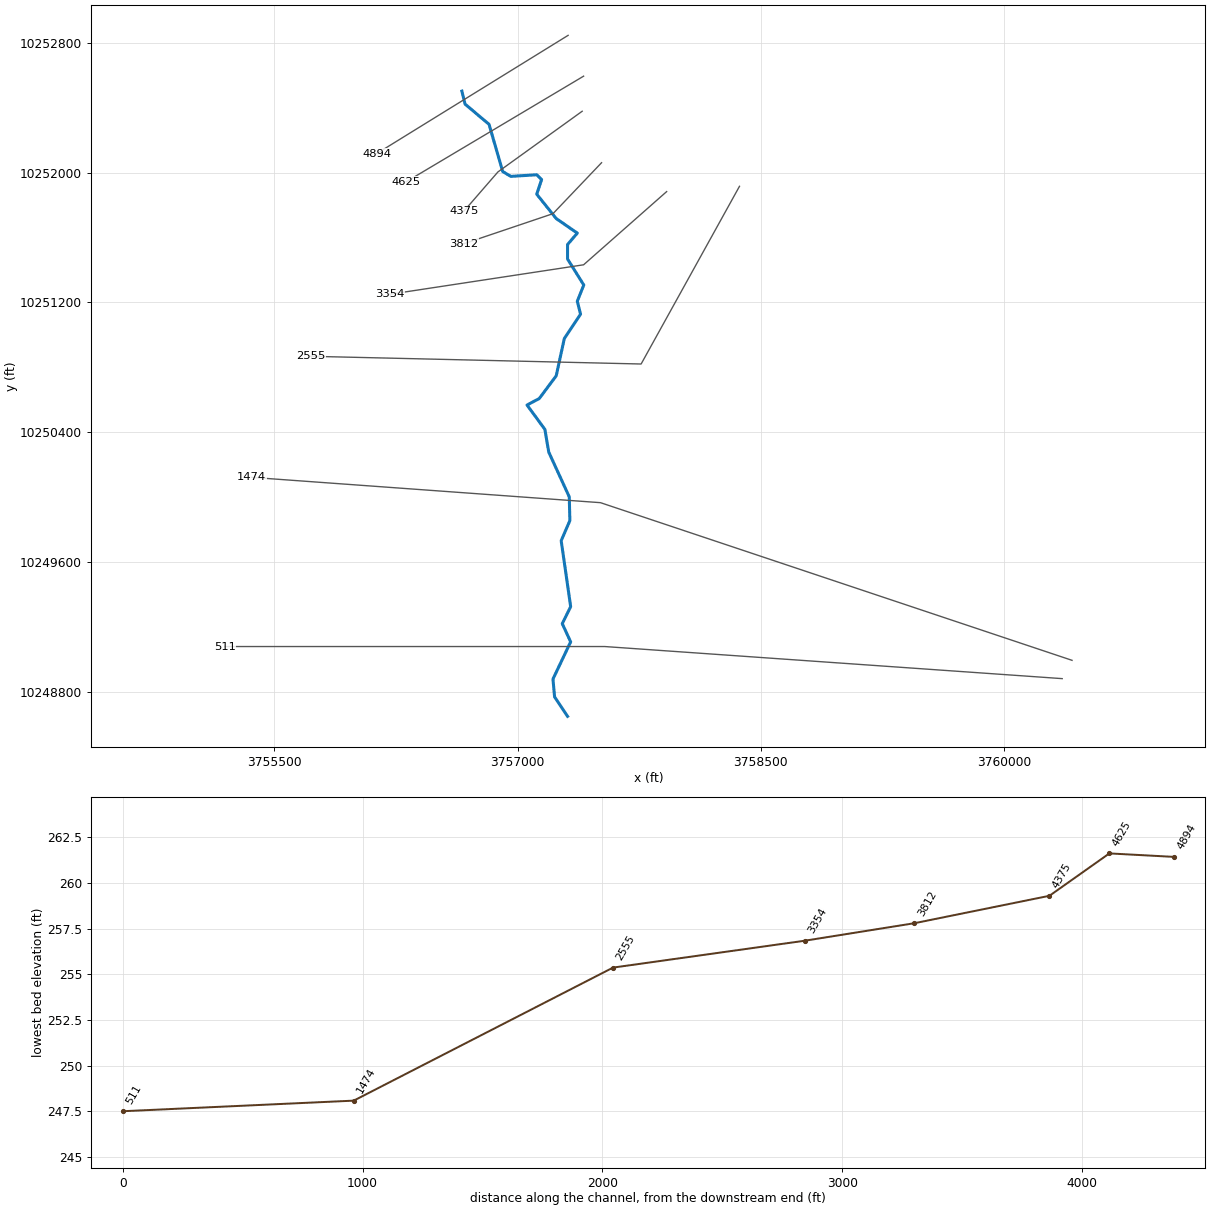
--- WFSJR 048.prj (project) ---

Proj Title=WFSJR 048 Base Level Engineering
Current Plan=p01
Default Exp/Contr=0.3,0.1
English Units
Geom File=g01
Flow File=f01
Plan File=p01
Y Axis Title=Elevation
X Axis Title(PF)=Main Channel Distance
X Axis Title(XS)=Station
BEGIN DESCRIPTION:
WFSJR 048
END DESCRIPTION:
DSS Export Rating Curves= 0
DSS Export Rating Curve Sorted= 0
DSS Export Volume Flow Curves= 0
DXF OffsetX= 0
DXF OffsetY= 0
DXF ScaleX= 1
DXF ScaleY= 10

--- WFSJR 048.p01 (plan) ---

Plan Title=Multiple Run
Program Version=4.10
Short Identifier=Multiple
Geom File=g01
Flow File=f01
Subcritical Flow
K Sum by GR= 0
Std Step Tol= 0.01
Critical Tol= 0.01
Num of Std Step Trials= 20
Max Error Tol= 0.3
Flow Tol Ratio= 0.001
Split Flow NTrial= 30
Split Flow Tol= 0.02
Split Flow Ratio= 0.02
Log Output Level= 0
Friction Slope Method= 1
Unsteady Friction Slope Method= 2
Unsteady Bridges Friction Slope Method= 1
Parabolic Critical Depth
Global Vel Dist= 1 , 1 , 1
Global Log Level= 0
CheckData=True
Encroach Param=-1 ,0,0, 0
BEGIN DESCRIPTION:
Multiple Run
END DESCRIPTION:
Computation Interval=1HOUR
Output Interval=1HOUR
Run HTab= 0
Run UNet= 0
Run PostProcess= 0
Run WQNet= 0
UNET Theta= 1
UNET Theta Warmup= 1
UNET ZTol= 0.02
UNET ZSATol= 0.05
UNET MxIter= 20
UNET MaxInSteps= 0
UNET DtIC= 0
UNET DtMin= 0
UNET MaxCRTS= 20
UNET WFStab= 2
UNET SFStab= 1
UNET WFX= 1
UNET SFX= 1
UNET DSS MLevel= 4
UNET DZMax Abort= 100
UNET Convert EG Bridges= 0
UNET Use Existing IB Tables=-1
UNET Froude Reduction=False
UNET Froude Limit= 1
UNET Froude Power= 10
UNET Time Slicing=0,0, 5
UNET Junction Losses=0
Instantaneous Interval=1HOUR
Write IC File= 0
Write IC File at Sim End=0
Echo Input=False
Echo Parameters=False
Echo Output=False
Write Detailed= 0
WQ AD Non Conservative
WQ ULTIMATE=-1
WQ Max Comp Step=1HOUR
WQ Output Interval=15MIN
WQ Output Selected Increments= 0
WQ Output face flow=0
WQ Output face velocity=0
WQ Output face area=0
WQ Output face dispersion=0
WQ Output cell volume=0
WQ Output cell surface area=0
WQ Output cell continuity=0
WQ Output cumulative cell continuity=0
WQ Output face conc=0
WQ Output face dconc_dx=0
WQ Output face courant=0
WQ Output face peclet=0
WQ Output face adv mass=0
WQ Output face disp mass=0
WQ Output cell mass=0
WQ Output cell source sink temp=0
WQ Output cell source sink nsm=0
WQ Output MaxMinRange=-1
WQ Daily Max Min Mean=-1
WQ Daily Range=0
WQ Daily Time=0
WQ Create Restart=0
WQ Fixed Restart=0
WQ System Summary=0
WQ Use Fixed Temperature=0
Sorting and Armoring Iterations= 10
XS Update Threshold= 0.02
Hydraulics Update Threshold= 0.02
Energy Slope Method= 1
Volume Change Method= 0
XS Weighting Method= 0
Number of US Weighted Cross Sections= 1
Number of DS Weighted Cross Sections= 1
Upstream XS Weight=0.25
Main XS Weight=0.5
Downstream XS Weight=0.25
Number of DS XS's Weighted with US Boundary= 1
Upstream Boundary Weight= 1
Weight of XSs Associated with US Boundary= 0
Number of US XS's Weighted with DS Boundary= 1
Downstream Boundary Weight= 0.5
Weight of XSs Associated with DS Boundary= 0.5
Sediment Output Level= 4
Mass or Volume Output= 0
Output Increment Type= 1
Profile and TS Output Increment= 10
XS Output Flag= 0
XS Output Increment= 10
Disregard all LS=0
Disregard all Conn=0
Disregard all Breaches=0
Disregard all Pumps=0

--- WFSJR 048.f01 (steady flow) ---

Flow Title=Multiple
Program Version=4.10
Number of Profiles= 7
Profile Names=10-year,25-year,50-year,1pct_min,100-year,1pct_plu,500-year
River Rch & RM=WFSJR 048,Reach-1         ,4894
     437     579     772     339    1023    3089    1856
River Rch & RM=WFSJR 048,Reach-1         ,4375
     692     939    1272     567    1711    5167    3197
River Rch & RM=WFSJR 048,Reach-1         ,511
    4812    6985    9882    4564   13783   41624   27754
Boundary for River Rch & Prof#=WFSJR 048,Reach-1         , 1
Up Type= 0
Dn Type= 3
Dn Slope=0.0025
Boundary for River Rch & Prof#=WFSJR 048,Reach-1         , 2
Up Type= 0
Dn Type= 3
Dn Slope=0.0025
Boundary for River Rch & Prof#=WFSJR 048,Reach-1         , 3
Up Type= 0
Dn Type= 3
Dn Slope=0.0025
Boundary for River Rch & Prof#=WFSJR 048,Reach-1         , 4
Up Type= 0
Dn Type= 3
Dn Slope=0.0025
Boundary for River Rch & Prof#=WFSJR 048,Reach-1         , 5
Up Type= 0
Dn Type= 3
Dn Slope=0.0025
Boundary for River Rch & Prof#=WFSJR 048,Reach-1         , 6
Up Type= 0
Dn Type= 3
Dn Slope=0.0025
Boundary for River Rch & Prof#=WFSJR 048,Reach-1         , 7
Up Type= 0
Dn Type= 3
Dn Slope=0.0025
DSS Import GetInterval= 0
DSS Import GetPeak= 0
DSS Import FillOption= 0

--- WFSJR 048.g01 (geometry) ---

Geom Title=Existing Conditions
Program Version=4.10

River Reach=WFSJR 048       ,Reach-1
Reach XY= 30
      3756656.46      10252502.4      3756676.06      10252422.5
      3756824.06     10252297.84      3756908.23     10252006.84
      3756958.23     10251976.84      3757118.23     10251986.84
      3757148.23     10251956.84      3757118.23     10251866.84
      3757238.23     10251716.84      3757368.23     10251626.84
      3757308.23     10251556.84      3757308.23     10251466.84
      3757408.23     10251306.84      3757368.23     10251206.84
      3757388.23     10251126.84      3757288.23     10250976.84
      3757238.23     10250746.84       3757133.7     10250606.84
      3757058.23     10250566.84      3757168.23     10250416.84
      3757192.23     10250276.41      3757318.79     10250000.36
      3757322.44     10249854.01       3757268.9       10249730.
      3757327.35     10249323.36      3757275.56     10249218.48
       3757327.3      10249106.2      3757218.23     10248876.84
      3757228.23     10248766.84      3757308.23     10248646.84

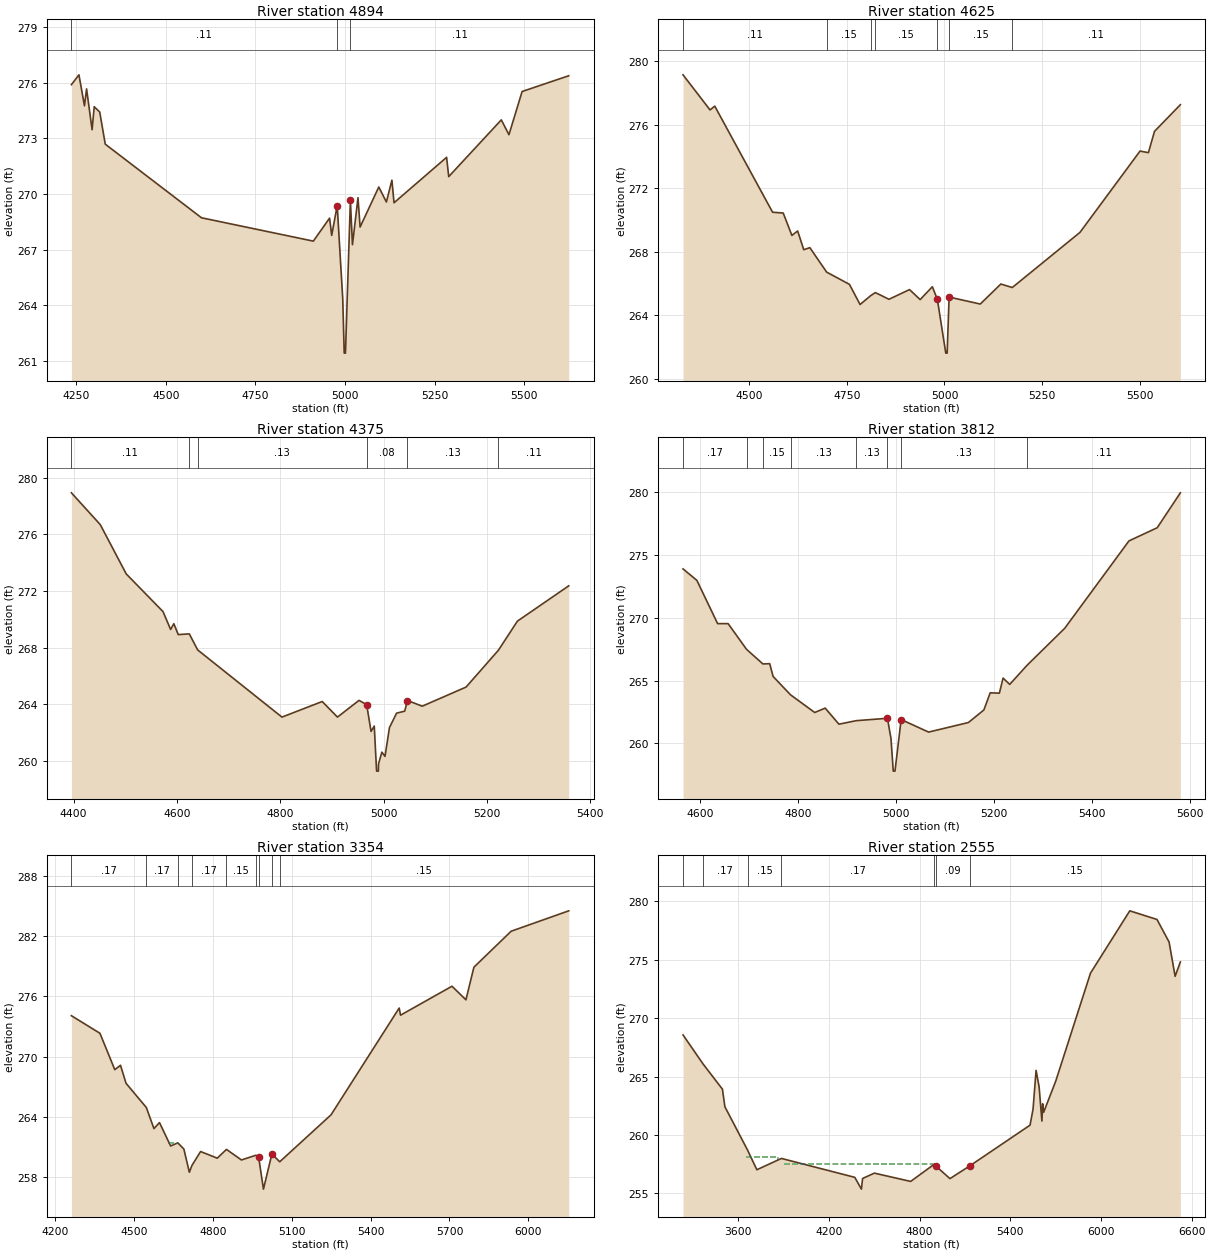
Type RM Length L Ch R = 1 ,4894    ,269,269,269
BEGIN DESCRIPTION:
WFSJR 048 4.0
END DESCRIPTION:
XS GIS Cut Line= 2
      3757311.69     10252846.55      3756131.97      10252117.9
#Sta/Elev= 30
    4237   275.9    4258  276.43  4273.4  274.76  4279.3  275.67  4294.7  273.47
  4300.6  274.71    4316  274.42  4331.4  272.69  4599.7  268.72  4911.5  267.46
  4956.8   268.7  4962.7  267.77  4978.1  269.38  4993.5  264.35  4997.6  261.42
  5001.1  261.42  5014.8  269.66  5020.6  267.27    5036   269.8  5041.9  268.22
    5094  270.38  5115.2  269.57  5130.6  270.75  5136.5  269.53  5283.1  271.98
    5289  270.94  5435.6     274  5456.9   273.2  5493.6  275.53  5623.6  276.38
#Mann= 3 , 0 , 0
    4237     .11       0  4978.1     .07       0  5014.8     .11       0
Bank Sta=4978.1,5014.8
XS Rating Curve= 0 ,0
Exp/Cntr=0.3,0.1

Type RM Length L Ch R = 1 ,4625    ,250,250,250
BEGIN DESCRIPTION:
Mapping XS b32f3ef3
END DESCRIPTION:
XS GIS Cut Line= 2
      3757407.21     10252594.84      3756313.42     10251943.77
#Sta/Elev= 30
  4330.8  279.13  4399.9  276.92    4412  277.16    4560  270.48  4587.2  270.43
  4609.4  269.02  4624.2   269.3  4639.8  268.12  4655.4  268.25  4698.4  266.71
  4756.7  265.94  4783.9  264.67  4810.7  265.22    4823  265.42  4857.9     265
  4910.5  265.61  4937.7  264.98  4968.9  265.79  4981.8  264.99  5003.3  261.61
  5006.8  261.61  5011.8  265.14  5091.6   264.7  5144.2  265.96  5173.5  265.74
  5346.7  269.21  5500.5  274.33  5521.9  274.23  5537.5  275.57  5603.7  277.25
#Mann= 7 ,-1 , 0
  4330.8     .11       0  4698.4     .15       0  4810.7     .11       0
    4823     .15       0  4981.8     .09       0  5011.8     .15       0
  5173.5     .11       0
Bank Sta=4981.8,5011.8
XS Rating Curve= 0 ,0
Exp/Cntr=0.3,0.1

Type RM Length L Ch R = 1 ,4375    ,563,563,563
BEGIN DESCRIPTION:
WFSJR 048 3.0
END DESCRIPTION:
XS GIS Cut Line= 3
      3757398.43     10252378.45      3756878.79     10252004.21
      3756667.83     10251761.05
#Sta/Elev= 30
  4395.9  278.92  4451.7  276.68    4502   273.2  4573.2  270.54  4587.9  269.28
  4594.1  269.69  4602.6  268.92    4624  268.97  4640.2  267.84  4803.3   263.1
  4881.2   264.2  4910.7   263.1  4952.4  264.28  4967.2  263.98  4975.7  262.09
  4981.9  262.47  4986.4  259.29  4989.9  259.29  4990.1  259.79  4996.6  260.63
  5002.7  260.33  5011.3  262.36  5025.1  263.38  5040.8  263.52  5046.2  264.27
  5074.7  263.87  5159.6  265.22  5222.2  267.82  5258.9  269.87  5358.2  272.36
#Mann= 6 ,-1 , 0
  4395.9     .11       0    4624     .17       0  4640.2     .13       0
  4967.2     .08       0  5046.2     .13       0  5222.2     .11       0
Bank Sta=4967.2,5046.2
XS Rating Curve= 0 ,0
Exp/Cntr=0.3,0.1

Type RM Length L Ch R = 1 ,3812    ,458,458,458
BEGIN DESCRIPTION:
WFSJR 048 2.0
END DESCRIPTION:
XS GIS Cut Line= 3
      3757517.87     10252061.09      3757218.23     10251746.84
      3756667.84     10251561.07
#Sta/Elev= 30
  4565.8   273.9    4594  272.99  4636.4  269.54  4657.8  269.54  4695.5  267.49
  4728.8  266.33  4742.7  266.35  4749.7  265.33  4785.2  263.87  4834.6  262.46
    4856  262.81    4884  261.53  4919.5  261.81    4983     262  4990.3  260.37
  4994.9  257.79  4998.4  257.79    5011   261.9    5067   260.9  5148.2  261.66
  5179.8  262.66  5192.8  264.03  5211.5     264    5219   265.2  5232.6   264.7
  5268.2  266.23  5344.9  269.17    5476  276.13  5533.7  277.18  5580.9  279.96
#Mann= 8 ,-1 , 0
  4565.8     .17       0  4695.5     .11       0  4728.8     .15       0
  4785.2     .13       0  4919.5     .13       0    4983     .08       0
    5011     .13       0  5268.2     .11       0
Bank Sta=4983,5011
XS Rating Curve= 0 ,0
Exp/Cntr=0.3,0.1

Type RM Length L Ch R = 1 ,3354    ,799,799,799
BEGIN DESCRIPTION:
Mapping XS 0008ab86
END DESCRIPTION:
XS GIS Cut Line= 3
      3757919.31       10251883.      3757407.17     10251431.62
       3756211.1     10251249.61
#Sta/Elev= 30
  4261.4  274.08    4370  272.33  4426.5  268.71  4448.3  269.15  4469.2  267.36
  4546.5  264.95  4575.5  262.85  4596.6  263.45    4639  261.12  4666.4  261.43
  4689.3  260.82  4710.2  258.51  4719.8  259.17  4752.9  260.57  4816.4  259.91
  4851.5  260.78  4908.5  259.73  4963.6   260.2  4973.7  260.04  4992.2  256.83
  5024.3  260.32  5054.1  259.55  5249.4  264.22  5508.7  274.84  5513.8  274.13
  5709.6  277.01  5762.7  275.66    5793   278.9  5934.7  282.48  6153.9  284.51
#Mann= 9 ,-1 , 0
  4261.4     .17       0  4546.5     .17       0  4666.4     .17       0
  4719.8     .17       0  4851.5     .15       0  4963.6     .15       0
  4973.7     .09       0  5024.3     .15       0  5054.1     .15       0
#XS Ineff= 1 ,-1
    4630  4667.5  261.46
Permanent Ineff=
       F
Bank Sta=4973.7,5024.3
XS Rating Curve= 0 ,0
Exp/Cntr=0.3,0.1

Type RM Length L Ch R = 1 ,2555    ,1081,1081,1081
BEGIN DESCRIPTION:
Mapping XS 1a624a94
END DESCRIPTION:
XS GIS Cut Line= 3
      3758368.48      10251915.7      3757761.88     10250819.77
      3755723.15     10250867.39
#Sta/Elev= 30
  3233.6  268.57  3365.7  266.09  3494.5  263.92  3510.6  262.42  3660.5  258.71
  3722.4  257.02    3885  257.99  4370.4  256.37  4414.4  255.36  4422.1  256.27
  4500.2  256.73  4740.3  256.02  4893.9  257.47  4910.4   257.3  5000.4  256.26
  5130.4  257.34  5530.5  260.84  5550.5  262.22  5570.5  265.53  5590.5  264.13
  5609.1  261.19  5614.1  262.67  5620.5  261.94  5700.6  264.61  5930.6  273.86
  6190.7   279.2  6370.8  278.46  6450.8  276.53  6490.8  273.59  6525.5  274.82
#Mann= 7 ,-1 , 0
  3233.6     .11       0  3365.7     .17       0  3660.5     .15       0
    3885     .17       0  4893.9     .12       0  4910.4     .09       0
  5130.4     .15       0
#XS Ineff= 2 ,-1
    3650  3863.3   258.1    3900  4900.4  257.55
Permanent Ineff=
       T       T
Bank Sta=4910.4,5130.4
XS Rating Curve= 0 ,0
Exp/Cntr=0.3,0.1

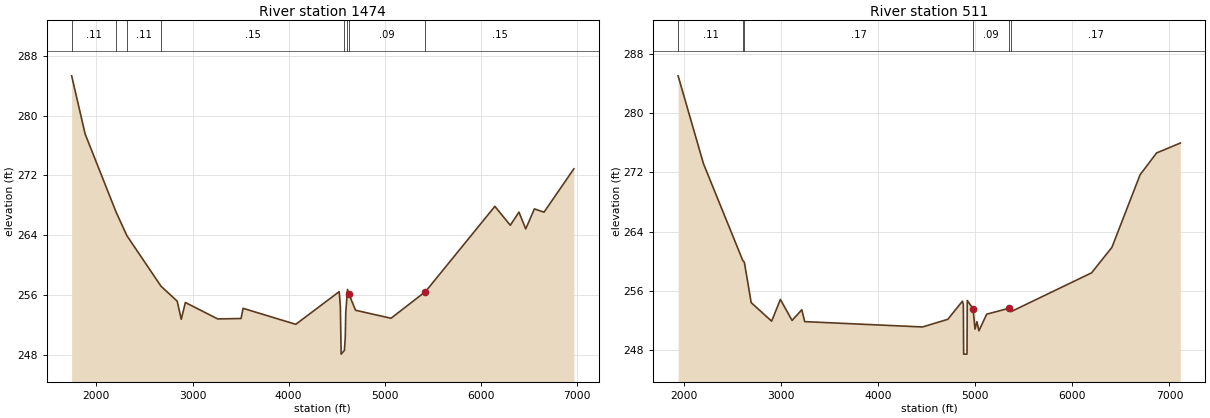
Type RM Length L Ch R = 1 ,1474    ,963,963,963
BEGIN DESCRIPTION:
Mapping XS da069a4c
END DESCRIPTION:
XS GIS Cut Line= 3
      3760419.31     10248992.39      3757511.34     10249964.61
      3755358.59     10250120.86
#Sta/Elev= 30
  1742.5  285.33  1883.3  277.53    2204  267.12  2316.9  263.94    2673  257.16
  2840.6  255.17  2882.8  252.74  2925.6  254.99  3262.4  252.79  3504.9  252.85
    3526  254.21  4074.3  252.07  4525.9  256.44  4538.2  254.46  4546.4  248.08
  4579.9  248.58  4589.1  250.29  4594.4  253.64    4612  256.73    4626  256.15
  4696.4  253.95    5065  252.88  5423.8  256.45  6145.7  267.86  6306.1  265.33
  6396.3  267.09  6466.5  264.84  6556.8  267.52    6657  267.08  6967.1  272.88
#Mann= 8 ,-1 , 0
  1742.5     .11       0    2204     .17       0  2316.9     .11       0
    2673     .15       0  4579.9     .15       0    4612     .15       0
    4626     .09       0  5423.8     .15       0
#XS Ineff= 1 ,-1
    2645    4612  256.73
Permanent Ineff=
       T
Bank Sta=4626,5423.8
XS Rating Curve= 0 ,0
Exp/Cntr=0.3,0.1

Type RM Length L Ch R = 1 ,511     ,0,0,0
BEGIN DESCRIPTION:
WFSJR 048 1.0
END DESCRIPTION:
XS GIS Cut Line= 3
      3760358.58     10248879.54      3757537.38     10249077.46
      3755193.61     10249077.46
#Sta/Elev= 30
  1939.9     285  2201.3  273.15  2606.5   260.1  2622.3  259.87  2692.5  254.44
    2903  251.94  2993.2  254.87  3113.5  252.04  3213.8  253.48  3243.8  251.88
  4456.8  251.16  4717.4  252.19  4867.6  254.63  4877.6  254.19  4880.6   247.5
  4914.5   247.5  4915.3     248  4917.6  254.73  4977.6  253.63  4997.6  250.87
  5017.6  251.88  5037.6  250.64  5117.6  252.88  5347.6  253.68  5367.6  253.22
  6197.6  258.45  6407.6  261.89  6697.6  271.67  6867.6  274.61  7111.8  275.94
#Mann= 6 ,-1 , 0
  1939.9     .11       0  2606.5     .17       0  2622.3     .17       0
  4977.6     .09       0  5347.6     .12       0  5367.6     .17       0
Bank Sta=4977.6,5347.6
XS Rating Curve= 0 ,0
Exp/Cntr=0.3,0.1

Chan Stop Cuts=-1
Use User Specified Reach Order=0
Composite Channel Slope=5