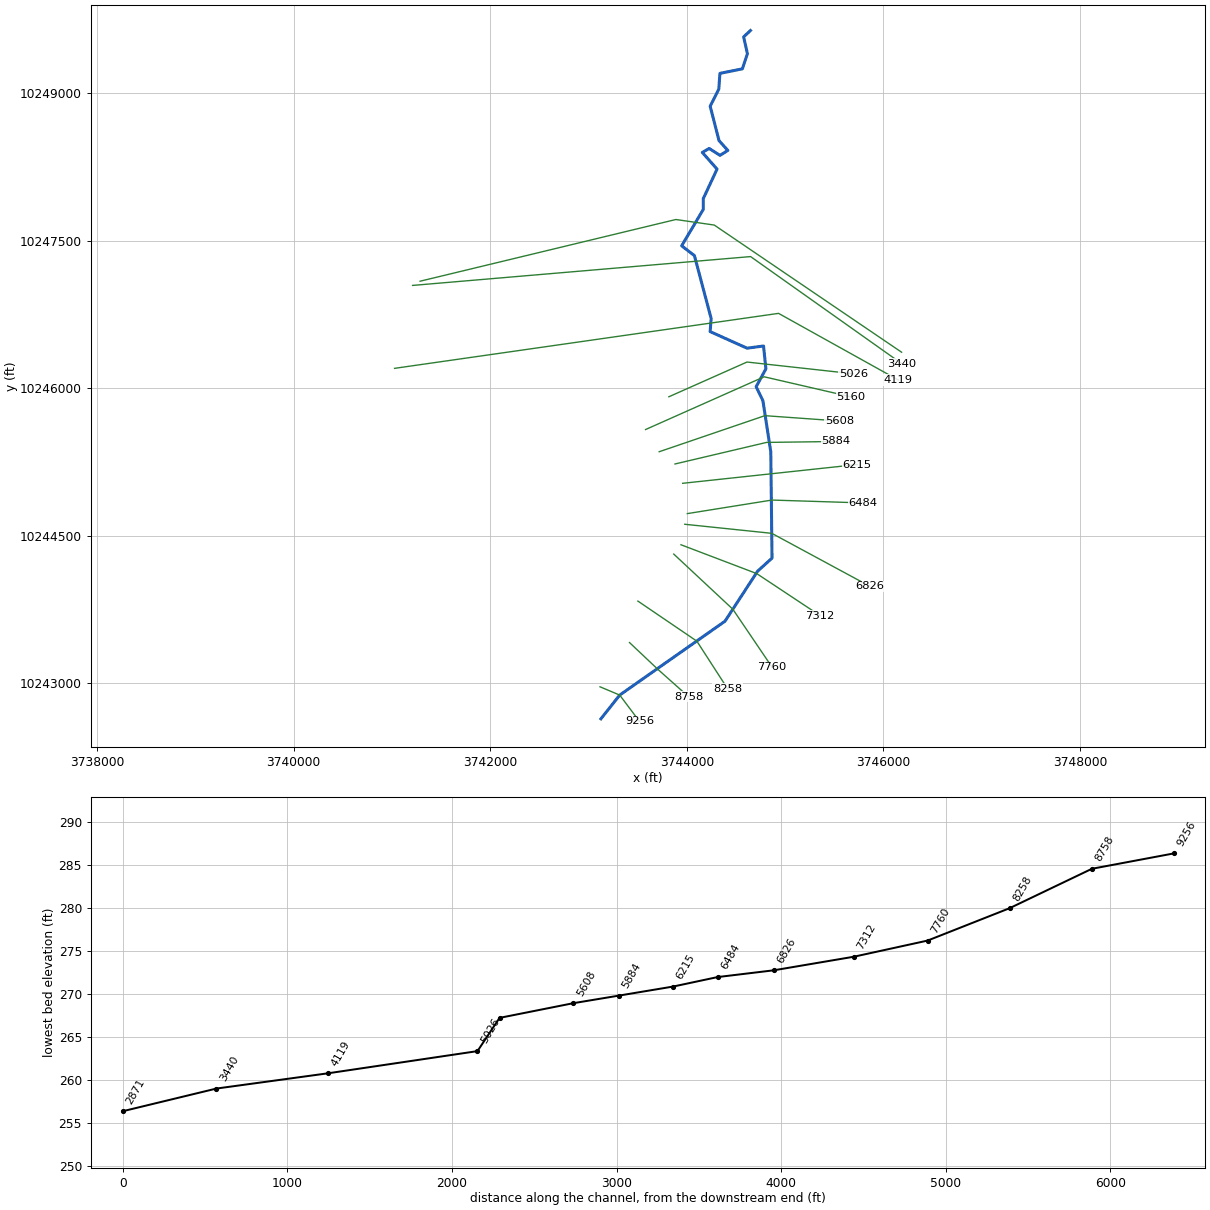
--- WFSJR 050.prj (project) ---

Proj Title=WFSJR 050 Base Level Engineering
Current Plan=p01
Default Exp/Contr=0.3,0.1
English Units
Geom File=g01
Flow File=f01
Plan File=p01
Y Axis Title=Elevation
X Axis Title(PF)=Main Channel Distance
X Axis Title(XS)=Station
BEGIN DESCRIPTION:
WFSJR 050
END DESCRIPTION:
DSS Export Rating Curves= 0
DSS Export Rating Curve Sorted= 0
DSS Export Volume Flow Curves= 0
DXF OffsetX= 0
DXF OffsetY= 0
DXF ScaleX= 1
DXF ScaleY= 10

--- WFSJR 050.p01 (plan) ---

Plan Title=Multiple Run
Program Version=4.10
Short Identifier=Multiple
Geom File=g01
Flow File=f01
Subcritical Flow
K Sum by GR= 0
Std Step Tol= 0.01
Critical Tol= 0.01
Num of Std Step Trials= 20
Max Error Tol= 0.3
Flow Tol Ratio= 0.001
Split Flow NTrial= 30
Split Flow Tol= 0.02
Split Flow Ratio= 0.02
Log Output Level= 0
Friction Slope Method= 1
Unsteady Friction Slope Method= 2
Unsteady Bridges Friction Slope Method= 1
Parabolic Critical Depth
Global Vel Dist= 1 , 1 , 1
Global Log Level= 0
CheckData=True
Encroach Param=-1 ,0,0, 0
BEGIN DESCRIPTION:
Multiple Run
END DESCRIPTION:
Computation Interval=1HOUR
Output Interval=1HOUR
Run HTab= 0
Run UNet= 0
Run PostProcess= 0
Run WQNet= 0
UNET Theta= 1
UNET Theta Warmup= 1
UNET ZTol= 0.02
UNET ZSATol= 0.05
UNET MxIter= 20
UNET MaxInSteps= 0
UNET DtIC= 0
UNET DtMin= 0
UNET MaxCRTS= 20
UNET WFStab= 2
UNET SFStab= 1
UNET WFX= 1
UNET SFX= 1
UNET DSS MLevel= 4
UNET DZMax Abort= 100
UNET Convert EG Bridges= 0
UNET Use Existing IB Tables=-1
UNET Froude Reduction=False
UNET Froude Limit= 1
UNET Froude Power= 10
UNET Time Slicing=0,0, 5
UNET Junction Losses=0
Instantaneous Interval=1HOUR
Write IC File= 0
Write IC File at Sim End=0
Echo Input=False
Echo Parameters=False
Echo Output=False
Write Detailed= 0
WQ AD Non Conservative
WQ ULTIMATE=-1
WQ Max Comp Step=1HOUR
WQ Output Interval=15MIN
WQ Output Selected Increments= 0
WQ Output face flow=0
WQ Output face velocity=0
WQ Output face area=0
WQ Output face dispersion=0
WQ Output cell volume=0
WQ Output cell surface area=0
WQ Output cell continuity=0
WQ Output cumulative cell continuity=0
WQ Output face conc=0
WQ Output face dconc_dx=0
WQ Output face courant=0
WQ Output face peclet=0
WQ Output face adv mass=0
WQ Output face disp mass=0
WQ Output cell mass=0
WQ Output cell source sink temp=0
WQ Output cell source sink nsm=0
WQ Output MaxMinRange=-1
WQ Daily Max Min Mean=-1
WQ Daily Range=0
WQ Daily Time=0
WQ Create Restart=0
WQ Fixed Restart=0
WQ System Summary=0
WQ Use Fixed Temperature=0
Sorting and Armoring Iterations= 10
XS Update Threshold= 0.02
Hydraulics Update Threshold= 0.02
Energy Slope Method= 1
Volume Change Method= 0
XS Weighting Method= 0
Number of US Weighted Cross Sections= 1
Number of DS Weighted Cross Sections= 1
Upstream XS Weight=0.25
Main XS Weight=0.5
Downstream XS Weight=0.25
Number of DS XS's Weighted with US Boundary= 1
Upstream Boundary Weight= 1
Weight of XSs Associated with US Boundary= 0
Number of US XS's Weighted with DS Boundary= 1
Downstream Boundary Weight= 0.5
Weight of XSs Associated with DS Boundary= 0.5
Sediment Output Level= 4
Mass or Volume Output= 0
Output Increment Type= 1
Profile and TS Output Increment= 10
XS Output Flag= 0
XS Output Increment= 10
Disregard all LS=0
Disregard all Conn=0
Disregard all Breaches=0
Disregard all Pumps=0

--- WFSJR 050.f01 (steady flow) ---

Flow Title=Multiple
Program Version=4.10
Number of Profiles= 7
Profile Names=10-year,25-year,50-year,1pct_min,100-year,1pct_plu,500-year
River Rch & RM=WFSJR 050,Reach-1         ,9256
     523     704     946     420    1268    3829    2348
River Rch & RM=WFSJR 050,Reach-1         ,8758
     786    1079    1472     660    1993    6019    3781
Boundary for River Rch & Prof#=WFSJR 050,Reach-1         , 1
Up Type= 0
Dn Type= 3
Dn Slope=0.005
Boundary for River Rch & Prof#=WFSJR 050,Reach-1         , 2
Up Type= 0
Dn Type= 3
Dn Slope=0.005
Boundary for River Rch & Prof#=WFSJR 050,Reach-1         , 3
Up Type= 0
Dn Type= 3
Dn Slope=0.005
Boundary for River Rch & Prof#=WFSJR 050,Reach-1         , 4
Up Type= 0
Dn Type= 3
Dn Slope=0.005
Boundary for River Rch & Prof#=WFSJR 050,Reach-1         , 5
Up Type= 0
Dn Type= 3
Dn Slope=0.005
Boundary for River Rch & Prof#=WFSJR 050,Reach-1         , 6
Up Type= 0
Dn Type= 3
Dn Slope=0.005
Boundary for River Rch & Prof#=WFSJR 050,Reach-1         , 7
Up Type= 0
Dn Type= 3
Dn Slope=0.005
DSS Import GetInterval= 0
DSS Import GetPeak= 0
DSS Import FillOption= 0

--- WFSJR 050.g01 (geometry) ---

Geom Title=Existing Conditions
Program Version=4.10

River Reach=WFSJR 050       ,Reach-1
Reach XY= 30
       3743126.8     10242635.41      3743318.23     10242876.84
      3744388.63      10243627.8      3744720.82     10244137.15
       3744867.4     10244270.03      3744854.75     10245350.96
       3744774.6     10245871.91      3744706.05     10246013.22
      3744805.18     10246195.66      3744780.93     10246427.67
      3744613.25     10246405.52      3744237.82     10246574.25
      3744248.23     10246706.84      3744078.23     10247346.84
      3743948.23     10247446.84      3744168.23     10247816.84
      3744168.23     10247926.84      3744308.23     10248226.84
      3744158.23     10248396.84      3744228.23     10248436.84
      3744338.23     10248366.84      3744418.23     10248416.84
      3744328.23     10248516.84      3744238.23     10248866.84
      3744325.83     10249039.81      3744337.38     10249200.77
      3744565.89     10249246.85      3744616.99     10249401.04
      3744578.86     10249571.74      3744648.23     10249636.84

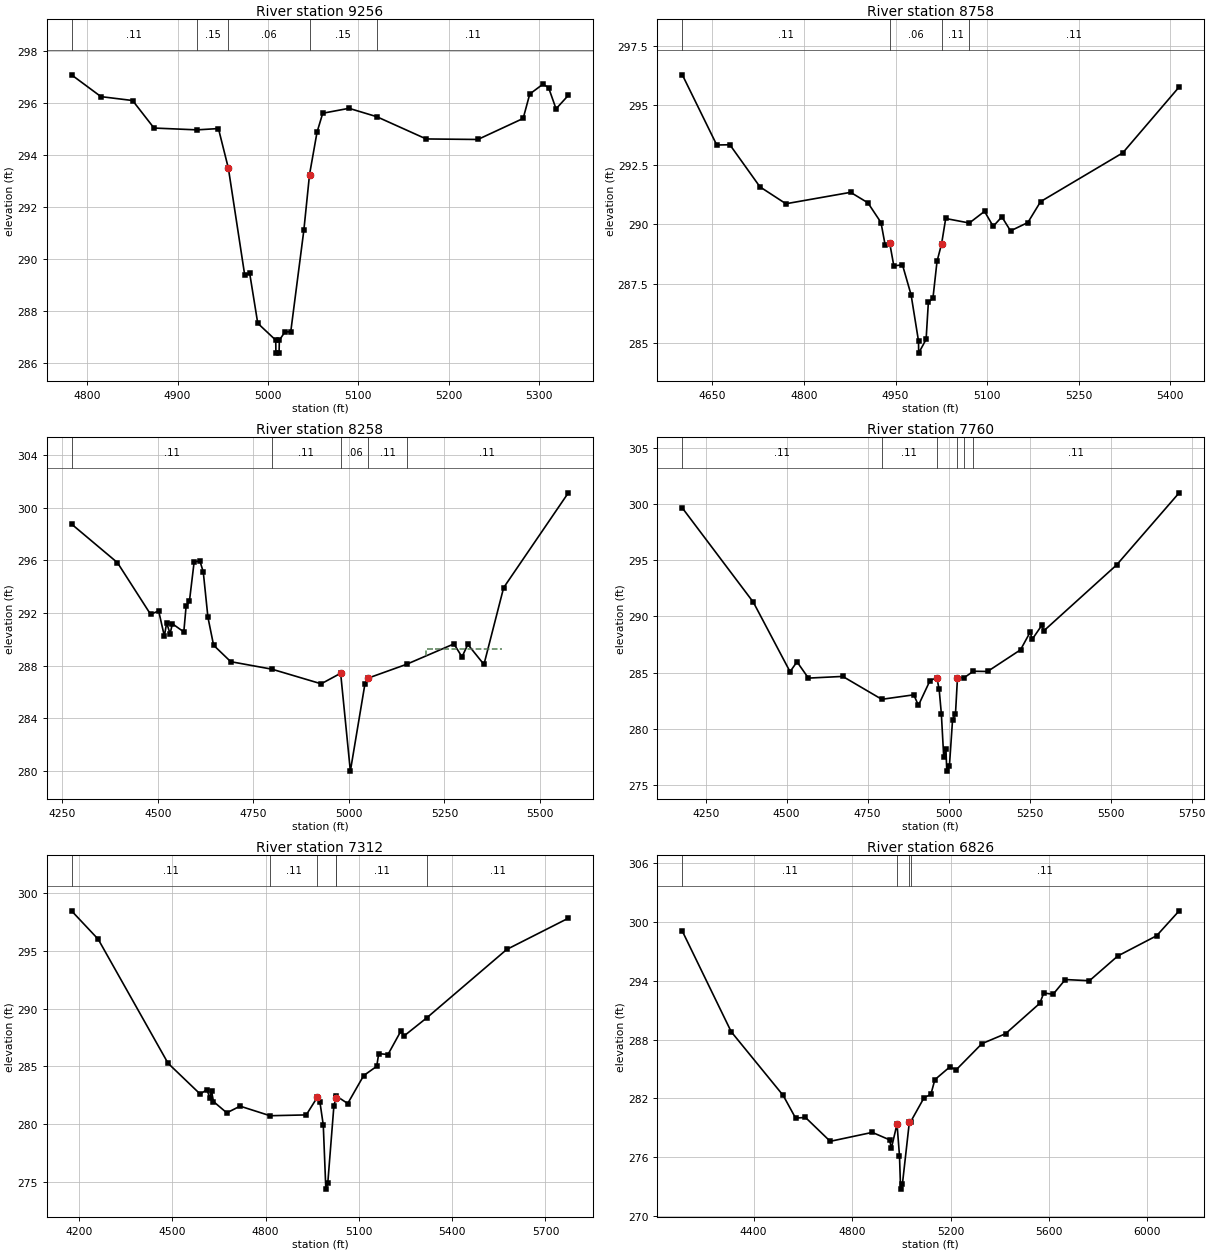
Type RM Length L Ch R = 1 ,9256    ,498,498,498
BEGIN DESCRIPTION:
WFSJR 050 13.0
END DESCRIPTION:
XS GIS Cut Line= 3
      3743117.82     10242961.09      3743318.23     10242876.84
      3743517.86     10242611.06
#Sta/Elev= 30
  4782.6  297.09  4815.2  296.25  4850.2   296.1  4873.9  295.04  4921.4  294.97
  4945.2  295.02  4956.2  293.49  4974.3  289.37  4979.8  289.44  4988.7  287.52
  5008.6  286.87  5008.8  286.37  5012.3  286.37  5012.6  286.87  5018.9  287.19
  5025.2  287.19  5039.7   291.1    5046  293.25  5054.3  294.88  5060.6  295.61
  5089.7   295.8  5120.2  295.48  5175.1  294.62  5232.3   294.6  5282.4  295.41
  5289.7  296.35  5304.3  296.73  5310.5   296.6  5318.8  295.78  5332.4   296.3
#Mann= 5 ,-1 , 0
  4782.6     .11       0  4921.4     .15       0  4956.2     .06       0
    5046     .15       0  5120.2     .11       0
Bank Sta=4956.2,5046
XS Rating Curve= 0 ,0
Exp/Cntr=0.3,0.1

Type RM Length L Ch R = 1 ,8758    ,500,500,500
BEGIN DESCRIPTION:
WFSJR 050 12.0
END DESCRIPTION:
XS GIS Cut Line= 3
      3743417.85     10243411.07      3743708.23     10243136.84
      3744017.83     10242861.09
#Sta/Elev= 30
  4600.6  296.28    4657  293.33  4678.5  293.34  4727.8  291.57  4770.3  290.86
  4876.3  291.34  4904.6   290.9  4926.1  290.07  4932.9  289.12  4940.2  289.23
  4947.1  288.25  4961.3  288.29  4975.4  287.03  4987.6  285.08  4987.8  284.58
    5000  285.16  5003.7  286.72  5011.2  286.89  5017.9  288.44  5025.4  289.18
  5032.1  290.24  5070.8  290.05  5095.7  290.54  5109.9  289.91  5124.1  290.31
  5138.3  289.72  5166.7  290.07  5187.6  290.95  5322.2     293  5414.6  295.77
#Mann= 4 ,-1 , 0
  4600.6     .11       0  4940.2     .06       0  5025.4     .11       0
  5070.8     .11       0
#XS Ineff= 1 ,-1
    4700  4876.3  291.34
Permanent Ineff=
       F
Bank Sta=4940.2,5025.4
XS Rating Curve= 0 ,0
Exp/Cntr=0.3,0.1

Type RM Length L Ch R = 1 ,8258    ,498,498,498
BEGIN DESCRIPTION:
WFSJR 050 11.0
END DESCRIPTION:
XS GIS Cut Line= 3
      3743502.76     10243833.07      3744102.84     10243425.32
      3744414.26     10242943.27
#Sta/Elev= 30
  4274.5  298.75  4394.6  295.82  4481.4  291.89  4502.4  292.16  4517.3  290.24
  4523.4  291.25  4532.3  290.41  4538.3  291.18  4568.2  290.56  4574.2   292.5
  4582.9  292.89  4595.2  295.87  4610.2  295.96  4619.1  295.11  4631.3  291.67
  4646.1  289.55  4690.9   288.3  4798.7  287.73  4927.5  286.62  4978.4  287.42
  5003.8  279.99  5041.8  286.59    5051  287.06  5150.7   288.1  5274.7  289.65
  5295.8  288.66    5311  289.61  5353.2  288.09  5404.7  293.92  5573.9  301.12
#Mann= 5 ,-1 , 0
  4274.5     .11       0  4798.7     .11       0  4978.4     .06       0
    5051     .11       0  5150.7     .11       0
#XS Ineff= 1 ,-1
  5202.1    5400  289.24
Permanent Ineff=
       F
Bank Sta=4978.4,5051
XS Rating Curve= 0 ,0
Exp/Cntr=0.3,0.1

Type RM Length L Ch R = 1 ,7760    ,448,448,448
BEGIN DESCRIPTION:
WFSJR 050 10.0
END DESCRIPTION:
XS GIS Cut Line= 3
      3743867.82     10244311.11      3744468.77     10243750.13
      3744867.84     10243161.08
#Sta/Elev= 30
  4177.9  299.67  4397.1  291.27  4510.4  285.08  4531.9  285.96  4567.1  284.51
  4673.1  284.66  4793.5  282.62  4892.4  283.02  4906.6  282.08  4942.3  284.28
  4963.3  284.55  4970.6  283.53  4977.4  281.34  4984.8  277.46  4991.6  278.17
  4994.2  276.22  5002.4  276.72  5012.1  280.82    5021  281.29  5027.1  284.48
  5048.1  284.55  5076.1  285.12    5120   285.1  5221.8  287.03  5251.7  288.61
  5257.7  287.96  5287.6  289.22  5293.7  288.72  5518.3  294.59  5711.5  301.02
#Mann= 6 ,-1 , 0
  4177.9     .11       0  4793.5     .11       0  4963.3     .06       0
  5027.1     .11       0  5048.1     .15       0  5076.1     .11       0
Bank Sta=4963.3,5027.1
XS Rating Curve= 0 ,0
Exp/Cntr=0.3,0.1

Type RM Length L Ch R = 1 ,7312    ,486,486,486
BEGIN DESCRIPTION:
WFSJR 050 9.0
END DESCRIPTION:
XS GIS Cut Line= 3
       3743941.2     10244405.95      3744711.32      10244112.9
      3745356.11     10243685.46
#Sta/Elev= 30
    4176  298.49  4261.7  296.03  4486.5  285.26  4589.7  282.59  4611.1  282.97
    4621  282.26  4626.3  282.85  4632.5  281.94  4675.3  280.96  4718.1  281.54
  4814.4  280.71  4930.8  280.78  4966.2   282.3  4974.9  281.88  4985.6   279.9
  4993.8  274.34    5000  274.84  5019.8  281.59  5026.6  282.26  5028.1  282.41
  5064.2  281.77  5115.4  284.19  5157.5     285  5163.8   286.1  5193.6  286.02
  5235.8  288.09  5244.7  287.62  5319.1  289.22  5575.6  295.14  5773.6  297.85
#Mann= 6 ,-1 , 0
    4176     .11       0  4814.4     .11       0  4966.2     .06       0
  5026.6     .11       0  5028.1     .11       0  5319.1     .11       0
Bank Sta=4966.2,5026.6
XS Rating Curve= 0 ,0
Exp/Cntr=0.3,0.1

Type RM Length L Ch R = 1 ,6826    ,342,342,342
BEGIN DESCRIPTION:
WFSJR 050 8.0
END DESCRIPTION:
XS GIS Cut Line= 3
      3743980.18      10244614.3      3744865.29     10244522.07
      3745858.53     10243985.51
#Sta/Elev= 30
  4110.1  299.04  4308.8  288.79    4520   282.3  4570.2     280  4610.5  280.06
    4711  277.63  4881.9  278.54  4952.3  277.78  4959.4  276.92  4982.5  279.39
  4992.5  276.16    4997  272.76  5004.3  273.26  5032.5  279.57  5038.2  279.64
  5092.5  282.08    5120  282.41  5136.2  283.91  5196.1  285.19  5223.8  284.94
  5327.5  287.58  5423.4  288.59  5562.6  291.69  5578.8  292.74  5616.7  292.61
  5666.3  294.11  5764.4  293.99  5879.5  296.51  6037.2  298.57  6128.9  301.11
#Mann= 4 ,-1 , 0
  4110.1     .11       0  4982.5     .06       0  5032.5     .11       0
  5038.2     .11       0
Bank Sta=4982.5,5032.5
XS Rating Curve= 0 ,0
Exp/Cntr=0.3,0.1

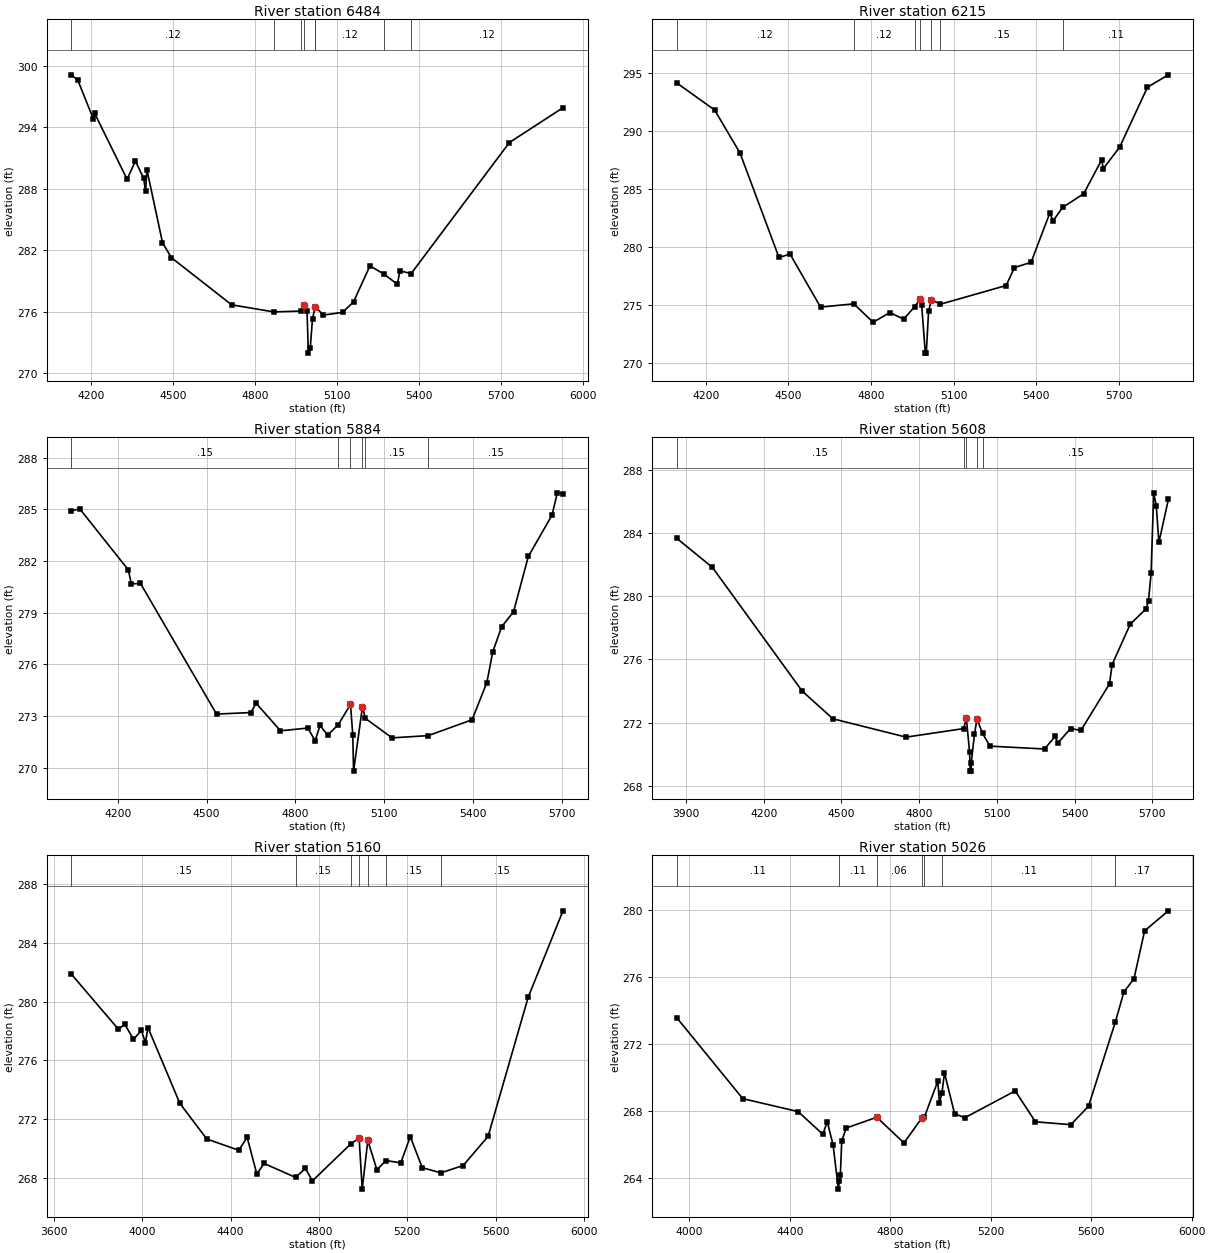
Type RM Length L Ch R = 1 ,6484    ,269,269,269
BEGIN DESCRIPTION:
WFSJR 050 7.0
END DESCRIPTION:
XS GIS Cut Line= 3
      3744006.21      10244722.8      3744866.35     10244860.58
      3745793.68     10244831.34
#Sta/Elev= 30
  4128.9  299.11  4152.7   298.6  4209.7  294.81  4214.7  295.34  4333.1  288.93
  4363.5   290.7  4393.9  289.02  4400.7  287.74  4405.8  289.85  4462.7  282.75
  4495.2  281.28  4715.7  276.68  4869.9  275.99  4968.8  276.07  4981.3  276.64
  4991.4  276.03  4996.5  271.97  5003.3  272.47  5011.5  275.33 5021.48  276.49
  5051.5  275.68  5121.6  275.95  5161.6  276.97  5221.6  280.48  5273.3  279.67
  5321.7  278.69  5331.7     280  5372.2  279.72  5731.9  292.51  5927.8   295.9
#Mann= 9 ,-1 , 0
  4128.9     .12       0  4869.9     .12       0  4968.8     .12       0
  4981.3     .06       0 5021.48     .09       0  5021.5     .12       0
  5021.5     .12       0  5273.3     .17       0  5372.2     .12       0
Bank Sta=4981.3,5021.48
XS Rating Curve= 0 ,0
Exp/Cntr=0.3,0.1

Type RM Length L Ch R = 1 ,6215    ,331,331,331
BEGIN DESCRIPTION:
Mapping XS e326d37f
END DESCRIPTION:
XS GIS Cut Line= 2
      3743958.52     10245030.97      3745733.28      10245221.9
#Sta/Elev= 30
  4094.2  294.18  4232.3  291.83  4324.4  288.12  4465.7  279.12  4505.9  279.41
  4616.5  274.84  4737.2  275.12  4807.6  273.53    4868  274.37  4918.3   273.8
  4958.5  274.88  4978.4  275.53  4983.5  275.06    4997  270.87  5000.5  270.87
  5008.8  274.49  5018.8  275.48  5051.8  275.09  5290.4   276.7  5320.6  278.25
  5380.9   278.7  5448.5  282.93  5461.4   282.3  5495.3  283.43    5572  284.62
  5637.6  287.56  5642.6  286.76  5702.8  288.65  5803.3   293.8  5879.2  294.87
#Mann= 7 ,-1 , 0
  4094.2     .12       0  4737.2     .12       0  4958.5     .12       0
  4978.4     .06       0  5018.8     .12       0  5051.8     .15       0
  5495.3     .11       0
Bank Sta=4978.4,5018.8
XS Rating Curve= 0 ,0
Exp/Cntr=0.3,0.1

Type RM Length L Ch R = 1 ,5884    ,276,276,276
BEGIN DESCRIPTION:
WFSJR 050 6.0
END DESCRIPTION:
XS GIS Cut Line= 3
      3743880.41     10245227.51      3744811.51     10245446.92
      3745514.75     10245456.29
#Sta/Elev= 30
  4043.4   284.9  4071.6  285.04    4236  281.49  4246.2  280.68  4277.1   280.7
  4533.9  273.12  4649.8  273.21  4667.5  273.75  4749.7  272.15  4842.1  272.31
  4866.7  271.57  4883.2  272.46    4909   271.9  4944.9  272.51    4986  273.68
  4993.7  271.93  4996.4  269.81  5026.3  273.53  5036.3  272.87  5126.4  271.74
  5248.4  271.87  5396.4  272.79  5446.4  274.95  5466.4  276.74  5496.4  278.19
  5536.4  279.06  5586.4  282.27  5666.4  284.67  5684.1  285.96  5703.3   285.9
#Mann= 6 ,-1 , 0
  4043.4     .15       0  4944.9     .11       0    4986     .06       0
  5026.3     .11       0  5036.3     .15       0  5248.4     .15       0
Bank Sta=4986,5026.3
XS Rating Curve= 0 ,0
Exp/Cntr=0.3,0.1

Type RM Length L Ch R = 1 ,5608    ,448,448,448
BEGIN DESCRIPTION:
WFSJR 050 5.0
END DESCRIPTION:
XS GIS Cut Line= 3
      3743719.82     10245352.15      3744794.64       10245719.
       3745554.3     10245664.75
#Sta/Elev= 30
  3864.3  283.66  4002.6  281.81  4348.3     274  4467.2  272.24  4749.8  271.08
  4971.7  271.62  4982.3  272.26  4994.5  270.15  4997.3  268.93  5000.8  268.93
  5001.1  269.43  5013.3  271.25  5023.3  272.22  5044.7  271.31  5073.4  270.51
  5283.9  270.33  5325.5  271.14  5334.1  270.69  5384.2  271.62  5424.3  271.51
  5534.6  274.45  5544.6  275.67  5614.8  278.23  5674.9  279.18    5685  279.71
    5695  281.43    5705  286.53    5715  285.71  5725.1  283.39  5761.6  286.11
#Mann= 5 ,-1 , 0
  3864.3     .15       0  4971.7     .11       0  4982.3     .06       0
  5023.3     .11       0  5044.7     .15       0
Bank Sta=4982.3,5023.3
XS Rating Curve= 0 ,0
Exp/Cntr=0.3,0.1

Type RM Length L Ch R = 1 ,5160    ,134,134,134
BEGIN DESCRIPTION:
WFSJR 050 4.0
END DESCRIPTION:
XS GIS Cut Line= 3
      3743580.92     10245577.85      3744787.25     10246114.46
      3745667.87     10245911.07
#Sta/Elev= 30
  3679.7  281.89  3893.3  278.12    3922  278.46  3960.9  277.44  3997.2  278.04
    4015   277.2  4026.6  278.24  4170.9  273.07  4292.6  270.64  4437.5  269.87
  4475.3  270.75  4519.1  268.25  4551.9  268.97  4694.2  268.02  4738.4  268.63
  4770.8  267.79  4945.9  270.33  4981.8  270.69  4995.8  267.22  5021.1  270.54
  5062.2  268.54  5103.2  269.17  5170.3  269.01    5213   270.8  5267.5  268.68
  5351.5  268.33  5452.2  268.83  5565.1  270.82  5746.5  280.31  5903.8   286.2
#Mann= 7 ,-1 , 0
  3679.7     .15       0  4694.2     .15       0  4945.9     .11       0
  4981.8     .06       0  5021.1     .11       0  5103.2     .15       0
  5351.5     .15       0
Bank Sta=4981.8,5021.1
XS Rating Curve= 0 ,0
Exp/Cntr=0.3,0.1

Type RM Length L Ch R = 1 ,5026    ,907,907,907
BEGIN DESCRIPTION:
WFSJR 050 3.0
END DESCRIPTION:
XS GIS Cut Line= 3
      3743817.85     10245911.07      3744612.77     10246264.49
      3745693.78     10246145.39
#Sta/Elev= 30
  3949.7  273.57    4213  268.74  4433.2  267.97  4531.7  266.62  4549.5  267.37
  4572.7  265.96  4593.6  263.35  4597.4  263.85  4601.4  264.17  4606.9  266.21
  4624.7  266.99  4746.4  267.63  4854.9   266.1  4925.4  267.58  4935.4  267.62
  4989.3  269.78  4995.8  268.51  5005.8  269.06  5015.9  270.28  5056.1  267.85
  5096.4   267.6  5297.6   269.2  5378.1  267.36  5518.9  267.19  5589.4  268.29
  5695.8  273.29  5730.2  275.09  5770.4  275.89  5812.7  278.74  5907.2  279.93
#Mann= 7 ,-1 , 0
  3949.7     .11       0  4597.4     .11       0  4746.4     .06       0
  4925.4     .11       0  4935.4     .11       0  5005.8     .11       0
  5695.8     .17       0
#XS Ineff= 1 ,-1
  5015.9    5680  270.28
Permanent Ineff=
       F
Bank Sta=4746.4,4925.4
XS Rating Curve= 0 ,0
Exp/Cntr=0.3,0.1

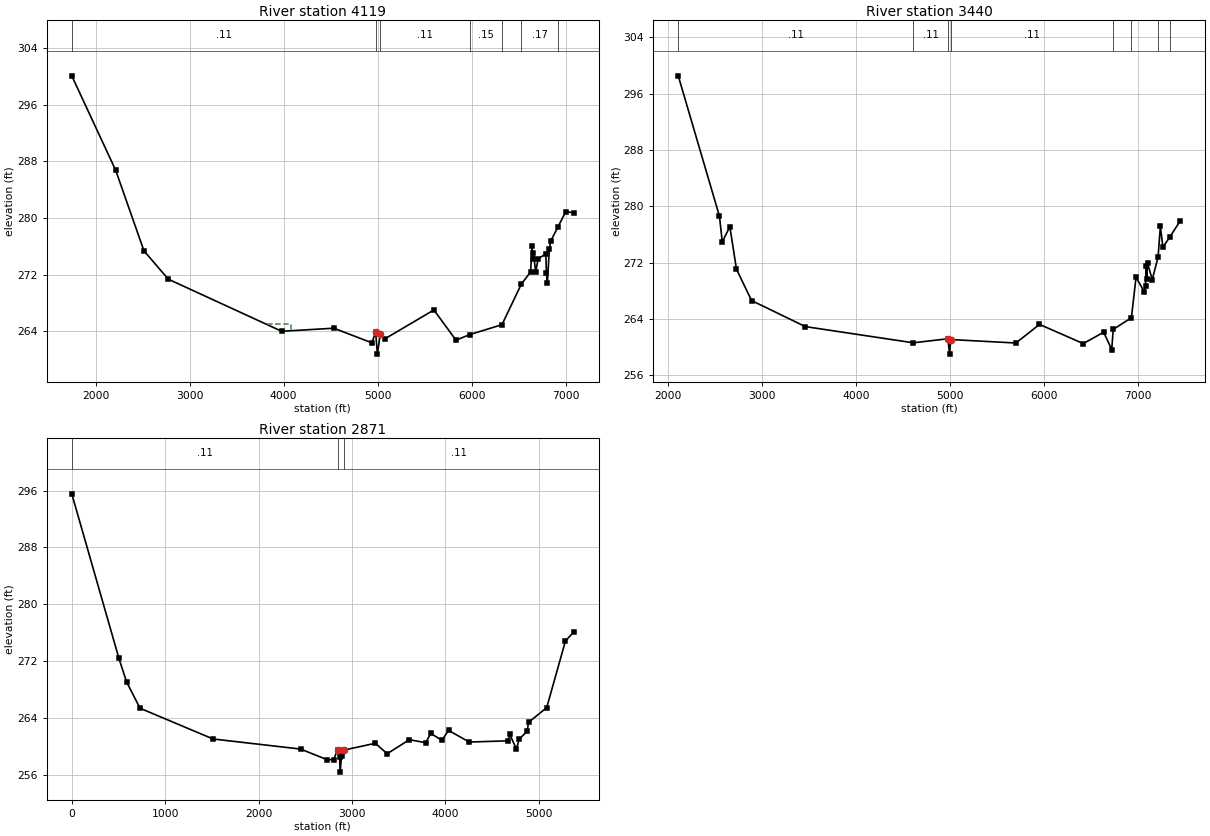
Type RM Length L Ch R = 1 ,4119    ,679,679,679
BEGIN DESCRIPTION:
WFSJR 050 2.0
END DESCRIPTION:
XS GIS Cut Line= 3
      3741027.88     10246200.31      3744933.67     10246759.59
      3746153.01     10246081.16
#Sta/Elev= 30
  1746.8  300.09  2213.6  286.76  2514.5  275.37  2773.6  271.36  3979.4     264
  4534.4  264.43    4939  262.37  4979.4  263.87  4997.9  260.77  5028.8  263.64
  5080.4  262.95  5598.9  267.01  5834.5  262.74  5978.3  263.52  6322.9  264.93
  6530.4  270.69  6627.5  272.37  6643.5  276.02  6649.3  274.17  6658.5  275.03
  6681.3  272.38  6708.7  274.25  6789.9  274.94  6795.8  272.27  6805.9  270.82
  6827.6  275.65  6841.6  276.74  6917.8  278.71  7001.8  280.91  7087.8  280.74
#Mann= 7 ,-1 , 0
  1746.8     .11       0  4979.4     .06       0  5028.8     .11       0
  5978.3     .15       0  6322.9     .11       0  6530.4     .17       0
  6917.8     .11       0
#XS Ineff= 2 ,-1
    3820  4080.3  265.07  5598.9    6460  267.01
Permanent Ineff=
       F       F
Bank Sta=4979.4,5028.8
XS Rating Curve= 0 ,0
Exp/Cntr=0.3,0.1

Type RM Length L Ch R = 1 ,3440    ,569,569,569
BEGIN DESCRIPTION:
WFSJR 050 1.0
END DESCRIPTION:
XS GIS Cut Line= 3
      3741211.24     10247043.81      3744649.44     10247337.21
      3746189.77     10246246.14
#Sta/Elev= 30
  2111.3  298.52  2549.5  278.58  2579.6  274.92  2659.9   277.1  2730.5  271.06
  2890.7   266.6  3462.8   262.9  4609.9   260.6  4978.3  261.17  4996.6  258.99
  5008.4  261.06  5701.7  260.57  5952.2  263.21  6417.9  260.49  6634.5   262.1
  6720.6  259.64  6736.2  262.51  6929.4  264.15    6979   269.9  7065.2  267.87
  7079.6  268.64  7086.1  271.47  7092.2  269.72  7100.9  271.91  7151.3  269.58
  7213.2  272.77  7237.5  277.12  7264.5  274.17  7334.7  275.56  7449.6  277.93
#Mann= 8 ,-1 , 0
  2111.3     .11       0  4609.9     .11       0  4978.3     .06       0
  5008.4     .11       0  6736.2     .15       0  6929.4     .11       0
  7213.2     .17       0  7334.7     .11       0
#XS Ineff= 1 ,-1
  5952.2    6960  263.21
Permanent Ineff=
       F
Bank Sta=4978.3,5008.4
XS Rating Curve= 0 ,0
Exp/Cntr=0.3,0.1

Type RM Length L Ch R = 1 ,2871    ,0,0,0
XS GIS Cut Line= 4
      3741287.63     10247086.66       3743889.2     10247714.26
      3744279.82     10247657.84       3746185.2     10246364.44
#Sta/Elev= 30
       0  295.56   504.2   272.4   586.6  269.06   730.6  265.35  1512.4  261.02
  2448.5   259.6  2731.9  258.11  2802.3  258.11  2846.6  259.53  2866.8   258.5
  2872.6  256.35    2887   258.6  2917.3  259.47  3247.9  260.41  3376.7  258.95
  3613.3  260.92  3786.9   260.5  3843.8  261.81  3960.6  260.82  4032.4  262.23
  4254.1  260.59  4673.2  260.76  4688.1  261.66    4760  259.59    4787  260.98
  4873.9   262.1  4888.8  263.36  5083.4  265.44  5284.1  274.84  5373.8  276.11
#Mann= 3 , 0 , 0
       0     .11       0  2846.6     .06       0  2917.3     .11       0
Bank Sta=2846.6,2917.3
XS Rating Curve= 0 ,0
Exp/Cntr=0.3,0.1

Chan Stop Cuts=-1
Use User Specified Reach Order=0
Composite Channel Slope=5