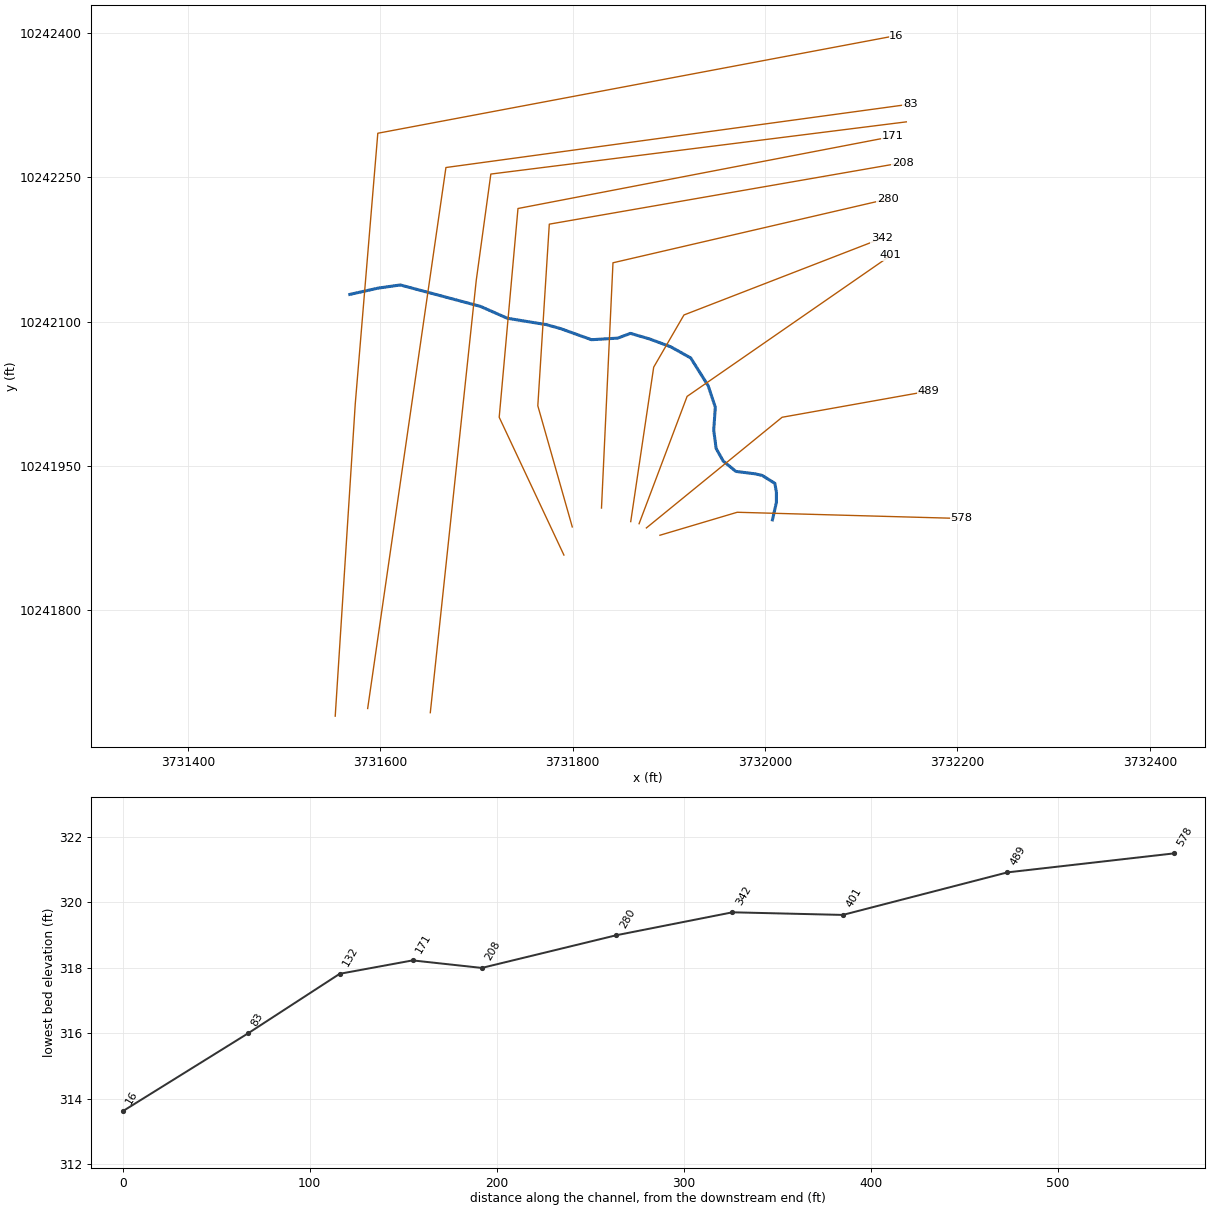
--- WFSJR 051.prj (project) ---

Proj Title=WFSJR 051 Base Level Engineering
Current Plan=p01
Default Exp/Contr=0.3,0.1
English Units
Geom File=g01
Flow File=f01
Plan File=p01
Y Axis Title=Elevation
X Axis Title(PF)=Main Channel Distance
X Axis Title(XS)=Station
BEGIN DESCRIPTION:
WFSJR 051
END DESCRIPTION:
DSS Export Rating Curves= 0
DSS Export Rating Curve Sorted= 0
DSS Export Volume Flow Curves= 0
DXF OffsetX= 0
DXF OffsetY= 0
DXF ScaleX= 1
DXF ScaleY= 10

--- WFSJR 051.p01 (plan) ---

Plan Title=Multiple Run
Program Version=4.10
Short Identifier=Multiple
Geom File=g01
Flow File=f01
Subcritical Flow
K Sum by GR= 0
Std Step Tol= 0.01
Critical Tol= 0.01
Num of Std Step Trials= 20
Max Error Tol= 0.3
Flow Tol Ratio= 0.001
Split Flow NTrial= 30
Split Flow Tol= 0.02
Split Flow Ratio= 0.02
Log Output Level= 0
Friction Slope Method= 1
Unsteady Friction Slope Method= 2
Unsteady Bridges Friction Slope Method= 1
Parabolic Critical Depth
Global Vel Dist= 1 , 1 , 1
Global Log Level= 0
CheckData=True
Encroach Param=-1 ,0,0, 0
BEGIN DESCRIPTION:
Multiple Run
END DESCRIPTION:
Computation Interval=1HOUR
Output Interval=1HOUR
Run HTab= 0
Run UNet= 0
Run PostProcess= 0
Run WQNet= 0
UNET Theta= 1
UNET Theta Warmup= 1
UNET ZTol= 0.02
UNET ZSATol= 0.05
UNET MxIter= 20
UNET MaxInSteps= 0
UNET DtIC= 0
UNET DtMin= 0
UNET MaxCRTS= 20
UNET WFStab= 2
UNET SFStab= 1
UNET WFX= 1
UNET SFX= 1
UNET DSS MLevel= 4
UNET DZMax Abort= 100
UNET Convert EG Bridges= 0
UNET Use Existing IB Tables=-1
UNET Froude Reduction=False
UNET Froude Limit= 1
UNET Froude Power= 10
UNET Time Slicing=0,0, 5
UNET Junction Losses=0
Instantaneous Interval=1HOUR
Write IC File= 0
Write IC File at Sim End=0
Echo Input=False
Echo Parameters=False
Echo Output=False
Write Detailed= 0
WQ AD Non Conservative
WQ ULTIMATE=-1
WQ Max Comp Step=1HOUR
WQ Output Interval=15MIN
WQ Output Selected Increments= 0
WQ Output face flow=0
WQ Output face velocity=0
WQ Output face area=0
WQ Output face dispersion=0
WQ Output cell volume=0
WQ Output cell surface area=0
WQ Output cell continuity=0
WQ Output cumulative cell continuity=0
WQ Output face conc=0
WQ Output face dconc_dx=0
WQ Output face courant=0
WQ Output face peclet=0
WQ Output face adv mass=0
WQ Output face disp mass=0
WQ Output cell mass=0
WQ Output cell source sink temp=0
WQ Output cell source sink nsm=0
WQ Output MaxMinRange=-1
WQ Daily Max Min Mean=-1
WQ Daily Range=0
WQ Daily Time=0
WQ Create Restart=0
WQ Fixed Restart=0
WQ System Summary=0
WQ Use Fixed Temperature=0
Sorting and Armoring Iterations= 10
XS Update Threshold= 0.02
Hydraulics Update Threshold= 0.02
Energy Slope Method= 1
Volume Change Method= 0
XS Weighting Method= 0
Number of US Weighted Cross Sections= 1
Number of DS Weighted Cross Sections= 1
Upstream XS Weight=0.25
Main XS Weight=0.5
Downstream XS Weight=0.25
Number of DS XS's Weighted with US Boundary= 1
Upstream Boundary Weight= 1
Weight of XSs Associated with US Boundary= 0
Number of US XS's Weighted with DS Boundary= 1
Downstream Boundary Weight= 0.5
Weight of XSs Associated with DS Boundary= 0.5
Sediment Output Level= 4
Mass or Volume Output= 0
Output Increment Type= 1
Profile and TS Output Increment= 10
XS Output Flag= 0
XS Output Increment= 10
Disregard all LS=0
Disregard all Conn=0
Disregard all Breaches=0
Disregard all Pumps=0

--- WFSJR 051.f01 (steady flow) ---

Flow Title=Multiple
Program Version=4.10
Number of Profiles= 7
Profile Names=10-year,25-year,50-year,1pct_min,100-year,1pct_plu,500-year
River Rch & RM=WFSJR 051,Reach-1         ,578
      56      64      77      31      94     284     139
River Rch & RM=WFSJR 051,Reach-1         ,83
    1054    1480    2049     932    2816    8504    5501
Boundary for River Rch & Prof#=WFSJR 051,Reach-1         , 1
Up Type= 0
Dn Type= 3
Dn Slope=0.035
Boundary for River Rch & Prof#=WFSJR 051,Reach-1         , 2
Up Type= 0
Dn Type= 3
Dn Slope=0.035
Boundary for River Rch & Prof#=WFSJR 051,Reach-1         , 3
Up Type= 0
Dn Type= 3
Dn Slope=0.035
Boundary for River Rch & Prof#=WFSJR 051,Reach-1         , 4
Up Type= 0
Dn Type= 3
Dn Slope=0.035
Boundary for River Rch & Prof#=WFSJR 051,Reach-1         , 5
Up Type= 0
Dn Type= 3
Dn Slope=0.035
Boundary for River Rch & Prof#=WFSJR 051,Reach-1         , 6
Up Type= 0
Dn Type= 3
Dn Slope=0.035
Boundary for River Rch & Prof#=WFSJR 051,Reach-1         , 7
Up Type= 0
Dn Type= 3
Dn Slope=0.035
DSS Import GetInterval= 0
DSS Import GetPeak= 0
DSS Import FillOption= 0

--- WFSJR 051.g01 (geometry) ---

Geom Title=Existing Conditions
Program Version=4.10

River Reach=WFSJR 051       ,Reach-1
Reach XY= 25
      3732007.75     10241894.01      3732011.87     10241912.16
      3732011.87     10241922.88      3732010.22     10241931.95
      3731997.03      10241940.2       3731989.6     10241941.85
      3731969.81     10241944.32      3731956.61     10241955.05
      3731949.19     10241968.24      3731946.71     10241987.22
      3731948.36     10242011.14      3731940.94     10242033.41
      3731922.79     10242062.27      3731902.17     10242073.82
       3731879.9     10242082.07      3731860.11     10242087.84
      3731846.91     10242082.89      3731819.69     10242081.25
      3731787.52     10242092.79      3731772.68     10242096.92
      3731732.26     10242103.52      3731704.22     10242115.89
      3731620.91     10242138.16      3731597.81     10242134.86
       3731568.4     10242128.32

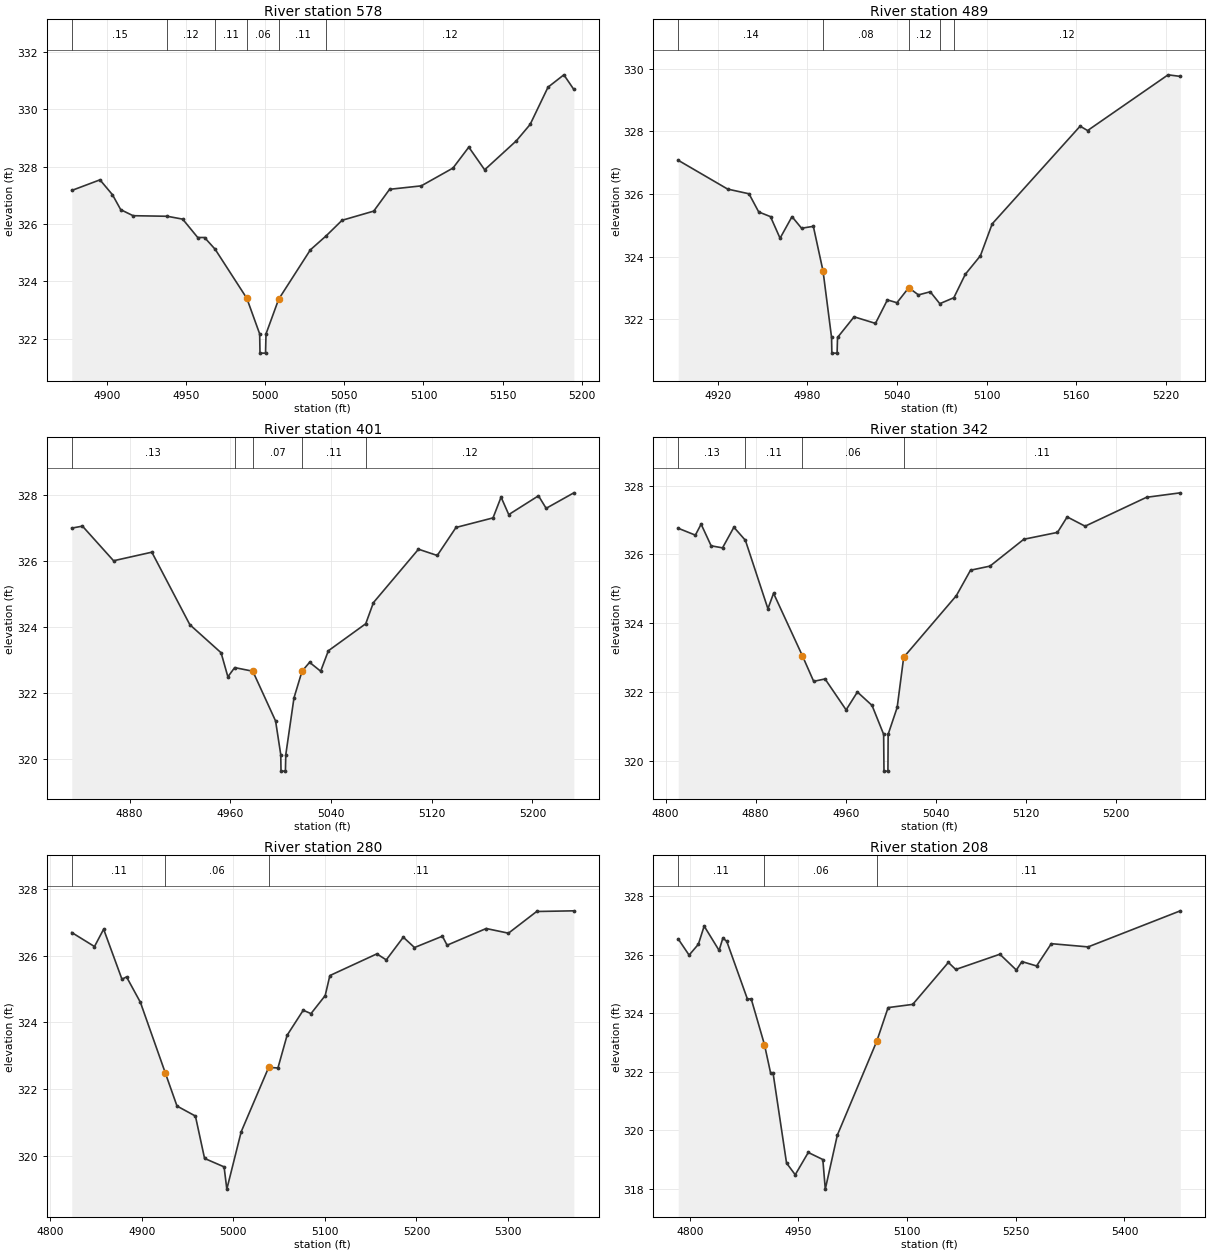
Type RM Length L Ch R = 1 ,578     ,89,89,89
BEGIN DESCRIPTION:
WFSJR 051 2.0
END DESCRIPTION:
XS GIS Cut Line= 3
      3731890.79       10241878.      3731971.11     10241901.88
      3732204.12     10241895.41
#Sta/Elev= 30
    4878  327.17  4895.8  327.54  4903.7  327.02  4908.9   326.5  4916.7  326.29
  4938.3  326.27    4948  326.17  4957.5  325.53  4961.8  325.53  4968.5  325.12
  4988.5  323.41  4996.6  322.17  4996.8   321.5  5000.3   321.5  5000.6  322.17
  5008.6  323.38  5028.6   325.1  5038.6  325.59  5048.6  326.13  5068.6  326.45
  5078.6  327.21  5098.6  327.33  5118.6  327.95  5128.6  328.68  5138.6  327.89
  5158.6   328.9  5167.3  329.47  5178.6  330.77  5188.6   331.2  5194.9  330.69
#Mann= 6 ,-1 , 0
    4878     .15       0  4938.3     .12       0  4968.5     .11       0
  4988.5     .06       0  5008.6     .11       0  5038.6     .12       0
Bank Sta=4988.5,5008.6
XS Rating Curve= 0 ,0
Exp/Cntr=0.3,0.1

Type RM Length L Ch R = 1 ,489     ,88,88,88
BEGIN DESCRIPTION:
Mapping XS 4b50c61f
END DESCRIPTION:
XS GIS Cut Line= 3
      3731876.71      10241885.6      3732017.77     10242000.62
      3732169.66     10242027.74
#Sta/Elev= 30
  4893.5  327.08  4926.6  326.16  4940.9  326.01  4947.4  325.43  4955.3  325.28
  4961.7  324.59  4969.7  325.28  4976.1  324.91    4984  324.97  4990.5  323.54
  4996.2  321.42  4996.4  320.92  4999.9  320.92  5000.2  321.42  5011.3  322.08
  5025.6  321.87  5033.6  322.62    5040  322.53  5047.9  323.01  5054.4  322.78
  5062.3  322.88  5068.7   322.5  5078.1  322.69  5085.8  323.44  5095.9  324.03
  5103.8  325.05  5162.7  328.17  5167.7  328.03  5221.6  329.81  5229.8  329.76
#Mann= 5 ,-1 , 0
  4893.5     .14       0  4990.5     .08       0  5047.9     .12       0
  5068.7     .12       0  5078.1     .12       0
#XS Ineff= 1 ,-1
  5047.9    5090  323.01
Permanent Ineff=
       F
Bank Sta=4990.5,5047.9
XS Rating Curve= 0 ,0
Exp/Cntr=0.3,0.1

Type RM Length L Ch R = 1 ,401     ,59,59,59
BEGIN DESCRIPTION:
Mapping XS 85a6e3af
END DESCRIPTION:
XS GIS Cut Line= 3
      3731869.13     10241889.99      3731919.03     10242022.32
      3732130.64     10242168.82
#Sta/Elev= 30
  4834.1  326.99  4842.6  327.05  4867.3     326  4897.7  326.26  4927.9  324.06
  4952.7  323.21  4958.1  322.48  4963.5  322.76  4977.9  322.65    4996  321.14
  5000.1  320.12  5000.3  319.62  5003.8  319.62  5004.1  320.12  5010.6  321.84
    5017  322.65    5023  322.92  5031.8  322.65  5037.9  323.27  5067.6  324.09
  5073.7  324.73  5109.5  326.35  5124.4  326.16  5139.3  327.01  5168.7   327.3
  5175.1  327.93  5181.2   327.4  5204.8  327.97  5210.9  327.59  5232.9  328.06
#Mann= 5 ,-1 , 0
  4834.1     .13       0  4963.5     .11       0  4977.9     .07       0
    5017     .11       0  5067.6     .12       0
Bank Sta=4977.9,5017
XS Rating Curve= 0 ,0
Exp/Cntr=0.3,0.1

Type RM Length L Ch R = 1 ,342     ,62,62,62
BEGIN DESCRIPTION:
Mapping XS ad0aea23
END DESCRIPTION:
XS GIS Cut Line= 4
      3731860.44     10241892.16      3731884.31      10242052.7
      3731915.77     10242106.96      3732121.45     10242186.64
#Sta/Elev= 30
  4811.3  326.76  4826.5  326.56  4831.6  326.88  4840.5  326.25  4850.6  326.19
  4860.7  326.79  4870.9  326.41  4890.9  324.42  4895.9  324.87  4921.4  323.06
  4931.5  322.31  4941.6  322.38  4960.3  321.48  4970.3     322  4983.3  321.61
  4993.6  320.77  4993.9   319.7  4997.4   319.7  4997.6  320.77  5005.6  321.55
  5011.4  323.01  5058.1   324.8  5070.7  325.54    5088  325.66    5118  326.44
  5147.9  326.64  5156.5  327.09  5172.4  326.82  5226.9  327.66  5256.9  327.79
#Mann= 4 ,-1 , 0
  4811.3     .13       0  4870.9     .11       0  4921.4     .06       0
  5011.4     .11       0
#XS Ineff= 1 ,-1
    4935  4970.3     322
Permanent Ineff=
       F
Bank Sta=4921.4,5011.4
XS Rating Curve= 0 ,0
Exp/Cntr=0.3,0.1

Type RM Length L Ch R = 1 ,280     ,72,72,72
BEGIN DESCRIPTION:
Mapping XS aa2772a3
END DESCRIPTION:
XS GIS Cut Line= 3
      3731830.05     10241906.27      3731841.99     10242161.21
      3732127.39     10242227.41
#Sta/Elev= 30
  4823.7  326.69  4848.5  326.27  4858.5  326.79  4878.5  325.29  4883.5  325.36
  4898.6   324.6  4925.8 322.485  4938.6  321.49  4958.7  321.19  4968.7  319.92
    4990 319.667    4993     319  5008.7  320.72  5038.7  322.65  5048.8  322.63
  5058.8  323.61  5076.4  324.36  5084.9  324.26  5100.4   324.8  5105.5   325.4
  5156.8  326.05  5167.1  325.87  5185.7  326.55  5197.9  326.24  5228.4  326.58
  5233.5  326.31  5276.2  326.81  5300.5  326.67  5331.3  327.32  5371.9  327.34
#Mann= 3 , 0 , 0
  4823.7     .11       0  4925.8     .06       0  5038.7     .11       0
Bank Sta=4925.8,5038.7
XS Rating Curve= 0 ,0
Exp/Cntr=0.3,0.1

Type RM Length L Ch R = 1 ,208     ,37,37,37
BEGIN DESCRIPTION:
Mapping XS b30f9717
END DESCRIPTION:
XS GIS Cut Line= 4
      3731799.68     10241886.64      3731763.86     10242012.56
       3731775.8     10242201.36      3732143.29     10242265.32
#Sta/Elev= 30
    4784  326.53    4799  325.98  4811.8  326.35  4819.8  326.97  4840.4  326.14
  4845.6  326.56    4851  326.45  4879.5  324.48  4884.7  324.49    4903  322.93
  4911.5  321.96  4914.9  321.96  4933.5  318.89  4945.5  318.49  4963.5  319.25
  4983.6  319.01    4987     318  5003.6  319.84    5058  323.04  5073.7  324.19
  5107.7   324.3  5156.9  325.73  5167.1  325.49    5228  326.01  5250.8  325.47
  5258.4  325.76  5278.7  325.61    5299  326.37  5349.8  326.26  5477.1  327.49
#Mann= 3 ,-1 , 0
    4784     .11       0    4903     .06       0    5058     .11       0
Bank Sta=4903,5058
XS Rating Curve= 0 ,0
Exp/Cntr=0.3,0.1

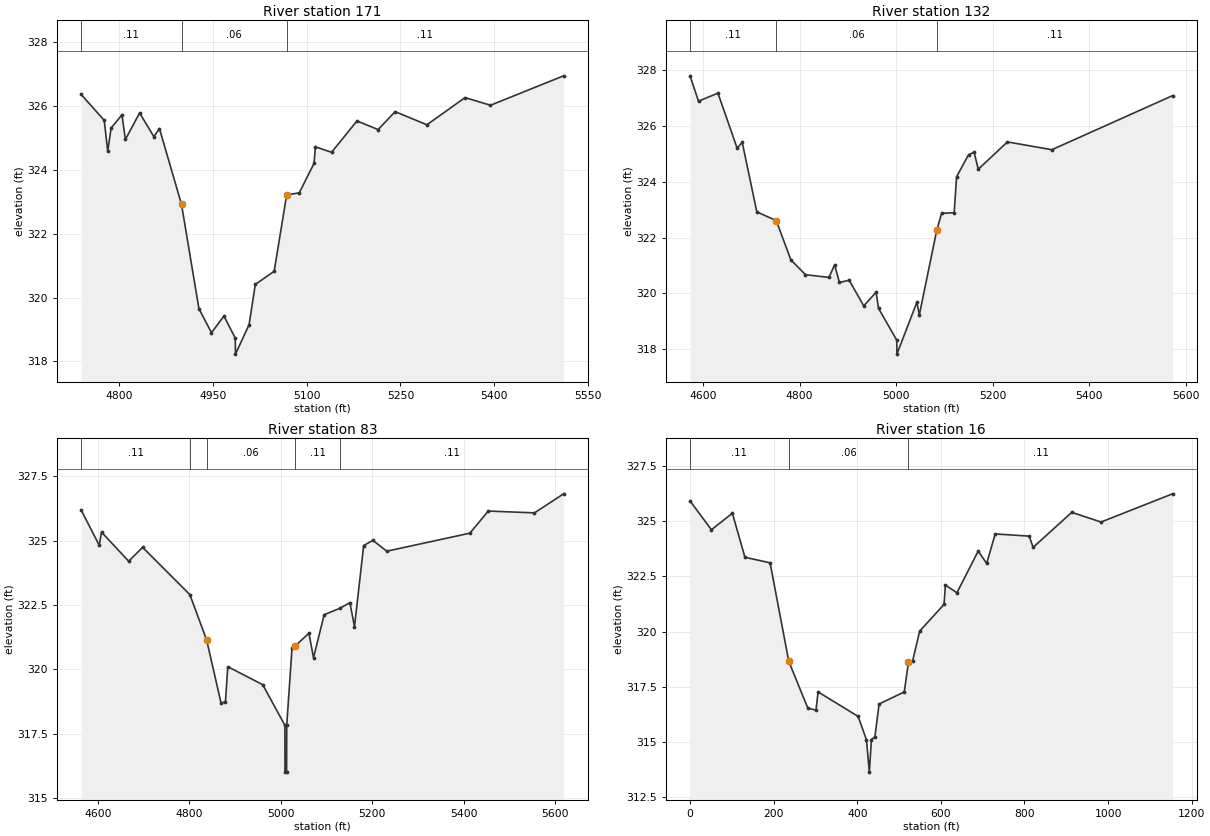
Type RM Length L Ch R = 1 ,171     ,39,39,39
BEGIN DESCRIPTION:
Mapping XS 2d07a6c0
END DESCRIPTION:
XS GIS Cut Line= 4
      3731790.97     10241857.42      3731723.72     10242000.62
      3731743.25     10242217.63      3732132.82     10242292.51
#Sta/Elev= 30
  4738.6  326.35  4775.7  325.54  4781.3  324.58  4786.8   325.3  4804.1  325.71
  4809.6  324.94  4832.4  325.77  4855.2  325.03  4864.2  325.28  4899.5  322.91
  4927.4  319.65  4947.5   318.9  4967.5  319.42  4985.6  318.73  4985.9  318.23
  5007.7  319.15  5017.7  320.41  5047.9  320.82  5067.9  323.21    5088  323.27
  5111.7  324.19  5113.9  324.71  5139.8  324.54  5180.5  325.52  5214.3  325.25
  5241.6  325.81  5292.5   325.4  5353.6  326.25  5394.3  326.01  5511.4  326.93
#Mann= 3 ,-1 , 0
  4738.6     .11       0  4899.5     .06       0  5067.9     .11       0
Bank Sta=4899.5,5067.9
XS Rating Curve= 0 ,0
Exp/Cntr=0.3,0.1

Type RM Length L Ch R = 1 ,132     ,49,49,49
BEGIN DESCRIPTION:
Mapping XS 6bb1229e
END DESCRIPTION:
XS GIS Cut Line= 4
       3731652.1     10241693.56      3731699.84     10242142.76
      3731715.03     10242253.44      3732146.89     10242307.69
#Sta/Elev= 30
  4573.4   327.8    4591  326.89  4631.2  327.18  4670.8  325.21  4681.5  325.41
  4711.7  322.92  4751.9  322.61  4782.1   321.2  4812.3  320.67  4860.9  320.57
  4872.6  321.02  4882.6  320.39  4902.8  320.47  4932.9  319.55  4958.5  320.04
  4963.6  319.46  5001.3  318.32  5001.6  317.82  5042.9  319.68    5048  319.23
    5084  322.26  5094.1  322.87  5120.1  322.89  5125.1  324.18  5149.8  324.97
  5161.4  325.06  5169.9  324.45  5230.4  325.43  5322.3  325.15  5572.1  327.09
#Mann= 3 , 0 , 0
  4573.4     .11       0  4751.9     .06       0    5084     .11       0
Bank Sta=4751.9,5084
XS Rating Curve= 0 ,0
Exp/Cntr=0.3,0.1

Type RM Length L Ch R = 1 ,83      ,67,67,67
BEGIN DESCRIPTION:
WFSJR 051 1.0
END DESCRIPTION:
XS GIS Cut Line= 3
        3731587.      10241697.9      3731668.35     10242260.23
      3732150.99     10242326.11
#Sta/Elev= 30
  4562.9   326.2  4602.6  324.82  4607.7  325.33  4667.1   324.2  4697.5  324.74
  4800.9   322.9  4837.5  321.14  4869.2  318.68  4878.7  318.74  4883.8   320.1
  4960.2   319.4  5008.7  317.82  5008.9     316  5012.4     316  5012.7  317.82
  5024.3  320.83  5030.9   320.9  5061.2   321.4  5071.3  320.45  5094.6  322.12
    5129  322.37  5150.8  322.59  5160.9  321.66    5181  324.81  5201.2  325.01
  5231.5  324.59  5413.2  325.29  5453.5  326.15  5554.5  326.08  5618.2  326.82
#Mann= 5 ,-1 , 0
  4562.9     .11       0  4800.9     .11       0  4837.5     .06       0
  5030.9     .11       0    5129     .11       0
Bank Sta=4837.5,5030.9
XS Rating Curve= 0 ,0
Exp/Cntr=0.3,0.1

Type RM Length L Ch R = 1 ,16      ,0,0,0
XS GIS Cut Line= 4
      3731553.27     10241689.94       3731574.1      10242014.6
      3731597.54     10242295.85       3732136.6     10242397.41
#Sta/Elev= 30
       0  325.93    51.2  324.62   101.3  325.37   131.4  323.37   191.5  323.12
   236.3 318.641   281.7  316.53   301.3  316.43   306.3  317.26   402.1  316.15
   422.1  315.08   428.9  313.62   433.9   315.1   442.2  315.22   452.2  316.71
   512.4  317.26   522.5   318.6   532.5  318.67   549.3  320.02   607.5  321.23
   610.9  322.11   638.4  321.76   689.3  323.65   709.6  323.09     730  324.43
   811.4  324.33   820.6  323.82   913.1  325.41   983.1  324.97  1154.2  326.25
#Mann= 3 , 0 , 0
       0     .11       0   236.3     .06       0   522.5     .11       0
Bank Sta=236.3,522.5
XS Rating Curve= 0 ,0
Exp/Cntr=0.3,0.1

Chan Stop Cuts=-1
Use User Specified Reach Order=0
Composite Channel Slope=5