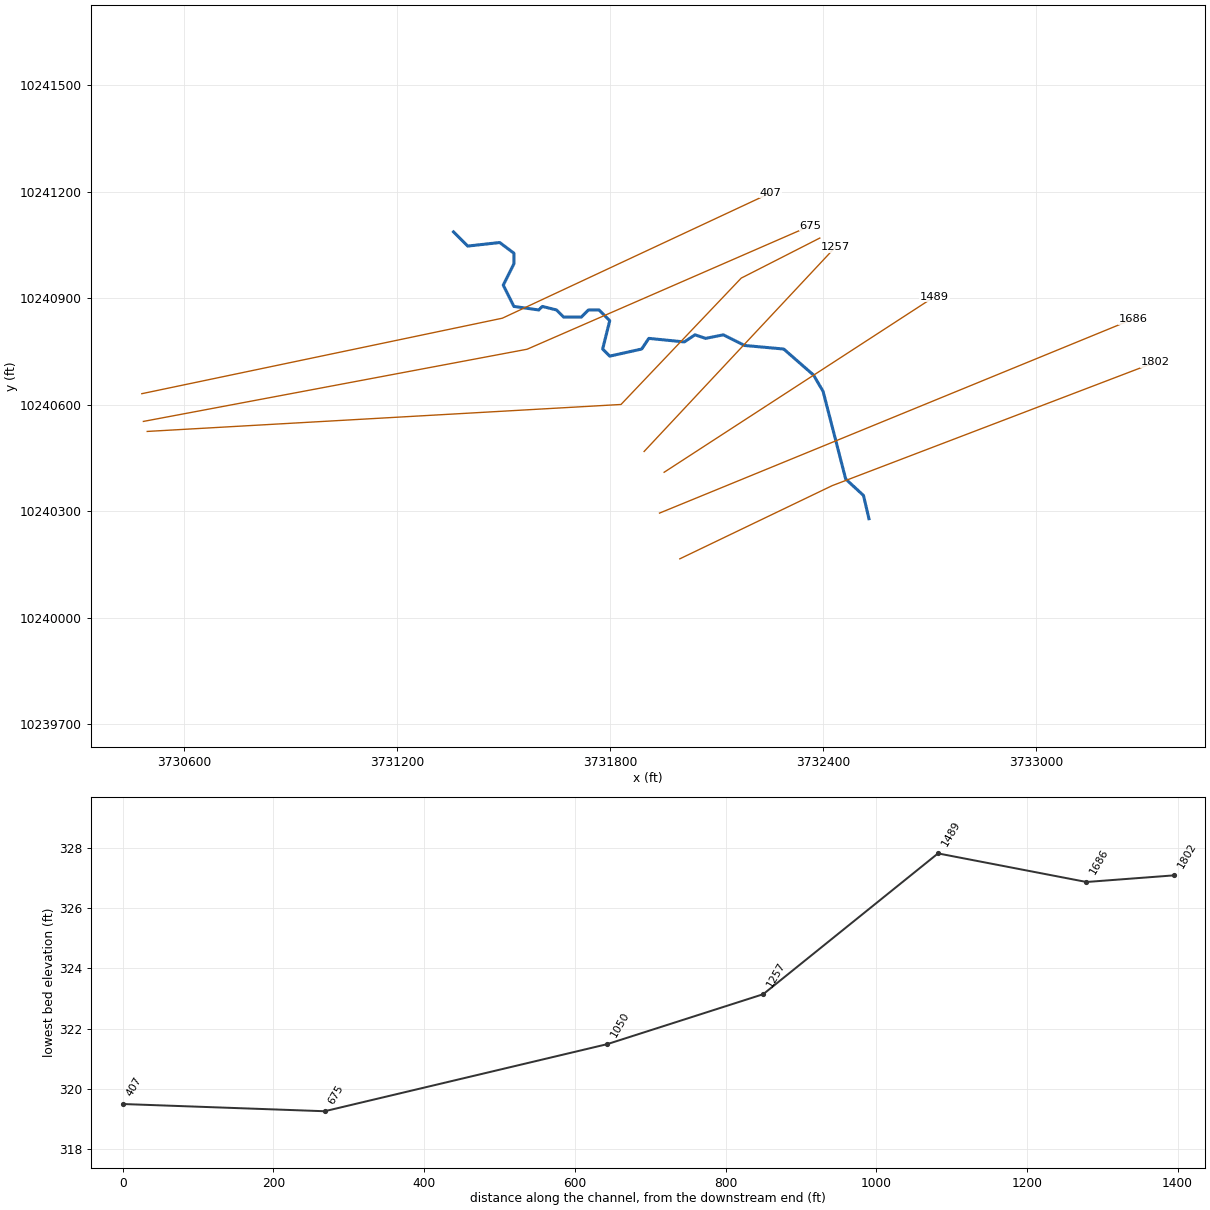
--- WFSJR 053.prj (project) ---

Proj Title=WFSJR 053 Base Level Engineering
Current Plan=p01
Default Exp/Contr=0.3,0.1
English Units
Geom File=g01
Flow File=f01
Plan File=p01
Y Axis Title=Elevation
X Axis Title(PF)=Main Channel Distance
X Axis Title(XS)=Station
BEGIN DESCRIPTION:
WFSJR 053
END DESCRIPTION:
DSS Export Rating Curves= 0
DSS Export Rating Curve Sorted= 0
DSS Export Volume Flow Curves= 0
DXF OffsetX= 0
DXF OffsetY= 0
DXF ScaleX= 1
DXF ScaleY= 10

--- WFSJR 053.p01 (plan) ---

Plan Title=Multiple Run
Program Version=4.10
Short Identifier=Multiple
Geom File=g01
Flow File=f01
Subcritical Flow
K Sum by GR= 0
Std Step Tol= 0.01
Critical Tol= 0.01
Num of Std Step Trials= 20
Max Error Tol= 0.3
Flow Tol Ratio= 0.001
Split Flow NTrial= 30
Split Flow Tol= 0.02
Split Flow Ratio= 0.02
Log Output Level= 0
Friction Slope Method= 1
Unsteady Friction Slope Method= 2
Unsteady Bridges Friction Slope Method= 1
Parabolic Critical Depth
Global Vel Dist= 1 , 1 , 1
Global Log Level= 0
CheckData=True
Encroach Param=-1 ,0,0, 0
BEGIN DESCRIPTION:
Multiple Run
END DESCRIPTION:
Computation Interval=1HOUR
Output Interval=1HOUR
Run HTab= 0
Run UNet= 0
Run PostProcess= 0
Run WQNet= 0
UNET Theta= 1
UNET Theta Warmup= 1
UNET ZTol= 0.02
UNET ZSATol= 0.05
UNET MxIter= 20
UNET MaxInSteps= 0
UNET DtIC= 0
UNET DtMin= 0
UNET MaxCRTS= 20
UNET WFStab= 2
UNET SFStab= 1
UNET WFX= 1
UNET SFX= 1
UNET DSS MLevel= 4
UNET DZMax Abort= 100
UNET Convert EG Bridges= 0
UNET Use Existing IB Tables=-1
UNET Froude Reduction=False
UNET Froude Limit= 1
UNET Froude Power= 10
UNET Time Slicing=0,0, 5
UNET Junction Losses=0
Instantaneous Interval=1HOUR
Write IC File= 0
Write IC File at Sim End=0
Echo Input=False
Echo Parameters=False
Echo Output=False
Write Detailed= 0
WQ AD Non Conservative
WQ ULTIMATE=-1
WQ Max Comp Step=1HOUR
WQ Output Interval=15MIN
WQ Output Selected Increments= 0
WQ Output face flow=0
WQ Output face velocity=0
WQ Output face area=0
WQ Output face dispersion=0
WQ Output cell volume=0
WQ Output cell surface area=0
WQ Output cell continuity=0
WQ Output cumulative cell continuity=0
WQ Output face conc=0
WQ Output face dconc_dx=0
WQ Output face courant=0
WQ Output face peclet=0
WQ Output face adv mass=0
WQ Output face disp mass=0
WQ Output cell mass=0
WQ Output cell source sink temp=0
WQ Output cell source sink nsm=0
WQ Output MaxMinRange=-1
WQ Daily Max Min Mean=-1
WQ Daily Range=0
WQ Daily Time=0
WQ Create Restart=0
WQ Fixed Restart=0
WQ System Summary=0
WQ Use Fixed Temperature=0
Sorting and Armoring Iterations= 10
XS Update Threshold= 0.02
Hydraulics Update Threshold= 0.02
Energy Slope Method= 1
Volume Change Method= 0
XS Weighting Method= 0
Number of US Weighted Cross Sections= 1
Number of DS Weighted Cross Sections= 1
Upstream XS Weight=0.25
Main XS Weight=0.5
Downstream XS Weight=0.25
Number of DS XS's Weighted with US Boundary= 1
Upstream Boundary Weight= 1
Weight of XSs Associated with US Boundary= 0
Number of US XS's Weighted with DS Boundary= 1
Downstream Boundary Weight= 0.5
Weight of XSs Associated with DS Boundary= 0.5
Sediment Output Level= 4
Mass or Volume Output= 0
Output Increment Type= 1
Profile and TS Output Increment= 10
XS Output Flag= 0
XS Output Increment= 10
Disregard all LS=0
Disregard all Conn=0
Disregard all Breaches=0
Disregard all Pumps=0

--- WFSJR 053.f01 (steady flow) ---

Flow Title=Multiple
Program Version=4.10
Number of Profiles= 7
Profile Names=10-year,25-year,50-year,1pct_min,100-year,1pct_plu,500-year
River Rch & RM=WFSJR 053,Reach-1         ,1802
     651     894    1219     548    1654    4995    3148
Boundary for River Rch & Prof#=WFSJR 053,Reach-1         , 1
Up Type= 0
Dn Type= 3
Dn Slope=0.009
Boundary for River Rch & Prof#=WFSJR 053,Reach-1         , 2
Up Type= 0
Dn Type= 3
Dn Slope=0.009
Boundary for River Rch & Prof#=WFSJR 053,Reach-1         , 3
Up Type= 0
Dn Type= 3
Dn Slope=0.009
Boundary for River Rch & Prof#=WFSJR 053,Reach-1         , 4
Up Type= 0
Dn Type= 3
Dn Slope=0.009
Boundary for River Rch & Prof#=WFSJR 053,Reach-1         , 5
Up Type= 0
Dn Type= 3
Dn Slope=0.009
Boundary for River Rch & Prof#=WFSJR 053,Reach-1         , 6
Up Type= 0
Dn Type= 3
Dn Slope=0.009
Boundary for River Rch & Prof#=WFSJR 053,Reach-1         , 7
Up Type= 0
Dn Type= 3
Dn Slope=0.009
DSS Import GetInterval= 0
DSS Import GetPeak= 0
DSS Import FillOption= 0

--- WFSJR 053.g01 (geometry) ---

Geom Title=Existing Conditions
Program Version=4.10

River Reach=WFSJR 053       ,Reach-1
Reach XY= 30
      3732528.39     10240278.85      3732512.97     10240344.37
      3732462.87     10240390.62      3732399.28     10240637.28
       3732372.3     10240683.53      3732288.23     10240756.84
      3732178.23     10240766.84      3732118.23     10240796.84
      3732068.23     10240786.84      3732038.23     10240796.84
      3732008.23     10240776.84      3731908.23     10240786.84
      3731888.23     10240756.84      3731798.23     10240736.84
      3731778.23     10240756.84      3731798.23     10240836.84
      3731768.23     10240866.84      3731738.23     10240866.84
      3731718.23     10240846.84      3731668.23     10240846.84
      3731648.23     10240866.84      3731608.23     10240876.84
      3731598.23     10240866.84      3731528.23     10240876.84
      3731498.23     10240936.84      3731528.23     10240996.84
      3731528.23     10241026.84      3731488.23     10241056.84
      3731398.23     10241046.84      3731358.23     10241086.84

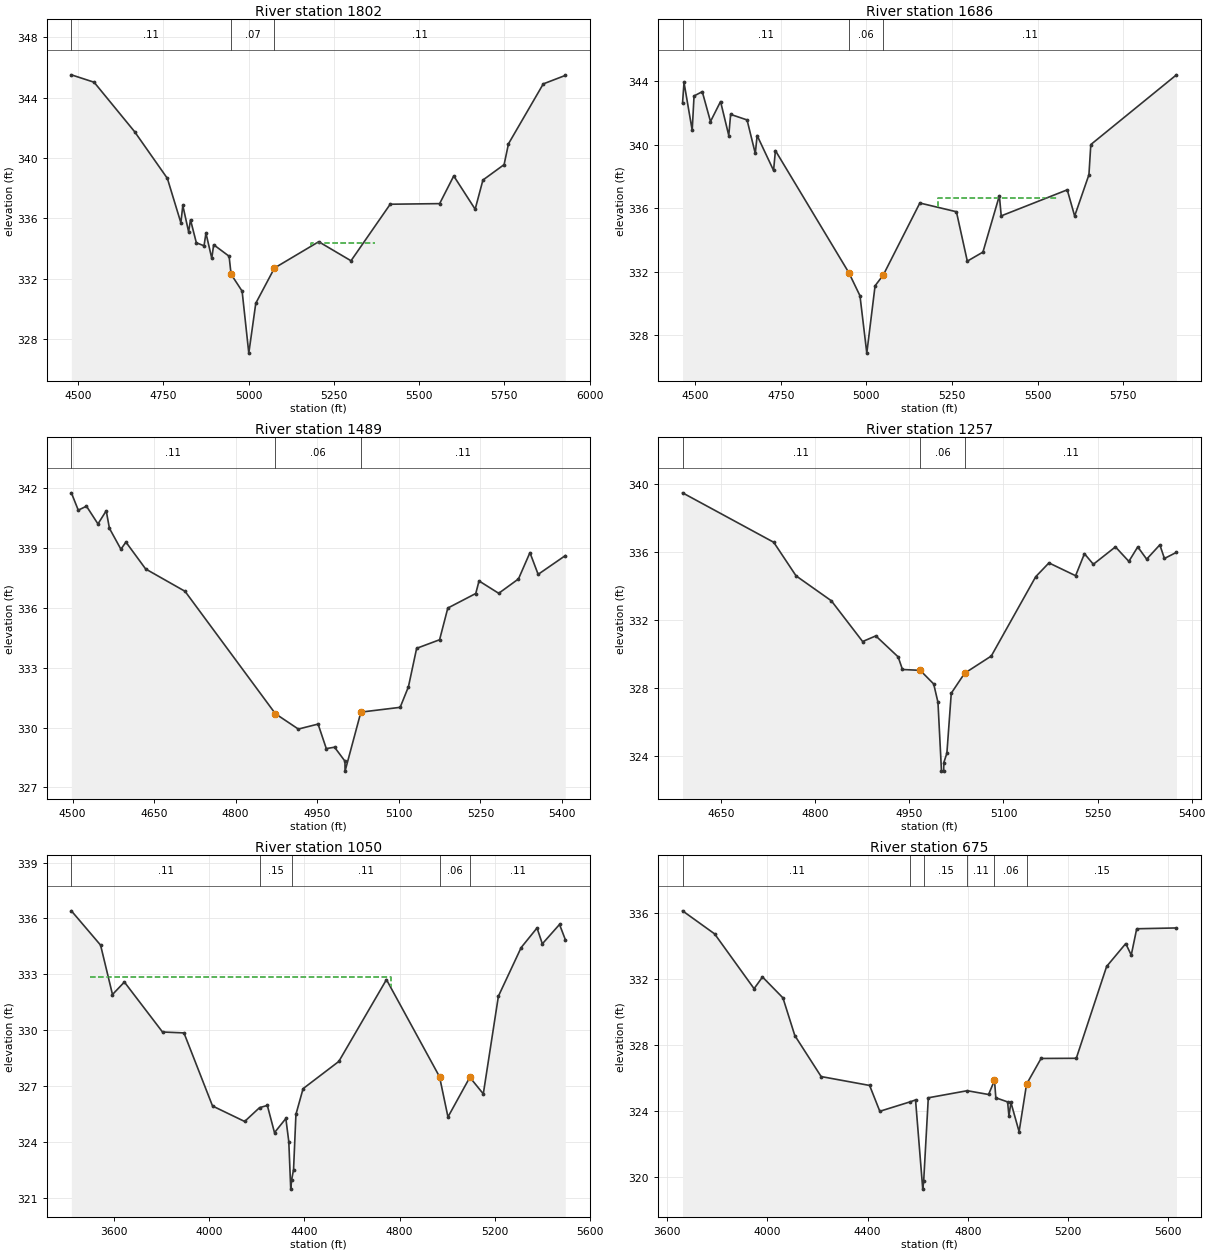
Type RM Length L Ch R = 1 ,1802    ,116,116,116
BEGIN DESCRIPTION:
WFSJR 053 1.0
END DESCRIPTION:
XS GIS Cut Line= 3
      3731995.56     10240165.82      3732424.85     10240372.01
      3733333.52       10240719.
#Sta/Elev= 30
  4479.9   345.5  4546.6  345.01  4665.4  341.74  4761.5  338.65  4801.2  335.71
  4806.8  336.86  4823.9  335.11  4829.4  335.91  4846.5  334.39  4869.1  334.19
  4874.7  335.03  4891.8  333.36  4897.3  334.26  4942.6   333.5  4948.4  332.31
  4980.8  331.19  5000.4  327.09  5020.9  330.39  5075.7  332.72  5205.5  334.46
  5300.2   333.2  5415.2  336.94  5560.2  336.98  5601.6  338.81  5664.4  336.61
  5687.2  338.54  5749.3  339.56  5762.2  340.94  5864.2   344.9  5928.8  345.46
#Mann= 3 , 0 , 0
  4479.9     .11       0  4948.4     .07       0  5075.7     .11       0
#XS Ineff= 1 ,-1
  5184.1    5370   334.4
Permanent Ineff=
       F
Bank Sta=4948.4,5075.7
XS Rating Curve= 0 ,0
Exp/Cntr=0.3,0.1

Type RM Length L Ch R = 1 ,1686    ,197,197,197
BEGIN DESCRIPTION:
WFSJR 053 2.0
END DESCRIPTION:
XS GIS Cut Line= 2
      3731938.43     10240294.66      3733272.95     10240841.48
#Sta/Elev= 30
  4463.4  342.61  4467.7  343.91  4491.6   340.9    4497  343.06    4521  343.33
    4545  341.45  4574.4  342.71  4598.4  340.57  4603.8   341.9  4651.8  341.55
  4675.8  339.44  4681.2  340.57  4729.2  338.37  4734.6  339.62  4949.1  331.93
  4981.5  330.48  5001.4  326.87  5025.6  331.11  5049.6  331.79  5156.3  336.32
  5263.1  335.77  5294.9  332.66  5340.5  333.23  5388.5  336.78  5393.9  335.51
  5586.7  337.15  5608.3   335.5    5650   338.1  5655.5     340  5905.6  344.39
#Mann= 3 , 0 , 0
  4463.4     .11       0  4949.1     .06       0  5049.6     .11       0
#XS Ineff= 1 ,-1
  5209.7    5560  336.64
Permanent Ineff=
       F
Bank Sta=4949.1,5049.6
XS Rating Curve= 0 ,0
Exp/Cntr=0.3,0.1

Type RM Length L Ch R = 1 ,1489    ,232,232,232
BEGIN DESCRIPTION:
Mapping XS 69a15f22
END DESCRIPTION:
XS GIS Cut Line= 2
      3731951.44     10240409.67      3732712.98     10240904.34
#Sta/Elev= 30
  4497.9  341.78  4510.6  340.91  4525.7  341.11  4546.8  340.22    4562  340.88
  4567.9     340    4589  338.95  4598.2  339.31  4634.5  337.96  4706.9  336.84
    4873   330.7  4915.2  329.93  4951.5  330.18  4966.6  328.95  4981.8  329.02
  5000.9  328.32  5001.1  327.82  5030.2  330.78  5102.4  331.02  5117.6  332.05
  5132.7  333.98  5174.9  334.41    5190     336  5241.4  336.73  5247.4  337.36
  5283.6  336.74  5319.9  337.46    5341  338.78  5356.1  337.69    5406  338.63
#Mann= 3 , 0 , 0
  4497.9     .11       0    4873     .06       0  5030.2     .11       0
Bank Sta=4873,5030.2
XS Rating Curve= 0 ,0
Exp/Cntr=0.3,0.1

Type RM Length L Ch R = 1 ,1257    ,207,207,207
BEGIN DESCRIPTION:
Mapping XS 3c737f93
END DESCRIPTION:
XS GIS Cut Line= 2
      3731895.03     10240468.27      3732433.06     10241043.18
#Sta/Elev= 30
  4588.4  339.46  4733.8  336.56  4769.4  334.59  4825.6  333.13  4875.5  330.74
  4896.5  331.07  4932.1  329.84    4939   329.1  4967.3  329.05  4988.8  328.25
  4995.6  327.17  5001.2  323.14  5004.7  323.14  5004.9  323.64  5009.8  324.19
  5016.8  327.71  5038.1  328.88  5080.6  329.89  5151.4  334.54  5172.5  335.35
    5215   334.6  5229.1  335.89  5243.3  335.27  5278.5  336.29  5299.9  335.44
  5314.1  336.29  5328.3  335.57  5349.3  336.41  5356.6  335.61  5375.8  335.97
#Mann= 3 ,-1 , 0
  4588.4     .11       0  4967.3     .06       0  5038.1     .11       0
Bank Sta=4967.3,5038.1
XS Rating Curve= 0 ,0
Exp/Cntr=0.3,0.1

Type RM Length L Ch R = 1 ,1050    ,375,375,375
BEGIN DESCRIPTION:
Mapping XS 5e8c4deb
END DESCRIPTION:
XS GIS Cut Line= 4
      3730495.26     10240524.69      3731829.92     10240600.65
      3732168.46     10240956.55      3732389.84     10241069.41
#Sta/Elev= 30
    3420  336.41  3542.8  334.57  3592.9  331.92  3642.9  332.59  3803.2  329.91
  3893.4  329.86  4013.5  325.94  4148.5  325.11    4211  325.85  4243.9  325.97
    4274  324.51  4321.7  325.27  4334.1  324.03  4342.3  321.48  4346.1  321.98
  4354.1  322.53  4364.1  325.49  4394.2  326.87  4544.4  328.33  4744.7  332.72
  4967.8  327.51  5003.3  325.35  5095.2  327.48  5151.8  326.59  5215.3  331.83
    5311  334.44  5377.7  335.49    5400  334.64  5472.3  335.68  5496.5  334.87
#Mann= 5 ,-1 , 0
    3420     .11       0    4211     .15       0  4346.1     .11       0
  4967.8     .06       0  5095.2     .11       0
#XS Ineff= 1 ,-1
    3500  4762.7  332.86
Permanent Ineff=
       F
Bank Sta=4967.8,5095.2
XS Rating Curve= 0 ,0
Exp/Cntr=0.3,0.1

Type RM Length L Ch R = 1 ,675     ,268,268,268
BEGIN DESCRIPTION:
Mapping XS c8cf7b96
END DESCRIPTION:
XS GIS Cut Line= 3
      3730484.48     10240552.91      3731565.43     10240756.28
      3732363.27      10241103.9
#Sta/Elev= 30
    3662  336.16  3789.9  334.76  3947.4  331.43  3980.9  332.14  4062.5  330.87
  4109.9  328.58  4214.9  326.09  4408.2  325.55  4448.9  323.98  4571.1  324.56
  4591.4  324.67  4620.2  319.25  4623.9  319.75  4642.3   324.8  4797.7  325.23
  4882.8     325  4906.3  325.86  4911.7   324.8  4958.6  324.55    4964  323.69
  4971.8  324.52  5004.5  322.74  5034.3  325.63  5092.1  327.19  5232.6   327.2
  5353.6  332.78  5429.9  334.17  5451.8  333.47  5473.6  335.07  5632.2  335.12
#Mann= 6 ,-1 , 0
    3662     .11       0  4571.1     .15       0  4623.9     .15       0
  4797.7     .11       0  4906.3     .06       0  5034.3     .15       0
Bank Sta=4906.3,5034.3
XS Rating Curve= 0 ,0
Exp/Cntr=0.3,0.1

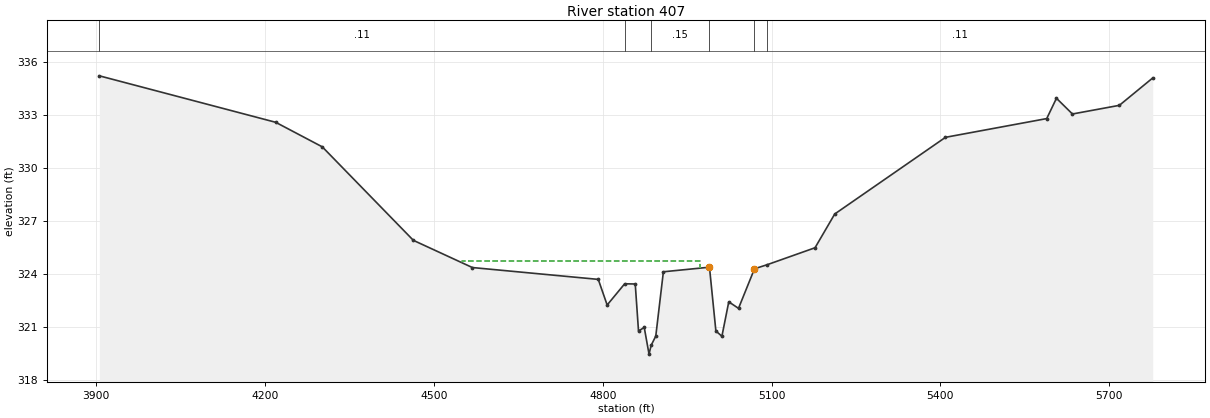
Type RM Length L Ch R = 1 ,407     ,0,0,0
BEGIN DESCRIPTION:
WFSJR 053 3.0
END DESCRIPTION:
XS GIS Cut Line= 3
      3730480.07     10240631.02      3731495.72      10240843.7
      3732251.56     10241196.72
#Sta/Elev= 30
  3905.4  335.24  4218.8  332.61  4301.6  331.22  4463.4  325.93  4568.3  324.39
    4792  323.72  4807.8  322.27  4838.9  323.47  4857.7  323.46  4863.5   320.8
  4873.7     321  4882.2  319.49    4886  319.99  4894.2  320.51  4907.7  324.15
  4989.6  324.41    5001   320.8  5011.7   320.5  5023.9  322.45  5041.2  322.08
  5069.6  324.32  5092.1  324.55  5177.2  325.51  5212.2  327.42    5409  331.76
  5588.9  332.82  5606.2  333.97  5634.6  333.08    5718  333.57  5777.3  335.12
#Mann= 6 ,-1 , 0
  3905.4     .11       0  4838.9     .15       0    4886     .15       0
  4989.6     .06       0  5069.6     .15       0  5092.1     .11       0
#XS Ineff= 1 ,-1
    4550  4972.7  324.74
Permanent Ineff=
       T
Bank Sta=4989.6,5069.6
XS Rating Curve= 0 ,0
Exp/Cntr=0.3,0.1

Chan Stop Cuts=-1
Use User Specified Reach Order=0
Composite Channel Slope=5