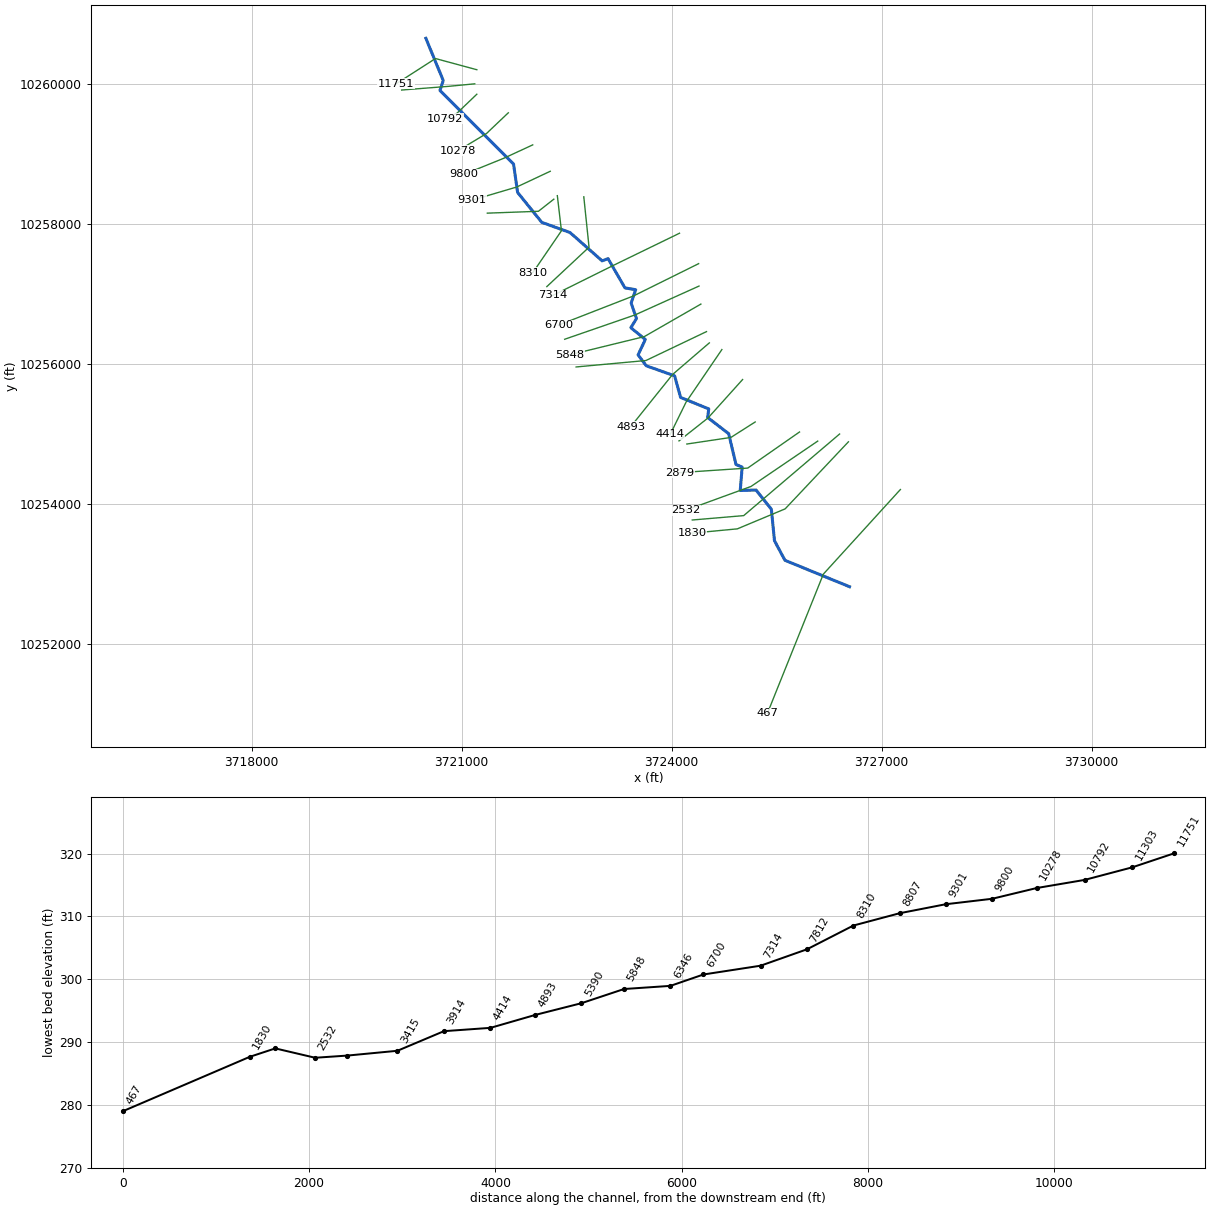
--- WFSJR 055.prj (project) ---

Proj Title=WFSJR 055 Base Level Engineering
Current Plan=p01
Default Exp/Contr=0.3,0.1
English Units
Geom File=g01
Flow File=f01
Plan File=p01
Y Axis Title=Elevation
X Axis Title(PF)=Main Channel Distance
X Axis Title(XS)=Station
BEGIN DESCRIPTION:
WFSJR 055
END DESCRIPTION:
DSS Export Rating Curves= 0
DSS Export Rating Curve Sorted= 0
DSS Export Volume Flow Curves= 0
DXF OffsetX= 0
DXF OffsetY= 0
DXF ScaleX= 1
DXF ScaleY= 10

--- WFSJR 055.p01 (plan) ---

Plan Title=Multiple Run
Program Version=4.10
Short Identifier=Multiple
Geom File=g01
Flow File=f01
Subcritical Flow
K Sum by GR= 0
Std Step Tol= 0.01
Critical Tol= 0.01
Num of Std Step Trials= 20
Max Error Tol= 0.3
Flow Tol Ratio= 0.001
Split Flow NTrial= 30
Split Flow Tol= 0.02
Split Flow Ratio= 0.02
Log Output Level= 0
Friction Slope Method= 1
Unsteady Friction Slope Method= 2
Unsteady Bridges Friction Slope Method= 1
Parabolic Critical Depth
Global Vel Dist= 1 , 1 , 1
Global Log Level= 0
CheckData=True
Encroach Param=-1 ,0,0, 0
BEGIN DESCRIPTION:
Multiple Run
END DESCRIPTION:
Computation Interval=1HOUR
Output Interval=1HOUR
Run HTab= 0
Run UNet= 0
Run PostProcess= 0
Run WQNet= 0
UNET Theta= 1
UNET Theta Warmup= 1
UNET ZTol= 0.02
UNET ZSATol= 0.05
UNET MxIter= 20
UNET MaxInSteps= 0
UNET DtIC= 0
UNET DtMin= 0
UNET MaxCRTS= 20
UNET WFStab= 2
UNET SFStab= 1
UNET WFX= 1
UNET SFX= 1
UNET DSS MLevel= 4
UNET DZMax Abort= 100
UNET Convert EG Bridges= 0
UNET Use Existing IB Tables=-1
UNET Froude Reduction=False
UNET Froude Limit= 1
UNET Froude Power= 10
UNET Time Slicing=0,0, 5
UNET Junction Losses=0
Instantaneous Interval=1HOUR
Write IC File= 0
Write IC File at Sim End=0
Echo Input=False
Echo Parameters=False
Echo Output=False
Write Detailed= 0
WQ AD Non Conservative
WQ ULTIMATE=-1
WQ Max Comp Step=1HOUR
WQ Output Interval=15MIN
WQ Output Selected Increments= 0
WQ Output face flow=0
WQ Output face velocity=0
WQ Output face area=0
WQ Output face dispersion=0
WQ Output cell volume=0
WQ Output cell surface area=0
WQ Output cell continuity=0
WQ Output cumulative cell continuity=0
WQ Output face conc=0
WQ Output face dconc_dx=0
WQ Output face courant=0
WQ Output face peclet=0
WQ Output face adv mass=0
WQ Output face disp mass=0
WQ Output cell mass=0
WQ Output cell source sink temp=0
WQ Output cell source sink nsm=0
WQ Output MaxMinRange=-1
WQ Daily Max Min Mean=-1
WQ Daily Range=0
WQ Daily Time=0
WQ Create Restart=0
WQ Fixed Restart=0
WQ System Summary=0
WQ Use Fixed Temperature=0
Sorting and Armoring Iterations= 10
XS Update Threshold= 0.02
Hydraulics Update Threshold= 0.02
Energy Slope Method= 1
Volume Change Method= 0
XS Weighting Method= 0
Number of US Weighted Cross Sections= 1
Number of DS Weighted Cross Sections= 1
Upstream XS Weight=0.25
Main XS Weight=0.5
Downstream XS Weight=0.25
Number of DS XS's Weighted with US Boundary= 1
Upstream Boundary Weight= 1
Weight of XSs Associated with US Boundary= 0
Number of US XS's Weighted with DS Boundary= 1
Downstream Boundary Weight= 0.5
Weight of XSs Associated with DS Boundary= 0.5
Sediment Output Level= 4
Mass or Volume Output= 0
Output Increment Type= 1
Profile and TS Output Increment= 10
XS Output Flag= 0
XS Output Increment= 10
Disregard all LS=0
Disregard all Conn=0
Disregard all Breaches=0
Disregard all Pumps=0

--- WFSJR 055.f01 (steady flow) ---

Flow Title=Multiple
Program Version=4.10
Number of Profiles= 7
Profile Names=10-year,25-year,50-year,1pct_min,100-year,1pct_plu,500-year
River Rch & RM=WFSJR 055,Reach-1         ,11751
     386     510     677     297     897    2709    1622
River Rch & RM=WFSJR 055,Reach-1         ,11303
     567     763    1027     455    1374    4149    2542
River Rch & RM=WFSJR 055,Reach-1         ,7314
     929    1275    1738     777    2348    7091    4434
Boundary for River Rch & Prof#=WFSJR 055,Reach-1         , 1
Up Type= 0
Dn Type= 3
Dn Slope=0.005
Boundary for River Rch & Prof#=WFSJR 055,Reach-1         , 2
Up Type= 0
Dn Type= 3
Dn Slope=0.005
Boundary for River Rch & Prof#=WFSJR 055,Reach-1         , 3
Up Type= 0
Dn Type= 3
Dn Slope=0.005
Boundary for River Rch & Prof#=WFSJR 055,Reach-1         , 4
Up Type= 0
Dn Type= 3
Dn Slope=0.005
Boundary for River Rch & Prof#=WFSJR 055,Reach-1         , 5
Up Type= 0
Dn Type= 3
Dn Slope=0.005
Boundary for River Rch & Prof#=WFSJR 055,Reach-1         , 6
Up Type= 0
Dn Type= 3
Dn Slope=0.005
Boundary for River Rch & Prof#=WFSJR 055,Reach-1         , 7
Up Type= 0
Dn Type= 3
Dn Slope=0.005
DSS Import GetInterval= 0
DSS Import GetPeak= 0
DSS Import FillOption= 0

--- WFSJR 055.g01 (geometry) ---

Geom Title=Existing Conditions
Program Version=4.10

River Reach=WFSJR 055       ,Reach-1
Reach XY= 30
      3720490.21     10260659.78      3720738.23     10260056.84
      3720691.06     10259915.44      3721742.65     10258862.39
      3721800.53     10258456.84      3722145.56     10258029.56
      3722548.84     10257884.26      3723007.61     10257479.33
       3723092.3      10257511.1      3723333.81      10257092.4
      3723486.98     10257067.12      3723422.62      10256875.8
      3723498.29     10256654.92      3723418.19     10256523.57
      3723624.43     10256355.44      3723521.08      10256135.2
       3723638.3     10255979.21      3724042.84      10255835.7
      3724128.63     10255526.63      3724530.49     10255363.23
      3724514.51     10255240.61      3724815.06     10255008.54
      3724919.72     10254568.21      3725007.73     10254531.68
      3724980.29     10254196.83      3725205.38     10254203.81
       3725424.7     10253929.19      3725469.32     10253478.87
      3725618.62     10253199.36      3726541.35     10252821.36

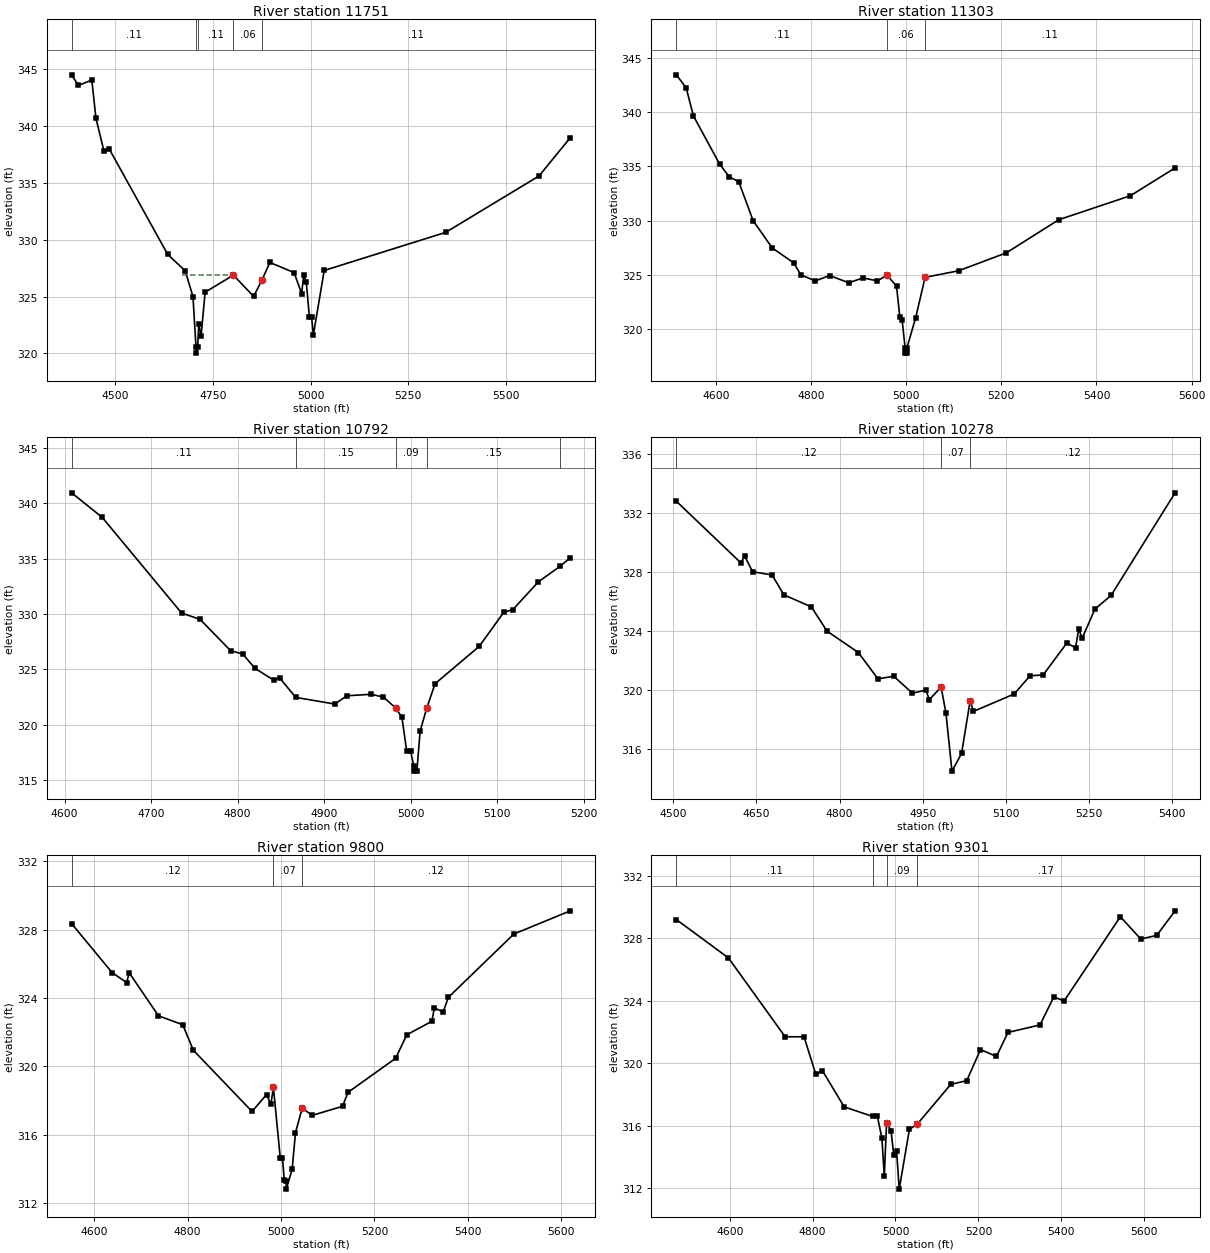
Type RM Length L Ch R = 1 ,11751   ,448,448,448
BEGIN DESCRIPTION:
WFSJR 055 23.0
END DESCRIPTION:
XS GIS Cut Line= 3
      3721217.87     10260211.07      3720627.36     10260371.04
      3720067.85     10260011.07
#Sta/Elev= 30
  4388.2  344.51  4405.6  343.58    4440  344.05  4450.6  340.68  4471.1  337.79
  4485.2  337.95  4634.2  328.72  4679.3  327.26    4699     325  4706.8  320.53
    4707  320.03  4710.8  320.53  4713.9  322.58  4719.8  321.54  4730.1  325.39
  4802.6  326.89  4854.4  325.02  4875.2  326.42  4895.9  328.01    4958  327.11
  4977.3  325.27  4982.5  326.87  4989.1   326.3  4997.2  323.23  5002.7  323.23
  5007.3  321.63  5035.1   327.3    5346  330.65  5585.1  335.61  5665.3  338.98
#Mann= 5 ,-1 , 0
  4388.2     .11       0  4706.8     .11       0  4710.8     .11       0
  4802.6     .06       0  4875.2     .11       0
#XS Ineff= 2 ,-1
    4670  4793.6  326.94  4902.8    5200  327.83
Permanent Ineff=
       T       F
Bank Sta=4802.6,4875.2
XS Rating Curve= 0 ,0
Exp/Cntr=0.3,0.1

Type RM Length L Ch R = 1 ,11303   ,511,511,511
BEGIN DESCRIPTION:
WFSJR 055 22.0
END DESCRIPTION:
XS GIS Cut Line= 3
      3721188.42     10260009.52      3720808.25     10259973.07
       3720144.2     10259920.99
#Sta/Elev= 30
  4517.2  343.43  4537.9  342.22  4553.1  339.64  4608.2   335.2  4628.3  334.05
  4648.4  333.57  4678.5     330  4718.7  327.49  4763.4  326.13    4779  325.01
  4809.1  324.46  4839.2  324.95  4879.4  324.29  4909.5  324.73  4939.6  324.46
  4959.7  324.98  4979.8  323.99  4986.7  321.16  4991.7  320.84  4997.8  318.31
  4998.1  317.81  5001.6  317.81  5001.8  318.31  5019.9  321.04  5039.9  324.79
  5110.2  325.39  5210.5  327.04  5320.8  330.09  5471.3   332.3  5565.2  334.86
#Mann= 3 , 0 , 0
  4517.2     .11       0  4959.7     .06       0  5039.9     .11       0
Bank Sta=4959.7,5039.9
XS Rating Curve= 0 ,0
Exp/Cntr=0.3,0.1

Type RM Length L Ch R = 1 ,10792   ,514,514,514
BEGIN DESCRIPTION:
WFSJR 055 21.0
END DESCRIPTION:
XS GIS Cut Line= 3
      3721217.83     10259861.05      3720934.92     10259589.85
      3720767.86     10259511.07
#Sta/Elev= 30
  4608.1  340.95  4643.4  338.74  4735.3  330.09  4756.7  329.52  4791.9  326.69
    4806  326.39  4820.2  325.09  4841.6  324.04  4848.5  324.24  4867.3  322.47
  4912.3  321.87  4926.5  322.62  4954.5  322.75  4968.6   322.5  4982.8  321.51
    4990  320.68  4995.5  317.66    5000  317.66  5003.6  316.31  5003.8  315.81
  5007.3  315.81  5011.1  319.43  5018.9  321.55  5028.4  323.71  5079.4  327.08
  5107.7  330.15  5118.4  330.41  5147.8  332.91    5173  334.32  5184.7  335.09
#Mann= 5 ,-1 , 0
  4608.1     .11       0  4867.3     .15       0  4982.8     .09       0
  5018.9     .15       0    5173     .11       0
Bank Sta=4982.8,5018.9
XS Rating Curve= 0 ,0
Exp/Cntr=0.3,0.1

Type RM Length L Ch R = 1 ,10278   ,478,478,478
BEGIN DESCRIPTION:
WFSJR 055 20.0
END DESCRIPTION:
XS GIS Cut Line= 3
      3721667.61     10259595.45      3721355.12     10259298.59
       3720954.1     10259056.41
#Sta/Elev= 30
  4505.7  332.78  4621.8  328.62    4629  329.06  4643.2  328.01  4678.4  327.79
  4699.5  326.45  4749.2  325.63  4777.5  323.99  4834.1  322.54  4869.3  320.76
  4897.6  320.94  4931.4   319.8    4956     320  4961.8  319.35  4983.2  320.21
  4991.9  318.45  5002.8  314.52  5020.1  315.72  5035.6  319.29  5041.4  318.56
  5115.1  319.74  5143.8  320.98  5167.2  321.02  5210.2   323.2  5225.6  322.85
  5231.6  324.15  5237.4   323.5  5260.6  325.48  5289.8  326.41  5405.2  333.35
#Mann= 3 , 0 , 0
  4505.7     .12       0  4983.2     .07       0  5035.6     .12       0
Bank Sta=4983.2,5035.6
XS Rating Curve= 0 ,0
Exp/Cntr=0.3,0.1

Type RM Length L Ch R = 1 ,9800    ,499,499,499
BEGIN DESCRIPTION:
WFSJR 055 19.0
END DESCRIPTION:
XS GIS Cut Line= 3
      3722016.61     10259137.14      3721609.88     10258948.37
      3721035.85     10258715.68
#Sta/Elev= 30
  4551.6  328.36  4638.4  325.49  4669.4  324.91    4675  325.48  4737.6  322.96
  4789.5  322.44  4812.4  320.94  4937.9  317.36  4969.2  318.35  4978.2  317.77
  4983.7  318.77  4998.4  314.64  5003.1  314.64  5006.9  313.36    5011  313.31
  5011.2  312.81  5023.8  313.97    5031  316.12  5045.3  317.55  5066.9  317.13
  5131.7  317.66  5143.5  318.48  5245.3  320.47  5269.4  321.85    5323  322.64
  5328.4  323.43  5347.1  323.18  5358.3  324.04  5498.5  327.75  5619.4  329.11
#Mann= 3 , 0 , 0
  4551.6     .12       0  4983.7     .07       0  5045.3     .12       0
Bank Sta=4983.7,5045.3
XS Rating Curve= 0 ,0
Exp/Cntr=0.3,0.1

Type RM Length L Ch R = 1 ,9301    ,494,494,494
BEGIN DESCRIPTION:
WFSJR 055 18.0
END DESCRIPTION:
XS GIS Cut Line= 3
      3722266.62     10258759.54      3721788.12     10258534.69
      3721141.23     10258343.35
#Sta/Elev= 30
  4471.3  329.21    4597  326.75  4733.8   321.7  4779.3   321.7  4807.8  319.29
  4823.5  319.54  4876.2  317.21  4944.6   316.6  4956.1  316.62  4967.2  315.21
    4973  312.76  4978.5   316.2  4989.2  315.69  4995.8  314.13  5002.7  314.37
    5009  311.94  5033.6  315.77  5052.4   316.1  5133.4  318.65  5171.9  318.89
  5205.1  320.88  5243.6  320.44  5271.4  321.98  5348.7  322.46  5381.9  324.25
    5407     324  5542.6  329.39    5592  327.96  5630.5   328.2  5674.6  329.77
#Mann= 4 ,-1 , 0
  4471.3     .11       0  4944.6     .17       0  4978.5     .09       0
  5052.4     .17       0
Bank Sta=4978.5,5052.4
XS Rating Curve= 0 ,0
Exp/Cntr=0.3,0.1

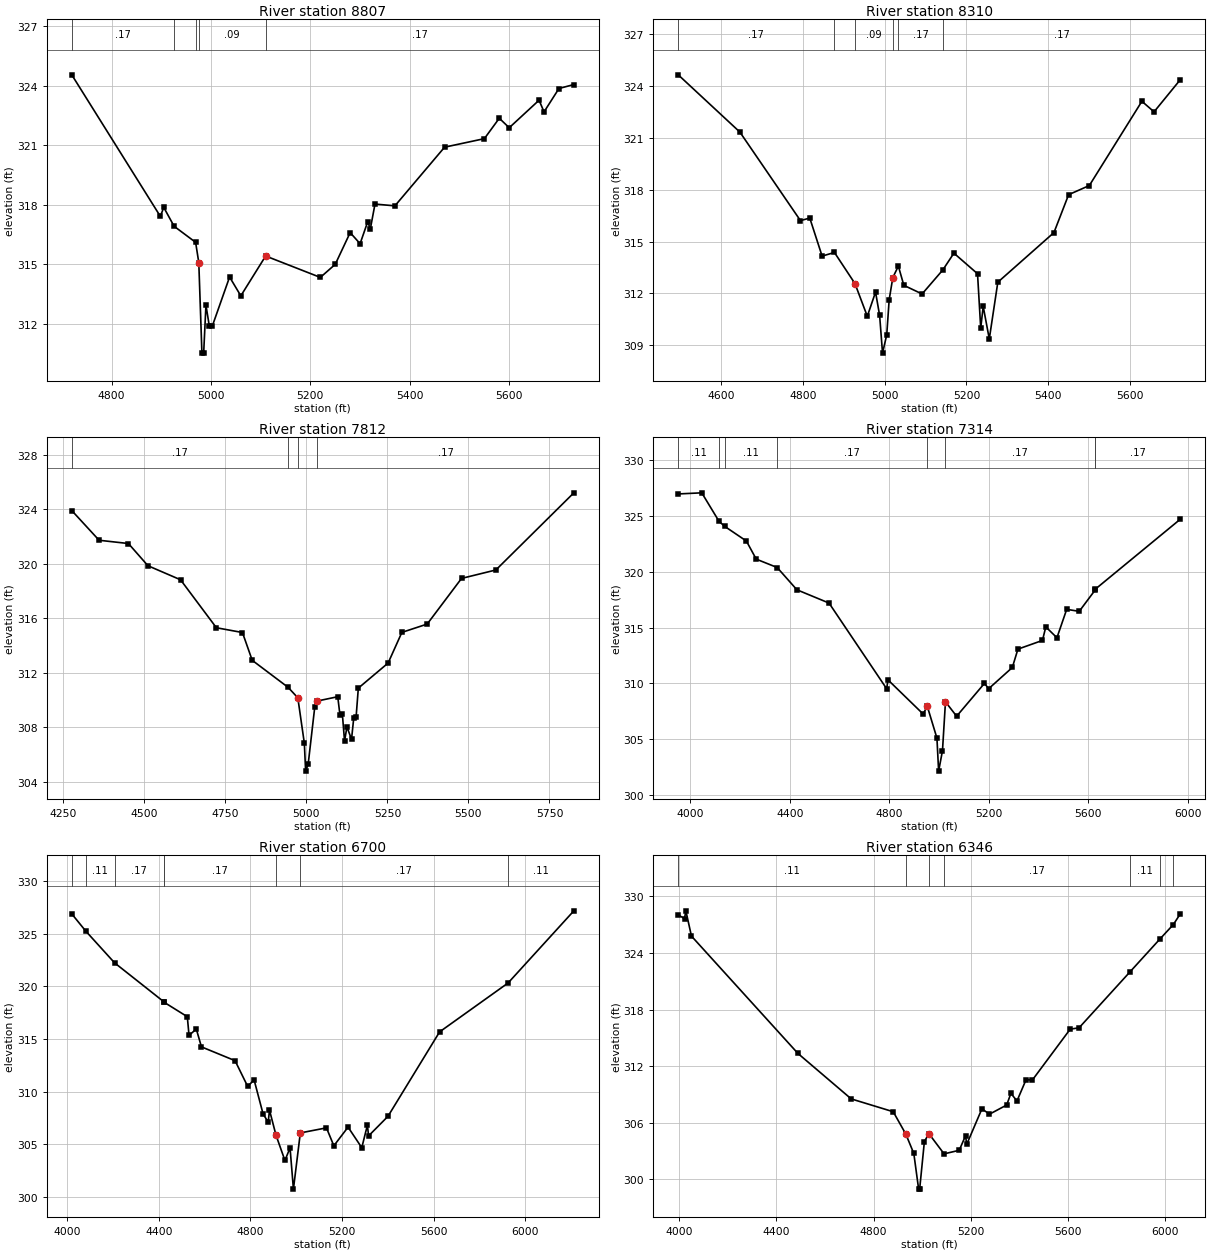
Type RM Length L Ch R = 1 ,8807    ,497,497,497
BEGIN DESCRIPTION:
WFSJR 055 17.0
END DESCRIPTION:
XS GIS Cut Line= 3
      3722317.86     10258361.08      3722097.88     10258187.52
      3721367.86     10258161.07
#Sta/Elev= 30
  4719.8  324.55  4898.1  317.41    4905  317.86  4925.8  316.91  4969.1   316.1
  4975.5  315.08  4981.8  310.51  4985.3  310.51  4989.9  312.93  4996.8  311.86
  5002.5  311.86  5037.5  314.35  5060.1   313.4  5110.1  315.41  5220.2  314.33
  5250.2  314.99  5280.2  316.59  5300.2  316.03  5315.7  317.15  5320.7  316.76
  5330.2  318.03  5370.3  317.94  5470.3   320.9  5550.4  321.33  5580.4  322.36
  5600.4  321.88  5660.5  323.27  5670.5  322.68  5700.5  323.86  5730.5  324.06
#Mann= 5 ,-1 , 0
  4719.8     .17       0  4925.8     .17       0  4969.1     .17       0
  4975.5     .09       0  5110.1     .17       0
Bank Sta=4975.5,5110.1
XS Rating Curve= 0 ,0
Exp/Cntr=0.3,0.1

Type RM Length L Ch R = 1 ,8310    ,498,498,498
BEGIN DESCRIPTION:
WFSJR 055 16.0
END DESCRIPTION:
XS GIS Cut Line= 3
      3722367.85     10258411.08       3722426.5     10257908.59
      3722017.85     10257311.07
#Sta/Elev= 30
  4494.1  324.64  4645.1  321.33  4793.5  316.21  4816.3  316.36  4846.5  314.16
  4876.7  314.37    4927  312.57  4957.2  310.68  4977.4  312.08  4987.4  310.73
  4994.5  308.55  5004.8  309.61  5010.8  311.64  5019.7  312.92  5033.3  313.58
  5046.7  312.47  5091.4  311.97  5142.2  313.36  5169.3  314.33  5227.2  313.14
    5235     310  5241.1  311.25    5256  309.37  5276.9  312.65  5414.4  315.52
  5450.3  317.71  5501.1  318.24  5629.8  323.11  5659.6   322.5  5723.9  324.36
#Mann= 6 ,-1 , 0
  4494.1     .17       0  4876.7     .17       0    4927     .09       0
  5019.7     .17       0  5033.3     .17       0  5142.2     .17       0
#XS Ineff= 1 ,-1
  5169.3    5370  314.33
Permanent Ineff=
       F
Bank Sta=4927,5019.7
XS Rating Curve= 0 ,0
Exp/Cntr=0.3,0.1

Type RM Length L Ch R = 1 ,7812    ,498,498,498
BEGIN DESCRIPTION:
WFSJR 055 15.0
END DESCRIPTION:
XS GIS Cut Line= 3
      3722745.75     10258394.95      3722820.71     10257674.74
      3722217.87     10257111.09
#Sta/Elev= 30
  4275.9  323.89  4360.2  321.71  4450.7  321.47    4511  319.84  4611.6  318.81
  4722.2  315.29  4802.6  314.94  4832.8   312.9  4943.4  310.92  4973.5  310.15
  4993.6  306.82  4997.6  304.77  5005.4  305.27  5025.9   309.5  5032.7  309.91
  5096.7  310.23  5103.6  308.87  5110.9  308.97  5117.7  306.97  5125.1  308.02
  5139.2   307.1  5146.1  308.68  5153.4  308.76  5160.2  310.86  5252.1   312.7
  5294.6  314.95  5372.7  315.56  5478.7  318.91  5584.7  319.53  5825.3  325.19
#Mann= 4 ,-1 , 0
  4275.9     .17       0  4943.4     .17       0  4973.5     .09       0
  5032.7     .17       0
Bank Sta=4973.5,5032.7
XS Rating Curve= 0 ,0
Exp/Cntr=0.3,0.1

Type RM Length L Ch R = 1 ,7314    ,614,614,614
BEGIN DESCRIPTION:
WFSJR 055 14.0
END DESCRIPTION:
XS GIS Cut Line= 3
      3724112.93      10257874.1      3723169.84     10257415.22
       3722301.6     10256984.06
#Sta/Elev= 30
  3951.2  326.95  4045.8  327.05  4115.2   324.5  4138.6  324.04  4225.1  322.74
  4264.7  321.12  4348.9  320.37  4428.1  318.38  4557.4  317.19  4788.9  309.53
  4794.4  310.32  4935.5  307.27  4952.3  307.96  4991.1  305.11  4997.9  302.16
  5013.4  303.99  5025.4  308.36  5070.2  307.07  5182.2  310.01    5199  309.53
  5294.2  311.43  5316.6  313.07  5415.3  313.85  5428.7  315.06  5473.5  314.09
  5512.7  316.63  5563.1  316.45  5627.5  318.37  5628.1  318.44  5969.4  324.69
#Mann= 8 ,-1 , 0
  3951.2     .11       0  4115.2     .17       0  4138.6     .11       0
  4348.9     .17       0  4952.3     .09       0  5025.4     .17       0
  5627.5     .11       0  5628.1     .17       0
Bank Sta=4952.3,5025.4
XS Rating Curve= 0 ,0
Exp/Cntr=0.3,0.1

Type RM Length L Ch R = 1 ,6700    ,354,354,354
BEGIN DESCRIPTION:
WFSJR 055 13.0
END DESCRIPTION:
XS GIS Cut Line= 3
      3724386.33     10257439.19      3723456.69     10256978.28
      3722381.99     10256559.33
#Sta/Elev= 30
  4020.1  326.86  4081.1  325.23  4206.8  322.22  4422.2  318.52  4423.1  318.48
  4524.3  317.11  4531.8  315.34  4563.6  315.94    4586  314.25  4732.7  312.94
  4787.8   310.5  4815.8  311.12    4855  307.89  4877.4  307.11    4883  308.25
  4911.3  305.88  4950.3  303.48  4972.7  304.67  4987.4  300.76  5017.5  306.09
  5131.6  306.57  5163.8  304.87  5225.9  306.64  5285.7  304.69  5310.2  306.82
  5315.5  305.81  5399.9  307.66  5625.3  315.67  5924.3  320.31  6211.2  327.15
#Mann= 8 ,-1 , 0
  4020.1     .17       0  4081.1     .11       0  4206.8     .17       0
  4422.2     .11       0  4423.1     .17       0  4911.3     .09       0
  5017.5     .17       0  5924.3     .11       0
Bank Sta=4911.3,5017.5
XS Rating Curve= 0 ,0
Exp/Cntr=0.3,0.1

Type RM Length L Ch R = 1 ,6346    ,498,498,498
BEGIN DESCRIPTION:
WFSJR 055 12.0
END DESCRIPTION:
XS GIS Cut Line= 3
      3724391.55     10257118.89      3723476.37     10256706.02
      3722472.59     10256358.58
#Sta/Elev= 30
    3996  328.03  4021.8  327.65  4027.3  328.47  4050.4  325.79  4488.7  313.34
  4707.9  308.52  4880.7  307.16  4932.5  304.79  4965.5  302.73  4985.3  298.95
  4989.5  298.95    5009     304  5027.6  304.83    5090  302.69  5152.3  303.07
  5178.2   304.6  5183.4  303.71  5245.8  307.47  5276.9   306.9  5347.6  307.87
  5365.1  309.11    5390   308.3  5427.4  310.56  5453.3  310.52  5609.1  315.92
  5645.5  316.06  5853.2  321.94  5978.3  325.48  6033.4  327.01  6062.2  328.15
#Mann= 7 ,-1 , 0
    3996     .11       0  4932.5     .05       0  5027.6     .11       0
    5090     .17       0  5853.2     .11       0  5978.3     .17       0
  6033.4     .11       0
Bank Sta=4932.5,5027.6
XS Rating Curve= 0 ,0
Exp/Cntr=0.3,0.1

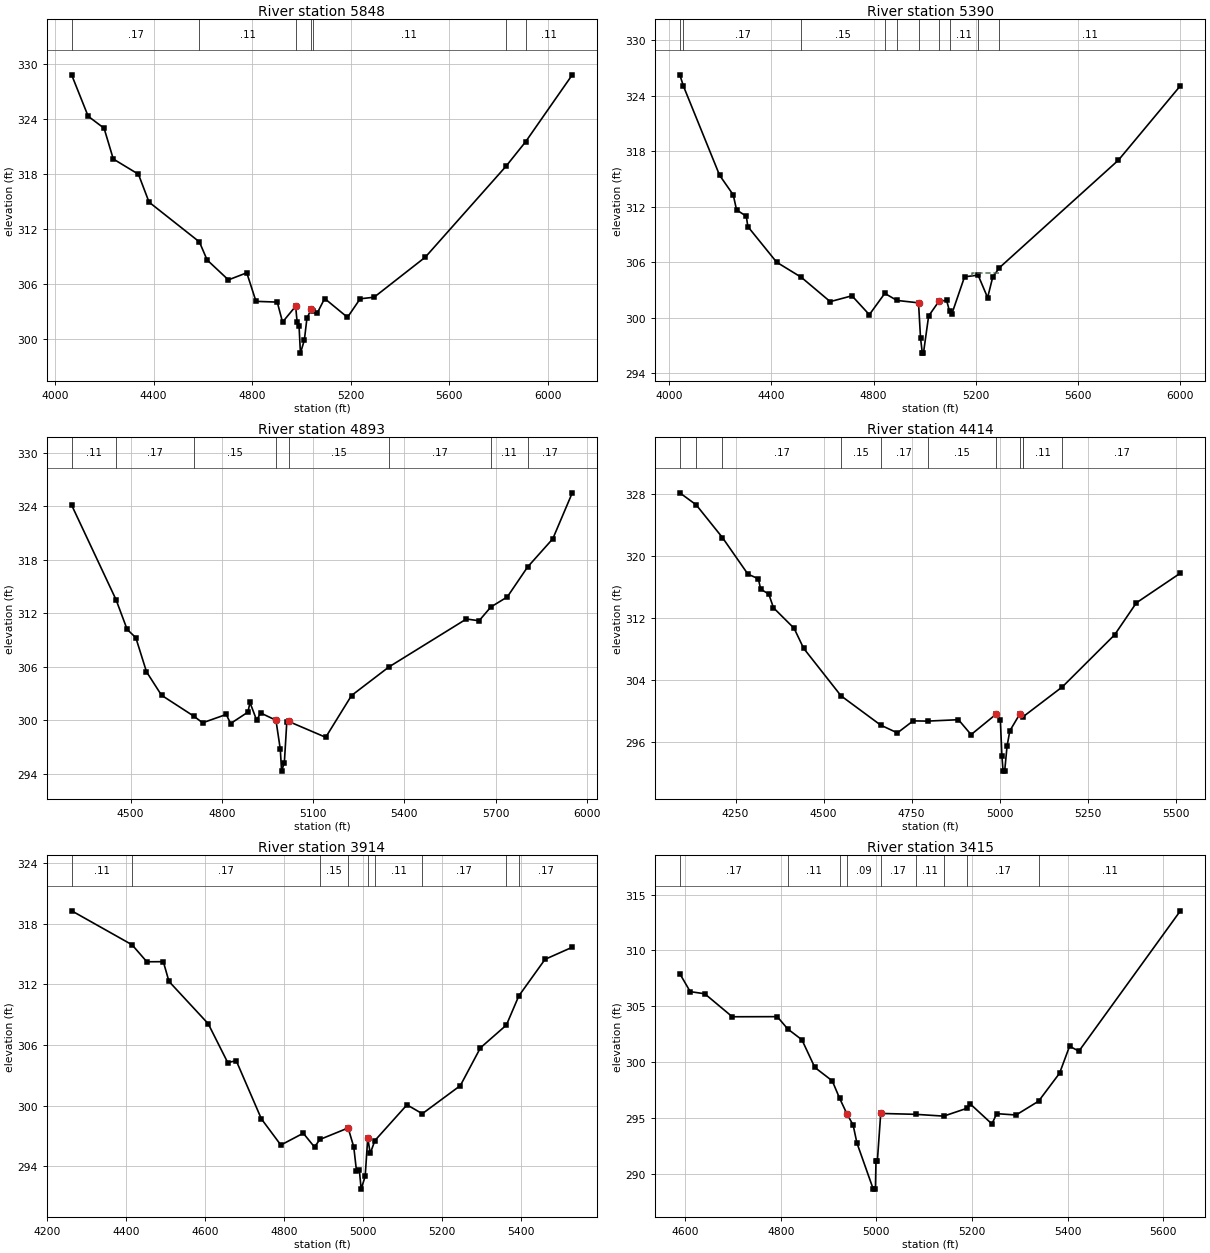
Type RM Length L Ch R = 1 ,5848    ,458,458,458
BEGIN DESCRIPTION:
WFSJR 055 11.0
END DESCRIPTION:
XS GIS Cut Line= 3
      3724417.81     10256861.05      3723609.28     10256396.08
      3722541.46     10256134.88
#Sta/Elev= 30
  4067.3  328.75  4134.1  324.26  4198.8  322.95  4236.1   319.6  4338.2  317.94
  4381.3   314.9  4585.6  310.57    4617   308.6  4703.3  306.43    4778   307.2
  4815.4  304.09  4901.7  304.01  4923.2  301.83  4976.4  303.56  4982.1  301.89
  4990.1  301.45  4995.8  298.45  5011.8  299.88  5022.1  302.23  5039.8  303.28
    5045  303.07  5063.2  302.77  5094.1   304.4  5186.8  302.35  5238.2  304.37
  5294.8  304.54  5502.9  308.91  5830.3  318.81  5909.7  321.47  6099.3  328.77
#Mann= 7 ,-1 , 0
  4067.3     .17       0  4585.6     .11       0  4976.4     .07       0
  5039.8     .11       0    5045     .11       0  5830.3     .17       0
  5909.7     .11       0
Bank Sta=4976.4,5039.8
XS Rating Curve= 0 ,0
Exp/Cntr=0.3,0.1

Type RM Length L Ch R = 1 ,5390    ,497,497,497
BEGIN DESCRIPTION:
WFSJR 055 10.0
END DESCRIPTION:
XS GIS Cut Line= 3
      3724498.34     10256467.85      3723633.35     10256054.67
      3722636.39     10255962.65
#Sta/Elev= 30
  4041.4  326.24  4055.8  325.01  4197.1   315.4  4250.6  313.28  4263.6  311.66
  4301.6  310.97  4307.9  309.85  4420.5  306.01  4517.5  304.37  4630.2  301.75
  4715.4  302.38  4783.4  300.34  4843.9  302.64  4891.6  301.88    4976  301.62
  4983.9  297.81  4990.9  296.19  4995.3  296.19  5015.6   300.2  5055.7  301.78
  5085.9   301.9  5097.3  300.72    5106  300.39  5156.2  304.43  5209.3  304.61
  5246.5  302.18  5266.6  304.41    5293  305.42  5758.7  317.03  6001.2  325.06
#Mann= 10 ,-1 , 0
  4041.4     .11       0  4055.8     .17       0  4517.5     .15       0
  4843.9     .17       0  4891.6     .15       0    4976     .09       0
  5055.7     .15       0  5097.3     .11       0  5209.3     .17       0
    5293     .11       0
#XS Ineff= 1 ,-1
  5186.3    5300  304.82
Permanent Ineff=
       F
Bank Sta=4976,5055.7
XS Rating Curve= 0 ,0
Exp/Cntr=0.3,0.1

Type RM Length L Ch R = 1 ,4893    ,479,479,479
BEGIN DESCRIPTION:
WFSJR 055 9.0
END DESCRIPTION:
XS GIS Cut Line= 3
      3724538.82     10256306.91      3724013.15     10255854.26
      3723417.86     10255111.08
#Sta/Elev= 30
  4306.3   324.1  4452.1  313.52  4488.6  310.19  4517.1  309.27  4552.2  305.45
  4601.6  302.82  4709.4  300.44  4736.6  299.73  4814.5  300.67  4828.7  299.65
  4885.8  300.93  4892.4  302.01  4914.3  300.04  4927.8  300.83  4977.9  300.02
  4992.2  296.77  4996.4  294.32  5005.5  295.28  5013.5  299.79  5019.9  299.88
  5141.5  298.11  5226.4  302.79  5349.4  305.99  5604.1  311.36  5645.7  311.16
  5684.4   312.7  5738.5  313.83    5805  317.17  5888.1  320.34  5952.2  325.49
#Mann= 8 ,-1 , 0
  4306.3     .11       0  4452.1     .17       0  4709.4     .15       0
  4977.9     .09       0  5019.9     .15       0  5349.4     .17       0
  5684.4     .11       0    5805     .17       0
Bank Sta=4977.9,5019.9
XS Rating Curve= 0 ,0
Exp/Cntr=0.3,0.1

Type RM Length L Ch R = 1 ,4414    ,500,500,500
BEGIN DESCRIPTION:
WFSJR 055 8.0
END DESCRIPTION:
XS GIS Cut Line= 3
      3724717.85     10256211.07      3724206.68     10255460.02
      3723980.11     10254999.09
#Sta/Elev= 30
  4091.5   328.1  4137.9  326.56  4212.6  322.34    4285  317.63  4314.5  317.04
  4321.3   315.7  4344.3  315.06  4357.6   313.3  4416.2  310.66  4443.2  308.09
  4549.6  301.96    4662   298.2  4709.6  297.19  4754.4  298.74  4795.3  298.71
  4883.1  298.89    4919  296.97  4990.8  299.63  5002.2  298.84  5006.5  294.26
  5009.9  292.27  5014.4  292.27  5021.1  295.45    5029  297.45  5057.1   299.6
    5067  299.28  5178.6  303.13  5326.8  309.82  5388.6  313.94  5513.6  317.76
#Mann= 11 ,-1 , 0
  4091.5     .17       0  4137.9     .11       0  4212.6     .17       0
  4549.6     .15       0    4662     .17       0  4795.3     .15       0
  4990.8     .09       0  5057.1     .15       0    5067     .17       0
    5067     .11       0  5178.6     .17       0
Bank Sta=4990.8,5057.1
XS Rating Curve= 0 ,0
Exp/Cntr=0.3,0.1

Type RM Length L Ch R = 1 ,3914    ,499,499,499
BEGIN DESCRIPTION:
WFSJR 055 7.0
END DESCRIPTION:
XS GIS Cut Line= 3
      3725014.01       10255783.      3724520.62     10255234.04
      3724105.58     10254905.72
#Sta/Elev= 30
  4261.9  319.27  4414.7  315.91  4452.1  314.23  4493.9  314.24  4508.1  312.29
  4607.5   308.1  4656.9  304.26  4678.5  304.44  4742.1  298.69  4791.4   296.1
  4848.2  297.27  4876.6   295.9  4890.1  296.65  4961.8  297.79    4976  295.91
  4982.8  293.57  4990.2   293.6  4994.7  291.74  5004.9  293.01  5011.4  296.81
  5017.7  295.27  5029.4  296.54  5110.7  300.08  5149.5   299.2  5245.8  301.98
  5296.7  305.72  5362.4  307.97  5393.8  310.85  5460.2  314.47  5529.2  315.67
#Mann= 9 ,-1 , 0
  4261.9     .11       0  4414.7     .17       0  4890.1     .15       0
  4961.8     .09       0  5011.4     .15       0  5029.4     .11       0
  5149.5     .17       0  5362.4     .11       0  5393.8     .17       0
Bank Sta=4961.8,5011.4
XS Rating Curve= 0 ,0
Exp/Cntr=0.3,0.1

Type RM Length L Ch R = 1 ,3415    ,536,536,536
BEGIN DESCRIPTION:
WFSJR 055 6.0
END DESCRIPTION:
XS GIS Cut Line= 3
      3725193.68      10255176.2      3724846.96     10254955.32
      3724217.88     10254861.08
#Sta/Elev= 30
  4588.9  307.92  4610.7  306.31  4641.1  306.12  4698.7  304.06  4792.7  304.07
  4814.9  302.96  4844.3     302  4871.4  299.52  4907.8  298.32    4923  296.78
  4938.2  295.39  4951.5  294.36  4959.4  292.76  4993.6  288.62  4998.1  288.62
  4999.3   291.1  5002.1   291.1  5009.2   295.4  5082.5  295.32    5141  295.16
  5188.8  295.85  5196.8  296.24  5241.8  294.46  5251.9  295.38  5292.3  295.26
  5339.5   296.5  5383.3     299  5404.3  301.42  5423.8  300.98  5636.1  313.55
#Mann= 9 ,-1 , 0
  4588.9     .17       0  4814.9     .11       0    4923     .17       0
  4938.2     .09       0  5009.2     .17       0  5082.5     .11       0
    5141     .15       0  5188.8     .17       0  5339.5     .11       0
Bank Sta=4938.2,5009.2
XS Rating Curve= 0 ,0
Exp/Cntr=0.3,0.1

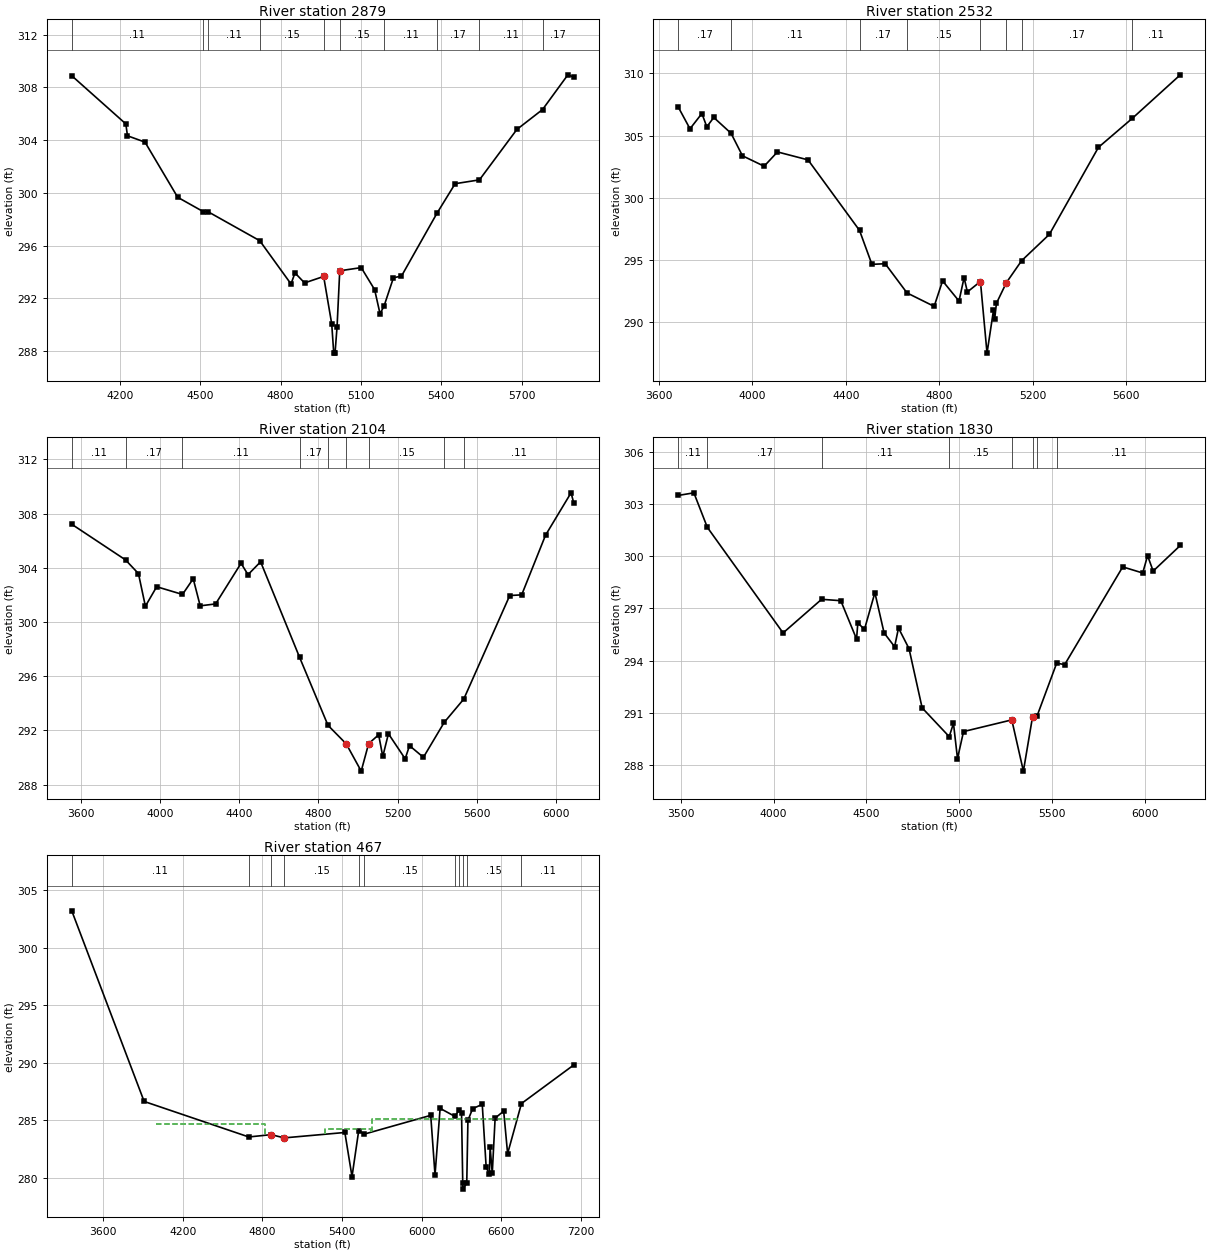
Type RM Length L Ch R = 1 ,2879    ,347,347,347
BEGIN DESCRIPTION:
WFSJR 055 5.0
END DESCRIPTION:
XS GIS Cut Line= 3
      3725826.47     10255032.96       3725086.9     10254517.34
      3724115.55     10254452.24
#Sta/Elev= 30
    4020  308.88  4221.9  305.23    4228  304.33  4293.5  303.85  4415.6  299.67
  4510.4  298.59  4528.6  298.58    4722  296.38  4838.8   293.1  4853.6  293.94
  4889.4  293.18  4960.7  293.67  4990.8  290.08  4998.4  287.86  5003.2  287.86
  5010.8  289.86  5020.8   294.1    5101  294.34  5151.1  292.67  5171.2  290.85
    5186  291.41  5221.3  293.57  5251.4   293.7  5384.2  298.47  5451.8   300.7
  5542.5  300.99  5682.3  304.81  5778.2  306.32  5872.8  308.95  5895.1  308.77
#Mann= 10 ,-1 , 0
    4020     .11       0  4510.4     .17       0  4528.6     .11       0
    4722     .15       0  4960.7     .09       0  5020.8     .15       0
    5186     .11       0  5384.2     .17       0  5542.5     .11       0
  5778.2     .17       0
Bank Sta=4960.7,5020.8
XS Rating Curve= 0 ,0
Exp/Cntr=0.3,0.1

Type RM Length L Ch R = 1 ,2532    ,428,428,428
BEGIN DESCRIPTION:
WFSJR 055 4.0
END DESCRIPTION:
XS GIS Cut Line= 3
      3726086.86     10254902.73      3725133.77     10254254.32
      3724198.91     10253913.19
#Sta/Elev= 30
  3683.3   307.3  3733.6  305.55  3784.5  306.78  3805.5  305.71  3835.3  306.46
  3909.2  305.19    3958  303.38  4050.8  302.54  4107.8  303.69  4238.5  303.05
  4458.8  297.38  4511.8  294.65  4568.7   294.7  4662.1  292.35  4778.1  291.27
  4814.1  293.32  4884.4   291.7  4906.2  293.58  4920.3  292.43  4976.1  293.27
  5004.3  287.51  5031.9  290.95  5037.2  290.29  5044.6  291.52  5087.2  293.18
  5152.2  294.94    5271  297.06    5481  304.06  5626.4   306.4  5831.2  309.89
#Mann= 8 ,-1 , 0
  3683.3     .17       0  3909.2     .11       0  4458.8     .17       0
  4662.1     .15       0  4976.1     .09       0  5087.2     .15       0
  5152.2     .17       0  5626.4     .11       0
Bank Sta=4976.1,5087.2
XS Rating Curve= 0 ,0
Exp/Cntr=0.3,0.1

Type RM Length L Ch R = 1 ,2104    ,274,274,274
BEGIN DESCRIPTION:
WFSJR 055 3.0
END DESCRIPTION:
XS GIS Cut Line= 3
      3726399.41     10255004.33       3725029.6     10253837.65
      3724295.26     10253775.15
#Sta/Elev= 30
  3554.1  307.22  3825.6  304.59  3890.9  303.58    3926  301.17  3983.1  302.61
  4113.4  302.04  4167.6   303.2  4202.8   301.2  4280.7  301.34  4409.2  304.34
  4444.4   303.5    4508  304.45  4704.6  297.41  4848.4  292.38  4940.7  291.01
  5016.2     289  5053.8  291.03  5104.3  291.68  5125.2  290.08  5153.7  291.76
  5238.3  289.91  5260.2  290.88  5330.5  290.02  5435.6   292.6  5534.4  294.32
  5766.6  301.96  5826.9  302.01  5947.3  306.41  6076.2  309.54  6090.4  308.77
#Mann= 9 ,-1 , 0
  3554.1     .11       0  3825.6     .17       0  4113.4     .11       0
  4704.6     .17       0  4848.4     .15       0  4940.7     .09       0
  5053.8     .15       0  5435.6     .17       0  5534.4     .11       0
Bank Sta=4940.7,5053.8
XS Rating Curve= 0 ,0
Exp/Cntr=0.3,0.1

Type RM Length L Ch R = 1 ,1830    ,1363,1363,1363
BEGIN DESCRIPTION:
WFSJR 055 2.0
END DESCRIPTION:
XS GIS Cut Line= 4
      3726525.23     10254892.57        3725622.     10253934.42
       3724939.3     10253648.57      3724292.25     10253586.62
#Sta/Elev= 30
  3485.4  303.48  3569.7  303.63  3642.2  301.65  4050.7  295.59  4258.3  297.52
  4361.8  297.44  4446.8  295.24  4453.7  296.17  4489.3  295.79  4545.6   297.9
  4595.3  295.59  4651.9   294.8    4673  295.87  4729.6  294.69  4800.4  291.29
  4946.3  289.64  4969.3   290.4    4991  288.38  5023.5  289.93  5283.7   290.6
  5346.3  287.66  5395.5  290.77  5420.5  290.84  5525.9  293.86  5568.7  293.77
  5881.8  299.38  5989.5  299.03  6015.9  300.02    6046  299.14  6192.3  300.61
#Mann= 8 ,-1 , 0
  3485.4     .11       0  3642.2     .17       0  4258.3     .11       0
  4946.3     .15       0  5283.7     .09       0  5395.5     .15       0
  5420.5     .17       0  5525.9     .11       0
Bank Sta=5283.7,5395.5
XS Rating Curve= 0 ,0
Exp/Cntr=0.3,0.1

Type RM Length L Ch R = 1 ,467     ,0,0,0
BEGIN DESCRIPTION:
WFSJR 055 1.0
END DESCRIPTION:
XS GIS Cut Line= 3
      3727267.85     10254211.07      3726167.24     10253001.44
      3725367.85     10251011.07
#Sta/Elev= 30
  3364.6  303.22  3909.5  286.63  4697.6  283.54  4865.3  283.74  4964.3  283.46
  5420.7  283.93  5474.6  280.09  5524.9  284.08  5567.8  283.79  6067.3  285.42
  6099.6  280.23    6138  286.03  6247.5  285.34  6281.1  285.85  6299.3  285.61
  6308.5   279.5    6309     279  6338.5   279.5  6347.4  284.98  6382.7     286
  6455.2  286.38  6484.8   280.9    6509  280.29  6514.4  282.68  6530.6  280.37
  6552.2  285.18  6616.6  285.79  6646.2  282.09  6750.4  286.45  7144.9  289.81
#Mann= 11 ,-1 , 0
  3364.6     .11       0  4697.6     .15       0  4865.3     .07       0
  4964.3     .15       0  5524.9     .11       0  5567.8     .15       0
  6247.5     .11       0  6281.1     .15       0  6308.5     .12       0
  6338.5     .15       0  6750.4     .11       0
#XS Ineff= 3 ,-1
    4000  4823.1  284.69  5269.8    5620  284.27  5624.5    6715  285.11
Permanent Ineff=
       T       T       T
Bank Sta=4865.3,4964.3
XS Rating Curve= 0 ,0
Exp/Cntr=0.3,0.1

Chan Stop Cuts=-1
Use User Specified Reach Order=0
Composite Channel Slope=5