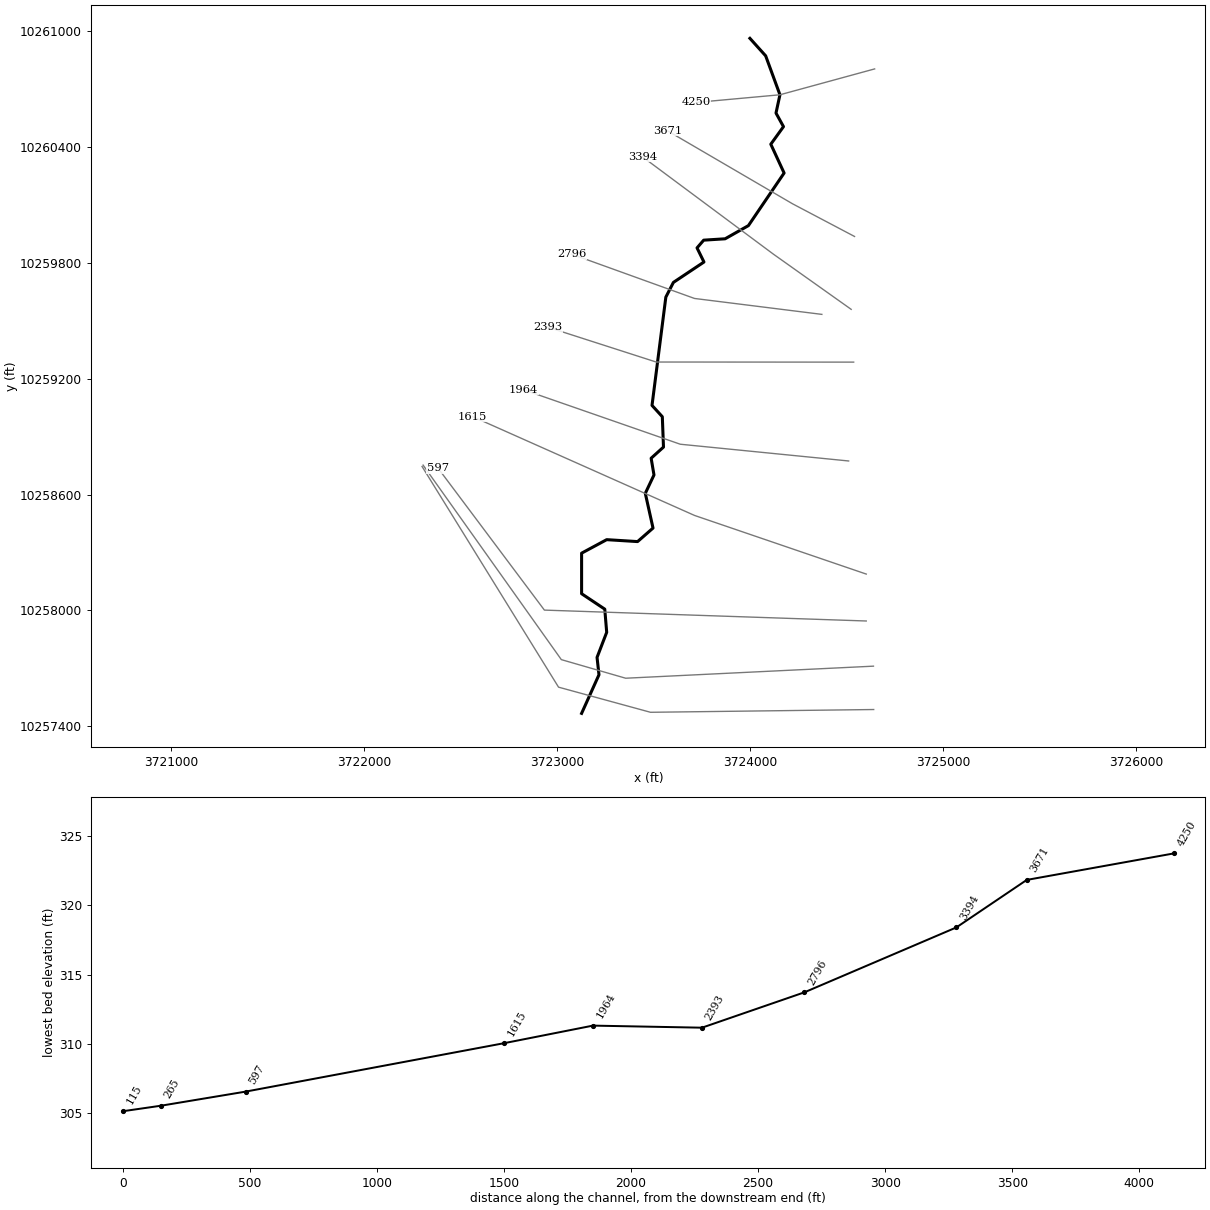
--- WFSJR 056.prj (project) ---

Proj Title=WFSJR 056 Base Level Engineering
Current Plan=p01
Default Exp/Contr=0.3,0.1
English Units
Geom File=g01
Flow File=f01
Plan File=p01
Y Axis Title=Elevation
X Axis Title(PF)=Main Channel Distance
X Axis Title(XS)=Station
BEGIN DESCRIPTION:
WFSJR 056
END DESCRIPTION:
DSS Export Rating Curves= 0
DSS Export Rating Curve Sorted= 0
DSS Export Volume Flow Curves= 0
DXF OffsetX= 0
DXF OffsetY= 0
DXF ScaleX= 1
DXF ScaleY= 10

--- WFSJR 056.p01 (plan) ---

Plan Title=Multiple Run
Program Version=4.10
Short Identifier=Multiple
Geom File=g01
Flow File=f01
Subcritical Flow
K Sum by GR= 0
Std Step Tol= 0.01
Critical Tol= 0.01
Num of Std Step Trials= 20
Max Error Tol= 0.3
Flow Tol Ratio= 0.001
Split Flow NTrial= 30
Split Flow Tol= 0.02
Split Flow Ratio= 0.02
Log Output Level= 0
Friction Slope Method= 1
Unsteady Friction Slope Method= 2
Unsteady Bridges Friction Slope Method= 1
Parabolic Critical Depth
Global Vel Dist= 1 , 1 , 1
Global Log Level= 0
CheckData=True
Encroach Param=-1 ,0,0, 0
BEGIN DESCRIPTION:
Multiple Run
END DESCRIPTION:
Computation Interval=1HOUR
Output Interval=1HOUR
Run HTab= 0
Run UNet= 0
Run PostProcess= 0
Run WQNet= 0
UNET Theta= 1
UNET Theta Warmup= 1
UNET ZTol= 0.02
UNET ZSATol= 0.05
UNET MxIter= 20
UNET MaxInSteps= 0
UNET DtIC= 0
UNET DtMin= 0
UNET MaxCRTS= 20
UNET WFStab= 2
UNET SFStab= 1
UNET WFX= 1
UNET SFX= 1
UNET DSS MLevel= 4
UNET DZMax Abort= 100
UNET Convert EG Bridges= 0
UNET Use Existing IB Tables=-1
UNET Froude Reduction=False
UNET Froude Limit= 1
UNET Froude Power= 10
UNET Time Slicing=0,0, 5
UNET Junction Losses=0
Instantaneous Interval=1HOUR
Write IC File= 0
Write IC File at Sim End=0
Echo Input=False
Echo Parameters=False
Echo Output=False
Write Detailed= 0
WQ AD Non Conservative
WQ ULTIMATE=-1
WQ Max Comp Step=1HOUR
WQ Output Interval=15MIN
WQ Output Selected Increments= 0
WQ Output face flow=0
WQ Output face velocity=0
WQ Output face area=0
WQ Output face dispersion=0
WQ Output cell volume=0
WQ Output cell surface area=0
WQ Output cell continuity=0
WQ Output cumulative cell continuity=0
WQ Output face conc=0
WQ Output face dconc_dx=0
WQ Output face courant=0
WQ Output face peclet=0
WQ Output face adv mass=0
WQ Output face disp mass=0
WQ Output cell mass=0
WQ Output cell source sink temp=0
WQ Output cell source sink nsm=0
WQ Output MaxMinRange=-1
WQ Daily Max Min Mean=-1
WQ Daily Range=0
WQ Daily Time=0
WQ Create Restart=0
WQ Fixed Restart=0
WQ System Summary=0
WQ Use Fixed Temperature=0
Sorting and Armoring Iterations= 10
XS Update Threshold= 0.02
Hydraulics Update Threshold= 0.02
Energy Slope Method= 1
Volume Change Method= 0
XS Weighting Method= 0
Number of US Weighted Cross Sections= 1
Number of DS Weighted Cross Sections= 1
Upstream XS Weight=0.25
Main XS Weight=0.5
Downstream XS Weight=0.25
Number of DS XS's Weighted with US Boundary= 1
Upstream Boundary Weight= 1
Weight of XSs Associated with US Boundary= 0
Number of US XS's Weighted with DS Boundary= 1
Downstream Boundary Weight= 0.5
Weight of XSs Associated with DS Boundary= 0.5
Sediment Output Level= 4
Mass or Volume Output= 0
Output Increment Type= 1
Profile and TS Output Increment= 10
XS Output Flag= 0
XS Output Increment= 10
Disregard all LS=0
Disregard all Conn=0
Disregard all Breaches=0
Disregard all Pumps=0

--- WFSJR 056.f01 (steady flow) ---

Flow Title=Multiple
Program Version=4.10
Number of Profiles= 7
Profile Names=10-year,25-year,50-year,1pct_min,100-year,1pct_plu,500-year
River Rch & RM=WFSJR 056,Reach-1         ,4250
     469     625     836     369    1113    3361    2038
Boundary for River Rch & Prof#=WFSJR 056,Reach-1         , 1
Up Type= 0
Dn Type= 3
Dn Slope=0.005
Boundary for River Rch & Prof#=WFSJR 056,Reach-1         , 2
Up Type= 0
Dn Type= 3
Dn Slope=0.005
Boundary for River Rch & Prof#=WFSJR 056,Reach-1         , 3
Up Type= 0
Dn Type= 3
Dn Slope=0.005
Boundary for River Rch & Prof#=WFSJR 056,Reach-1         , 4
Up Type= 0
Dn Type= 3
Dn Slope=0.005
Boundary for River Rch & Prof#=WFSJR 056,Reach-1         , 5
Up Type= 0
Dn Type= 3
Dn Slope=0.005
Boundary for River Rch & Prof#=WFSJR 056,Reach-1         , 6
Up Type= 0
Dn Type= 3
Dn Slope=0.005
Boundary for River Rch & Prof#=WFSJR 056,Reach-1         , 7
Up Type= 0
Dn Type= 3
Dn Slope=0.005
DSS Import GetInterval= 0
DSS Import GetPeak= 0
DSS Import FillOption= 0

--- WFSJR 056.g01 (geometry) ---

Geom Title=Existing Conditions
Program Version=4.10

River Reach=WFSJR 056       ,Reach-1
Reach XY= 30
      3724000.21     10260964.12      3724081.88     10260873.33
      3724155.78      10260671.7      3724135.37     10260576.95
      3724174.15      10260506.6       3724108.5     10260415.62
      3724177.38      10260266.3      3723992.42     10259993.81
      3723871.77     10259925.57      3723760.79      10259918.5
      3723726.25     10259878.47      3723762.14     10259805.24
      3723603.84     10259699.61      3723564.67     10259623.47
      3723493.04     10259062.45      3723546.41     10259003.72
      3723552.46     10258846.43      3723488.53     10258788.68
      3723503.23     10258701.84      3723458.23     10258606.84
      3723498.23     10258426.84      3723418.23     10258356.84
      3723258.23     10258366.84      3723128.23     10258296.84
      3723128.23     10258086.84      3723248.23     10258006.84
      3723258.23     10257886.84      3723208.23     10257756.84
      3723218.23     10257666.84      3723128.23     10257466.84

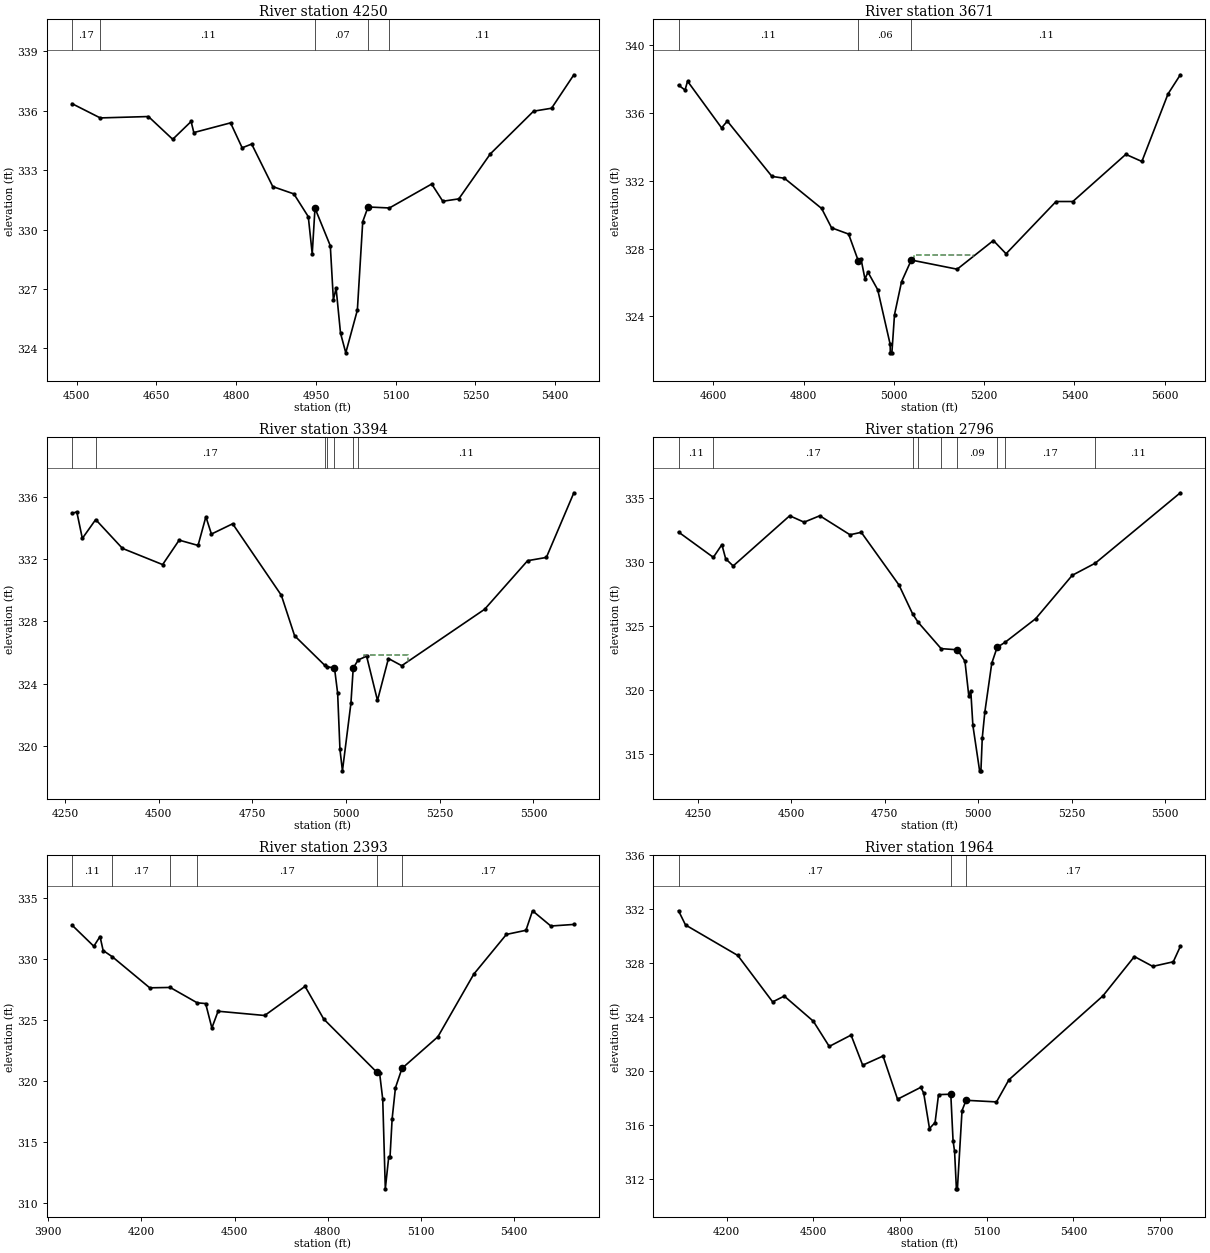
Type RM Length L Ch R = 1 ,4250    ,579,579,579
BEGIN DESCRIPTION:
WFSJR 056 8.0
END DESCRIPTION:
XS GIS Cut Line= 3
      3724646.41     10260805.71      3724155.78      10260671.7
      3723722.38     10260632.14
#Sta/Elev= 30
  4491.4  336.36  4544.4  335.64    4635  335.71  4680.7  334.56  4715.3  335.46
  4720.4   334.9  4789.5  335.39  4811.3  334.13  4829.2  334.32  4868.9  332.17
  4908.6   331.8  4935.7  330.65  4943.1  328.77  4948.3  331.08  4977.1  329.18
  4982.9  326.45    4988  327.04  4996.3  324.77  5006.2  323.77    5028  325.93
  5038.1   330.4  5048.1  331.14  5088.3  331.09  5167.8   332.3  5188.7  331.43
  5218.8  331.55    5278  333.82  5359.4  335.98  5393.3  336.13  5435.2  337.82
#Mann= 5 ,-1 , 0
  4491.4     .17       0  4544.4     .11       0  4948.3     .07       0
  5048.1     .17       0  5088.3     .11       0
#XS Ineff= 1 ,-1
    4915  4948.3  331.08
Permanent Ineff=
       F
Bank Sta=4948.3,5048.1
XS Rating Curve= 0 ,0
Exp/Cntr=0.3,0.1

Type RM Length L Ch R = 1 ,3671    ,277,277,277
BEGIN DESCRIPTION:
WFSJR 056 7.0
END DESCRIPTION:
XS GIS Cut Line= 3
      3724542.26     10259937.63      3724221.04     10260106.92
      3723574.32     10260484.54
#Sta/Elev= 30
  4522.6  337.63    4537  337.34  4542.6  337.86    4618  335.11  4630.7  335.51
  4729.6  332.25  4757.3  332.14  4839.7  330.36  4861.7  329.22  4899.5  328.85
    4921  327.27  4926.8  327.41  4935.7  326.21  4942.5   326.6    4964  325.57
  4991.6  322.35  4991.9  321.85  4995.4  321.85  5001.2   324.1  5016.8  326.04
  5038.4  327.32  5140.1  326.78  5220.3  328.47  5248.4  327.69  5359.2  330.77
  5396.4  330.77  5513.8  333.55  5549.4  333.13  5607.3  337.11  5634.6  338.24
#Mann= 3 ,-1 , 0
  4522.6     .11       0    4921     .06       0  5038.4     .11       0
#XS Ineff= 1 ,-1
  5044.2    5175  327.59
Permanent Ineff=
       F
Bank Sta=4921,5038.4
XS Rating Curve= 0 ,0
Exp/Cntr=0.3,0.1

Type RM Length L Ch R = 1 ,3394    ,598,598,598
BEGIN DESCRIPTION:
WFSJR 056 6.0
END DESCRIPTION:
XS GIS Cut Line= 3
      3724524.87     10259560.04      3724121.21     10259846.51
      3723444.16     10260349.95
#Sta/Elev= 30
  4269.3  334.93  4281.9  335.04  4296.7  333.33  4332.3  334.54  4403.7  332.69
  4510.9  331.65    4555  333.22  4605.4  332.88  4626.3  334.72  4641.1  333.61
  4697.7  334.27  4827.6  329.68    4863  327.08  4943.2  325.19  4948.5   325.1
  4969.4  325.01  4977.8   323.4    4984  319.78  4990.6  318.41  5013.2  322.74
  5019.4  325.01  5032.6  325.53  5055.1  325.77  5084.1  322.93  5113.3  325.62
  5148.8  325.16  5369.9  328.78  5484.6   331.9  5534.7  332.11    5608  336.26
#Mann= 7 ,-1 , 0
  4269.3     .11       0  4332.3     .17       0  4943.2     .11       0
  4948.5     .17       0  4969.4     .09       0  5019.4     .17       0
  5032.6     .11       0
#XS Ineff= 1 ,-1
  5048.7    5165  325.85
Permanent Ineff=
       F
Bank Sta=4969.4,5019.4
XS Rating Curve= 0 ,0
Exp/Cntr=0.3,0.1

Type RM Length L Ch R = 1 ,2796    ,403,403,403
BEGIN DESCRIPTION:
WFSJR 056 5.0
END DESCRIPTION:
XS GIS Cut Line= 3
      3724372.97       10259534.      3723713.23     10259616.47
      3723075.77      10259846.3
#Sta/Elev= 30
    4198  332.31  4291.1  330.34    4314  331.33  4324.1  330.23  4344.2  329.67
  4495.4  333.58  4533.9  333.08    4576  333.58  4656.7   332.1  4686.9  332.29
  4787.7  328.19  4824.4  325.93  4839.1  325.28  4900.5  323.23    4944  323.14
  4964.3  322.25  4974.6  319.54  4979.9  319.93  4985.5  317.25  5003.5  313.71
    5007  313.71  5010.6  316.27  5017.4  318.27    5036  322.09  5050.4  323.33
    5072  323.73  5153.4  325.56  5251.3  328.94  5313.1  329.89  5540.5  335.37
#Mann= 9 ,-1 , 0
    4198     .11       0  4291.1     .17       0  4824.4     .11       0
  4839.1     .17       0  4900.5     .15       0    4944     .09       0
  5050.4     .15       0    5072     .17       0  5313.1     .11       0
Bank Sta=4944,5050.4
XS Rating Curve= 0 ,0
Exp/Cntr=0.3,0.1

Type RM Length L Ch R = 1 ,2393    ,429,429,429
BEGIN DESCRIPTION:
WFSJR 056 4.0
END DESCRIPTION:
XS GIS Cut Line= 3
      3724537.86     10259286.61      3723514.46     10259287.13
      3722951.09     10259468.34
#Sta/Elev= 30
  3976.6  332.78  4046.6  331.05  4066.6  331.85  4076.6   330.7  4106.6  330.18
  4226.6  327.64  4292.5  327.67  4379.4  326.41  4406.6  326.35  4426.6  324.35
  4446.6  325.72  4596.6  325.37  4726.6  327.76  4786.6  325.08  4956.6  320.74
  4966.6  320.63  4976.6   318.5  4984.9  311.15  4995.8  313.75    5000  313.75
  5006.9  316.91  5017.5  319.44  5038.5  321.03    5154  323.62  5269.6  328.76
  5374.6  332.02  5437.6  332.36  5458.8  333.96  5517.7  332.71  5591.8  332.84
#Mann= 6 ,-1 , 0
  3976.6     .11       0  4106.6     .17       0  4292.5     .11       0
  4379.4     .17       0  4956.6     .09       0  5038.5     .17       0
Bank Sta=4956.6,5038.5
XS Rating Curve= 0 ,0
Exp/Cntr=0.3,0.1

Type RM Length L Ch R = 1 ,1964    ,349,349,349
BEGIN DESCRIPTION:
WFSJR 056 3.0
END DESCRIPTION:
XS GIS Cut Line= 3
      3724511.83     10258774.46      3723639.44     10258861.26
      3722827.77     10259143.39
#Sta/Elev= 30
  4033.9   331.9    4058  330.85  4238.9  328.59  4359.5  325.15  4399.7  325.58
  4500.2  323.72  4555.3  321.85  4630.8  322.69    4671  320.46  4741.4  321.14
  4791.6  317.94    4872  318.82    4882   318.4  4902.1  315.77  4921.4  316.21
  4933.4  318.28  4975.8  318.31  4983.6  314.88  4988.9  314.07  4995.2   311.3
  4998.7   311.3  5014.7   317.1  5028.7  317.86  5133.9  317.74  5176.9  319.38
  5501.9  325.59    5611  328.51  5674.5  327.78  5745.5  328.12  5769.9  329.26
#Mann= 3 , 0 , 0
  4033.9     .17       0  4975.8     .09       0  5028.7     .17       0
Bank Sta=4975.8,5028.7
XS Rating Curve= 0 ,0
Exp/Cntr=0.3,0.1

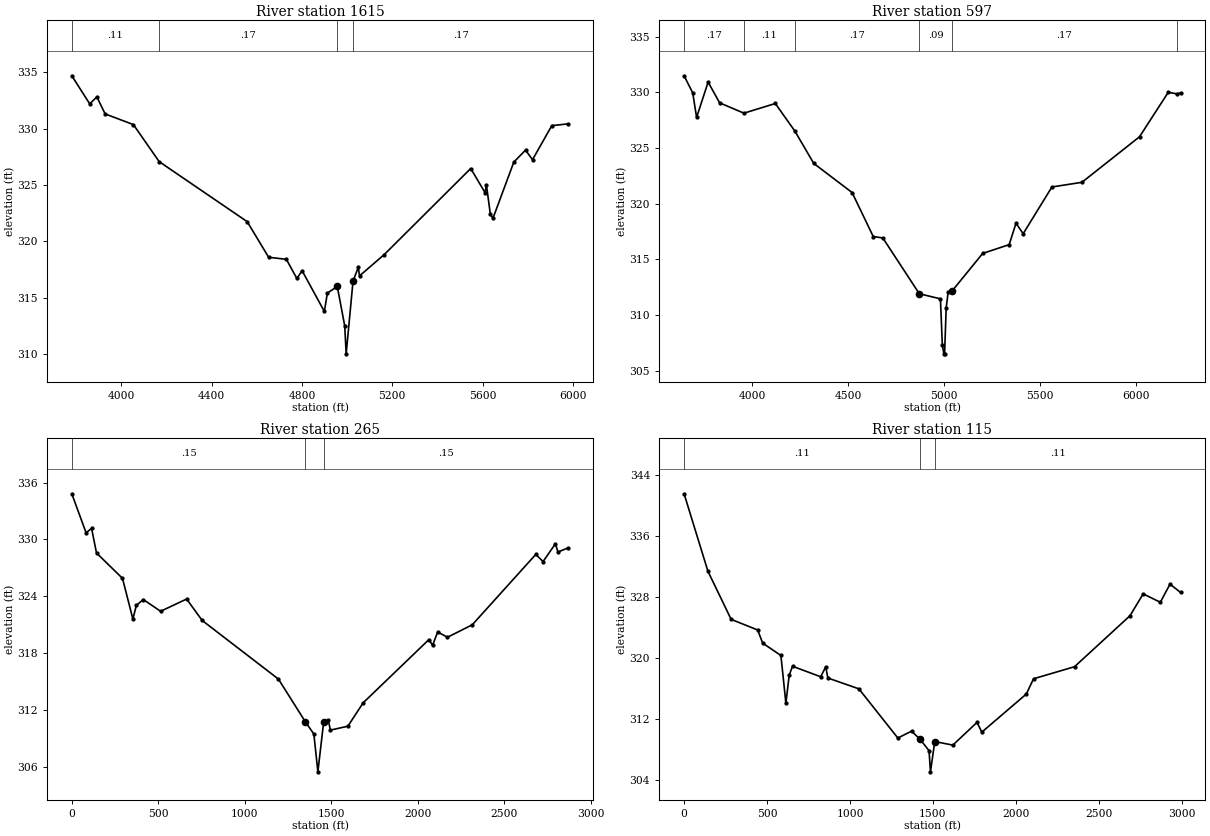
Type RM Length L Ch R = 1 ,1615    ,1018,1018,1018
BEGIN DESCRIPTION:
WFSJR 056 2.0
END DESCRIPTION:
XS GIS Cut Line= 3
      3724602.95     10258188.53      3723713.23     10258492.34
      3722563.06     10259004.49
#Sta/Elev= 30
  3780.7  334.68  3860.1  332.19  3891.7  332.81  3928.3   331.3  4053.6  330.35
  4167.7  327.07  4557.5  321.75  4652.6  318.59  4731.1  318.41  4777.6  316.71
  4800.8   317.4  4899.3  313.79  4912.8  315.42  4956.7     316  4989.5  312.52
    4996  310.03  5026.4  316.48  5049.7   317.7  5055.1  316.94  5164.6  318.83
  5547.7  326.46  5611.5  324.31    5617  325.04  5634.7  322.39  5646.3  322.05
  5738.6  327.03  5790.6  328.09  5821.4  327.24  5906.8  330.26  5979.9  330.42
#Mann= 4 ,-1 , 0
  3780.7     .11       0  4167.7     .17       0  4956.7     .09       0
  5026.4     .17       0
Bank Sta=4956.7,5026.4
XS Rating Curve= 0 ,0
Exp/Cntr=0.3,0.1

Type RM Length L Ch R = 1 ,597     ,333,333,333
BEGIN DESCRIPTION:
WFSJR 056 1.0
END DESCRIPTION:
XS GIS Cut Line= 3
      3724602.95     10257945.46      3722935.45     10258001.89
      3722384.44     10258737.43
#Sta/Elev= 30
  3644.5   331.5  3689.6  329.96  3709.6  327.76  3769.7  330.93  3829.7  329.07
  3956.3  328.14  4119.9  329.01  4222.6  326.51    4320  323.63  4520.1  321.01
  4630.2  317.06  4680.2  316.93  4870.3  311.92  4980.4  311.46  4990.4  307.27
  4998.6  306.52  5002.1  306.52  5010.4  310.65  5020.4  312.04  5040.4  312.15
  5200.5  315.54  5338.6  316.33  5374.4  318.26  5411.5  317.31  5561.5  321.51
  5717.8  321.93  6017.9  326.02  6167.9  330.02  6213.3  329.87    6232  329.97
#Mann= 6 ,-1 , 0
  3644.5     .17       0  3956.3     .11       0  4222.6     .17       0
  4870.3     .09       0  5040.4     .17       0  6213.3     .11       0
Bank Sta=4870.3,5040.4
XS Rating Curve= 0 ,0
Exp/Cntr=0.3,0.1

Type RM Length L Ch R = 1 ,265     ,150,150,150
XS GIS Cut Line= 4
      3724640.36     10257711.46      3723356.51     10257648.96
      3723023.18     10257745.31      3722307.03     10258753.13
#Sta/Elev= 30
       0  334.82    82.6   330.7   114.2  331.18   142.7  328.58   292.9   325.9
   352.9  321.61     373  323.05     413  323.67   513.1  322.43   663.3  323.72
   753.4  321.46  1193.9  315.28  1349.3  310.78  1398.5  309.49  1421.8   305.5
  1455.4  310.79  1481.8  310.95  1494.2   309.9  1595.1  310.31  1683.5  312.78
  2063.6  319.45  2084.5  318.84    2114  320.25  2170.6  319.69  2314.1  321.01
    2681  328.43  2722.8  327.67  2794.1  329.55  2808.9  328.68  2868.7  329.12
#Mann= 3 , 0 , 0
       0     .15       0  1349.3     .07       0  1455.4     .15       0
Bank Sta=1349.3,1455.4
XS Rating Curve= 0 ,0
Exp/Cntr=0.3,0.1

Type RM Length L Ch R = 1 ,115     ,0,0,0
XS GIS Cut Line= 4
      3724641.55     10257486.79       3723485.3     10257472.47
      3723008.74     10257602.67      3722301.71      10258745.9
#Sta/Elev= 30
       0  341.52   143.7  331.37   283.7  325.07   443.7  323.68   473.7  321.96
   583.7  320.34   613.7  314.09   633.7  317.76   653.7  318.93   823.8  317.55
   853.8  318.86     867  317.39  1053.8  315.97  1288.7  309.53  1371.4  310.43
  1423.2  309.35  1476.9  307.87  1485.4   305.1  1511.4  309.07  1620.2   308.6
  1766.1  311.58  1795.1   310.3  2063.3  315.29    2107  317.29    2354  318.87
  2688.6  325.55  2767.8  328.41  2871.3  327.31  2929.8  329.69  2993.5  328.59
#Mann= 3 , 0 , 0
       0     .11       0  1423.2     .06       0  1511.4     .11       0
Bank Sta=1423.2,1511.4
XS Rating Curve= 0 ,0
Exp/Cntr=0.3,0.1

Chan Stop Cuts=-1
Use User Specified Reach Order=0
Composite Channel Slope=5