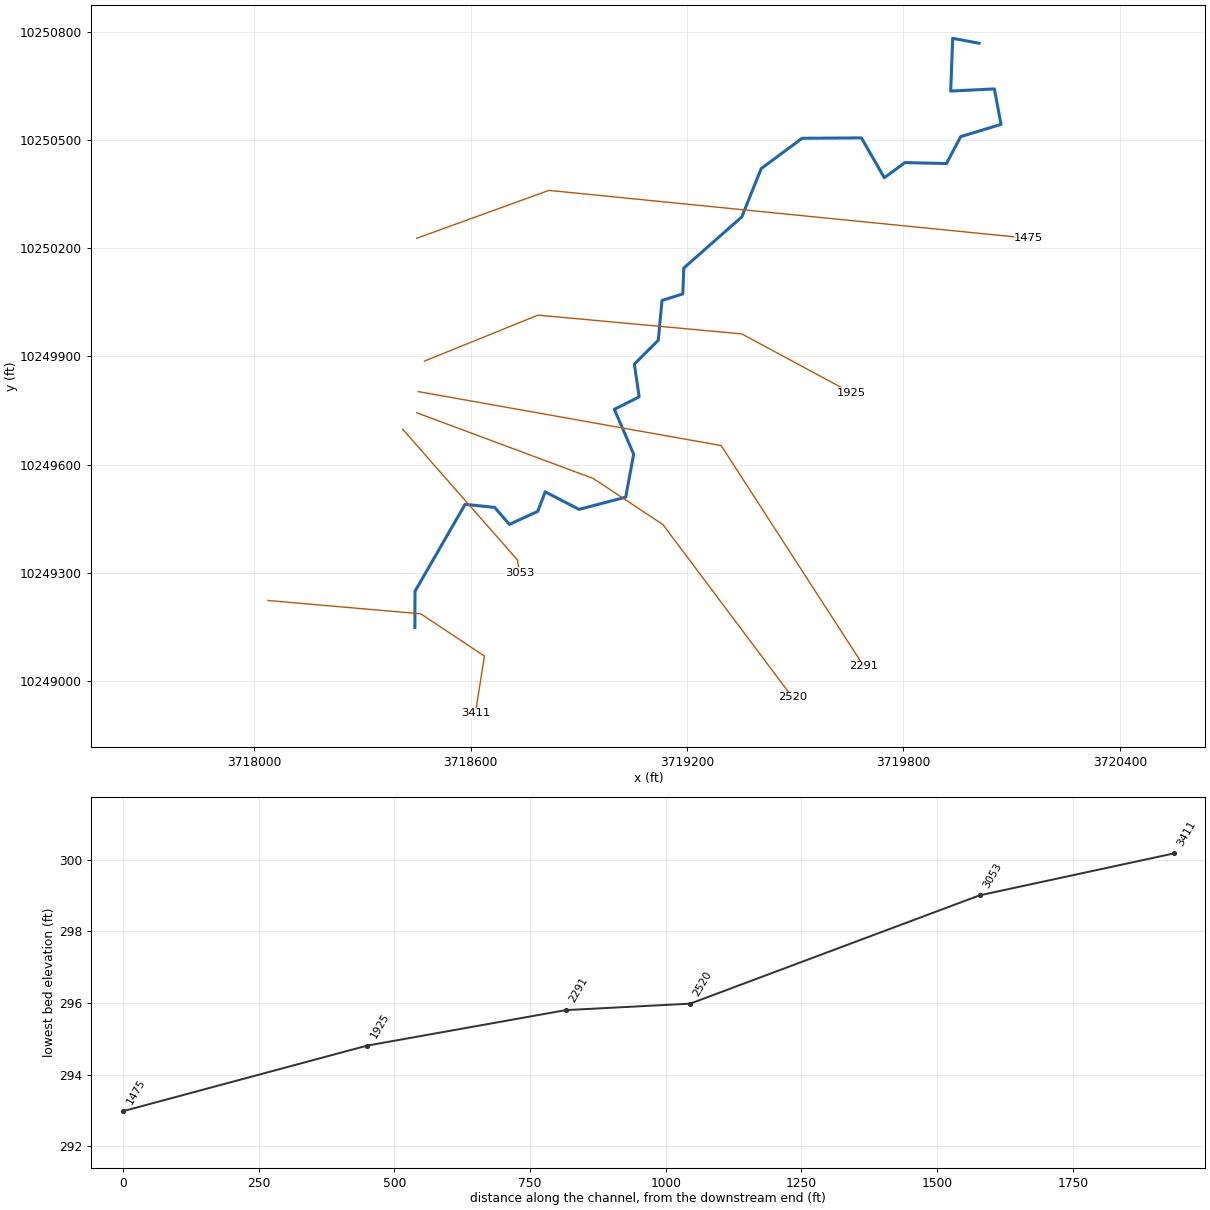
--- WFSJR 057.prj (project) ---

Proj Title=WFSJR 057 Base Level Engineering
Current Plan=p01
Default Exp/Contr=0.3,0.1
English Units
Geom File=g01
Flow File=f01
Plan File=p01
Y Axis Title=Elevation
X Axis Title(PF)=Main Channel Distance
X Axis Title(XS)=Station
BEGIN DESCRIPTION:
WFSJR 057
END DESCRIPTION:
DSS Export Rating Curves= 0
DSS Export Rating Curve Sorted= 0
DSS Export Volume Flow Curves= 0
DXF OffsetX= 0
DXF OffsetY= 0
DXF ScaleX= 1
DXF ScaleY= 10

--- WFSJR 057.p01 (plan) ---

Plan Title=Multiple Run
Program Version=4.10
Short Identifier=Multiple
Geom File=g01
Flow File=f01
Subcritical Flow
K Sum by GR= 0
Std Step Tol= 0.01
Critical Tol= 0.01
Num of Std Step Trials= 20
Max Error Tol= 0.3
Flow Tol Ratio= 0.001
Split Flow NTrial= 30
Split Flow Tol= 0.02
Split Flow Ratio= 0.02
Log Output Level= 0
Friction Slope Method= 1
Unsteady Friction Slope Method= 2
Unsteady Bridges Friction Slope Method= 1
Parabolic Critical Depth
Global Vel Dist= 1 , 1 , 1
Global Log Level= 0
CheckData=True
Encroach Param=-1 ,0,0, 0
BEGIN DESCRIPTION:
Multiple Run
END DESCRIPTION:
Computation Interval=1HOUR
Output Interval=1HOUR
Run HTab= 0
Run UNet= 0
Run PostProcess= 0
Run WQNet= 0
UNET Theta= 1
UNET Theta Warmup= 1
UNET ZTol= 0.02
UNET ZSATol= 0.05
UNET MxIter= 20
UNET MaxInSteps= 0
UNET DtIC= 0
UNET DtMin= 0
UNET MaxCRTS= 20
UNET WFStab= 2
UNET SFStab= 1
UNET WFX= 1
UNET SFX= 1
UNET DSS MLevel= 4
UNET DZMax Abort= 100
UNET Convert EG Bridges= 0
UNET Use Existing IB Tables=-1
UNET Froude Reduction=False
UNET Froude Limit= 1
UNET Froude Power= 10
UNET Time Slicing=0,0, 5
UNET Junction Losses=0
Instantaneous Interval=1HOUR
Write IC File= 0
Write IC File at Sim End=0
Echo Input=False
Echo Parameters=False
Echo Output=False
Write Detailed= 0
WQ AD Non Conservative
WQ ULTIMATE=-1
WQ Max Comp Step=1HOUR
WQ Output Interval=15MIN
WQ Output Selected Increments= 0
WQ Output face flow=0
WQ Output face velocity=0
WQ Output face area=0
WQ Output face dispersion=0
WQ Output cell volume=0
WQ Output cell surface area=0
WQ Output cell continuity=0
WQ Output cumulative cell continuity=0
WQ Output face conc=0
WQ Output face dconc_dx=0
WQ Output face courant=0
WQ Output face peclet=0
WQ Output face adv mass=0
WQ Output face disp mass=0
WQ Output cell mass=0
WQ Output cell source sink temp=0
WQ Output cell source sink nsm=0
WQ Output MaxMinRange=-1
WQ Daily Max Min Mean=-1
WQ Daily Range=0
WQ Daily Time=0
WQ Create Restart=0
WQ Fixed Restart=0
WQ System Summary=0
WQ Use Fixed Temperature=0
Sorting and Armoring Iterations= 10
XS Update Threshold= 0.02
Hydraulics Update Threshold= 0.02
Energy Slope Method= 1
Volume Change Method= 0
XS Weighting Method= 0
Number of US Weighted Cross Sections= 1
Number of DS Weighted Cross Sections= 1
Upstream XS Weight=0.25
Main XS Weight=0.5
Downstream XS Weight=0.25
Number of DS XS's Weighted with US Boundary= 1
Upstream Boundary Weight= 1
Weight of XSs Associated with US Boundary= 0
Number of US XS's Weighted with DS Boundary= 1
Downstream Boundary Weight= 0.5
Weight of XSs Associated with DS Boundary= 0.5
Sediment Output Level= 4
Mass or Volume Output= 0
Output Increment Type= 1
Profile and TS Output Increment= 10
XS Output Flag= 0
XS Output Increment= 10
Disregard all LS=0
Disregard all Conn=0
Disregard all Breaches=0
Disregard all Pumps=0

--- WFSJR 057.f01 (steady flow) ---

Flow Title=Multiple
Program Version=4.10
Number of Profiles= 7
Profile Names=10-year,25-year,50-year,1pct_min,100-year,1pct_plu,500-year
River Rch & RM=WFSJR 057,Reach-1         ,3411
     387     506     669     291     879    2655    1569
River Rch & RM=WFSJR 057,Reach-1         ,2291
     452     598     795     348    1050    3171    1895
Boundary for River Rch & Prof#=WFSJR 057,Reach-1         , 1
Up Type= 0
Dn Type= 3
Dn Slope=0.004
Boundary for River Rch & Prof#=WFSJR 057,Reach-1         , 2
Up Type= 0
Dn Type= 3
Dn Slope=0.004
Boundary for River Rch & Prof#=WFSJR 057,Reach-1         , 3
Up Type= 0
Dn Type= 3
Dn Slope=0.004
Boundary for River Rch & Prof#=WFSJR 057,Reach-1         , 4
Up Type= 0
Dn Type= 3
Dn Slope=0.004
Boundary for River Rch & Prof#=WFSJR 057,Reach-1         , 5
Up Type= 0
Dn Type= 3
Dn Slope=0.004
Boundary for River Rch & Prof#=WFSJR 057,Reach-1         , 6
Up Type= 0
Dn Type= 3
Dn Slope=0.004
Boundary for River Rch & Prof#=WFSJR 057,Reach-1         , 7
Up Type= 0
Dn Type= 3
Dn Slope=0.004
DSS Import GetInterval= 0
DSS Import GetPeak= 0
DSS Import FillOption= 0

--- WFSJR 057.g01 (geometry) ---

Geom Title=Existing Conditions
Program Version=4.10

River Reach=WFSJR 057       ,Reach-1
Reach XY= 30
      3718445.21     10249148.23      3718445.56     10249248.75
      3718584.45     10249489.72      3718666.39     10249481.39
      3718707.36     10249434.17      3718785.84     10249470.28
      3718806.67     10249524.44      3718900.42     10249475.83
      3719029.75     10249509.69      3719051.79     10249628.86
      3718998.32     10249753.16      3719067.07     10249787.89
      3719053.74     10249878.74      3719120.06     10249944.71
      3719130.47     10250055.13      3719188.11     10250073.19
      3719190.89     10250145.06      3719351.65     10250286.73
      3719405.47     10250420.76      3719519.02     10250504.78
      3719683.25     10250505.83      3719746.79     10250395.41
      3719804.09     10250437.42      3719919.02     10250434.65
       3719958.6      10250509.3       3720070.4     10250543.33
        3720052.     10250641.59      3719930.82     10250635.69
      3719936.38     10250781.87       3720009.5     10250768.25

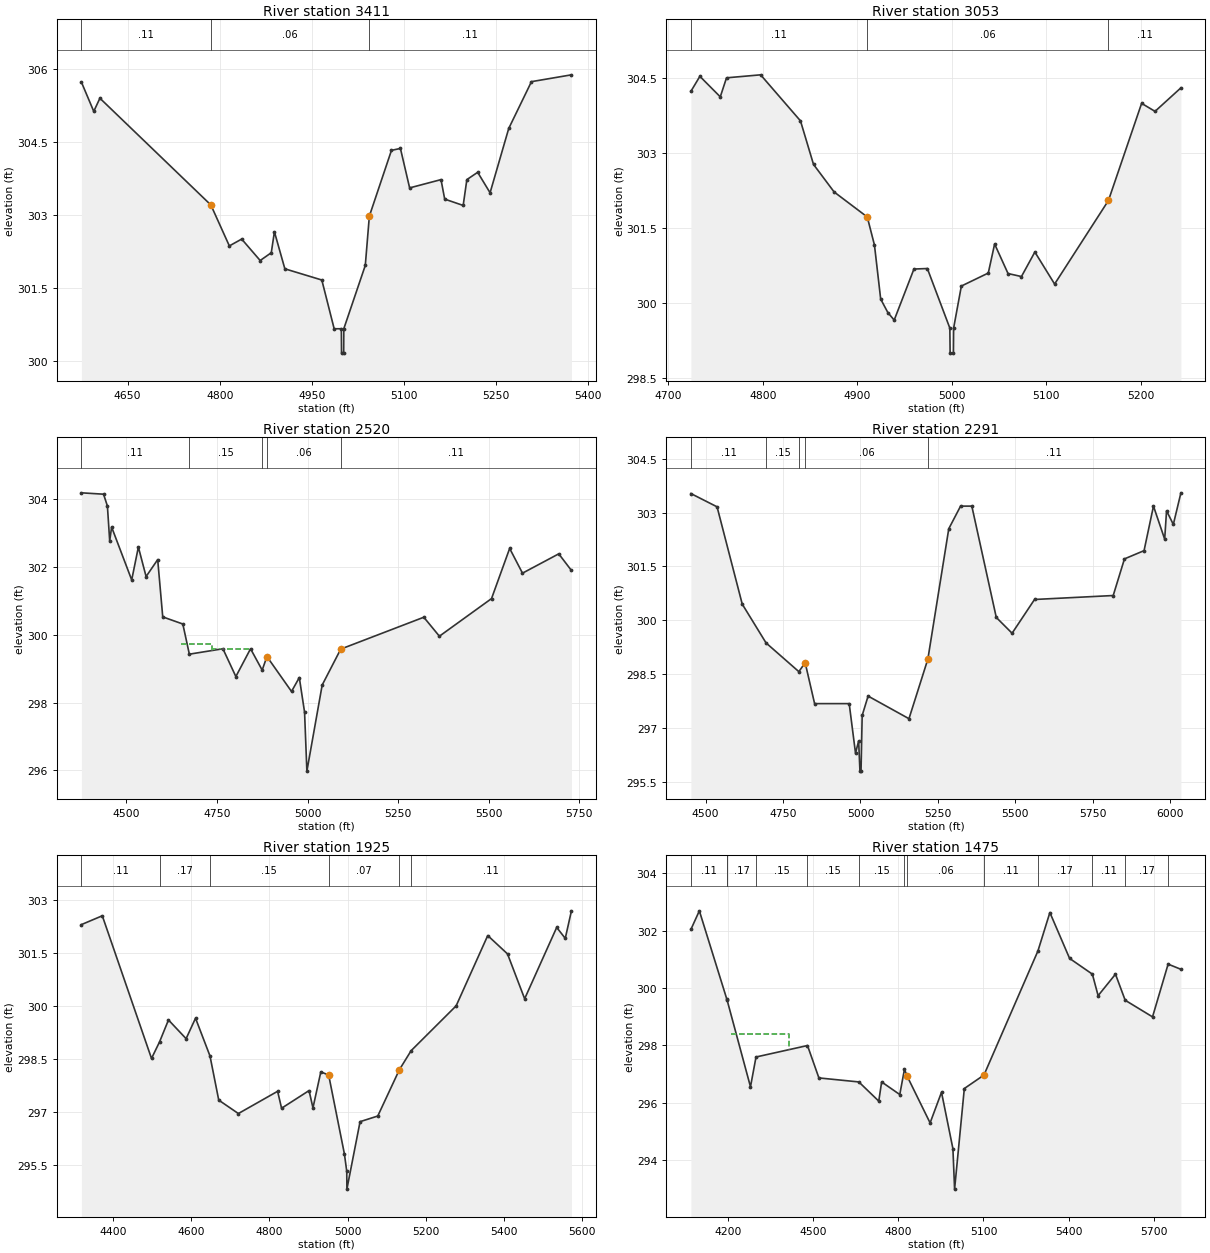
Type RM Length L Ch R = 1 ,3411    ,358,358,358
BEGIN DESCRIPTION:
WFSJR 057 2.0
END DESCRIPTION:
XS GIS Cut Line= 4
      3718037.84     10249223.22      3718461.53     10249186.25
      3718638.08     10249069.03      3718612.92     10248910.23
#Sta/Elev= 30
  4574.7  305.73  4594.8  305.13  4604.8   305.4  4785.5  303.21  4815.6  302.37
  4835.7  302.51  4865.8  302.07  4883.9  302.23    4889  302.66    4906   301.9
  4966.2  301.67  4986.3  300.67    4998  300.67  4998.3  300.17  5001.8  300.17
    5002  300.67    5037  301.97  5043.6  302.98  5079.6  304.33  5094.2  304.37
  5109.2  303.56  5160.3  303.73  5166.3  303.33  5196.4   303.2  5202.4  303.73
    5220  303.88  5240.2  303.46  5270.6  304.78  5307.6  305.74  5372.7  305.88
#Mann= 3 , 0 , 0
  4574.7     .11       0  4785.5     .06       0  5043.6     .11       0
Bank Sta=4785.5,5043.6
XS Rating Curve= 0 ,0
Exp/Cntr=0.3,0.1

Type RM Length L Ch R = 1 ,3053    ,533,533,533
BEGIN DESCRIPTION:
Mapping XS ab9b6f3a
END DESCRIPTION:
XS GIS Cut Line= 3
      3718411.29     10249698.22      3718729.72     10249335.45
      3718735.12     10249299.86
#Sta/Elev= 30
  4723.9  304.23  4733.4  304.53    4755  304.12  4761.6   304.5  4797.7  304.56
  4839.9  303.64  4853.7  302.77  4875.5  302.22  4910.6  301.72  4918.2  301.16
  4924.8  300.08  4932.4  299.81  4939.1  299.66    4960  300.68  4974.2  300.69
    4998   299.5  4998.3     299  5001.8     299    5002   299.5  5010.2  300.34
  5038.7   300.6  5045.4  301.18  5059.6  300.59  5073.8  300.53    5088  301.02
  5108.9  300.38  5165.9  302.05    5201  303.99  5215.2  303.83  5242.6   304.3
#Mann= 3 , 0 , 0
  4723.9     .11       0  4910.6     .06       0  5165.9     .11       0
Bank Sta=4910.6,5165.9
XS Rating Curve= 0 ,0
Exp/Cntr=0.3,0.1

Type RM Length L Ch R = 1 ,2520    ,229,229,229
BEGIN DESCRIPTION:
Mapping XS 0b094df0
END DESCRIPTION:
XS GIS Cut Line= 4
      3718450.64     10249743.62      3718940.23     10249561.32
      3719132.94     10249433.72      3719491.76     10248955.29
#Sta/Elev= 30
  4376.4  304.19  4437.5  304.15  4448.1   303.8  4454.4  302.77  4459.7  303.18
  4515.1  301.62  4533.5  302.59  4554.8  301.72  4586.8  302.22  4600.7  300.53
  4656.1  300.32  4674.1  299.43  4766.7  299.59  4802.4  298.77  4842.9  299.59
    4875  298.96  4888.1  299.36  4955.9  298.33  4977.4  298.74  4991.9  297.72
  4998.3  295.98  5040.5  298.52  5091.7  299.58  5320.8  300.52  5363.8  299.96
  5507.6  301.07  5557.6  302.55    5593  301.82    5693  302.39    5728   301.9
#Mann= 5 ,-1 , 0
  4376.4     .11       0  4674.1     .15       0    4875     .11       0
  4888.1     .06       0  5091.7     .11       0
#XS Ineff= 2 ,-1
    4650  4736.2  299.73    4737  4842.9  299.59
Permanent Ineff=
       F       F
Bank Sta=4888.1,5091.7
XS Rating Curve= 0 ,0
Exp/Cntr=0.3,0.1

Type RM Length L Ch R = 1 ,2291    ,366,366,366
BEGIN DESCRIPTION:
Mapping XS 3908bedb
END DESCRIPTION:
XS GIS Cut Line= 3
      3718454.63     10249802.43      3719294.45     10249652.76
      3719690.23     10249040.49
#Sta/Elev= 30
  4452.5  303.53    4537  303.16  4618.3  300.45  4695.2  299.37  4801.1  298.57
  4821.4  298.82  4851.9  297.68  4963.6  297.68    4984   296.3  4994.1  296.64
  4998.3   295.8  5001.8   295.8  5005.5  297.35  5024.6  297.89  5156.6  297.26
  5217.6  298.92  5285.1  302.55  5323.2  303.18  5359.5  303.18  5438.5  300.08
  5489.5  299.64    5562  300.58    5816  300.69  5852.3  301.71  5915.6  301.94
    5946  303.18  5982.2  302.26  5988.2  303.05  6010.1  302.67  6034.6  303.55
#Mann= 5 ,-1 , 0
  4452.5     .11       0  4695.2     .15       0  4801.1     .11       0
  4821.4     .06       0  5217.6     .11       0
Bank Sta=4821.4,5217.6
XS Rating Curve= 0 ,0
Exp/Cntr=0.3,0.1

Type RM Length L Ch R = 1 ,1925    ,450,450,450
BEGIN DESCRIPTION:
Mapping XS 5a4de4b4
END DESCRIPTION:
XS GIS Cut Line= 4
      3718471.45     10249886.83      3718786.59     10250014.45
      3719351.69     10249962.36      3719656.34     10249798.32
#Sta/Elev= 30
  4319.2   302.3  4372.6  302.55  4498.5  298.51  4519.1  298.98  4541.9   299.6
    4587  299.07  4611.1  299.65  4648.1  298.58  4670.5  297.33  4720.7  296.95
  4821.1  297.58  4831.2   297.1  4901.5   297.6  4911.5  297.11  4931.6  298.13
  4951.7  298.04  4991.9  295.81    4998  295.31  4998.3  294.81    5032  296.72
  5077.3  296.88  5132.5  298.19  5162.6  298.73  5277.8     300  5358.6  301.99
  5409.2  301.47    5453   300.2    5535  302.22  5556.9  301.91  5572.7  302.69
#Mann= 6 ,-1 , 0
  4319.2     .11       0  4519.1     .17       0  4648.1     .15       0
  4951.7     .07       0  5132.5     .15       0  5162.6     .11       0
Bank Sta=4951.7,5132.5
XS Rating Curve= 0 ,0
Exp/Cntr=0.3,0.1

Type RM Length L Ch R = 1 ,1475    ,0,0,0
BEGIN DESCRIPTION:
WFSJR 057 1.0
END DESCRIPTION:
XS GIS Cut Line= 3
      3718450.36     10250227.52      3718816.91     10250360.31
      3720147.34     10250227.51
#Sta/Elev= 30
    4069  302.04  4098.8  302.69  4194.9  299.63  4196.5  299.58    4279  296.55
  4298.5  297.59  4479.9  297.99  4520.1  296.86  4660.8  296.72  4731.1  296.05
  4741.2  296.72  4805.1  296.28  4821.6  297.16  4831.6  296.91    4912  295.29
  4952.2  296.36  4992.4  294.39  4998.3  292.98  5032.6  296.49  5101.8  296.96
    5292  301.29  5334.1  302.63  5403.6  301.03  5483.9  300.48  5504.1  299.73
  5565.3  300.48  5599.5  299.57  5695.9  298.99  5750.8  300.83  5795.9  300.65
#Mann= 13 ,-1 , 0
    4069     .11       0  4194.9     .15       0  4196.5     .17       0
  4298.5     .15       0  4479.9     .15       0  4660.8     .15       0
  4821.6     .11       0  4831.6     .06       0  5101.8     .11       0
    5292     .17       0  5483.9     .11       0  5599.5     .17       0
  5750.8     .11       0
#XS Ineff= 2 ,-1
    4210  4414.5  298.38    4440  4821.6  297.16
Permanent Ineff=
       F       T
Bank Sta=4831.6,5101.8
XS Rating Curve= 0 ,0
Exp/Cntr=0.3,0.1

Chan Stop Cuts=-1
Use User Specified Reach Order=0
Composite Channel Slope=5