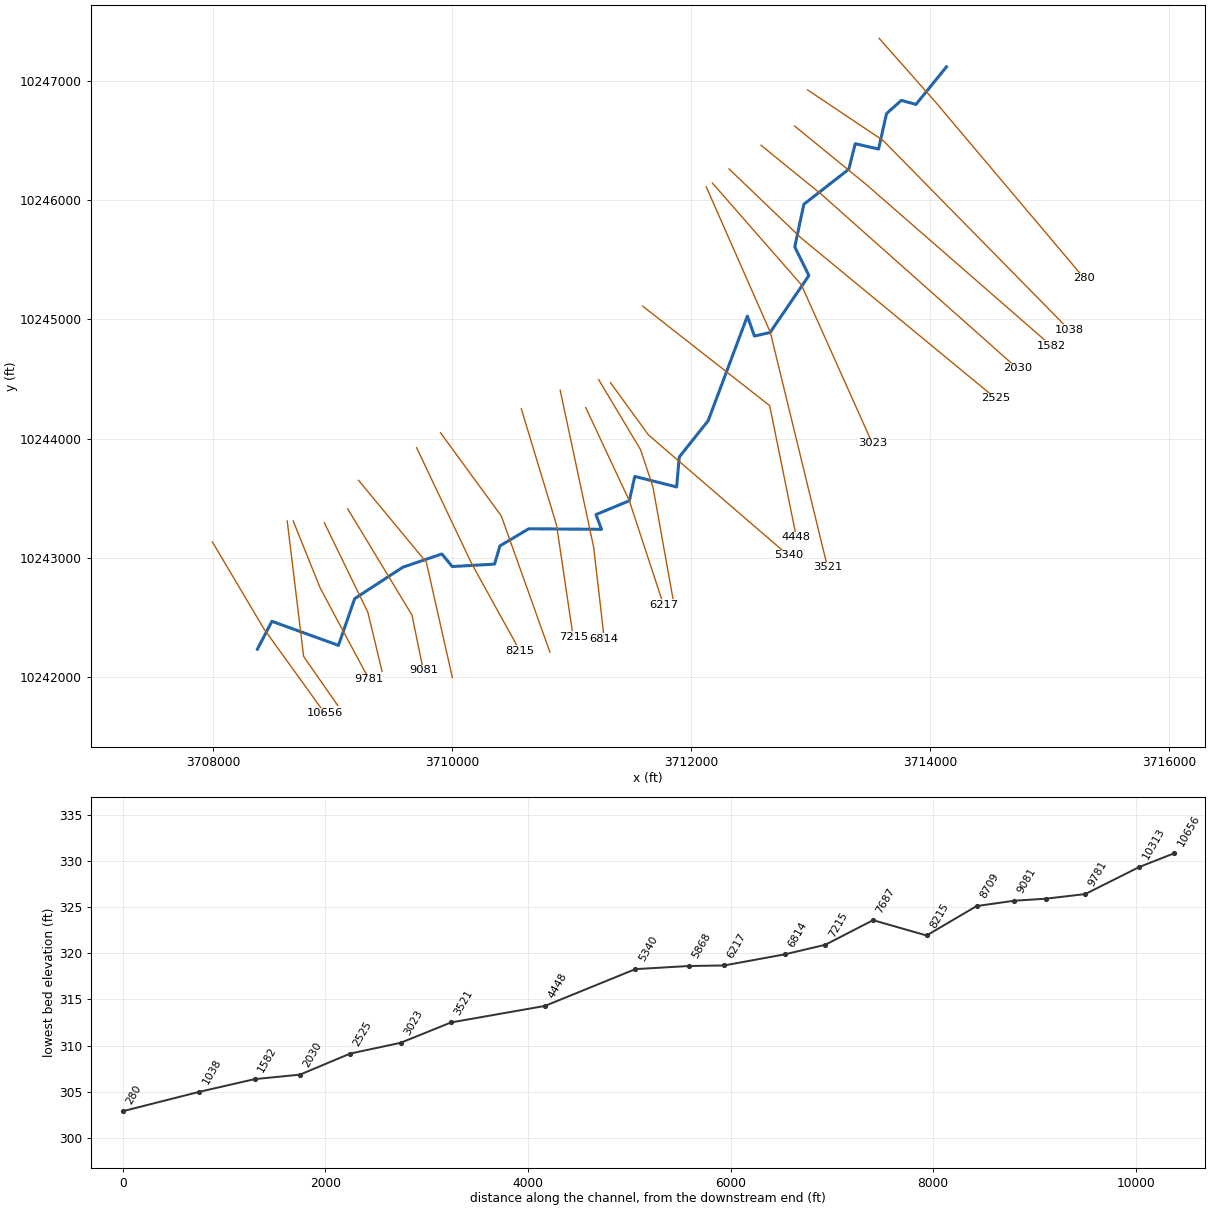
--- WFSJR 058.prj (project) ---

Proj Title=WFSJR 058 Base Level Engineering
Current Plan=p01
Default Exp/Contr=0.3,0.1
English Units
Geom File=g01
Flow File=f01
Plan File=p01
Y Axis Title=Elevation
X Axis Title(PF)=Main Channel Distance
X Axis Title(XS)=Station
BEGIN DESCRIPTION:
WFSJR 058
END DESCRIPTION:
DSS Export Rating Curves= 0
DSS Export Rating Curve Sorted= 0
DSS Export Volume Flow Curves= 0
DXF OffsetX= 0
DXF OffsetY= 0
DXF ScaleX= 1
DXF ScaleY= 10

--- WFSJR 058.p01 (plan) ---

Plan Title=Multiple Run
Program Version=4.10
Short Identifier=Multiple
Geom File=g01
Flow File=f01
Subcritical Flow
K Sum by GR= 0
Std Step Tol= 0.01
Critical Tol= 0.01
Num of Std Step Trials= 20
Max Error Tol= 0.3
Flow Tol Ratio= 0.001
Split Flow NTrial= 30
Split Flow Tol= 0.02
Split Flow Ratio= 0.02
Log Output Level= 0
Friction Slope Method= 1
Unsteady Friction Slope Method= 2
Unsteady Bridges Friction Slope Method= 1
Parabolic Critical Depth
Global Vel Dist= 1 , 1 , 1
Global Log Level= 0
CheckData=True
Encroach Param=-1 ,0,0, 0
BEGIN DESCRIPTION:
Multiple Run
END DESCRIPTION:
Computation Interval=1HOUR
Output Interval=1HOUR
Run HTab= 0
Run UNet= 0
Run PostProcess= 0
Run WQNet= 0
UNET Theta= 1
UNET Theta Warmup= 1
UNET ZTol= 0.02
UNET ZSATol= 0.05
UNET MxIter= 20
UNET MaxInSteps= 0
UNET DtIC= 0
UNET DtMin= 0
UNET MaxCRTS= 20
UNET WFStab= 2
UNET SFStab= 1
UNET WFX= 1
UNET SFX= 1
UNET DSS MLevel= 4
UNET DZMax Abort= 100
UNET Convert EG Bridges= 0
UNET Use Existing IB Tables=-1
UNET Froude Reduction=False
UNET Froude Limit= 1
UNET Froude Power= 10
UNET Time Slicing=0,0, 5
UNET Junction Losses=0
Instantaneous Interval=1HOUR
Write IC File= 0
Write IC File at Sim End=0
Echo Input=False
Echo Parameters=False
Echo Output=False
Write Detailed= 0
WQ AD Non Conservative
WQ ULTIMATE=-1
WQ Max Comp Step=1HOUR
WQ Output Interval=15MIN
WQ Output Selected Increments= 0
WQ Output face flow=0
WQ Output face velocity=0
WQ Output face area=0
WQ Output face dispersion=0
WQ Output cell volume=0
WQ Output cell surface area=0
WQ Output cell continuity=0
WQ Output cumulative cell continuity=0
WQ Output face conc=0
WQ Output face dconc_dx=0
WQ Output face courant=0
WQ Output face peclet=0
WQ Output face adv mass=0
WQ Output face disp mass=0
WQ Output cell mass=0
WQ Output cell source sink temp=0
WQ Output cell source sink nsm=0
WQ Output MaxMinRange=-1
WQ Daily Max Min Mean=-1
WQ Daily Range=0
WQ Daily Time=0
WQ Create Restart=0
WQ Fixed Restart=0
WQ System Summary=0
WQ Use Fixed Temperature=0
Sorting and Armoring Iterations= 10
XS Update Threshold= 0.02
Hydraulics Update Threshold= 0.02
Energy Slope Method= 1
Volume Change Method= 0
XS Weighting Method= 0
Number of US Weighted Cross Sections= 1
Number of DS Weighted Cross Sections= 1
Upstream XS Weight=0.25
Main XS Weight=0.5
Downstream XS Weight=0.25
Number of DS XS's Weighted with US Boundary= 1
Upstream Boundary Weight= 1
Weight of XSs Associated with US Boundary= 0
Number of US XS's Weighted with DS Boundary= 1
Downstream Boundary Weight= 0.5
Weight of XSs Associated with DS Boundary= 0.5
Sediment Output Level= 4
Mass or Volume Output= 0
Output Increment Type= 1
Profile and TS Output Increment= 10
XS Output Flag= 0
XS Output Increment= 10
Disregard all LS=0
Disregard all Conn=0
Disregard all Breaches=0
Disregard all Pumps=0

--- WFSJR 058.f01 (steady flow) ---

Flow Title=Multiple
Program Version=4.10
Number of Profiles= 7
Profile Names=10-year,25-year,50-year,1pct_min,100-year,1pct_plu,500-year
River Rch & RM=WFSJR 058,Reach-1         ,10656
     667     905    1224     544    1643    4962    3065
River Rch & RM=WFSJR 058,Reach-1         ,4448
     765    1040    1409     627    1892    5714    3533
Boundary for River Rch & Prof#=WFSJR 058,Reach-1         , 1
Up Type= 0
Dn Type= 3
Dn Slope=0.002
Boundary for River Rch & Prof#=WFSJR 058,Reach-1         , 2
Up Type= 0
Dn Type= 3
Dn Slope=0.002
Boundary for River Rch & Prof#=WFSJR 058,Reach-1         , 3
Up Type= 0
Dn Type= 3
Dn Slope=0.002
Boundary for River Rch & Prof#=WFSJR 058,Reach-1         , 4
Up Type= 0
Dn Type= 3
Dn Slope=0.002
Boundary for River Rch & Prof#=WFSJR 058,Reach-1         , 5
Up Type= 0
Dn Type= 3
Dn Slope=0.002
Boundary for River Rch & Prof#=WFSJR 058,Reach-1         , 6
Up Type= 0
Dn Type= 3
Dn Slope=0.002
Boundary for River Rch & Prof#=WFSJR 058,Reach-1         , 7
Up Type= 0
Dn Type= 3
Dn Slope=0.002
DSS Import GetInterval= 0
DSS Import GetPeak= 0
DSS Import FillOption= 0

--- WFSJR 058.g01 (geometry) ---

Geom Title=Existing Conditions
Program Version=4.10

River Reach=WFSJR 058       ,Reach-1
Reach XY= 30
      3708368.23     10242236.84      3708489.45     10242470.31
      3709046.73     10242268.48      3709182.87     10242660.29
      3709586.66     10242923.97      3709913.06     10243034.55
      3709999.69     10242929.15      3710354.03     10242949.48
      3710399.17     10243102.25      3710640.71     10243245.71
      3711249.86     10243241.14      3711202.99     10243364.41
       3711482.5     10243480.73      3711528.35     10243684.32
      3711878.75     10243596.34      3711900.88      10243847.6
      3712142.72     10244150.79      3712471.04     10245027.73
      3712530.56     10244860.39      3712661.47     10244890.86
      3712986.21      10245367.7      3712868.13     10245608.14
      3712943.93     10245965.07      3713320.72     10246258.82
      3713374.17     10246472.53      3713569.45     10246427.89
      3713636.52     10246725.25      3713760.38      10246835.6
      3713882.86     10246801.84      3714138.23     10247116.84

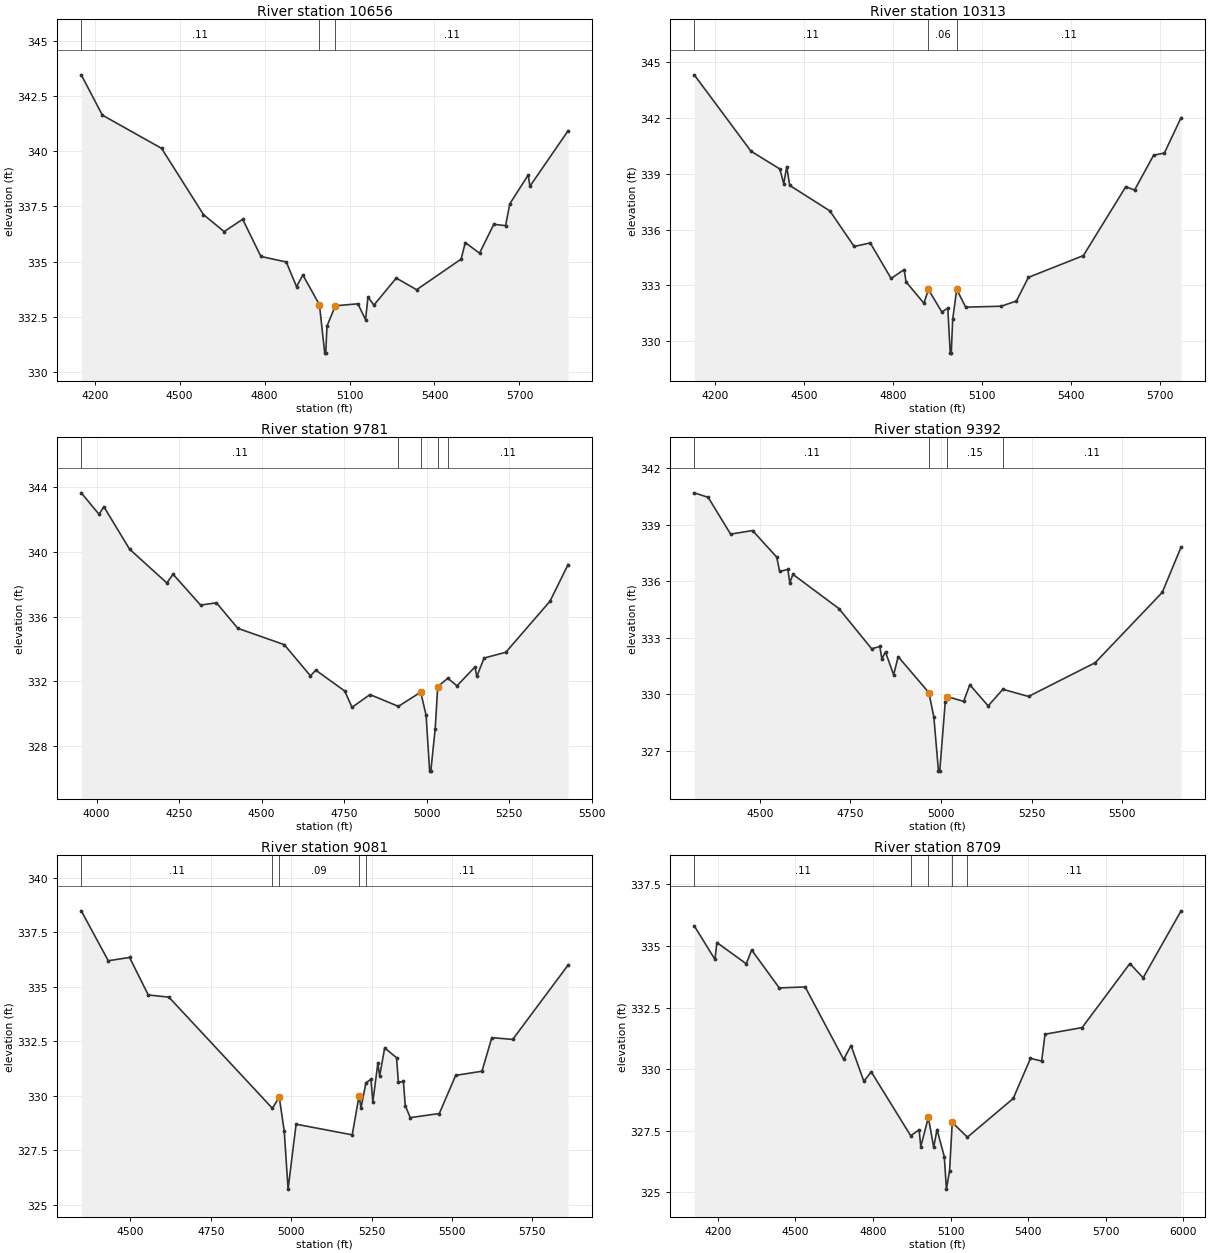
Type RM Length L Ch R = 1 ,10656   ,343,343,343
BEGIN DESCRIPTION:
WFSJR 058 18.0
END DESCRIPTION:
XS GIS Cut Line= 3
      3707991.33     10243135.12      3708423.47     10242406.07
      3708933.03     10241698.69
#Sta/Elev= 30
  4152.5  343.48    4227  341.65  4436.2  340.14  4584.2  337.13  4657.1  336.36
  4722.6  336.92  4786.9  335.23  4876.6  334.98  4912.8  333.86  4935.1  334.39
  4993.6  333.04  5012.4  330.84  5015.9  330.84  5020.3  332.07  5049.8  332.99
  5129.4  333.08  5156.6  332.36  5165.1  333.39    5186  333.02    5265  334.25
  5336.9  333.72    5494  335.11  5508.8  335.86  5559.1  335.38  5609.4  336.69
  5651.1  336.63  5665.9  337.62  5730.9  338.93    5737  338.42  5871.8  340.94
#Mann= 3 , 0 , 0
  4152.5     .11       0  4993.6     .06       0  5049.8     .11       0
Bank Sta=4993.6,5049.8
XS Rating Curve= 0 ,0
Exp/Cntr=0.3,0.1

Type RM Length L Ch R = 1 ,10313   ,532,532,532
BEGIN DESCRIPTION:
WFSJR 058 17.0
END DESCRIPTION:
XS GIS Cut Line= 3
      3708617.85     10243311.08      3708755.21     10242175.95
      3709040.82     10241764.84
#Sta/Elev= 30
  4128.7  344.31  4320.1  340.21  4417.9  339.25  4430.9  338.46    4441  339.38
    4451  338.37  4586.8     337  4668.7  335.09    4723  335.28  4793.5  333.37
  4837.6  333.85  4843.9  333.19  4904.3  332.04  4919.5  332.78  4964.8  331.57
  4984.9  331.78  4993.2  329.36  4996.7  329.36  5001.4  331.17  5015.1  332.78
  5045.3  331.83  5165.2  331.88  5216.6  332.16  5257.2  333.43  5442.8   334.6
    5586   338.3  5615.7  338.12  5679.9  339.99  5716.4  340.11  5772.7  342.01
#Mann= 3 , 0 , 0
  4128.7     .11       0  4919.5     .06       0  5015.1     .11       0
Bank Sta=4919.5,5015.1
XS Rating Curve= 0 ,0
Exp/Cntr=0.3,0.1

Type RM Length L Ch R = 1 ,9781    ,389,389,389
BEGIN DESCRIPTION:
WFSJR 058 16.0
END DESCRIPTION:
XS GIS Cut Line= 3
      3708667.85     10243311.07      3708894.09     10242748.86
      3709303.39     10241982.76
#Sta/Elev= 30
  3953.8  343.66  4007.7  342.33  4022.3   342.8  4100.2  340.17  4213.1  338.08
  4231.9  338.62  4315.2  336.71  4363.4  336.85  4428.1  335.27  4568.7  334.26
    4648  332.33  4664.2  332.68  4751.9  331.39  4773.9  330.38  4828.4  331.17
  4914.3  330.44    4982  331.32  4998.3  329.89  5009.1  326.43  5012.6  326.43
  5025.9  329.06  5033.5  331.66  5064.2  332.18  5091.8  331.71  5146.3  332.88
    5152  332.29  5173.9  333.43  5239.8  333.79  5373.6  336.95  5428.4  339.22
#Mann= 5 ,-1 , 0
  3953.8     .11       0  4914.3     .15       0    4982     .09       0
  5033.5     .15       0  5064.2     .11       0
Bank Sta=4982,5033.5
XS Rating Curve= 0 ,0
Exp/Cntr=0.3,0.1

Type RM Length L Ch R = 1 ,9392    ,311,311,311
BEGIN DESCRIPTION:
WFSJR 058 15.0
END DESCRIPTION:
XS GIS Cut Line= 3
      3708928.83     10243295.72       3709293.4     10242544.87
      3709411.83     10242050.64
#Sta/Elev= 30
  4319.2  340.69  4357.7  340.45  4419.4   338.5    4480  338.69  4546.7  337.28
  4554.8  336.52  4577.4  336.63  4582.9  335.91  4591.2  336.37  4718.3  334.55
  4808.6  332.42  4831.1  332.54  4836.7  331.89  4846.8  332.25  4869.1  331.04
  4881.8     332  4966.5  330.09  4980.2  328.79  4992.9  325.93  4996.4  325.93
  5011.6  329.61  5017.2  329.88  5062.3  329.63  5079.3  330.51    5130  329.39
  5170.5  330.27  5241.3  329.89  5425.1  331.68  5610.2  335.41  5662.1  337.81
#Mann= 4 ,-1 , 0
  4319.2     .11       0  4966.5     .07       0  5017.2     .15       0
  5170.5     .11       0
Bank Sta=4966.5,5017.2
XS Rating Curve= 0 ,0
Exp/Cntr=0.3,0.1

Type RM Length L Ch R = 1 ,9081    ,372,372,372
BEGIN DESCRIPTION:
Mapping XS fa518184
END DESCRIPTION:
XS GIS Cut Line= 3
      3709124.13     10243412.92      3709662.32     10242523.17
      3709757.81     10242058.74
#Sta/Elev= 30
  4347.2  338.48  4431.2  336.19  4497.4  336.34  4555.6  334.62  4619.6  334.52
  4941.6  329.42    4963  329.93  4978.5  328.37  4990.4  325.71  5015.3  328.69
  5189.9   328.2  5211.3     330  5217.1  329.44  5232.6  330.59  5248.1  330.75
    5254  329.71  5269.5  331.48  5275.3  330.91  5290.8  332.19  5327.7  331.74
  5333.5  330.61    5349  330.65  5354.9  329.54  5370.4  328.99  5460.7  329.18
  5511.7  330.93  5593.4  331.12    5624  332.66    5689  332.58  5861.2  335.99
#Mann= 5 ,-1 , 0
  4347.2     .11       0  4941.6     .15       0    4963     .09       0
  5211.3     .15       0  5232.6     .11       0
#XS Ineff= 1 ,-1
  5290.8    5640  332.19
Permanent Ineff=
       F
Bank Sta=4963,5211.3
XS Rating Curve= 0 ,0
Exp/Cntr=0.3,0.1

Type RM Length L Ch R = 1 ,8709    ,494,494,494
BEGIN DESCRIPTION:
WFSJR 058 14.0
END DESCRIPTION:
XS GIS Cut Line= 3
      3709215.26     10243651.66      3709782.85      10242965.1
      3710000.87     10241997.97
#Sta/Elev= 30
  4109.2  335.82  4189.1  334.46  4196.9  335.14  4310.3  334.28  4331.1  334.84
  4437.9   333.3  4538.1  333.34  4686.7   330.4  4715.4  330.96  4764.9  329.51
  4793.6  329.89    4946   327.3  4978.6  327.54    4985  326.86  5014.4  328.04
  5034.9  326.83  5047.9  327.55  5075.9  326.45  5084.2  325.13  5096.4  325.88
  5106.6  327.84  5165.3  327.24  5342.4  328.81  5409.2  330.44  5452.4  330.33
  5465.4  331.42  5608.9  331.69  5793.5  334.29  5844.7  333.71  5991.4  336.43
#Mann= 5 ,-1 , 0
  4109.2     .11       0    4946     .15       0  5014.4     .09       0
  5106.6     .15       0  5165.3     .11       0
Bank Sta=5014.4,5106.6
XS Rating Curve= 0 ,0
Exp/Cntr=0.3,0.1

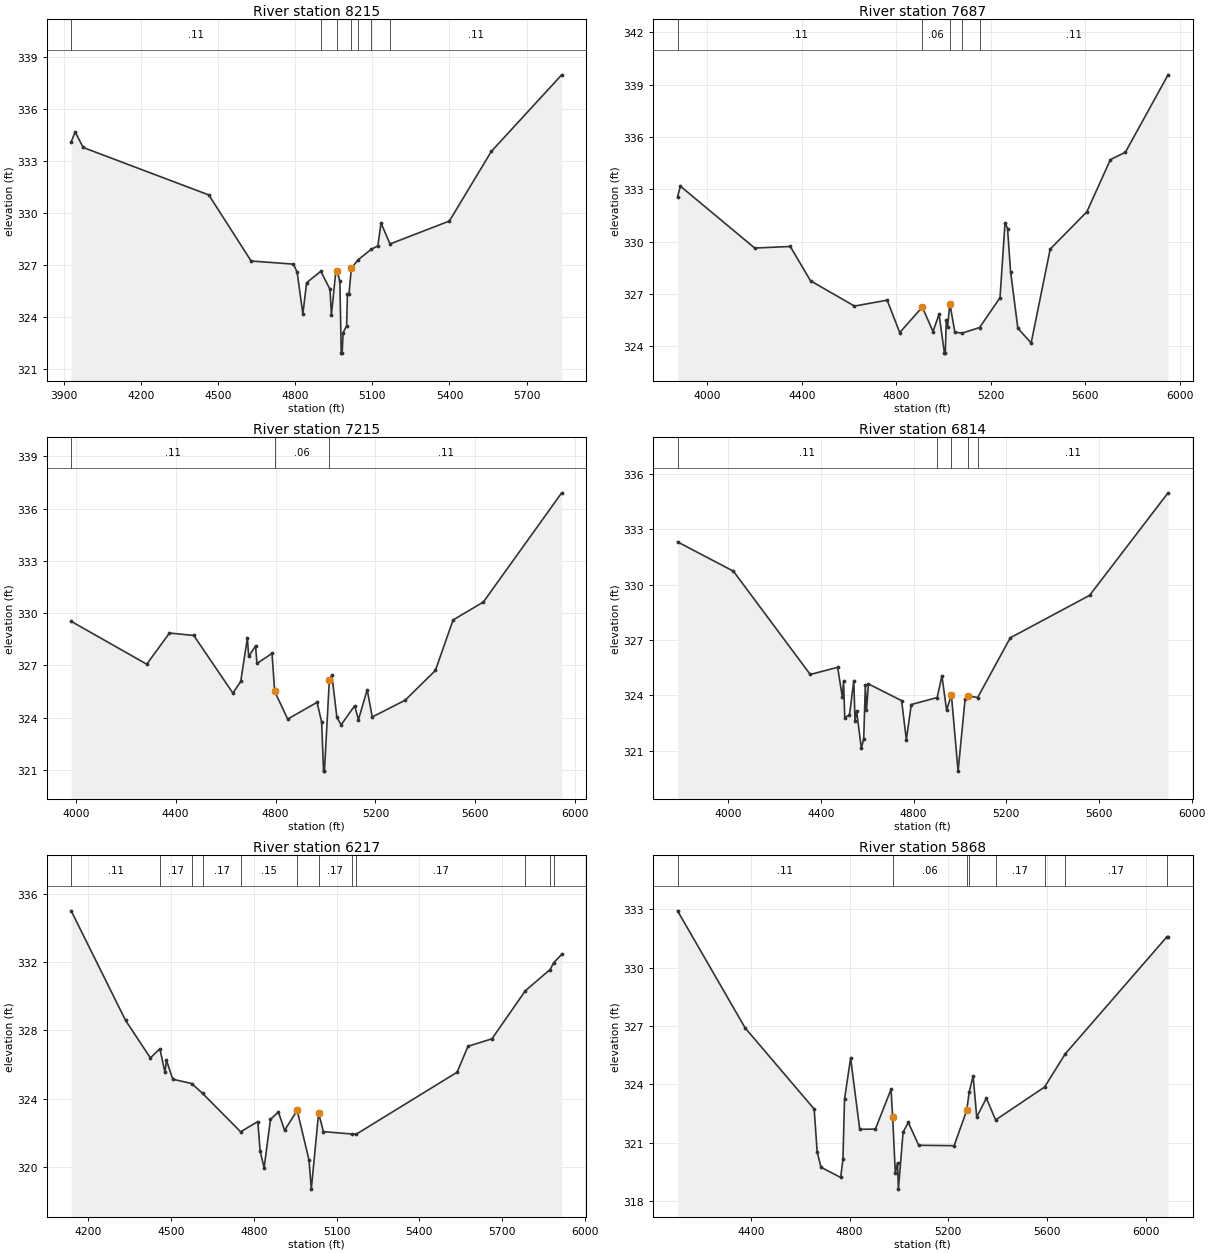
Type RM Length L Ch R = 1 ,8215    ,528,528,528
BEGIN DESCRIPTION:
WFSJR 058 13.0
END DESCRIPTION:
XS GIS Cut Line= 3
      3709701.37     10243925.12      3710160.46     10242957.28
      3710564.43     10242224.91
#Sta/Elev= 30
  3928.8   334.1  3944.3  334.66  3975.5  333.77    4464  331.04  4628.6  327.24
  4793.3  327.06  4807.7  326.58  4829.8  324.19  4844.3  325.99  4899.6  326.65
  4935.3  325.61  4940.8  324.14    4958  326.65  4963.5  326.65  4973.7  326.07
    4979  321.94  4982.5  321.94  4986.3  323.12    5000  323.51  5003.2  325.36
  5008.9  325.32  5018.5  326.83  5045.4  327.32  5095.6  327.91  5121.3  328.11
  5133.8  329.42  5168.8  328.22  5399.7  329.54  5562.5  333.54  5836.4  337.95
#Mann= 7 ,-1 , 0
  3928.8     .11       0  4899.6     .15       0  4963.5     .09       0
  5018.5     .15       0  5045.4     .11       0  5095.6     .15       0
  5168.8     .11       0
Bank Sta=4963.5,5018.5
XS Rating Curve= 0 ,0
Exp/Cntr=0.3,0.1

Type RM Length L Ch R = 1 ,7687    ,472,472,472
BEGIN DESCRIPTION:
WFSJR 058 12.0
END DESCRIPTION:
XS GIS Cut Line= 3
      3709901.03     10244050.96      3710410.55      10243353.2
      3710817.86     10242211.05
#Sta/Elev= 30
    3874  332.57  3886.2  333.18  4200.6  329.63  4351.2  329.72    4437  327.75
  4623.1   326.3  4761.5  326.64  4814.6  324.78  4910.1  326.24  4955.6  324.84
  4981.1  325.83  5003.9   323.6  5007.4   323.6  5011.9  325.49  5017.2  325.12
  5026.9  326.44  5048.1   324.8  5079.5  324.75  5152.8  325.07  5239.2  326.78
  5260.5  331.08  5271.1  330.75  5283.9  328.28  5314.7  325.03    5371  324.18
  5451.6  329.57  5606.9  331.71  5706.4   334.7  5770.1  335.13  5950.6  339.57
#Mann= 5 ,-1 , 0
    3874     .11       0  4910.1     .06       0  5026.9     .11       0
  5079.5     .15       0  5152.8     .11       0
#XS Ineff= 1 ,-1
  5260.5    5600  331.08
Permanent Ineff=
       F
Bank Sta=4910.1,5026.9
XS Rating Curve= 0 ,0
Exp/Cntr=0.3,0.1

Type RM Length L Ch R = 1 ,7215    ,401,401,401
BEGIN DESCRIPTION:
WFSJR 058 11.0
END DESCRIPTION:
XS GIS Cut Line= 3
      3710578.11     10244250.64      3710873.42      10243276.1
      3711012.16     10242340.83
#Sta/Elev= 30
  3981.7  329.53  4284.3  327.07  4375.2  328.86  4472.4  328.72  4629.1  325.41
  4660.4  326.08  4687.1  328.57  4692.3  327.52    4720  328.12  4725.3  327.11
  4785.8  327.69  4796.3  325.51  4848.5  323.92  4966.1  324.88  4984.4  323.75
  4992.1  320.93  4995.6  320.93  5015.2  326.14  5025.3  326.45  5045.5  324.01
  5062.5  323.59  5116.3  324.68  5131.9  323.89  5166.8   325.6  5187.1  324.04
  5318.5     325  5439.8  326.71  5510.6  329.61  5631.9  330.64  5945.5  336.91
#Mann= 3 , 0 , 0
  3981.7     .11       0  4796.3     .06       0  5015.2     .11       0
#XS Ineff= 2 ,-1
    4425  4687.1  328.57  5025.3    5450  326.45
Permanent Ineff=
       F       F
Bank Sta=4796.3,5015.2
XS Rating Curve= 0 ,0
Exp/Cntr=0.3,0.1

Type RM Length L Ch R = 1 ,6814    ,597,597,597
BEGIN DESCRIPTION:
WFSJR 058 10.0
END DESCRIPTION:
XS GIS Cut Line= 3
      3710903.65     10244406.83      3711184.07     10243090.58
      3711272.42     10242324.75
#Sta/Elev= 30
  3781.4  332.32  4022.6  330.73  4354.1  325.13  4472.3  325.52  4492.6   323.9
  4497.7  324.75    4503  322.79  4523.4  322.94  4542.1   324.8  4547.2  322.62
  4554.1  323.15  4574.6  321.13  4584.8  321.64  4591.7  324.54  4596.8  323.19
  4605.2  324.62  4748.4  323.71  4768.8  321.59  4789.9   323.5  4901.8  323.88
  4922.2  325.06  4942.6  323.19  4963.1  324.04    4992  319.89  5022.4  323.81
  5034.7  323.97  5076.5  323.88  5217.3  327.12  5559.5  329.42  5898.1  334.98
#Mann= 5 ,-1 , 0
  3781.4     .11       0  4901.8     .15       0  4963.1     .09       0
  5034.7     .15       0  5076.5     .11       0
Bank Sta=4963.1,5034.7
XS Rating Curve= 0 ,0
Exp/Cntr=0.3,0.1

Type RM Length L Ch R = 1 ,6217    ,349,349,349
BEGIN DESCRIPTION:
WFSJR 058 9.0
END DESCRIPTION:
XS GIS Cut Line= 3
      3711117.87     10244261.03       3711482.5     10243480.73
      3711767.86     10242611.05
#Sta/Elev= 30
  4138.7     335  4335.6  328.58  4425.6  326.38  4459.9  326.92  4478.2  325.54
  4483.8  326.24  4506.6  325.13  4575.2  324.88  4614.6   324.3  4752.5  322.05
  4814.7  322.65    4823  320.93  4837.5  319.94  4860.4  322.78  4889.2  323.21
  4911.6  322.14  4957.3   323.3    5000   320.4  5008.4  318.69  5034.8  323.15
  5052.3  322.06  5155.3  321.92  5171.2  321.91  5536.4  325.54  5575.9  327.06
  5662.7   327.5  5783.8  330.32  5873.4  331.56  5885.9  331.95  5915.3  332.45
#Mann= 12 ,-1 , 0
  4138.7     .11       0  4459.9     .17       0  4575.2     .11       0
  4614.6     .17       0  4752.5     .15       0  4957.3     .09       0
  5034.8     .17       0  5155.3     .11       0  5171.2     .17       0
  5783.8     .11       0  5873.4     .17       0  5885.9     .11       0
Bank Sta=4957.3,5034.8
XS Rating Curve= 0 ,0
Exp/Cntr=0.3,0.1

Type RM Length L Ch R = 1 ,5868    ,528,528,528
BEGIN DESCRIPTION:
WFSJR 058 8.0
END DESCRIPTION:
XS GIS Cut Line= 4
      3711225.71     10244496.22      3711576.48     10243908.76
      3711680.55     10243595.22       3711851.9     10242638.21
#Sta/Elev= 30
  4103.1  332.91    4377   326.9  4656.5  322.74  4668.6  320.55  4684.2  319.75
  4763.9  319.23    4773  320.16  4779.5  323.25  4804.1  325.35  4841.1   321.7
  4904.4  321.71  4967.8  323.75  4974.5  322.32  4985.1  319.46  4994.2  319.99
  4997.6  318.63  5016.7  321.56  5037.8  322.05  5079.9  320.88  5223.5  320.86
  5274.3  322.67  5284.4   323.6  5300.3  324.44  5314.9  322.33  5354.1   323.3
  5391.4  322.18  5589.9  323.87  5673.5  325.57  6085.5  331.58  6089.9  331.58
#Mann= 8 ,-1 , 0
  4103.1     .11       0  4974.5     .06       0  5274.3     .09       0
  5284.4     .11       0  5391.4     .17       0  5589.9     .11       0
  5673.5     .17       0  6085.5     .11       0
#XS Ineff= 3 ,-1
    4470  4804.1  325.35    4819  4967.8  323.75  5300.3    5640  324.44
Permanent Ineff=
       F       F       F
Bank Sta=4974.5,5274.3
XS Rating Curve= 0 ,0
Exp/Cntr=0.3,0.1

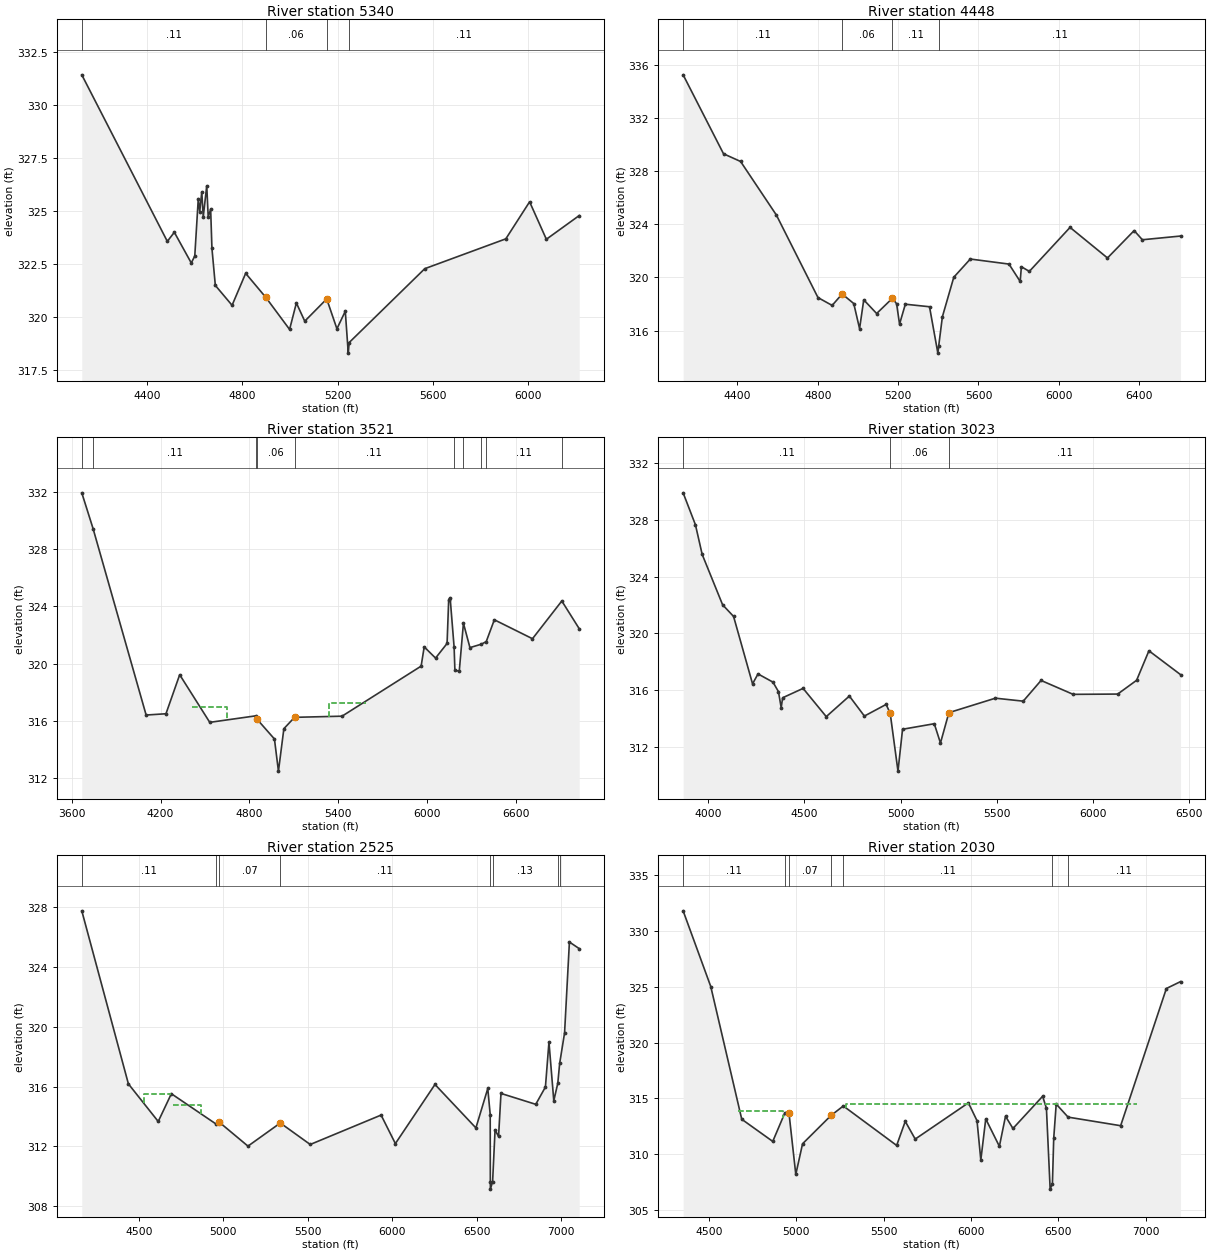
Type RM Length L Ch R = 1 ,5340    ,892,892,892
BEGIN DESCRIPTION:
Mapping XS 42cf9041
END DESCRIPTION:
XS GIS Cut Line= 3
      3711324.67      10244470.2      3711642.36     10244032.72
      3712813.56     10243022.88
#Sta/Elev= 30
  4125.9  331.44  4484.8  323.57  4514.2     324  4585.3  322.55    4600  322.88
  4614.7  325.59  4620.8  324.98  4629.4  325.91  4635.5  324.73  4650.2   326.2
  4656.4  324.72  4666.6  325.09    4672  323.24  4686.2  321.49  4756.5  320.55
  4813.5  322.06  4898.3  320.92  4997.8  319.41  5026.3  320.66  5061.5   319.8
  5153.6  320.85  5196.4  319.44  5231.5  320.27    5244  318.29  5247.8  318.79
    5565  322.28  5905.1  323.69  6004.9  325.44  6075.2  323.67    6213  324.79
#Mann= 4 ,-1 , 0
  4125.9     .11       0  4898.3     .06       0  5153.6     .11       0
  5247.8     .11       0
#XS Ineff= 1 ,-1
    4650  4813.5  322.06
Permanent Ineff=
       F
Bank Sta=4898.3,5153.6
XS Rating Curve= 0 ,0
Exp/Cntr=0.3,0.1

Type RM Length L Ch R = 1 ,4448    ,927,927,927
BEGIN DESCRIPTION:
Mapping XS 5c6ec076
END DESCRIPTION:
XS GIS Cut Line= 3
      3711595.52     10245110.81      3712657.98     10244277.51
      3712881.66     10243174.73
#Sta/Elev= 30
  4130.1  335.24  4331.1   329.3  4416.1  328.72  4594.2  324.69  4801.2  318.48
  4871.7  317.89  4921.5  318.75  4979.3  318.03  5008.2  316.14    5029  318.31
  5093.2  317.28  5171.8  318.43  5192.6  318.01  5207.1  316.48    5236  317.98
  5356.3  317.79  5397.8   314.3  5401.7   314.8  5420.4  317.04  5477.1  320.01
  5559.3  321.38  5751.8     321  5807.5  319.69  5813.5   320.8  5853.1  320.45
  6055.7  323.76    6242  321.46  6374.7  323.52  6415.5  322.83  6605.6  323.11
#Mann= 4 ,-1 , 0
  4130.1     .11       0  4921.5     .06       0  5171.8     .11       0
  5401.7     .11       0
Bank Sta=4921.5,5171.8
XS Rating Curve= 0 ,0
Exp/Cntr=0.3,0.1

Type RM Length L Ch R = 1 ,3521    ,498,498,498
BEGIN DESCRIPTION:
WFSJR 058 7.0
END DESCRIPTION:
XS GIS Cut Line= 3
      3712126.72     10246110.88      3712663.41     10244892.23
      3713142.03      10242924.7
#Sta/Elev= 30
  3668.4  331.91  3744.4  329.42  4102.6  316.42  4236.4  316.51    4329  319.23
    4532  315.91  4846.3  316.37  4851.7  316.12  4968.4  314.75  4995.4  312.51
  5032.1  315.47  5104.1  316.26  5424.5  316.34  5958.3  319.83  5978.9  321.17
  6055.7  320.39  6133.3  321.41  6144.3  324.47  6153.9   324.6  6180.9  321.14
  6186.1  319.54  6215.6  319.48  6243.7  322.82  6287.6  321.12  6364.9  321.36
  6397.6  321.54  6452.3  323.06  6709.6  321.74  6907.5  324.37  7024.9  322.44
#Mann= 10 ,-1 , 0
  3668.4     .17       0  3744.4     .11       0  4846.3     .11       0
  4851.7     .06       0  5104.1     .11       0  6180.9     .17       0
  6243.7     .11       0  6364.9     .17       0  6397.6     .11       0
  6907.5     .17       0
#XS Ineff= 3 ,-1
    3980    4329  319.23    4410  4648.7  317.01  5335.9    5585  317.24
Permanent Ineff=
       F       F       F
Bank Sta=4851.7,5104.1
XS Rating Curve= 0 ,0
Exp/Cntr=0.3,0.1

Type RM Length L Ch R = 1 ,3023    ,498,498,498
BEGIN DESCRIPTION:
WFSJR 058 6.0
END DESCRIPTION:
XS GIS Cut Line= 3
      3712178.84     10246142.07      3712923.06     10245290.82
      3713517.85     10243961.08
#Sta/Elev= 30
  3869.3  329.91  3933.3  327.66  3968.4  325.57  4074.7  322.02  4131.7   321.2
  4230.4  316.45  4258.8  317.15  4336.7  316.57  4365.2   315.9  4379.4  314.77
    4387  315.47  4493.3  316.13  4613.8  314.14    4734  315.59  4812.2  314.18
  4925.2     315  4946.5  314.37  4986.9   310.3  5010.7  313.25  5175.7  313.64
  5207.9  312.28  5251.7  314.42  5493.7  315.44  5638.4  315.23  5731.2  316.69
    5898  315.71  6129.8  315.73  6228.1   316.7  6292.2  318.78  6456.7   317.1
#Mann= 3 , 0 , 0
  3869.3     .11       0  4946.5     .06       0  5251.7     .11       0
#XS Ineff= 1 ,-1
    4200    4734  315.59
Permanent Ineff=
       F
Bank Sta=4946.5,5251.7
XS Rating Curve= 0 ,0
Exp/Cntr=0.3,0.1

Type RM Length L Ch R = 1 ,2525    ,495,495,495
BEGIN DESCRIPTION:
WFSJR 058 5.0
END DESCRIPTION:
XS GIS Cut Line= 3
      3712317.82      10246261.1      3712922.45      10245681.6
      3714548.58     10244340.03
#Sta/Elev= 30
  4162.5  327.77  4438.5  316.18  4615.2  313.66  4692.9  315.52  4957.6  313.49
    4976  313.62  5146.6  312.01  5338.1  313.56  5515.3  312.12  5934.9  314.09
  6019.5  312.18    6254  316.14  6496.4  313.23  6566.7  315.87  6581.1  314.12
  6581.8  309.63  6582.3  309.13  6595.3  309.63  6609.8  313.09  6630.6  312.66
  6644.9  315.54  6850.8  314.81  6908.1  315.97    6929  318.98  6957.6  315.05
  6981.3  316.22  6992.4  317.55  7021.5   319.6  7050.1  325.68  7108.1  325.24
#Mann= 8 ,-1 , 0
  4162.5     .11       0  4957.6     .15       0    4976     .07       0
  5338.1     .11       0  6581.8     .11       0  6595.3     .13       0
  6981.3     .15       0  6992.4     .11       0
#XS Ineff= 3 ,-1
    4529  4692.9  315.52    4705  4869.7  314.76    6254    7010  316.14
Permanent Ineff=
       F       F       F
Bank Sta=4976,5338.1
XS Rating Curve= 0 ,0
Exp/Cntr=0.3,0.1

Type RM Length L Ch R = 1 ,2030    ,448,448,448
BEGIN DESCRIPTION:
WFSJR 058 4.0
END DESCRIPTION:
XS GIS Cut Line= 3
      3712585.06     10246459.81      3713087.81     10246050.97
      3714730.92     10244589.99
#Sta/Elev= 30
    4352  331.82  4510.1  325.03  4687.5  313.12  4864.9  311.13  4934.5   313.7
  4957.6   313.7  4996.8  308.17  5035.5  310.92  5198.5  313.46  5268.8  314.31
    5574  310.77  5623.3  312.93  5680.2  311.34  5984.6  314.59  6033.9  312.99
  6055.7  309.46  6083.9  313.15  6161.9  310.69    6197  313.39  6239.6  312.29
  6409.4  315.18  6431.1  314.11  6452.5  306.85  6465.5  307.35  6472.9  311.41
  6487.1  314.48  6555.2  313.31  6855.9  312.54  7117.6  324.85  7198.7  325.47
#Mann= 7 ,-1 , 0
    4352     .11       0  4934.5     .12       0  4957.6     .07       0
  5198.5     .12       0  5268.8     .11       0  6465.5     .11       0
  6555.2     .11       0
#XS Ineff= 2 ,-1
 4663.62  4922.4  313.82    5283    6950  314.45
Permanent Ineff=
       F       F
Bank Sta=4957.6,5198.5
XS Rating Curve= 0 ,0
Exp/Cntr=0.3,0.1

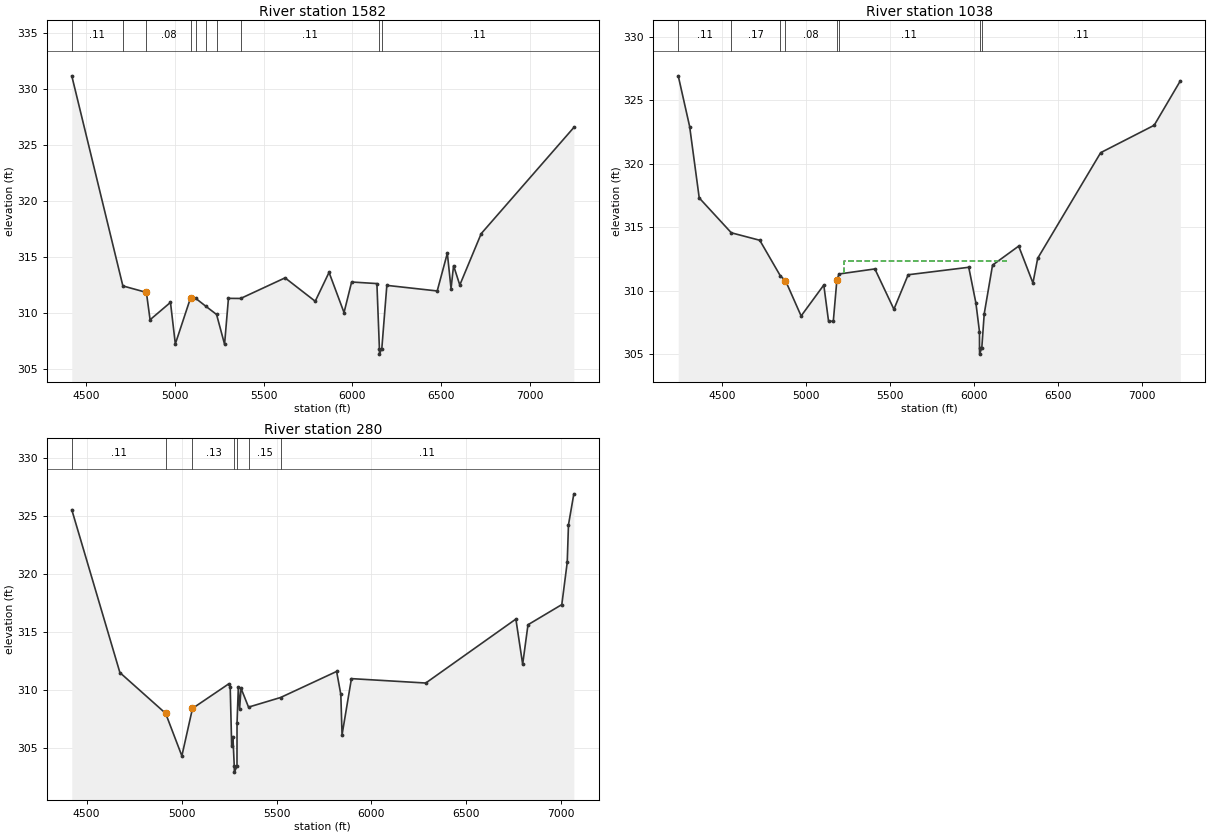
Type RM Length L Ch R = 1 ,1582    ,544,544,544
BEGIN DESCRIPTION:
WFSJR 058 3.0
END DESCRIPTION:
XS GIS Cut Line= 3
      3712866.28     10246621.29      3713465.27     10246131.68
      3715013.96      10244781.1
#Sta/Elev= 30
  4419.2  331.21  4707.1  312.45  4839.6  311.87  4860.4  309.43  4975.3  310.98
  5002.6  307.27  5088.7   311.4  5117.5  311.34  5174.8  310.63    5235   309.9
    5280  307.24  5301.8  311.34  5370.6  311.33  5620.8  313.17  5790.7  311.08
  5868.6  313.66    5953  310.07  5995.8   312.8  6138.2  312.66  6152.3  306.86
  6152.8  306.36  6165.9  306.86  6194.2   312.5    6478     312    6535  315.37
  6555.9  312.21  6570.1  314.26  6605.2  312.53  6725.8  317.12  7247.7   326.6
#Mann= 10 ,-1 , 0
  4419.2     .11       0  4707.1     .17       0  4839.6     .08       0
  5088.7     .13       0  5117.5     .17       0  5174.8     .11       0
    5235     .17       0  5370.6     .11       0  6152.3     .12       0
  6165.9     .11       0
#XS Ineff= 2 ,-1
  5620.8  5854.3  313.17  5868.6    6690  313.66
Permanent Ineff=
       F       F
Bank Sta=4839.6,5088.7
XS Rating Curve= 0 ,0
Exp/Cntr=0.3,0.1

Type RM Length L Ch R = 1 ,1038    ,758,758,758
BEGIN DESCRIPTION:
WFSJR 058 2.0
END DESCRIPTION:
XS GIS Cut Line= 3
      3712975.68     10246923.35      3713606.93      10246500.3
      3715167.86     10244911.06
#Sta/Elev= 30
  4240.1  326.94    4308  322.94    4365  317.31  4555.9  314.56  4725.2  313.97
  4848.3  311.15  4878.3  310.79  4971.3     308  5106.2  310.44  5134.5  307.59
  5162.8  307.58  5183.9  310.81  5196.7  311.31  5410.2  311.71  5523.4  308.53
  5608.2  311.25  5968.8  311.84  6011.3  309.02  6032.6  306.76  6032.8  305.49
  6033.3  304.99  6046.4  305.49  6060.8  308.17  6110.3  312.01  6265.9  313.51
  6350.7   310.6    6379  312.55  6753.8  320.88  7072.1  323.04  7227.6  326.54
#Mann= 8 ,-1 , 0
  4240.1     .11       0  4555.9     .17       0  4848.3     .13       0
  4878.3     .08       0  5183.9     .13       0  5196.7     .11       0
  6032.8     .12       0  6046.4     .11       0
#XS Ineff= 2 ,-1
  5226.4    6196  312.33  6265.9    6470  313.51
Permanent Ineff=
       F       F
Bank Sta=4878.3,5183.9
XS Rating Curve= 0 ,0
Exp/Cntr=0.3,0.1

Type RM Length L Ch R = 1 ,280     ,0,0,0
BEGIN DESCRIPTION:
WFSJR 058 1.0
END DESCRIPTION:
XS GIS Cut Line= 3
      3713574.64     10247355.65      3714048.61     10246819.18
      3715291.58     10245345.01
#Sta/Elev= 30
  4421.7  325.53  4675.2  311.47  4916.1  307.95  5001.5  304.28  5057.5  308.38
  5249.5  310.51    5256  310.27  5263.8  305.16  5270.3  305.95  5277.5  303.38
    5278  302.88  5291.8  303.38    5292  307.09  5298.9  310.23  5305.5  308.33
  5313.2  310.11  5352.6  308.49  5521.3  309.32  5816.5  311.57  5838.6  309.59
  5845.1   306.1  5894.5  310.95  6285.9  310.57  6760.5  316.09  6796.3  312.19
  6824.3   315.6  7002.4  317.34    7031  320.99  7037.5  324.22  7065.8   326.9
#Mann= 7 ,-1 , 0
  4421.7     .11       0  4916.1     .08       0  5057.5     .13       0
  5277.5     .11       0  5291.8     .11       0  5352.6     .15       0
  5521.3     .11       0
#XS Ineff= 1 ,-1
  5249.5    6000  310.51
Permanent Ineff=
       T
Bank Sta=4916.1,5057.5
XS Rating Curve= 0 ,0
Exp/Cntr=0.3,0.1

Chan Stop Cuts=-1
Use User Specified Reach Order=0
Composite Channel Slope=5