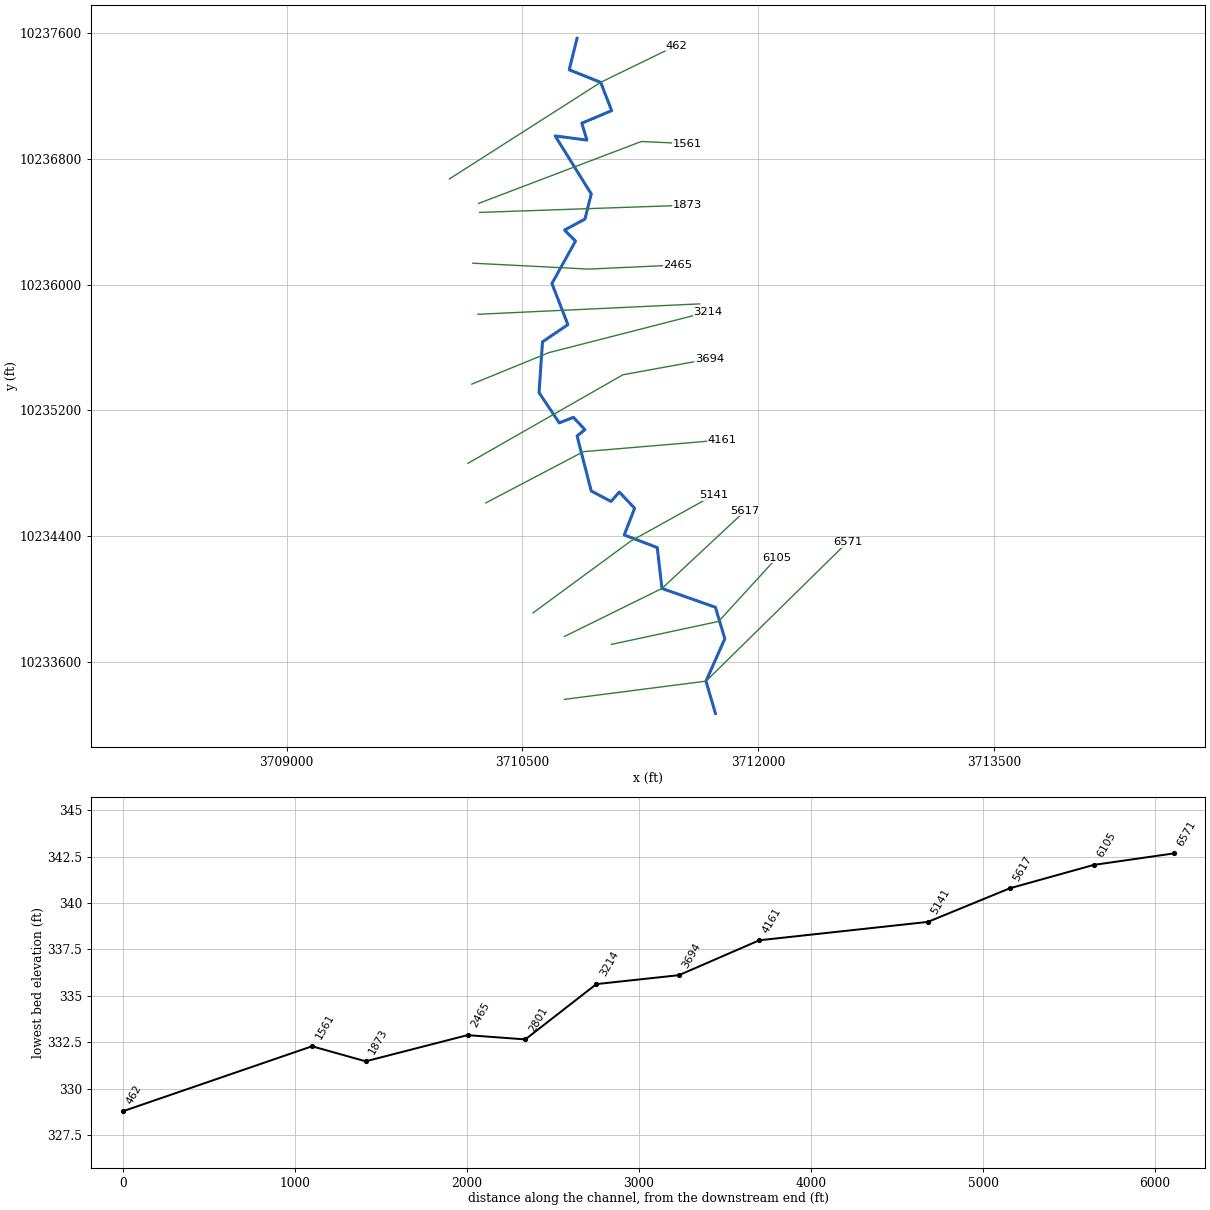
--- WFSJR 059.prj (project) ---

Proj Title=WFSJR 059 Base Level Engineering
Current Plan=p01
Default Exp/Contr=0.3,0.1
English Units
Geom File=g01
Flow File=f01
Plan File=p01
Y Axis Title=Elevation
X Axis Title(PF)=Main Channel Distance
X Axis Title(XS)=Station
BEGIN DESCRIPTION:
WFSJR 059
END DESCRIPTION:
DSS File=dss
DSS Export Rating Curves= 0
DSS Export Rating Curve Sorted= 0
DSS Export Volume Flow Curves= 0
DXF OffsetX= 0
DXF OffsetY= 0
DXF ScaleX= 1
DXF ScaleY= 10

--- WFSJR 059.p01 (plan) ---

Plan Title=Multiple Run
Program Version=4.10
Short Identifier=Multiple Run
Geom File=g01
Flow File=f01
Subcritical Flow
K Sum by GR= 0
Std Step Tol= 0.01
Critical Tol= 0.01
Num of Std Step Trials= 20
Max Error Tol= 0.3
Flow Tol Ratio= 0.001
Split Flow NTrial= 30
Split Flow Tol= 0.02
Split Flow Ratio= 0.02
Log Output Level= 0
Friction Slope Method= 1
Unsteady Friction Slope Method= 2
Unsteady Bridges Friction Slope Method= 1
Parabolic Critical Depth
Global Vel Dist= 1 , 1 , 1
Global Log Level= 0
CheckData=True
Encroach Param=-1 ,0,0, 0
BEGIN DESCRIPTION:
Multiple Run
END DESCRIPTION:
Computation Interval=1HOUR
Output Interval=1HOUR
Run HTab= 0
Run UNet= 0
Run PostProcess= 0
Run WQNet= 0
UNET Theta= 1
UNET Theta Warmup= 1
UNET ZTol= 0.02
UNET ZSATol= 0.05
UNET MxIter= 20
UNET MaxInSteps= 0
UNET DtIC= 0
UNET DtMin= 0
UNET MaxCRTS= 20
UNET WFStab= 2
UNET SFStab= 1
UNET WFX= 1
UNET SFX= 1
UNET DSS MLevel= 4
UNET DZMax Abort= 100
UNET Convert EG Bridges= 0
UNET Use Existing IB Tables=-1
UNET Froude Reduction=False
UNET Froude Limit= 1
UNET Froude Power= 10
UNET Time Slicing=0,0, 5
UNET Junction Losses=0
Instantaneous Interval=1HOUR
DSS File=dss
Write IC File= 0
Write IC File at Sim End=0
Echo Input=False
Echo Parameters=False
Echo Output=False
Write Detailed= 0
WQ AD Non Conservative
WQ ULTIMATE=-1
WQ Max Comp Step=1HOUR
WQ Output Interval=15MIN
WQ Output Selected Increments= 0
WQ Output face flow=0
WQ Output face velocity=0
WQ Output face area=0
WQ Output face dispersion=0
WQ Output cell volume=0
WQ Output cell surface area=0
WQ Output cell continuity=0
WQ Output cumulative cell continuity=0
WQ Output face conc=0
WQ Output face dconc_dx=0
WQ Output face courant=0
WQ Output face peclet=0
WQ Output face adv mass=0
WQ Output face disp mass=0
WQ Output cell mass=0
WQ Output cell source sink temp=0
WQ Output cell source sink nsm=0
WQ Output MaxMinRange=-1
WQ Daily Max Min Mean=-1
WQ Daily Range=0
WQ Daily Time=0
WQ Create Restart=0
WQ Fixed Restart=0
WQ System Summary=0
WQ Use Fixed Temperature=0
Sorting and Armoring Iterations= 10
XS Update Threshold= 0.02
Hydraulics Update Threshold= 0.02
Energy Slope Method= 1
Volume Change Method= 0
XS Weighting Method= 0
Number of US Weighted Cross Sections= 1
Number of DS Weighted Cross Sections= 1
Upstream XS Weight=0.25
Main XS Weight=0.5
Downstream XS Weight=0.25
Number of DS XS's Weighted with US Boundary= 1
Upstream Boundary Weight= 1
Weight of XSs Associated with US Boundary= 0
Number of US XS's Weighted with DS Boundary= 1
Downstream Boundary Weight= 0.5
Weight of XSs Associated with DS Boundary= 0.5
Sediment Output Level= 4
Mass or Volume Output= 0
Output Increment Type= 1
Profile and TS Output Increment= 10
XS Output Flag= 0
XS Output Increment= 10
Disregard all LS=0
Disregard all Conn=0
Disregard all Breaches=0
Disregard all Pumps=0

--- WFSJR 059.f01 (steady flow) ---

Flow Title=Multiple
Program Version=4.10
Number of Profiles= 7
Profile Names=10-year,25-year,50-year,1pct_min,100-year,1pct_plu,500-year
River Rch & RM=WFSJR 059,Reach-1         ,6571
     789    1082    1474     660    1993    6019    3770
Boundary for River Rch & Prof#=WFSJR 059,Reach-1         , 1
Up Type= 0
Dn Type= 3
Dn Slope=0.003
Boundary for River Rch & Prof#=WFSJR 059,Reach-1         , 2
Up Type= 0
Dn Type= 3
Dn Slope=0.003
Boundary for River Rch & Prof#=WFSJR 059,Reach-1         , 3
Up Type= 0
Dn Type= 3
Dn Slope=0.003
Boundary for River Rch & Prof#=WFSJR 059,Reach-1         , 4
Up Type= 0
Dn Type= 3
Dn Slope=0.003
Boundary for River Rch & Prof#=WFSJR 059,Reach-1         , 5
Up Type= 0
Dn Type= 3
Dn Slope=0.003
Boundary for River Rch & Prof#=WFSJR 059,Reach-1         , 6
Up Type= 0
Dn Type= 3
Dn Slope=0.003
Boundary for River Rch & Prof#=WFSJR 059,Reach-1         , 7
Up Type= 0
Dn Type= 3
Dn Slope=0.003
DSS Import GetInterval= 0
DSS Import GetPeak= 0
DSS Import FillOption= 0

--- WFSJR 059.g01 (geometry) ---

Geom Title=Existing Conditions
Program Version=4.10

River Reach=WFSJR 059       ,Reach-1
Reach XY= 30
      3711728.23     10233271.84      3711668.23     10233476.84
      3711788.23     10233746.84      3711728.23     10233946.84
      3711388.23     10234066.84      3711358.23     10234326.84
      3711148.23     10234406.84      3711214.23     10234577.19
      3711116.57     10234680.05      3711064.49     10234620.16
      3710938.23     10234686.84      3710848.23     10235036.84
      3710898.23     10235076.84      3710824.91     10235155.31
      3710735.06     10235120.16      3710606.16     10235312.86
      3710628.29     10235635.78      3710789.75     10235745.16
      3710688.23     10236006.84      3710838.23     10236276.84
      3710768.23     10236346.84      3710898.23     10236416.84
      3710938.23     10236576.84      3710709.02     10236945.68
      3710910.84     10236919.64      3710878.23     10237026.84
      3711068.23     10237106.84      3710998.23     10237286.84
      3710798.23     10237366.84      3710848.23     10237566.84

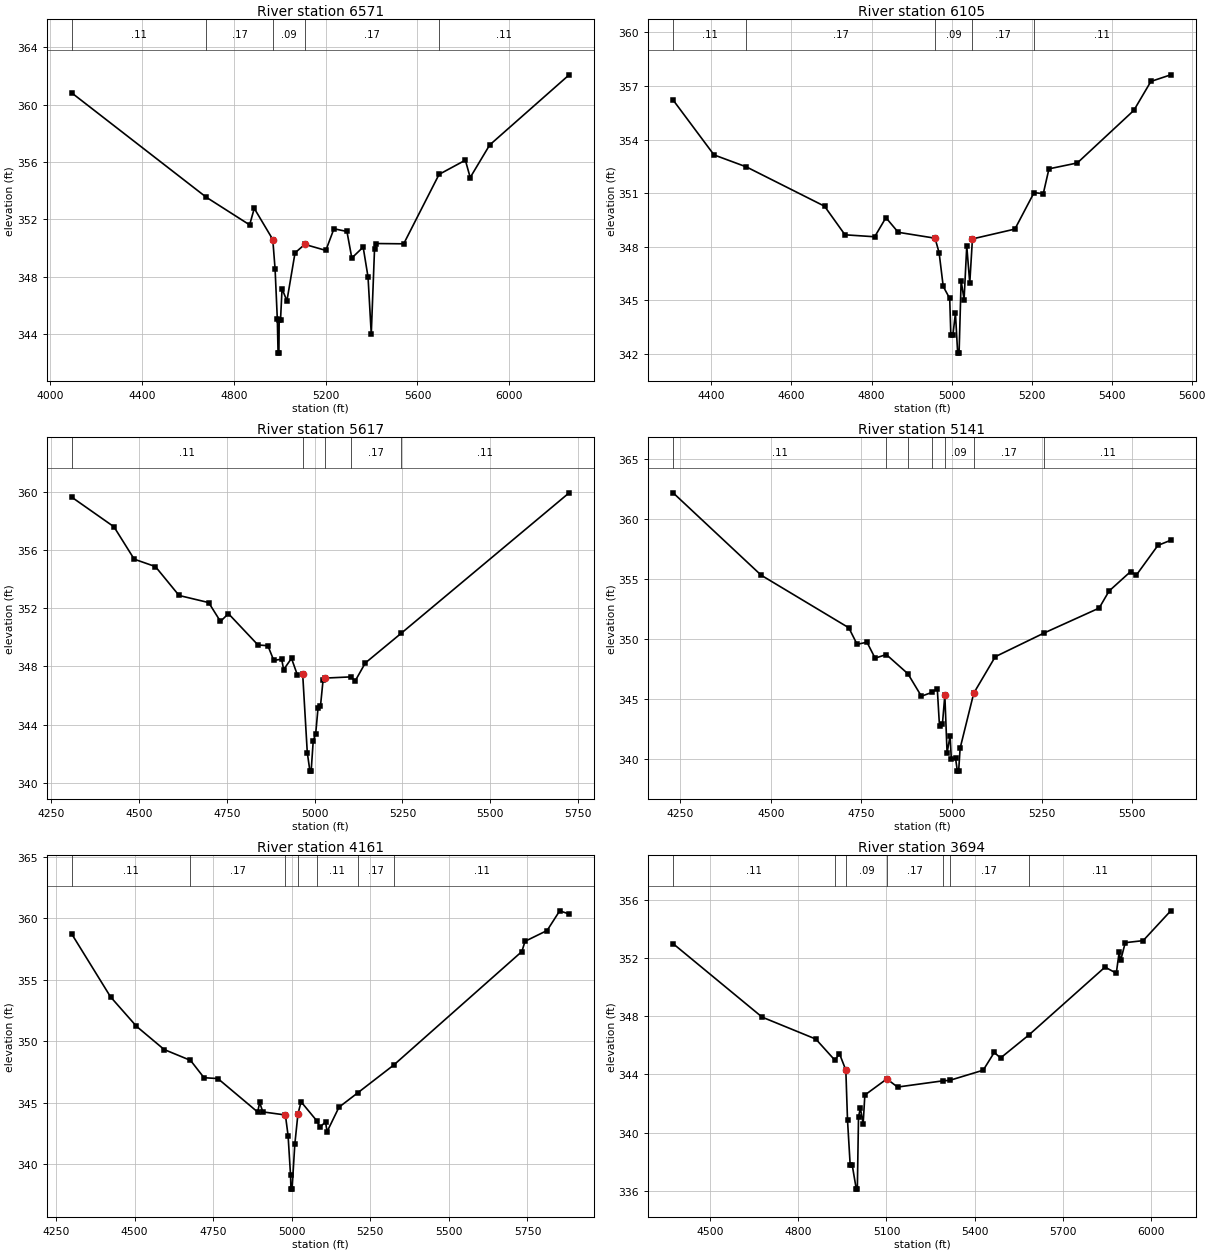
Type RM Length L Ch R = 1 ,6571    ,466,466,466
BEGIN DESCRIPTION:
WFSJR 059 12.0
END DESCRIPTION:
XS GIS Cut Line= 3
      3710767.84     10233361.07      3711668.23     10233476.84
      3712567.84     10234361.06
#Sta/Elev= 30
  4092.2  360.82  4679.3  353.54  4868.5  351.61  4888.7  352.76  4969.4  350.59
  4979.5  348.52  4989.2  345.04  4992.5  342.67    4996  342.67  4997.3  344.99
  5003.2  344.99  5009.8  347.16    5031  346.31  5066.4  349.66  5108.8  350.25
  5200.7  349.83  5236.1  351.34  5292.7  351.15  5313.9   349.3  5363.4  350.06
  5384.6  347.98  5398.7     344  5412.9   349.9    5420  350.31  5540.1  350.29
  5694.3  355.13  5808.9  356.12    5830  354.91  5914.9  357.18  6261.4  362.07
#Mann= 5 ,-1 , 0
  4092.2     .11       0  4679.3     .17       0  4969.4     .09       0
  5108.8     .17       0  5694.3     .11       0
Bank Sta=4969.4,5108.8
XS Rating Curve= 0 ,0
Exp/Cntr=0.3,0.1

Type RM Length L Ch R = 1 ,6105    ,488,488,488
BEGIN DESCRIPTION:
WFSJR 059 11.0
END DESCRIPTION:
XS GIS Cut Line= 3
      3711067.87     10233711.08      3711748.23     10233856.84
      3712117.82     10234261.04
#Sta/Elev= 30
  4304.2  356.21  4406.4  353.14  4487.2  352.47  4682.6  350.27  4733.7  348.67
  4807.9  348.56    4836  349.63  4866.7  348.81  4958.7  348.48  4968.9  347.67
  4979.2  345.78  4995.4  345.11  4998.2  343.08  5003.4  343.08  5009.7  344.28
  5015.3  342.05  5018.8  342.05  5023.9   346.1  5031.3  345.05    5038  348.04
  5045.5  345.97  5052.2  348.44  5158.3  348.99  5206.2  351.03  5229.2  350.97
  5243.4  352.36  5314.3  352.69  5455.5  355.63  5498.1  357.25  5547.7  357.62
#Mann= 5 ,-1 , 0
  4304.2     .11       0  4487.2     .17       0  4958.7     .09       0
  5052.2     .17       0  5206.2     .11       0
Bank Sta=4958.7,5052.2
XS Rating Curve= 0 ,0
Exp/Cntr=0.3,0.1

Type RM Length L Ch R = 1 ,5617    ,476,476,476
BEGIN DESCRIPTION:
WFSJR 059 10.0
END DESCRIPTION:
XS GIS Cut Line= 3
      3710767.89     10233761.09      3711388.23     10234066.84
      3711917.85     10234561.07
#Sta/Elev= 30
  4308.4  359.67  4429.1  357.62  4486.7  355.39    4547  354.88  4614.3  352.89
  4698.6   352.4  4732.2   351.1  4754.7  351.64  4838.9  349.48    4867  349.43
  4883.8  348.42  4906.3   348.5  4911.9  347.78  4934.3  348.56  4951.2   347.4
  4966.1  347.48  4979.2  342.07  4986.7  340.79  4990.2  340.79  4996.1  342.87
  5003.2  343.38  5009.9  345.17  5016.8  345.28  5024.1  347.06  5030.9   347.2
  5102.2  347.28  5115.9  347.02  5144.3  348.24  5246.2  350.28  5724.4  359.96
#Mann= 5 ,-1 , 0
  4308.4     .11       0  4966.1     .07       0  5030.9     .11       0
  5102.2     .17       0  5246.2     .11       0
Bank Sta=4966.1,5030.9
XS Rating Curve= 0 ,0
Exp/Cntr=0.3,0.1

Type RM Length L Ch R = 1 ,5141    ,980,980,980
BEGIN DESCRIPTION:
WFSJR 059 9.0
END DESCRIPTION:
XS GIS Cut Line= 3
      3710567.86     10233911.07      3711188.23     10234366.84
      3711717.89     10234661.09
#Sta/Elev= 30
  4230.2  362.16  4473.6   355.3  4715.9  350.92  4738.9  349.54  4766.1  349.72
  4788.6  348.39  4819.6  348.69  4879.3  347.09  4916.6  345.22    4946  345.54
  4960.5  345.86  4966.7   342.7  4974.7  342.89  4981.4   345.3  4987.6   340.5
    4996  341.91  4999.3  339.99    5011  340.05  5016.1  338.98  5019.6  338.98
  5023.6  340.88  5061.3  345.47  5120.8  348.51  5256.2  350.49    5408  352.56
  5435.4  353.98  5494.9   355.6  5510.9  355.31  5570.4  357.78  5605.9  358.21
#Mann= 7 ,-1 , 0
  4230.2     .11       0  4819.6     .17       0  4879.3     .11       0
    4946     .17       0  4981.4     .09       0  5061.3     .17       0
  5256.2     .11       0
Bank Sta=4981.4,5061.3
XS Rating Curve= 0 ,0
Exp/Cntr=0.3,0.1

Type RM Length L Ch R = 1 ,4161    ,467,467,467
BEGIN DESCRIPTION:
WFSJR 059 8.0
END DESCRIPTION:
XS GIS Cut Line= 3
      3710267.86     10234611.08      3710888.23     10234936.84
       3711767.8     10235011.07
#Sta/Elev= 30
  4299.3  358.76  4423.5  353.62  4505.9  351.23  4594.1  349.34  4677.8  348.46
  4720.8  347.05  4764.9  346.98  4891.5  344.26  4897.9  345.04  4907.9  344.27
  4979.7  344.02  4988.3  342.35  4996.1  339.13  4997.4  337.99    5001  337.99
  5009.7  341.63  5019.7  344.11  5029.7  345.09  5079.2  343.56  5089.9  343.03
  5107.4  343.46  5112.4  342.66  5150.2  344.65  5210.5  345.83  5324.5  348.08
  5732.2  357.31  5742.2  358.14  5812.5  359.02  5852.6  360.62  5882.7  360.36
#Mann= 7 ,-1 , 0
  4299.3     .11       0  4677.8     .17       0  4979.7     .09       0
  5019.7     .17       0  5079.2     .11       0  5210.5     .17       0
  5324.5     .11       0
Bank Sta=4979.7,5019.7
XS Rating Curve= 0 ,0
Exp/Cntr=0.3,0.1

Type RM Length L Ch R = 1 ,3694    ,480,480,480
BEGIN DESCRIPTION:
WFSJR 059 7.0
END DESCRIPTION:
XS GIS Cut Line= 3
      3710154.17     10234863.14      3711139.58     10235426.06
      3711690.26     10235526.87
#Sta/Elev= 30
  4373.4  352.99  4676.5  347.94  4859.4  346.43  4924.2  344.98    4940  345.42
  4961.6   344.3  4967.4  340.84  4976.5  337.74  4983.2  337.79  4997.2  336.11
  5000.8  336.11  5004.8  341.08  5011.1  341.68  5020.6  340.61  5026.4  342.58
  5101.3  343.69  5137.7  343.13  5292.9  343.56  5315.3  343.59  5429.5  344.29
    5467  345.51  5488.6  345.13  5585.5  346.72  5844.3  351.38  5882.7  350.96
  5892.4  352.39  5897.5  351.84  5913.2  353.06  5974.2   353.2  6068.1  355.25
#Mann= 7 ,-1 , 0
  4373.4     .11       0  4924.2     .17       0  4961.6     .09       0
  5101.3     .17       0  5292.9     .11       0  5315.3     .17       0
  5585.5     .11       0
Bank Sta=4961.6,5101.3
XS Rating Curve= 0 ,0
Exp/Cntr=0.3,0.1

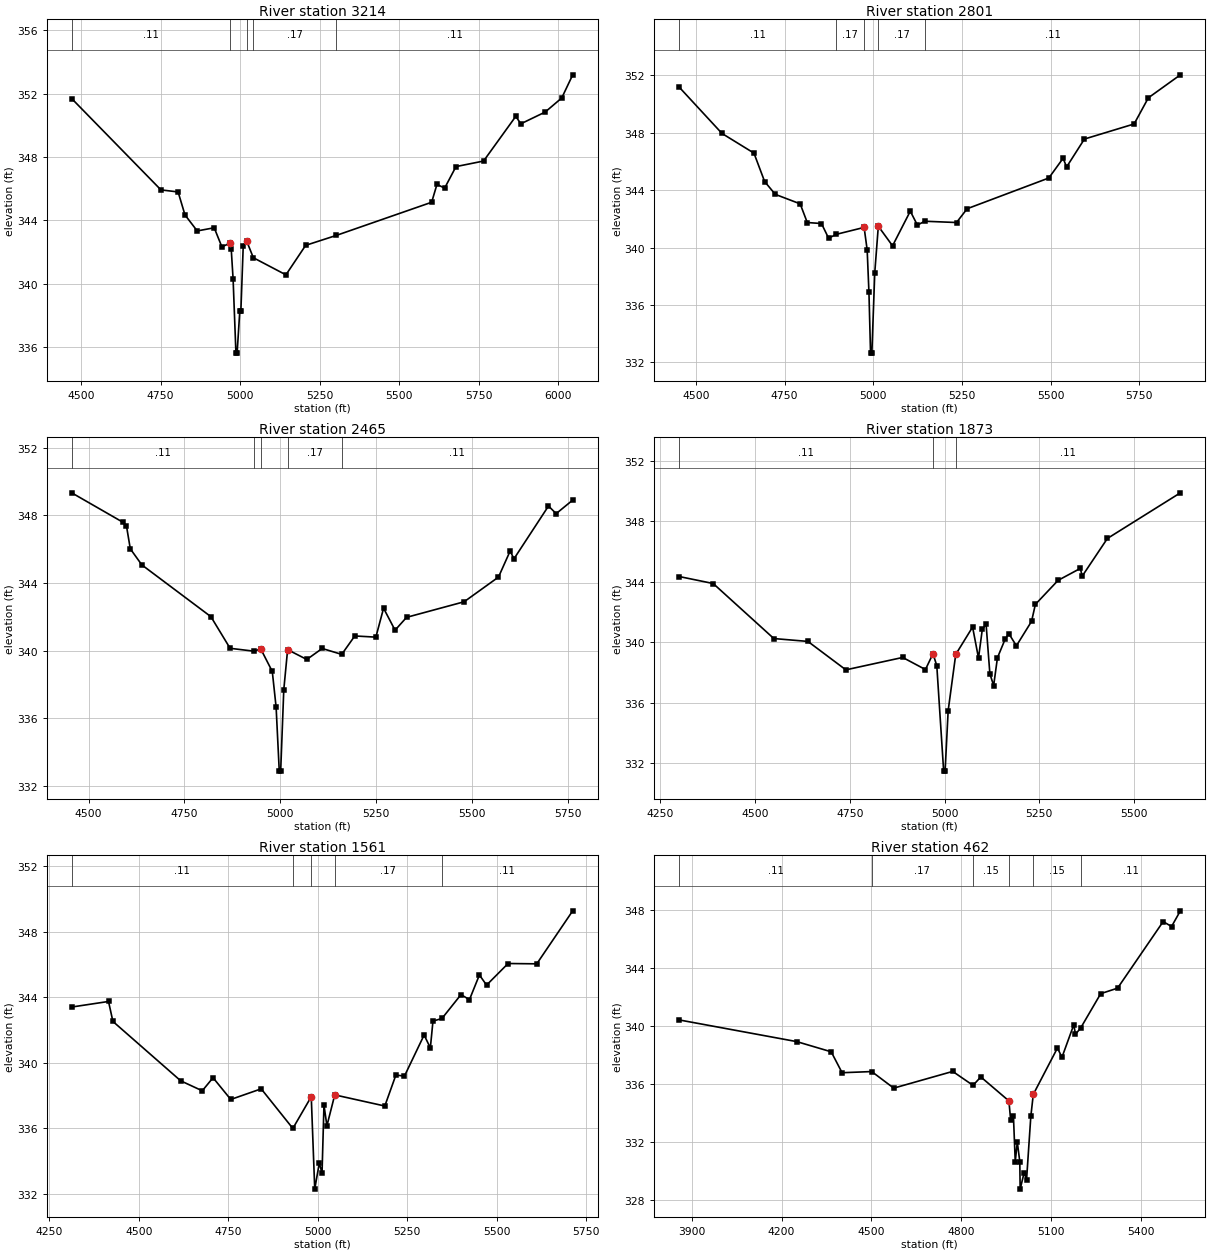
Type RM Length L Ch R = 1 ,3214    ,413,413,413
BEGIN DESCRIPTION:
WFSJR 059 6.0
END DESCRIPTION:
XS GIS Cut Line= 3
      3710178.21     10235366.49      3710668.23     10235566.84
       3711681.3     10235826.45
#Sta/Elev= 30
  4470.6  351.69  4751.1  345.93  4805.1   345.8  4826.7  344.35  4865.2  343.34
  4918.6  343.54  4942.6  342.34  4966.7  342.55  4972.1   342.2    4978  340.31
  4986.9  335.63  4990.6  335.63    4999  338.27  5002.4  338.27  5009.9  342.42
  5020.3  342.72  5041.6  341.65  5144.1  340.57  5206.1  342.43  5302.9  343.06
  5602.3  345.15    5619  346.28  5643.1  346.04  5678.8   347.4  5765.5  347.75
  5866.8  350.57  5882.7   350.1  5959.1  350.84  6011.3  351.73  6045.8  353.19
#Mann= 5 ,-1 , 0
  4470.6     .11       0  4966.7     .06       0  5020.3     .11       0
  5041.6     .17       0  5302.9     .11       0
Bank Sta=4966.7,5020.3
XS Rating Curve= 0 ,0
Exp/Cntr=0.3,0.1

Type RM Length L Ch R = 1 ,2801    ,336,336,336
BEGIN DESCRIPTION:
WFSJR 059 5.0
END DESCRIPTION:
XS GIS Cut Line= 2
      3710217.85     10235811.07        3711628.     10235877.31
#Sta/Elev= 30
  4453.7  351.15  4573.8  347.94  4663.9  346.57    4694  344.59    4724   343.7
  4794.1  343.04  4814.1  341.74  4854.1  341.67  4874.2  340.65  4896.1  340.92
  4974.3   341.4  4982.9  339.83  4987.9  336.87  4992.4  332.65  4996.1  332.65
  5004.3  338.26  5014.3  341.48  5054.4  340.12  5104.4  342.53  5124.4  341.56
  5145.1  341.83  5234.6  341.74  5264.6   342.7  5494.8  344.84  5534.9  346.21
  5544.9  345.61    5595  347.55  5735.1   348.6  5775.2  350.42  5865.4  352.02
#Mann= 5 ,-1 , 0
  4453.7     .11       0  4896.1     .17       0  4974.3     .09       0
  5014.3     .17       0  5145.1     .11       0
Bank Sta=4974.3,5014.3
XS Rating Curve= 0 ,0
Exp/Cntr=0.3,0.1

Type RM Length L Ch R = 1 ,2465    ,592,592,592
BEGIN DESCRIPTION:
WFSJR 059 4.0
END DESCRIPTION:
XS GIS Cut Line= 3
      3710185.14     10236136.25      3710922.91     10236098.54
      3711490.97      10236124.8
#Sta/Elev= 30
  4456.2  349.33  4589.1   347.6  4599.1  347.37  4609.1  346.02  4639.2  345.07
  4819.4  342.01  4869.5  340.14  4931.6  339.97  4949.6   340.1  4979.6  338.77
  4989.6  336.66  4997.8  332.88  5001.5  332.88  5009.6  337.69  5019.6  340.06
  5069.7  339.48  5109.8  340.13  5160.8  339.78  5194.9  340.87  5249.9   340.8
    5270  342.51    5300  341.21    5330  341.97  5480.2  342.89  5569.9  344.35
  5600.3  345.89  5610.3  345.43  5700.4  348.55  5720.4   348.1  5763.6   348.9
#Mann= 5 ,-1 , 0
  4456.2     .11       0  4931.6     .17       0  4949.6     .09       0
  5019.6     .17       0  5160.8     .11       0
#XS Ineff= 1 ,-1
    5270    5440  342.51
Permanent Ineff=
       F
Bank Sta=4949.6,5019.6
XS Rating Curve= 0 ,0
Exp/Cntr=0.3,0.1

Type RM Length L Ch R = 1 ,1873    ,312,312,312
BEGIN DESCRIPTION:
WFSJR 059 3.0
END DESCRIPTION:
XS GIS Cut Line= 2
      3710228.65     10236459.28      3711550.46     10236505.09
#Sta/Elev= 30
    4300  344.34  4389.3  343.88  4549.4  340.24  4639.4  340.05  4739.5  338.17
  4889.6  338.99  4949.6  338.19  4969.6  339.24  4979.6  338.44  4997.7  331.47
  5001.5  331.47  5009.6  335.47  5029.6  339.19  5074.1     341  5089.7  338.95
  5099.7  340.84  5109.7   341.2  5119.7  337.91  5129.7  337.13  5139.7  338.97
  5159.7  340.18  5169.7  340.57  5189.7  339.76  5229.8  341.38  5239.8   342.5
  5299.8  344.09  5358.5  344.88  5363.5  344.37  5429.9  346.86  5622.6  349.88
#Mann= 3 , 0 , 0
    4300     .11       0  4969.6     .06       0  5029.6     .11       0
#XS Ineff= 1 ,-1
  5074.1    5225     341
Permanent Ineff=
       F
Bank Sta=4969.6,5029.6
XS Rating Curve= 0 ,0
Exp/Cntr=0.3,0.1

Type RM Length L Ch R = 1 ,1561    ,1099,1099,1099
BEGIN DESCRIPTION:
WFSJR 059 2.0
END DESCRIPTION:
XS GIS Cut Line= 3
      3710221.73     10236516.54      3711257.25     10236910.59
      3711548.17     10236896.85
#Sta/Elev= 30
  4312.7  343.41  4415.5  343.75  4427.7  342.53  4617.1   338.9  4677.3  338.29
  4707.4  339.09  4756.9  337.76  4841.9  338.41  4930.3  335.99  4981.7  337.93
  4991.4  332.28    5004  333.86  5011.8  333.27  5017.2  337.42  5025.4  336.15
  5047.3  338.04  5187.1  337.36    5218  339.25    5242  339.19  5296.9   341.7
  5314.3  340.91  5321.6  342.55  5346.7  342.71  5399.9  344.17  5423.5  343.86
  5451.3  345.37  5471.3  344.75  5531.4  346.07  5611.5  346.05  5711.9  349.29
#Mann= 5 ,-1 , 0
  4312.7     .11       0  4930.3     .17       0  4981.7     .09       0
  5047.3     .17       0  5346.7     .11       0
Bank Sta=4981.7,5047.3
XS Rating Curve= 0 ,0
Exp/Cntr=0.3,0.1

Type RM Length L Ch R = 1 ,462     ,0,0,0
BEGIN DESCRIPTION:
WFSJR 059 1.0
END DESCRIPTION:
XS GIS Cut Line= 3
      3710036.15     10236672.31      3710998.23     10237286.84
       3711477.2     10237519.99
#Sta/Elev= 30
  3858.4  340.42  4250.8  338.93  4365.8  338.23  4402.2  336.79  4501.2  336.87
  4574.8  335.73  4771.9  336.88  4839.8  335.92  4865.8   336.5  4959.7  334.85
  4965.6  333.52  4974.9  333.78  4980.9  330.66  4987.7  332.02  4996.1  330.67
  4997.3  328.78  5010.7  329.92  5018.7  329.43  5032.9  333.78  5041.2   335.3
  5121.9  338.49    5137  337.85  5176.5  340.09  5182.1  339.44    5199  339.85
  5266.5  342.23  5322.9  342.61  5475.2  347.19  5503.3  346.85  5532.7  347.93
#Mann= 6 ,-1 , 0
  3858.4     .11       0  4501.2     .17       0  4839.8     .15       0
  4959.7     .07       0  5041.2     .15       0    5199     .11       0
Bank Sta=4959.7,5041.2
XS Rating Curve= 0 ,0
Exp/Cntr=0.3,0.1

Chan Stop Cuts=-1
Use User Specified Reach Order=0
Composite Channel Slope=5