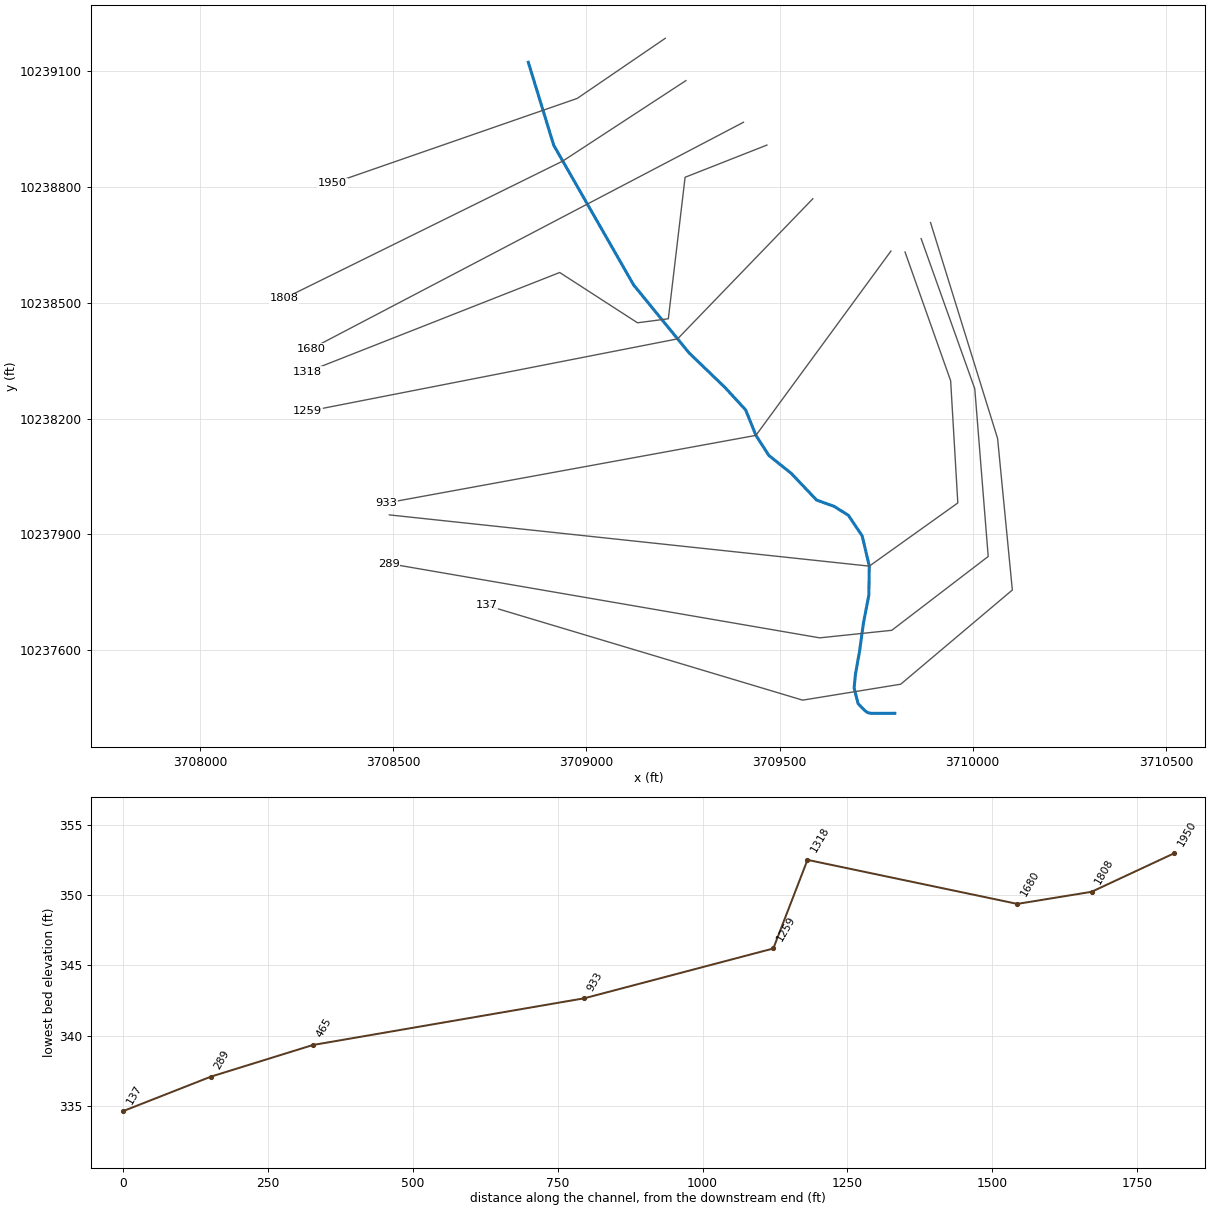
--- WFSJR 060.prj (project) ---

Proj Title=WFSJR 060 Base Level Engineering
Current Plan=p01
Default Exp/Contr=0.3,0.1
English Units
Geom File=g01
Flow File=f01
Plan File=p01
Y Axis Title=Elevation
X Axis Title(PF)=Main Channel Distance
X Axis Title(XS)=Station
BEGIN DESCRIPTION:
WFSJR 060
END DESCRIPTION:
DSS Export Rating Curves= 0
DSS Export Rating Curve Sorted= 0
DSS Export Volume Flow Curves= 0
DXF OffsetX= 0
DXF OffsetY= 0
DXF ScaleX= 1
DXF ScaleY= 10

--- WFSJR 060.p01 (plan) ---

Plan Title=Multiple Run
Program Version=4.10
Short Identifier=Multiple
Geom File=g01
Flow File=f01
Subcritical Flow
K Sum by GR= 0
Std Step Tol= 0.01
Critical Tol= 0.01
Num of Std Step Trials= 20
Max Error Tol= 0.3
Flow Tol Ratio= 0.001
Split Flow NTrial= 30
Split Flow Tol= 0.02
Split Flow Ratio= 0.02
Log Output Level= 0
Friction Slope Method= 1
Unsteady Friction Slope Method= 2
Unsteady Bridges Friction Slope Method= 1
Parabolic Critical Depth
Global Vel Dist= 1 , 1 , 1
Global Log Level= 0
CheckData=True
Encroach Param=-1 ,0,0, 0
BEGIN DESCRIPTION:
Multiple Run
END DESCRIPTION:
Computation Interval=1HOUR
Output Interval=1HOUR
Run HTab= 0
Run UNet= 0
Run PostProcess= 0
Run WQNet= 0
UNET Theta= 1
UNET Theta Warmup= 1
UNET ZTol= 0.02
UNET ZSATol= 0.05
UNET MxIter= 20
UNET MaxInSteps= 0
UNET DtIC= 0
UNET DtMin= 0
UNET MaxCRTS= 20
UNET WFStab= 2
UNET SFStab= 1
UNET WFX= 1
UNET SFX= 1
UNET DSS MLevel= 4
UNET DZMax Abort= 100
UNET Convert EG Bridges= 0
UNET Use Existing IB Tables=-1
UNET Froude Reduction=False
UNET Froude Limit= 1
UNET Froude Power= 10
UNET Time Slicing=0,0, 5
UNET Junction Losses=0
Instantaneous Interval=1HOUR
Write IC File= 0
Write IC File at Sim End=0
Echo Input=False
Echo Parameters=False
Echo Output=False
Write Detailed= 0
WQ AD Non Conservative
WQ ULTIMATE=-1
WQ Max Comp Step=1HOUR
WQ Output Interval=15MIN
WQ Output Selected Increments= 0
WQ Output face flow=0
WQ Output face velocity=0
WQ Output face area=0
WQ Output face dispersion=0
WQ Output cell volume=0
WQ Output cell surface area=0
WQ Output cell continuity=0
WQ Output cumulative cell continuity=0
WQ Output face conc=0
WQ Output face dconc_dx=0
WQ Output face courant=0
WQ Output face peclet=0
WQ Output face adv mass=0
WQ Output face disp mass=0
WQ Output cell mass=0
WQ Output cell source sink temp=0
WQ Output cell source sink nsm=0
WQ Output MaxMinRange=-1
WQ Daily Max Min Mean=-1
WQ Daily Range=0
WQ Daily Time=0
WQ Create Restart=0
WQ Fixed Restart=0
WQ System Summary=0
WQ Use Fixed Temperature=0
Sorting and Armoring Iterations= 10
XS Update Threshold= 0.02
Hydraulics Update Threshold= 0.02
Energy Slope Method= 1
Volume Change Method= 0
XS Weighting Method= 0
Number of US Weighted Cross Sections= 1
Number of DS Weighted Cross Sections= 1
Upstream XS Weight=0.25
Main XS Weight=0.5
Downstream XS Weight=0.25
Number of DS XS's Weighted with US Boundary= 1
Upstream Boundary Weight= 1
Weight of XSs Associated with US Boundary= 0
Number of US XS's Weighted with DS Boundary= 1
Downstream Boundary Weight= 0.5
Weight of XSs Associated with DS Boundary= 0.5
Sediment Output Level= 4
Mass or Volume Output= 0
Output Increment Type= 1
Profile and TS Output Increment= 10
XS Output Flag= 0
XS Output Increment= 10
Disregard all LS=0
Disregard all Conn=0
Disregard all Breaches=0
Disregard all Pumps=0

--- WFSJR 060.f01 (steady flow) ---

Flow Title=Multiple
Program Version=4.10
Number of Profiles= 7
Profile Names=10-year,25-year,50-year,1pct_min,100-year,1pct_plu,500-year
River Rch & RM=WFSJR 060,Reach-1         ,1950
     128     156     196      81     246     743     401
Boundary for River Rch & Prof#=WFSJR 060,Reach-1         , 1
Up Type= 0
Dn Type= 3
Dn Slope=0.02
Boundary for River Rch & Prof#=WFSJR 060,Reach-1         , 2
Up Type= 0
Dn Type= 3
Dn Slope=0.02
Boundary for River Rch & Prof#=WFSJR 060,Reach-1         , 3
Up Type= 0
Dn Type= 3
Dn Slope=0.02
Boundary for River Rch & Prof#=WFSJR 060,Reach-1         , 4
Up Type= 0
Dn Type= 3
Dn Slope=0.02
Boundary for River Rch & Prof#=WFSJR 060,Reach-1         , 5
Up Type= 0
Dn Type= 3
Dn Slope=0.02
Boundary for River Rch & Prof#=WFSJR 060,Reach-1         , 6
Up Type= 0
Dn Type= 3
Dn Slope=0.02
Boundary for River Rch & Prof#=WFSJR 060,Reach-1         , 7
Up Type= 0
Dn Type= 3
Dn Slope=0.02
DSS Import GetInterval= 0
DSS Import GetPeak= 0
DSS Import FillOption= 0

--- WFSJR 060.g01 (geometry) ---

Geom Title=Existing Conditions
Program Version=4.10

River Reach=WFSJR 060       ,Reach-1
Reach XY= 30
      3708849.38     10239122.41      3708915.24     10238907.48
      3709122.09     10238545.79      3709265.38     10238370.15
      3709358.98     10238280.02      3709412.13     10238222.24
      3709438.71     10238156.37      3709472.22     10238104.37
        3709530.     10238058.15      3709595.86     10237988.82
      3709640.93     10237972.64      3709677.91     10237949.53
      3709713.73     10237896.37      3709732.22      10237817.8
      3709731.06     10237742.69      3709717.19     10237671.04
      3709706.79     10237595.93      3709696.39     10237538.16
      3709692.93     10237502.33      3709703.23     10237461.84
      3709718.35     10237446.16      3709722.67     10237442.23
      3709725.72     10237440.02      3709728.08     10237438.74
      3709731.44     10237437.58      3709733.28      10237437.2
      3709737.15     10237436.78      3709741.13     10237436.62
      3709746.89     10237436.61      3709798.23     10237436.84

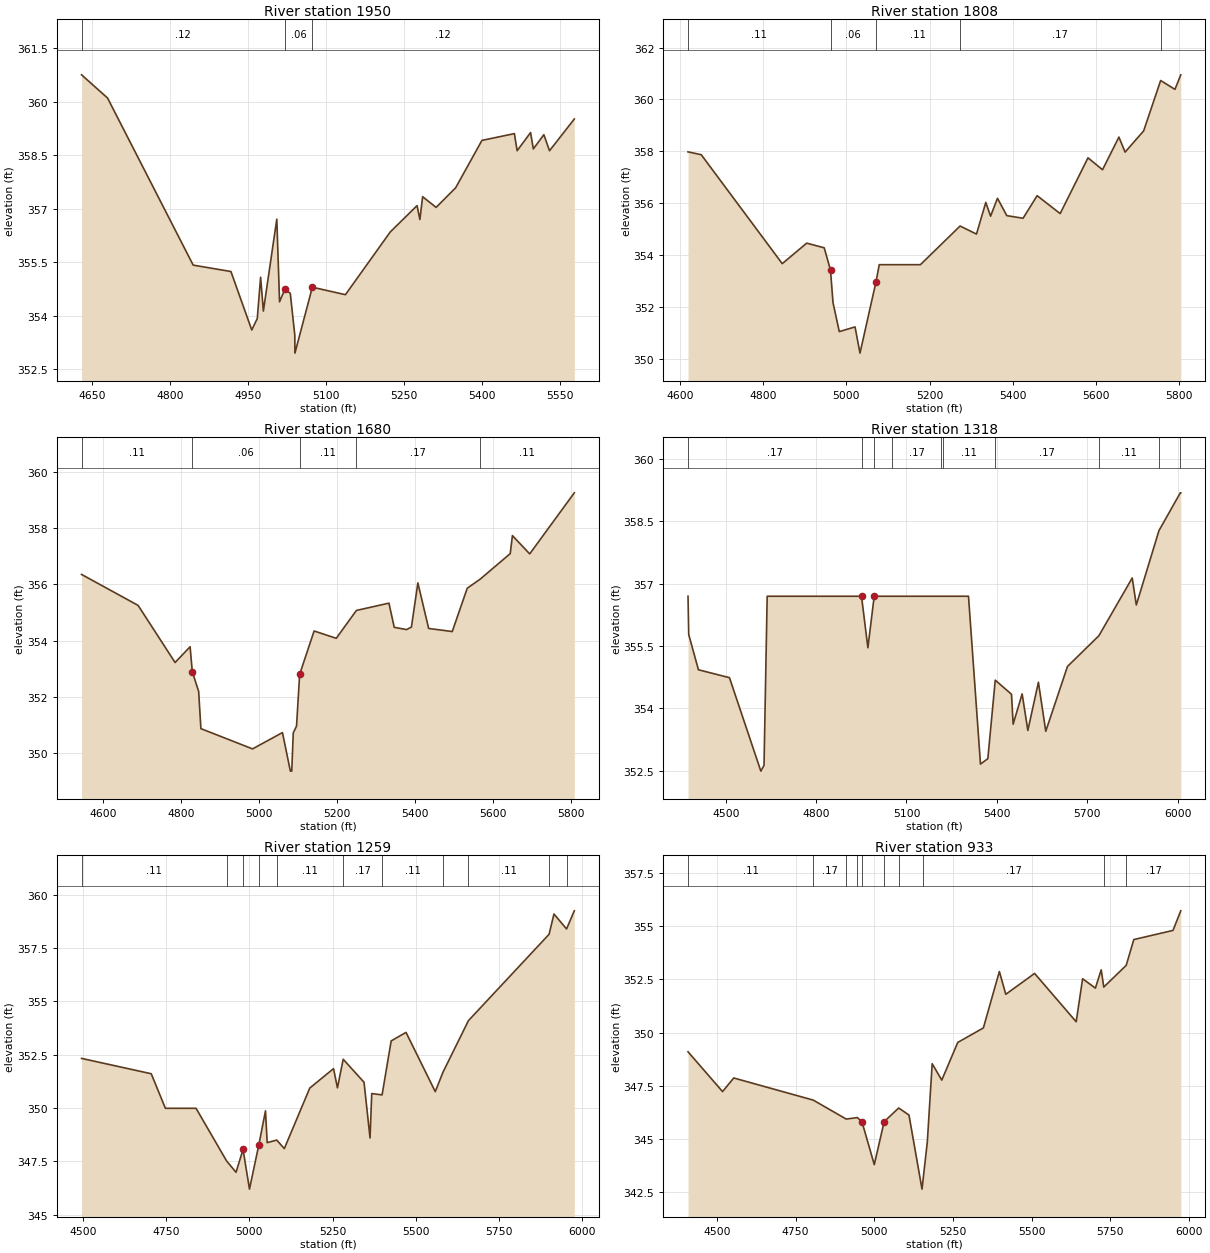
Type RM Length L Ch R = 1 ,1950    ,142,142,142
BEGIN DESCRIPTION:
WFSJR 060 5.0
END DESCRIPTION:
XS GIS Cut Line= 3
      3709203.89      10239184.3      3708976.05     10239028.75
       3708342.6     10238808.85
#Sta/Elev= 30
  4630.4  360.76  4680.3  360.11  4844.8  355.42  4917.3  355.24  4957.3   353.6
  4967.9  353.92  4974.3  355.08  4979.6  354.13  5005.4  356.71  5010.7  354.39
  5020.8  354.74  5031.3  354.63    5040  353.45  5040.2  352.95  5073.7   354.8
  5137.2  354.59  5223.3  356.35  5274.8  357.09  5280.2   356.7  5285.5  357.34
  5311.4  357.04  5348.9  357.59  5399.4  358.92  5461.7  359.11    5467  358.63
  5492.8  359.14  5498.1  358.68  5518.3  359.08  5529.2  358.63  5576.8  359.52
#Mann= 3 , 0 , 0
  4630.4     .12       0  5020.8     .06       0  5073.7     .12       0
Bank Sta=5020.8,5073.7
XS Rating Curve= 0 ,0
Exp/Cntr=0.3,0.1

Type RM Length L Ch R = 1 ,1808    ,128,128,128
BEGIN DESCRIPTION:
WFSJR 060 4.0
END DESCRIPTION:
XS GIS Cut Line= 3
      3709257.43     10239074.85      3708938.64     10238866.57
      3708217.84     10238511.07
#Sta/Elev= 30
  4619.2  357.98    4651  357.87  4845.7  353.67  4904.5  354.46  4946.6  354.28
  4961.7  353.42  4967.7  352.17  4982.8  351.05  5020.7  351.23  5032.6  350.22
  5071.1  352.97  5078.9  353.63  5177.8  353.63  5273.2  355.12  5312.6  354.81
    5335  356.03  5346.5   355.5  5363.1  356.19  5385.5  355.52  5424.6  355.42
  5458.4  356.29  5513.8   355.6  5580.7  357.75  5615.6  357.29    5655  358.55
  5669.9  357.97  5714.5  358.79  5755.3  360.73  5789.7  360.39  5803.7  360.95
#Mann= 5 ,-1 , 0
  4619.2     .11       0  4961.7     .06       0  5071.1     .11       0
  5273.2     .17       0  5755.3     .11       0
Bank Sta=4961.7,5071.1
XS Rating Curve= 0 ,0
Exp/Cntr=0.3,0.1

Type RM Length L Ch R = 1 ,1680    ,362,362,362
BEGIN DESCRIPTION:
Mapping XS 0704d293
END DESCRIPTION:
XS GIS Cut Line= 2
      3709406.41     10238966.96      3708286.55     10238380.12
#Sta/Elev= 30
  4543.8  356.35  4688.9  355.25  4783.8  353.22  4822.3  353.78  4827.9   352.9
  4844.3  352.19    4850  350.87  4982.5  350.15  5059.3  350.73  5079.6  349.36
  5083.1  349.36    5087  350.72  5095.4  350.96  5103.4   352.8  5140.5  354.34
  5197.3  354.08    5249  355.07  5332.5  355.33  5346.1  354.47  5377.6  354.39
  5390.2  354.48  5406.7  356.05  5434.4  354.43  5494.9  354.32  5533.4  355.86
  5566.4  356.18  5643.7  357.09  5649.3  357.73  5693.7  357.08  5808.1  359.25
#Mann= 5 ,-1 , 0
  4543.8     .11       0  4827.9     .06       0  5103.4     .11       0
    5249     .17       0  5566.4     .11       0
Bank Sta=4827.9,5103.4
XS Rating Curve= 0 ,0
Exp/Cntr=0.3,0.1

Type RM Length L Ch R = 1 ,1318    ,59,59,59
BEGIN DESCRIPTION:
Mapping XS a9c8105b
END DESCRIPTION:
XS GIS Cut Line= 6
      3709467.14     10238907.92      3709255.33     10238824.58
      3709211.93     10238458.26      3709132.07     10238447.84
      3708930.68     10238578.05      3708277.88      10238321.1
#Sta/Elev= 30
  4374.8   356.7  4377.1  355.78  4409.4  354.93  4512.4  354.74  4616.6  352.49
  4627.1  352.63  4637.6   356.7  4950.7   356.7  4971.9  355.46  4992.9   356.7
  5053.2   356.7  5216.2   356.7  5220.2   356.7  5305.9   356.7  5345.7  352.66
  5370.1  352.79  5394.7  354.68  5448.7  354.34  5454.1  353.62    5484  354.35
  5502.9  353.47    5538  354.63  5562.4  353.45  5634.5  355.01  5738.8  355.75
  5849.4  357.14    5863  356.49  5938.2  358.28    6009  359.19  6010.6  359.19
#Mann= 10 ,-1 , 0
  4374.8     .17       0  4950.7     .06       0  4992.9     .11       0
  5053.2     .17       0  5216.2     .11       0  5220.2     .11       0
  5394.7     .17       0  5738.8     .11       0  5938.2     .17       0
    6009     .11       0
#XS Ineff= 2 ,-1
  4374.8  4637.6   353.5  5305.9    5880   353.5
Permanent Ineff=
       T       T
Bank Sta=4950.7,4992.9
XS Rating Curve= 0 ,0
Exp/Cntr=0.3,0.1

Type RM Length L Ch R = 1 ,1259    ,326,326,326
BEGIN DESCRIPTION:
WFSJR 060 3.0
END DESCRIPTION:
XS GIS Cut Line= 3
      3709586.07     10238769.03      3709235.93     10238406.25
      3708277.92     10238218.68
#Sta/Elev= 30
  4495.8  352.32  4705.2   351.6  4747.7  349.98  4839.8  349.98  4931.6  347.51
  4959.9  346.98    4981  348.05  5000.3  346.19  5028.6  348.28  5048.4  349.86
  5053.5  348.37  5082.2  348.49    5105  348.09  5181.5  350.93  5252.8  351.84
  5264.6  350.94  5281.9  352.28  5344.5   351.2  5362.5  348.59  5367.6  350.67
  5398.7  350.61    5426  353.14  5470.6  353.54  5558.5  350.76  5581.3  351.66
  5658.1  354.09  5900.4  358.14  5915.1  359.09  5952.9  358.39  5976.2  359.24
#Mann= 11 ,-1 , 0
  4495.8     .11       0  4931.6     .17       0    4981     .09       0
  5028.6     .17       0  5082.2     .11       0  5281.9     .17       0
  5398.7     .11       0  5581.3     .17       0  5658.1     .11       0
  5900.4     .17       0  5952.9     .11       0
Bank Sta=4981,5028.6
XS Rating Curve= 0 ,0
Exp/Cntr=0.3,0.1

Type RM Length L Ch R = 1 ,933     ,468,468,468
BEGIN DESCRIPTION:
WFSJR 060 2.0
END DESCRIPTION:
XS GIS Cut Line= 3
      3709788.32     10238633.61      3709438.71     10238156.37
       3708481.1     10237981.16
#Sta/Elev= 30
  4408.4   349.1  4518.1  347.23  4553.6  347.87  4806.2  346.83  4910.9  345.94
  4946.5  346.01  4961.2   345.8    5000   343.8  5031.4  345.82  5077.6  346.46
  5110.2  346.13  5151.6  342.65  5155.4  343.15  5168.5  344.87  5183.9  348.54
  5214.4  347.77  5265.2  349.54  5346.5  350.22  5397.3  352.87  5417.7   351.8
  5509.2  352.78  5641.3  350.51  5661.7  352.53  5702.3  352.09  5720.8  352.95
  5728.9  352.14  5800.2  353.16  5824.3  354.37  5948.8   354.8  5973.5  355.72
#Mann= 10 ,-1 , 0
  4408.4     .11       0  4806.2     .17       0  4910.9     .11       0
  4946.5     .17       0  4961.2     .07       0  5031.4     .17       0
  5077.6     .17       0  5155.4     .17       0  5728.9     .11       0
  5800.2     .17       0
Bank Sta=4961.2,5031.4
XS Rating Curve= 0 ,0
Exp/Cntr=0.3,0.1

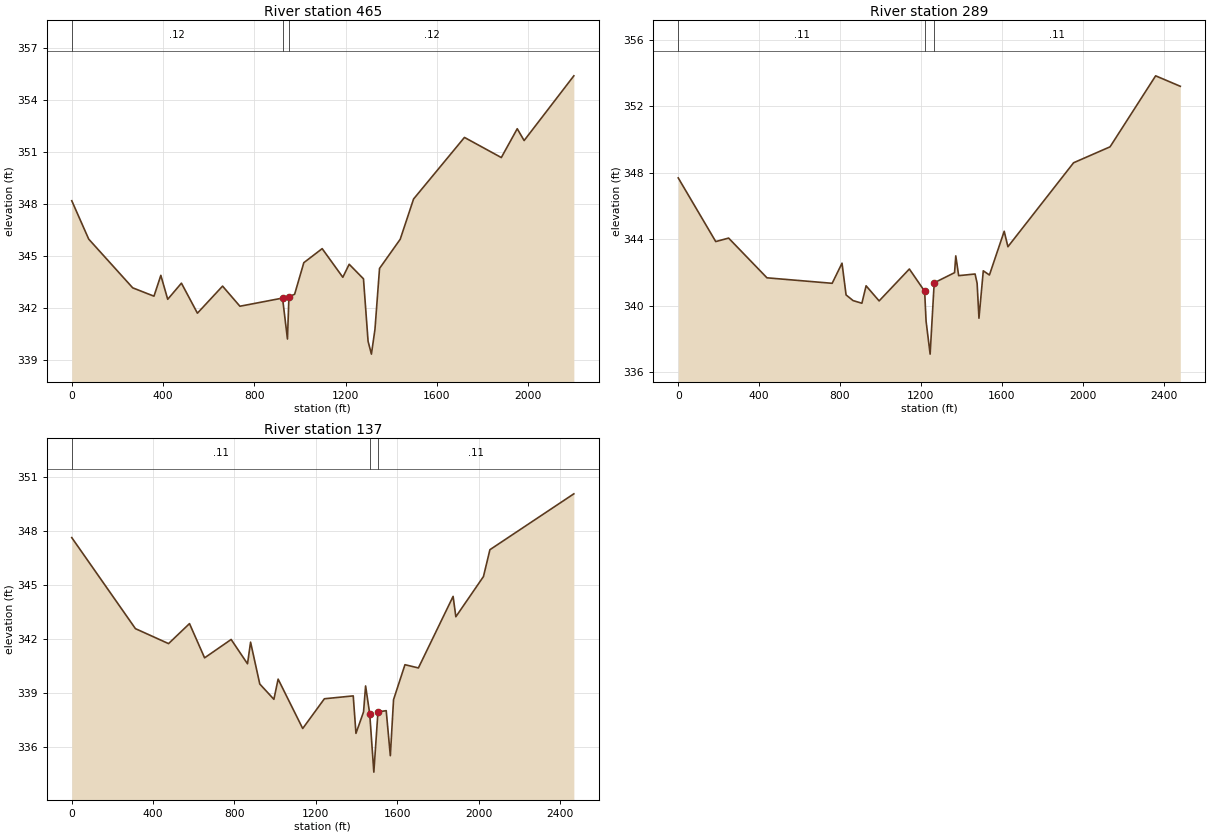
Type RM Length L Ch R = 1 ,465     ,176,176,176
XS GIS Cut Line= 5
       3709824.8     10238631.02      3709942.85     10238297.69
      3709961.41     10237981.43      3709732.22      10237817.8
      3708489.73     10237950.46
#Sta/Elev= 30
       0  348.17    74.2  345.96   267.1  343.15   360.2  342.67   390.3  343.87
   420.4  342.49   480.5  343.42   550.6  341.69   660.8  343.25   736.8  342.09
   923.6  342.56   945.1   340.2   951.6  342.64   976.5  342.78  1016.8   344.6
  1097.2  345.41  1187.7  343.76  1215.6  344.51  1278.2  343.67  1298.4  340.07
    1313  339.33  1328.5  340.75  1348.6  344.27  1439.2  345.95  1497.7  348.27
  1720.7  351.82  1882.2  350.66    1952  352.32  1982.2  351.64    2200  355.37
#Mann= 3 , 0 , 0
       0     .12       0   923.6     .07       0   951.6     .12       0
Bank Sta=923.6,951.6
XS Rating Curve= 0 ,0
Exp/Cntr=0.3,0.1

Type RM Length L Ch R = 1 ,289     ,152,152,152
XS GIS Cut Line= 6
      3709866.46     10238665.74      3710005.35     10238276.85
      3710040.08     10237842.83      3709790.44     10237651.68
      3709603.81     10237632.15      3708487.56      10237824.6
#Sta/Elev= 30
       0  347.68   185.5  343.85   249.2  344.06   438.8  341.67   761.3  341.34
     810  342.55   830.1  340.64   864.8   340.3   908.3  340.14   929.1  341.19
   993.5  340.28  1143.1   342.2  1218.7  340.86  1225.7  339.07  1245.8  337.08
  1265.9  341.37  1366.6  341.98  1372.6  342.99  1386.9   341.8  1468.1   341.9
  1478.2  341.34  1487.3  339.24  1508.7  342.09  1539.1  341.84  1612.1  344.47
  1630.5  343.54  1955.2  348.59  2135.7  349.55  2361.1  353.82  2483.1  353.19
#Mann= 3 , 0 , 0
       0     .11       0  1218.7     .06       0  1265.9     .11       0
Bank Sta=1218.7,1265.9
XS Rating Curve= 0 ,0
Exp/Cntr=0.3,0.1

Type RM Length L Ch R = 1 ,137     ,0,0,0
BEGIN DESCRIPTION:
WFSJR 060 DS
END DESCRIPTION:
XS GIS Cut Line= 6
      3709890.77     10238707.41      3710064.38     10238148.38
      3710102.58     10237756.02      3709813.51      10237512.1
      3709559.61     10237470.86      3708741.46     10237716.09
#Sta/Elev= 30
       0  347.63     313  342.58   475.8  341.75   578.8  342.86     653  340.96
   783.6  341.98     864  340.63   879.1  341.83   924.3  339.51   993.7  338.66
  1014.5  339.78  1135.4  337.04    1242  338.69  1383.8  338.85  1397.2  336.77
  1434.5  337.96  1444.6   339.4  1464.9  337.85  1485.1  334.62  1505.4  337.96
  1545.9  338.03  1566.2  335.53    1582  338.64  1638.1  340.58  1704.2   340.4
  1874.8  344.37  1888.3  343.24    2024  345.47  2055.8  346.96  2468.4  350.06
#Mann= 3 , 0 , 0
       0     .11       0  1464.9     .06       0  1505.4     .11       0
Bank Sta=1464.9,1505.4
XS Rating Curve= 0 ,0
Exp/Cntr=0.3,0.1

Chan Stop Cuts=-1
Use User Specified Reach Order=0
Composite Channel Slope=5