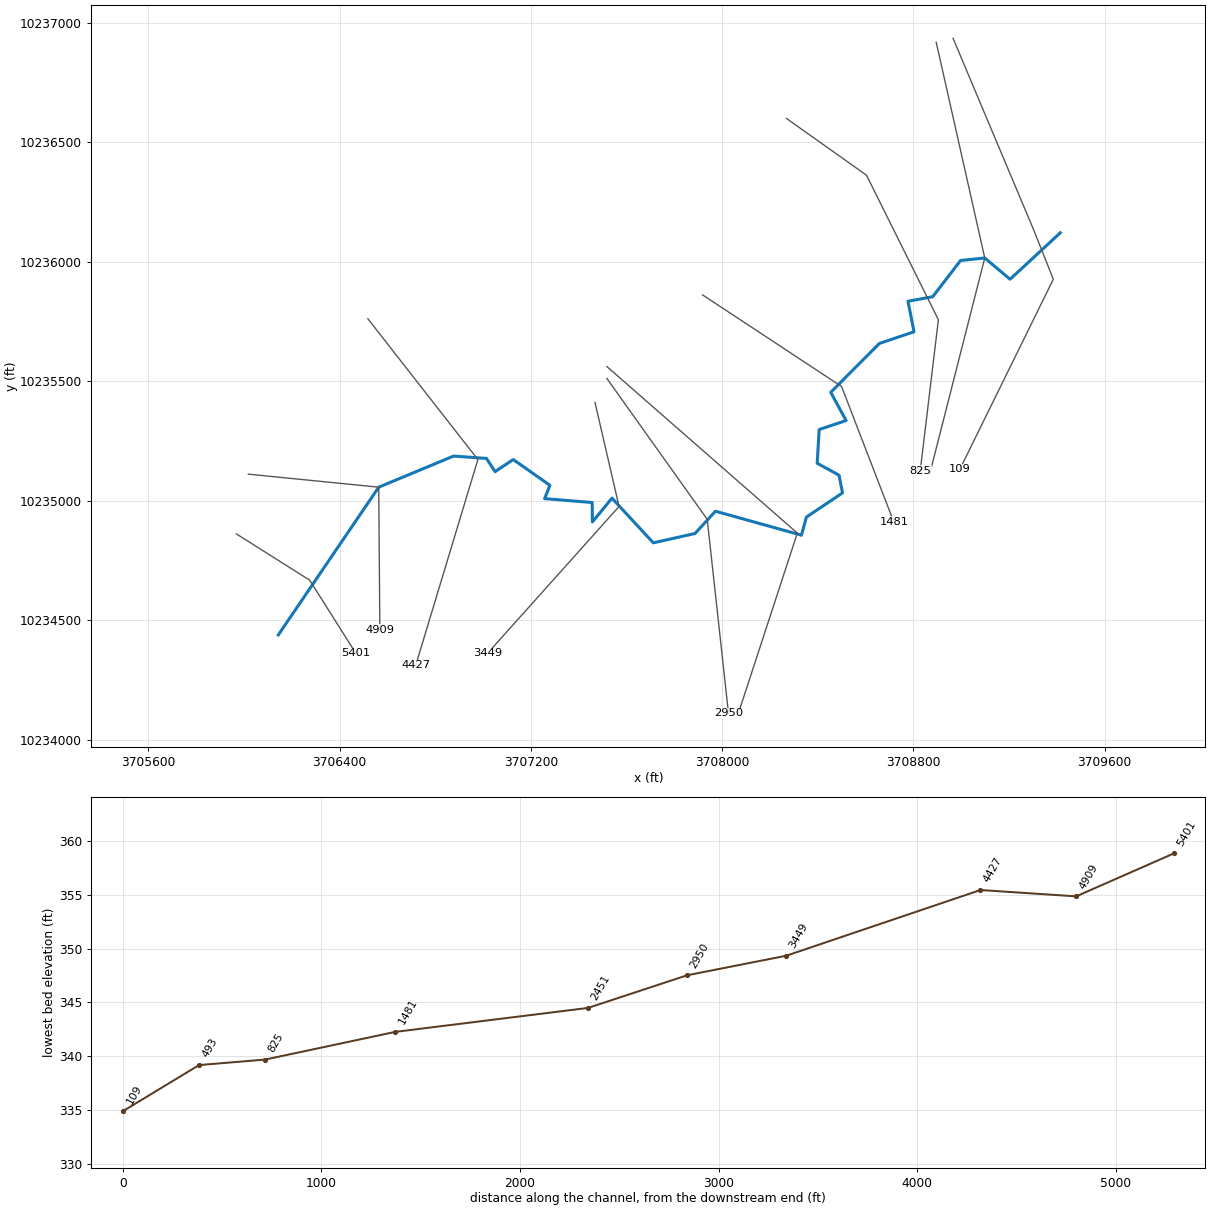
--- WFSJR 061.prj (project) ---

Proj Title=WFSJR 061 Base Level Engineering
Current Plan=p01
Default Exp/Contr=0.3,0.1
English Units
Geom File=g01
Flow File=f01
Plan File=p01
Y Axis Title=Elevation
X Axis Title(PF)=Main Channel Distance
X Axis Title(XS)=Station
BEGIN DESCRIPTION:
WFSJR 061
END DESCRIPTION:
DSS Export Rating Curves= 0
DSS Export Rating Curve Sorted= 0
DSS Export Volume Flow Curves= 0
DXF OffsetX= 0
DXF OffsetY= 0
DXF ScaleX= 1
DXF ScaleY= 10

--- WFSJR 061.p01 (plan) ---

Plan Title=Multiple Run
Program Version=4.10
Short Identifier=Multiple
Geom File=g01
Flow File=f01
Subcritical Flow
K Sum by GR= 0
Std Step Tol= 0.01
Critical Tol= 0.01
Num of Std Step Trials= 20
Max Error Tol= 0.3
Flow Tol Ratio= 0.001
Split Flow NTrial= 30
Split Flow Tol= 0.02
Split Flow Ratio= 0.02
Log Output Level= 0
Friction Slope Method= 1
Unsteady Friction Slope Method= 2
Unsteady Bridges Friction Slope Method= 1
Parabolic Critical Depth
Global Vel Dist= 1 , 1 , 1
Global Log Level= 0
CheckData=True
Encroach Param=-1 ,0,0, 0
BEGIN DESCRIPTION:
Multiple Run
END DESCRIPTION:
Computation Interval=1HOUR
Output Interval=1HOUR
Run HTab= 0
Run UNet= 0
Run PostProcess= 0
Run WQNet= 0
UNET Theta= 1
UNET Theta Warmup= 1
UNET ZTol= 0.02
UNET ZSATol= 0.05
UNET MxIter= 20
UNET MaxInSteps= 0
UNET DtIC= 0
UNET DtMin= 0
UNET MaxCRTS= 20
UNET WFStab= 2
UNET SFStab= 1
UNET WFX= 1
UNET SFX= 1
UNET DSS MLevel= 4
UNET DZMax Abort= 100
UNET Convert EG Bridges= 0
UNET Use Existing IB Tables=-1
UNET Froude Reduction=False
UNET Froude Limit= 1
UNET Froude Power= 10
UNET Time Slicing=0,0, 5
UNET Junction Losses=0
Instantaneous Interval=1HOUR
Write IC File= 0
Write IC File at Sim End=0
Echo Input=False
Echo Parameters=False
Echo Output=False
Write Detailed= 0
WQ AD Non Conservative
WQ ULTIMATE=-1
WQ Max Comp Step=1HOUR
WQ Output Interval=15MIN
WQ Output Selected Increments= 0
WQ Output face flow=0
WQ Output face velocity=0
WQ Output face area=0
WQ Output face dispersion=0
WQ Output cell volume=0
WQ Output cell surface area=0
WQ Output cell continuity=0
WQ Output cumulative cell continuity=0
WQ Output face conc=0
WQ Output face dconc_dx=0
WQ Output face courant=0
WQ Output face peclet=0
WQ Output face adv mass=0
WQ Output face disp mass=0
WQ Output cell mass=0
WQ Output cell source sink temp=0
WQ Output cell source sink nsm=0
WQ Output MaxMinRange=-1
WQ Daily Max Min Mean=-1
WQ Daily Range=0
WQ Daily Time=0
WQ Create Restart=0
WQ Fixed Restart=0
WQ System Summary=0
WQ Use Fixed Temperature=0
Sorting and Armoring Iterations= 10
XS Update Threshold= 0.02
Hydraulics Update Threshold= 0.02
Energy Slope Method= 1
Volume Change Method= 0
XS Weighting Method= 0
Number of US Weighted Cross Sections= 1
Number of DS Weighted Cross Sections= 1
Upstream XS Weight=0.25
Main XS Weight=0.5
Downstream XS Weight=0.25
Number of DS XS's Weighted with US Boundary= 1
Upstream Boundary Weight= 1
Weight of XSs Associated with US Boundary= 0
Number of US XS's Weighted with DS Boundary= 1
Downstream Boundary Weight= 0.5
Weight of XSs Associated with DS Boundary= 0.5
Sediment Output Level= 4
Mass or Volume Output= 0
Output Increment Type= 1
Profile and TS Output Increment= 10
XS Output Flag= 0
XS Output Increment= 10
Disregard all LS=0
Disregard all Conn=0
Disregard all Breaches=0
Disregard all Pumps=0

--- WFSJR 061.f01 (steady flow) ---

Flow Title=Multiple
Program Version=4.10
Number of Profiles= 7
Profile Names=10-year,25-year,50-year,1pct_min,100-year,1pct_plu,500-year
River Rch & RM=WFSJR 061,Reach-1         ,5401
     315     408     536     231     699    2111    1235
Boundary for River Rch & Prof#=WFSJR 061,Reach-1         , 1
Up Type= 0
Dn Type= 3
Dn Slope=0.011
Boundary for River Rch & Prof#=WFSJR 061,Reach-1         , 2
Up Type= 0
Dn Type= 3
Dn Slope=0.011
Boundary for River Rch & Prof#=WFSJR 061,Reach-1         , 3
Up Type= 0
Dn Type= 3
Dn Slope=0.011
Boundary for River Rch & Prof#=WFSJR 061,Reach-1         , 4
Up Type= 0
Dn Type= 3
Dn Slope=0.011
Boundary for River Rch & Prof#=WFSJR 061,Reach-1         , 5
Up Type= 0
Dn Type= 3
Dn Slope=0.011
Boundary for River Rch & Prof#=WFSJR 061,Reach-1         , 6
Up Type= 0
Dn Type= 3
Dn Slope=0.011
Boundary for River Rch & Prof#=WFSJR 061,Reach-1         , 7
Up Type= 0
Dn Type= 3
Dn Slope=0.011
DSS Import GetInterval= 0
DSS Import GetPeak= 0
DSS Import FillOption= 0

--- WFSJR 061.g01 (geometry) ---

Geom Title=Existing Conditions
Program Version=4.10

River Reach=WFSJR 061       ,Reach-1
Reach XY= 30
      3706143.09     10234438.57      3706563.23     10235056.62
      3706876.38     10235186.79      3707013.88     10235176.89
      3707049.81     10235121.68      3707125.86     10235172.21
       3707279.5     10235064.39      3707257.11     10235008.66
      3707456.06     10234992.52      3707457.11     10234911.27
      3707538.88     10235010.75      3707711.79     10234823.77
      3707886.27     10234862.83      3707971.69     10234956.06
      3708331.45     10234855.84      3708352.29     10234931.58
      3708503.33     10235032.71      3708488.79     10235106.49
      3708397.43     10235156.84      3708405.67     10235297.68
       3708518.3     10235335.44      3708454.07      10235453.5
      3708657.84     10235658.14      3708802.37     10235706.54
       3708777.2     10235834.36      3708880.72     10235853.46
      3708997.25     10236004.93      3709098.38     10236015.35
      3709204.28     10235926.37      3709414.31     10236120.77

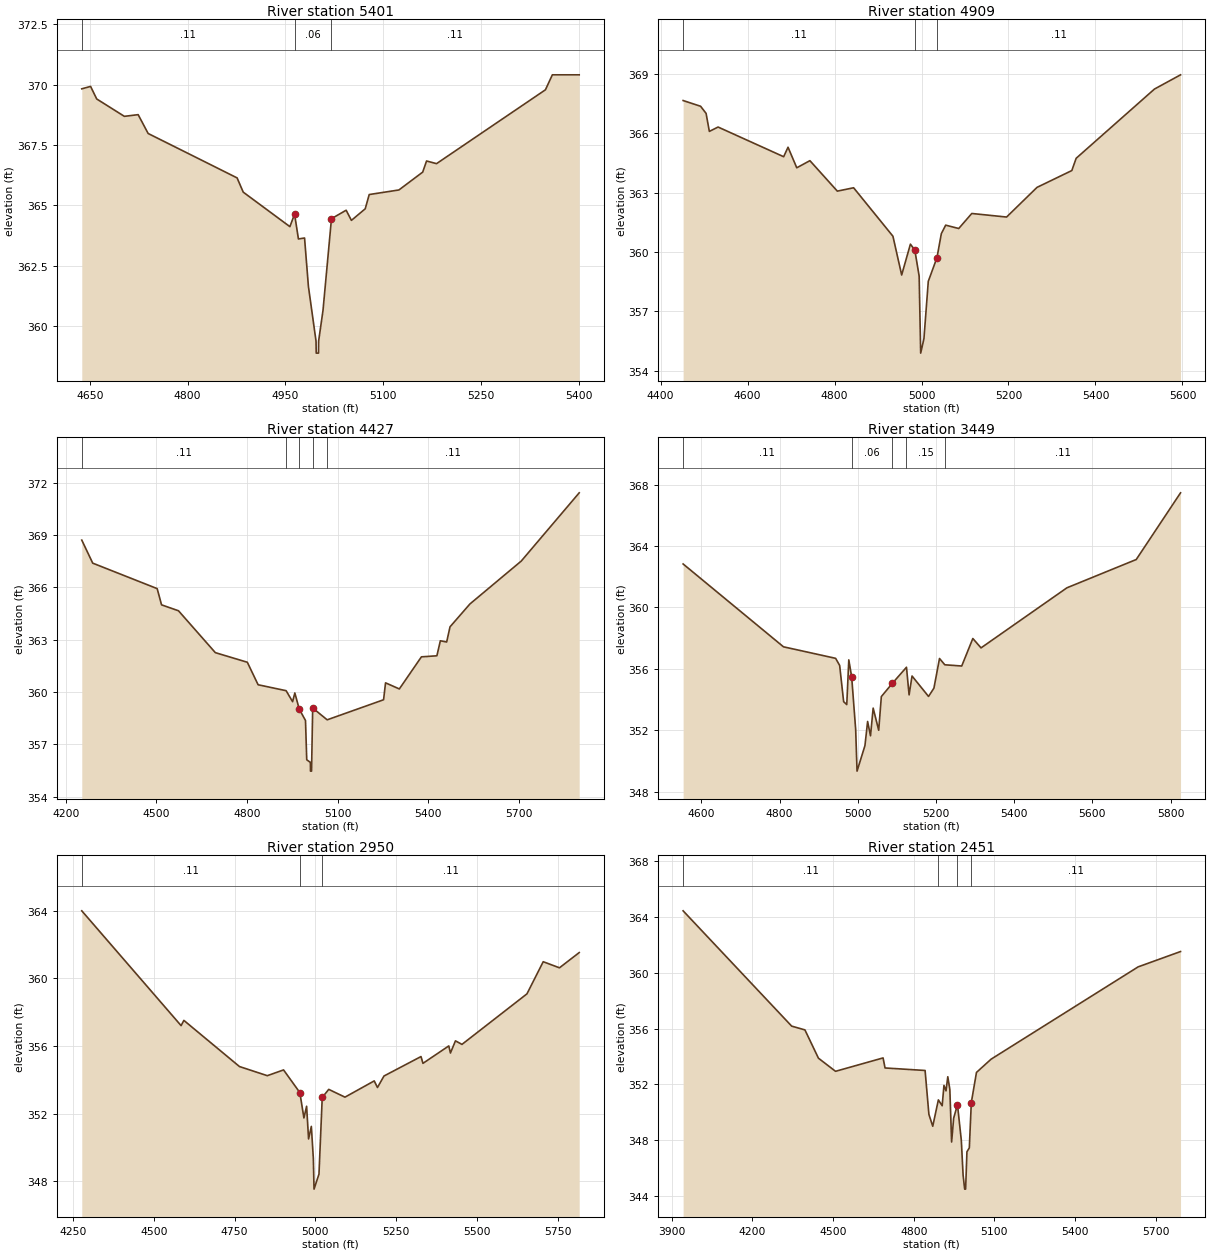
Type RM Length L Ch R = 1 ,5401    ,492,492,492
BEGIN DESCRIPTION:
WFSJR 061 8.0
END DESCRIPTION:
XS GIS Cut Line= 3
      3705967.87     10234861.06      3706274.16     10234667.73
      3706467.85     10234361.08
#Sta/Elev= 30
  4637.8  369.83  4651.3  369.93  4660.7  369.41  4703.1  368.69  4724.3  368.76
  4739.6  367.98  4876.1  366.14  4885.5  365.55  4957.1  364.12  4964.3  364.64
  4970.2  363.61  4979.6  363.65  4985.5  361.65  4997.2  359.38  4997.5  358.88
    5001  358.88  5001.2  359.38  5007.9  360.65  5020.9  364.45  5043.4   364.8
  5051.5  364.38  5072.7  364.86  5078.8  365.45  5124.4  365.64  5160.9  366.38
  5166.8  366.84  5182.1  366.73  5349.2  369.79  5359.8  370.41    5401  370.41
#Mann= 3 , 0 , 0
  4637.8     .11       0  4964.3     .06       0  5020.9     .11       0
Bank Sta=4964.3,5020.9
XS Rating Curve= 0 ,0
Exp/Cntr=0.3,0.1

Type RM Length L Ch R = 1 ,4909    ,482,482,482
BEGIN DESCRIPTION:
WFSJR 061 7.0
END DESCRIPTION:
XS GIS Cut Line= 3
      3706017.84     10235111.07      3706563.23     10235056.62
      3706567.85     10234461.04
#Sta/Elev= 30
  4451.9  367.65  4492.1  367.36  4504.7     367  4512.2  366.09  4532.3  366.31
  4683.1  364.81  4693.1  365.29  4713.2  364.25  4743.4  364.61  4806.5  363.07
  4843.9  363.24  4934.3  360.79  4954.4  358.83  4974.5  360.39  4984.6  360.09
  4994.6  358.77  4998.1  354.88  5005.6  355.61  5015.6  358.51  5035.6  359.71
  5045.6  360.92  5055.6  361.35  5085.6  361.18  5115.6  361.94  5195.6  361.76
  5265.6  363.26  5345.6  364.11  5355.6  364.73  5535.6  368.23  5595.6  368.95
#Mann= 3 , 0 , 0
  4451.9     .11       0  4984.6     .06       0  5035.6     .11       0
Bank Sta=4984.6,5035.6
XS Rating Curve= 0 ,0
Exp/Cntr=0.3,0.1

Type RM Length L Ch R = 1 ,4427    ,978,978,978
BEGIN DESCRIPTION:
WFSJR 061 6.0
END DESCRIPTION:
XS GIS Cut Line= 3
      3706517.85     10235761.08      3706977.94     10235172.21
      3706717.84     10234311.03
#Sta/Elev= 30
  4252.7  368.71  4288.9  367.39  4502.3  365.93  4516.8     365  4572.9  364.66
  4694.9  362.26  4800.8  361.71  4836.5  360.42  4929.2  360.08  4950.7  359.45
  4958.1  359.95  4972.6  359.03  4993.4  358.37  4997.5  356.12  5009.6  355.97
  5009.9  355.47  5013.4  355.47  5017.2  359.09  5065.1  358.41  5251.9  359.56
  5258.4  360.53  5304.1  360.18  5377.2  362.02  5428.4  362.08  5439.9  362.94
  5460.8  362.87  5471.9  363.74  5537.8  365.05  5707.8  367.51  5899.6  371.42
#Mann= 5 ,-1 , 0
  4252.7     .11       0  4929.2     .15       0  4972.6     .09       0
  5017.2     .15       0  5065.1     .11       0
Bank Sta=4972.6,5017.2
XS Rating Curve= 0 ,0
Exp/Cntr=0.3,0.1

Type RM Length L Ch R = 1 ,3449    ,499,499,499
BEGIN DESCRIPTION:
WFSJR 061 5.0
END DESCRIPTION:
XS GIS Cut Line= 3
      3707467.86     10235411.05      3707568.56     10234975.85
      3707017.83     10234361.05
#Sta/Elev= 30
  4553.3  362.83  4809.9  357.44  4943.3  356.69  4953.6  356.23  4963.8  353.87
  4971.8  353.68    4977  356.59  4984.4  355.47  4994.6  352.04  4998.1  349.35
  5018.3  351.01  5025.1  352.58  5032.5  351.65  5039.3  353.45  5053.5  352.01
  5060.2   354.2  5088.6  355.07  5124.5  356.11  5131.2  354.31  5138.7  355.54
  5180.9  354.21  5194.7  354.75    5209  356.68  5222.5  356.27  5265.8  356.19
  5294.2  357.98  5315.2  357.37  5534.9  361.28  5712.1  363.12  5825.4  367.46
#Mann= 5 ,-1 , 0
  4553.3     .11       0  4984.4     .06       0  5088.6     .11       0
  5124.5     .15       0  5222.5     .11       0
#XS Ineff= 2 ,-1
    4900    4977  356.59  5124.5    5205  356.11
Permanent Ineff=
       F       F
Bank Sta=4984.4,5088.6
XS Rating Curve= 0 ,0
Exp/Cntr=0.3,0.1

Type RM Length L Ch R = 1 ,2950    ,499,499,499
BEGIN DESCRIPTION:
WFSJR 061 4.0
END DESCRIPTION:
XS GIS Cut Line= 3
      3707517.84     10235511.08      3707937.31      10234922.2
      3708026.38     10234110.38
#Sta/Elev= 30
    4277  363.99  4584.4   357.2    4593  357.51  4765.1  354.78  4851.2  354.24
  4901.6  354.58    4952  353.24  4964.6  351.74  4972.9  352.43    4979   350.5
  4987.6  351.24  4993.8  349.33  4995.9  347.53  5011.2  348.42  5021.3  352.95
  5041.4  353.43  5091.7  352.97  5182.2  353.93  5192.3  353.54  5212.4  354.22
    5327  355.37  5333.1  354.97  5413.1     356  5418.1  355.58  5433.7   356.3
  5453.8  356.09    5655  359.08  5705.3  360.98  5755.6  360.62  5816.7  361.52
#Mann= 3 , 0 , 0
    4277     .11       0    4952     .06       0  5021.3     .11       0
Bank Sta=4952,5021.3
XS Rating Curve= 0 ,0
Exp/Cntr=0.3,0.1

Type RM Length L Ch R = 1 ,2451    ,970,970,970
BEGIN DESCRIPTION:
WFSJR 061 3.0
END DESCRIPTION:
XS GIS Cut Line= 3
      3707517.83     10235561.09      3708314.31     10234864.52
      3708067.86     10234111.11
#Sta/Elev= 30
  3941.9  364.45  4345.8  356.18  4395.1  355.91  4445.4  353.88    4509  352.94
  4685.9   353.9  4693.2  353.18  4842.2     353  4856.4  349.85  4870.7     349
  4891.6  350.89  4905.8  350.47  4912.4  351.93    4920  351.54  4926.7  352.55
  4934.3  351.64  4940.9  347.87  4948.5  349.58  4962.7  350.55    4977  347.99
  4983.6   345.5  4989.5  344.49    4993  344.49  4997.9  347.17  5006.8  347.45
  5014.2   350.7  5033.4  352.86  5087.8  353.81  5634.9  360.43  5792.7  361.53
#Mann= 4 ,-1 , 0
  3941.9     .11       0  4891.6     .11       0  4962.7     .07       0
  5014.2     .11       0
#XS Ineff= 2 ,-1
    4838  4926.7  352.55    4934  4962.7  350.55
Permanent Ineff=
       T       F
Bank Sta=4962.7,5014.2
XS Rating Curve= 0 ,0
Exp/Cntr=0.3,0.1

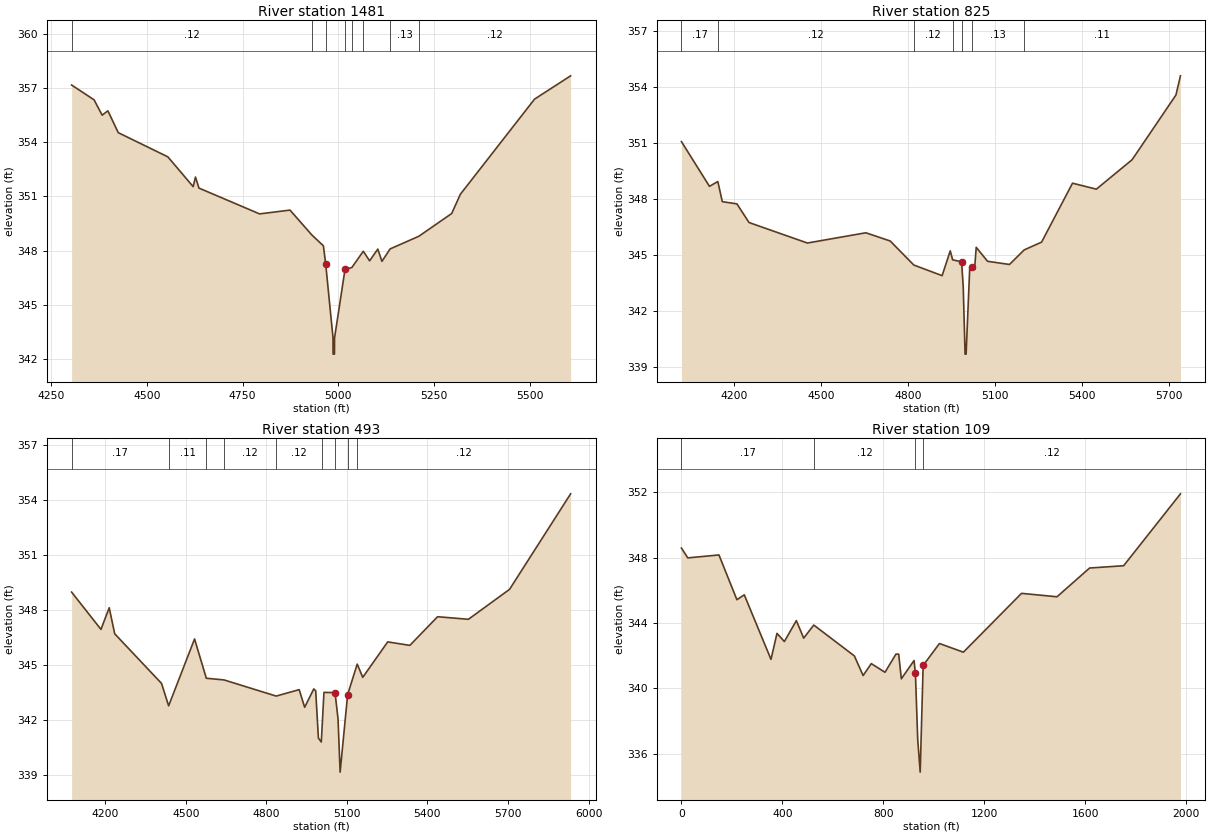
Type RM Length L Ch R = 1 ,1481    ,656,656,656
BEGIN DESCRIPTION:
WFSJR 061 2.0
END DESCRIPTION:
XS GIS Cut Line= 3
      3707917.87     10235861.06      3708499.42     10235477.59
      3708717.86     10234911.04
#Sta/Elev= 30
  4303.4  357.17  4362.1  356.35  4383.2   355.5  4398.2  355.74  4425.3  354.53
  4554.9  353.19    4621  351.54    4627  352.07  4636.1  351.46  4794.5  350.03
    4874  350.24  4931.2  348.86  4961.3  348.26  4967.3  347.25  4986.4  343.16
  4986.6  342.26  4990.1  342.26  4990.4  343.16  5017.7  346.95  5035.6  347.06
  5065.5  347.96    5082  347.43  5103.4  348.08  5114.2   347.4  5135.6  348.09
  5210.6  348.79  5296.4  350.05  5319.2  351.12    5513  356.39  5607.2  357.68
#Mann= 8 ,-1 , 0
  4303.4     .12       0  4931.2     .12       0  4967.3     .08       0
  5017.7     .12       0  5035.6     .12       0  5065.5     .12       0
  5135.6     .13       0  5210.6     .12       0
Bank Sta=4967.3,5017.7
XS Rating Curve= 0 ,0
Exp/Cntr=0.3,0.1

Type RM Length L Ch R = 1 ,825     ,332,332,332
BEGIN DESCRIPTION:
Mapping XS df1b83b6
END DESCRIPTION:
XS GIS Cut Line= 4
      3708269.43     10236598.63      3708603.64     10236361.65
      3708904.42     10235757.05      3708828.53     10235125.58
#Sta/Elev= 30
  4018.9  351.08  4115.5  348.68  4144.3  348.94  4159.8  347.86  4210.2  347.74
    4252  346.74  4453.2  345.64  4654.8  346.19  4738.8  345.75  4820.2  344.46
  4917.9  343.89  4945.9  345.22  4954.2  344.74  4985.1  344.63  4990.7   343.3
  4997.1  339.68  5000.6  339.68  5013.1   344.3  5021.2  344.36  5029.9  344.26
  5035.5  345.41  5074.7  344.66  5150.2  344.49  5200.8  345.27    5261  345.69
  5367.6  348.85  5449.8  348.53  5573.2  350.11  5724.3  353.58  5739.9  354.61
#Mann= 7 ,-1 , 0
  4018.9     .17       0  4144.3     .12       0  4820.2     .12       0
  4954.2     .13       0  4985.1     .08       0  5021.2     .13       0
  5200.8     .11       0
#XS Ineff= 2 ,-1
    4745  4945.9  345.22  5035.5    5250  345.41
Permanent Ineff=
       T       T
Bank Sta=4985.1,5021.2
XS Rating Curve= 0 ,0
Exp/Cntr=0.3,0.1

Type RM Length L Ch R = 1 ,493     ,384,384,384
BEGIN DESCRIPTION:
WFSJR 061 1.0
END DESCRIPTION:
XS GIS Cut Line= 3
       3708895.3     10236917.68      3709098.38     10236015.35
      3708867.85     10235111.07
#Sta/Elev= 30
  4075.1  348.97  4184.4  346.94  4215.1  348.12  4235.6   346.7  4409.9     344
  4436.4  342.78  4532.9  346.42  4576.7  344.28  4642.5  344.19  4836.7  343.31
  4922.4  343.66  4942.9   342.7  4976.8   343.7  4983.9   343.6  4994.1  341.02
  5004.8  340.81  5008.2  341.74  5014.7  343.51    5056   343.5  5067.2  342.06
  5074.9  339.17  5102.9  343.39  5138.6  345.05  5159.2  344.33  5252.1  346.26
  5334.6  346.07  5437.8  347.63  5552.6  347.49  5705.8  349.12  5933.2  354.32
#Mann= 9 ,-1 , 0
  4075.1     .17       0  4436.4     .11       0  4576.7     .15       0
  4642.5     .12       0  4836.7     .12       0  5008.2     .13       0
    5056     .08       0  5102.9     .13       0  5138.6     .12       0
#XS Ineff= 1 ,-1
    4200  4532.9  346.42
Permanent Ineff=
       F
Bank Sta=5056,5102.9
XS Rating Curve= 0 ,0
Exp/Cntr=0.3,0.1

Type RM Length L Ch R = 1 ,109     ,0,0,0
XS GIS Cut Line= 4
      3708965.83     10236934.23      3709304.37     10236129.55
       3709385.1     10235926.42      3708994.47     10235132.15
#Sta/Elev= 30
       0  348.58    25.1  347.98   148.5  348.16   219.7  345.42   248.9  345.72
   354.7  341.77   378.4  343.36   407.6  342.86   455.1  344.14   484.2  343.07
   524.2  343.87     685  341.98   719.6  340.78     752  341.51   806.3  340.98
   849.7  342.09   860.5  342.09     871  340.58   921.4   341.7   926.8  340.91
   935.9  336.87   945.7  334.87   957.4   341.4    1022  342.74  1116.8  342.21
  1347.1  345.81  1487.6   345.6  1616.8  347.36  1751.6   347.5  1976.7   351.9
#Mann= 4 ,-1 , 0
       0     .17       0   524.2     .12       0   926.8     .08       0
   957.4     .12       0
#XS Ineff= 1 ,-1
     250   455.1  344.14
Permanent Ineff=
       F
Bank Sta=926.8,957.4
XS Rating Curve= 0 ,0
Exp/Cntr=0.3,0.1

Chan Stop Cuts=-1
Use User Specified Reach Order=0
Composite Channel Slope=5