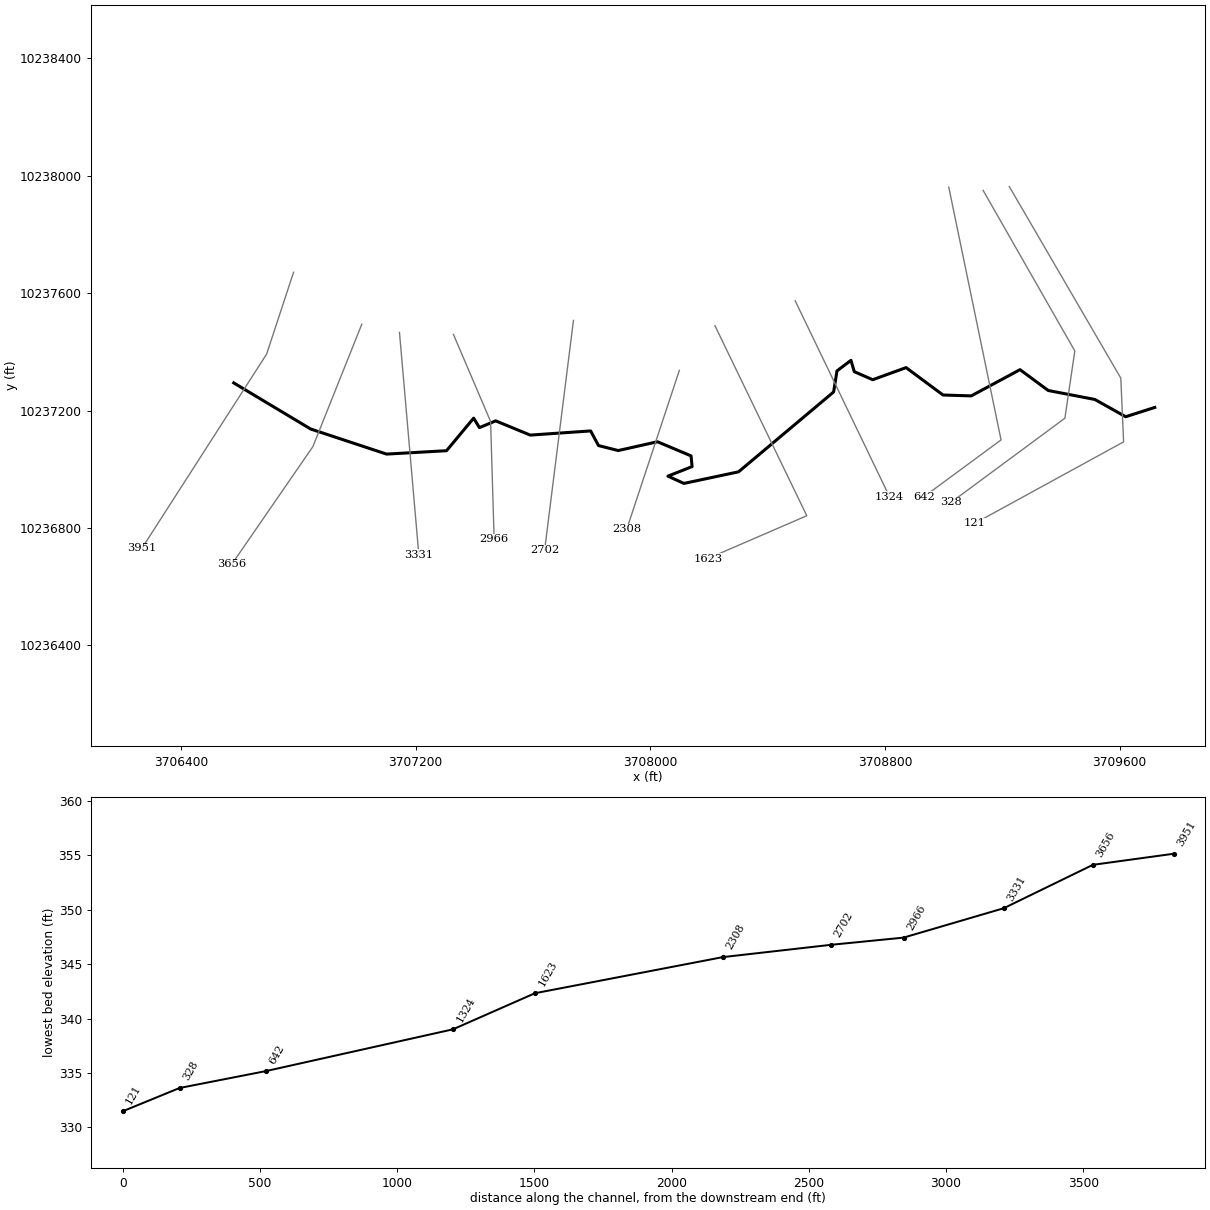
--- WFSJR 063.prj (project) ---

Proj Title=WFSJR 063 Base Level Engineering
Current Plan=p01
Default Exp/Contr=0.3,0.1
English Units
Geom File=g01
Flow File=f01
Plan File=p01
Y Axis Title=Elevation
X Axis Title(PF)=Main Channel Distance
X Axis Title(XS)=Station
BEGIN DESCRIPTION:
WFSJR 063
END DESCRIPTION:
DSS Export Rating Curves= 0
DSS Export Rating Curve Sorted= 0
DSS Export Volume Flow Curves= 0
DXF OffsetX= 0
DXF OffsetY= 0
DXF ScaleX= 1
DXF ScaleY= 10

--- WFSJR 063.p01 (plan) ---

Plan Title=Multiple Run
Program Version=4.10
Short Identifier=Multiple
Geom File=g01
Flow File=f01
Subcritical Flow
K Sum by GR= 0
Std Step Tol= 0.01
Critical Tol= 0.01
Num of Std Step Trials= 20
Max Error Tol= 0.3
Flow Tol Ratio= 0.001
Split Flow NTrial= 30
Split Flow Tol= 0.02
Split Flow Ratio= 0.02
Log Output Level= 0
Friction Slope Method= 1
Unsteady Friction Slope Method= 2
Unsteady Bridges Friction Slope Method= 1
Parabolic Critical Depth
Global Vel Dist= 1 , 1 , 1
Global Log Level= 0
CheckData=True
Encroach Param=-1 ,0,0, 0
BEGIN DESCRIPTION:
Multiple Run
END DESCRIPTION:
Computation Interval=1HOUR
Output Interval=1HOUR
Run HTab= 0
Run UNet= 0
Run PostProcess= 0
Run WQNet= 0
UNET Theta= 1
UNET Theta Warmup= 1
UNET ZTol= 0.02
UNET ZSATol= 0.05
UNET MxIter= 20
UNET MaxInSteps= 0
UNET DtIC= 0
UNET DtMin= 0
UNET MaxCRTS= 20
UNET WFStab= 2
UNET SFStab= 1
UNET WFX= 1
UNET SFX= 1
UNET DSS MLevel= 4
UNET DZMax Abort= 100
UNET Convert EG Bridges= 0
UNET Use Existing IB Tables=-1
UNET Froude Reduction=False
UNET Froude Limit= 1
UNET Froude Power= 10
UNET Time Slicing=0,0, 5
UNET Junction Losses=0
Instantaneous Interval=1HOUR
Write IC File= 0
Write IC File at Sim End=0
Echo Input=False
Echo Parameters=False
Echo Output=False
Write Detailed= 0
WQ AD Non Conservative
WQ ULTIMATE=-1
WQ Max Comp Step=1HOUR
WQ Output Interval=15MIN
WQ Output Selected Increments= 0
WQ Output face flow=0
WQ Output face velocity=0
WQ Output face area=0
WQ Output face dispersion=0
WQ Output cell volume=0
WQ Output cell surface area=0
WQ Output cell continuity=0
WQ Output cumulative cell continuity=0
WQ Output face conc=0
WQ Output face dconc_dx=0
WQ Output face courant=0
WQ Output face peclet=0
WQ Output face adv mass=0
WQ Output face disp mass=0
WQ Output cell mass=0
WQ Output cell source sink temp=0
WQ Output cell source sink nsm=0
WQ Output MaxMinRange=-1
WQ Daily Max Min Mean=-1
WQ Daily Range=0
WQ Daily Time=0
WQ Create Restart=0
WQ Fixed Restart=0
WQ System Summary=0
WQ Use Fixed Temperature=0
Sorting and Armoring Iterations= 10
XS Update Threshold= 0.02
Hydraulics Update Threshold= 0.02
Energy Slope Method= 1
Volume Change Method= 0
XS Weighting Method= 0
Number of US Weighted Cross Sections= 1
Number of DS Weighted Cross Sections= 1
Upstream XS Weight=0.25
Main XS Weight=0.5
Downstream XS Weight=0.25
Number of DS XS's Weighted with US Boundary= 1
Upstream Boundary Weight= 1
Weight of XSs Associated with US Boundary= 0
Number of US XS's Weighted with DS Boundary= 1
Downstream Boundary Weight= 0.5
Weight of XSs Associated with DS Boundary= 0.5
Sediment Output Level= 4
Mass or Volume Output= 0
Output Increment Type= 1
Profile and TS Output Increment= 10
XS Output Flag= 0
XS Output Increment= 10
Disregard all LS=0
Disregard all Conn=0
Disregard all Breaches=0
Disregard all Pumps=0

--- WFSJR 063.f01 (steady flow) ---

Flow Title=Multiple
Program Version=4.10
Number of Profiles= 7
Profile Names=10-year,25-year,50-year,1pct_min,100-year,1pct_plu,500-year
River Rch & RM=WFSJR 063,Reach-1         ,3951
     228     289     374     160     482    1456     829
Boundary for River Rch & Prof#=WFSJR 063,Reach-1         , 1
Up Type= 0
Dn Type= 3
Dn Slope=0.007
Boundary for River Rch & Prof#=WFSJR 063,Reach-1         , 2
Up Type= 0
Dn Type= 3
Dn Slope=0.007
Boundary for River Rch & Prof#=WFSJR 063,Reach-1         , 3
Up Type= 0
Dn Type= 3
Dn Slope=0.007
Boundary for River Rch & Prof#=WFSJR 063,Reach-1         , 4
Up Type= 0
Dn Type= 3
Dn Slope=0.007
Boundary for River Rch & Prof#=WFSJR 063,Reach-1         , 5
Up Type= 0
Dn Type= 3
Dn Slope=0.007
Boundary for River Rch & Prof#=WFSJR 063,Reach-1         , 6
Up Type= 0
Dn Type= 3
Dn Slope=0.007
Boundary for River Rch & Prof#=WFSJR 063,Reach-1         , 7
Up Type= 0
Dn Type= 3
Dn Slope=0.007
DSS Import GetInterval= 0
DSS Import GetPeak= 0
DSS Import FillOption= 0

--- WFSJR 063.g01 (geometry) ---

Geom Title=Existing Conditions
Program Version=4.10

River Reach=WFSJR 063       ,Reach-1
Reach XY= 30
      3706579.99     10237294.24      3706842.19     10237137.18
      3707101.03     10237051.67      3707305.57     10237063.22
      3707398.01     10237174.16      3707417.66      10237141.8
      3707473.12     10237164.91      3707590.99     10237116.38
      3707796.79      10237130.6       3707823.7     10237080.69
      3707890.97     10237063.76      3708024.66     10237093.71
      3708139.24     10237045.53      3708142.71     10237009.07
      3708060.25     10236976.52      3708114.93     10236951.78
      3708301.13     10236991.28      3708625.35     10237263.41
      3708636.63     10237335.03      3708684.38     10237371.05
      3708695.66     10237332.42       3708758.6     10237305.08
      3708872.31     10237346.31      3708998.16     10237252.94
      3709094.53     10237249.96      3709260.75     10237339.31
      3709356.89     10237268.35      3709515.96     10237237.75
      3709620.99     10237178.94      3709720.17     10237210.63

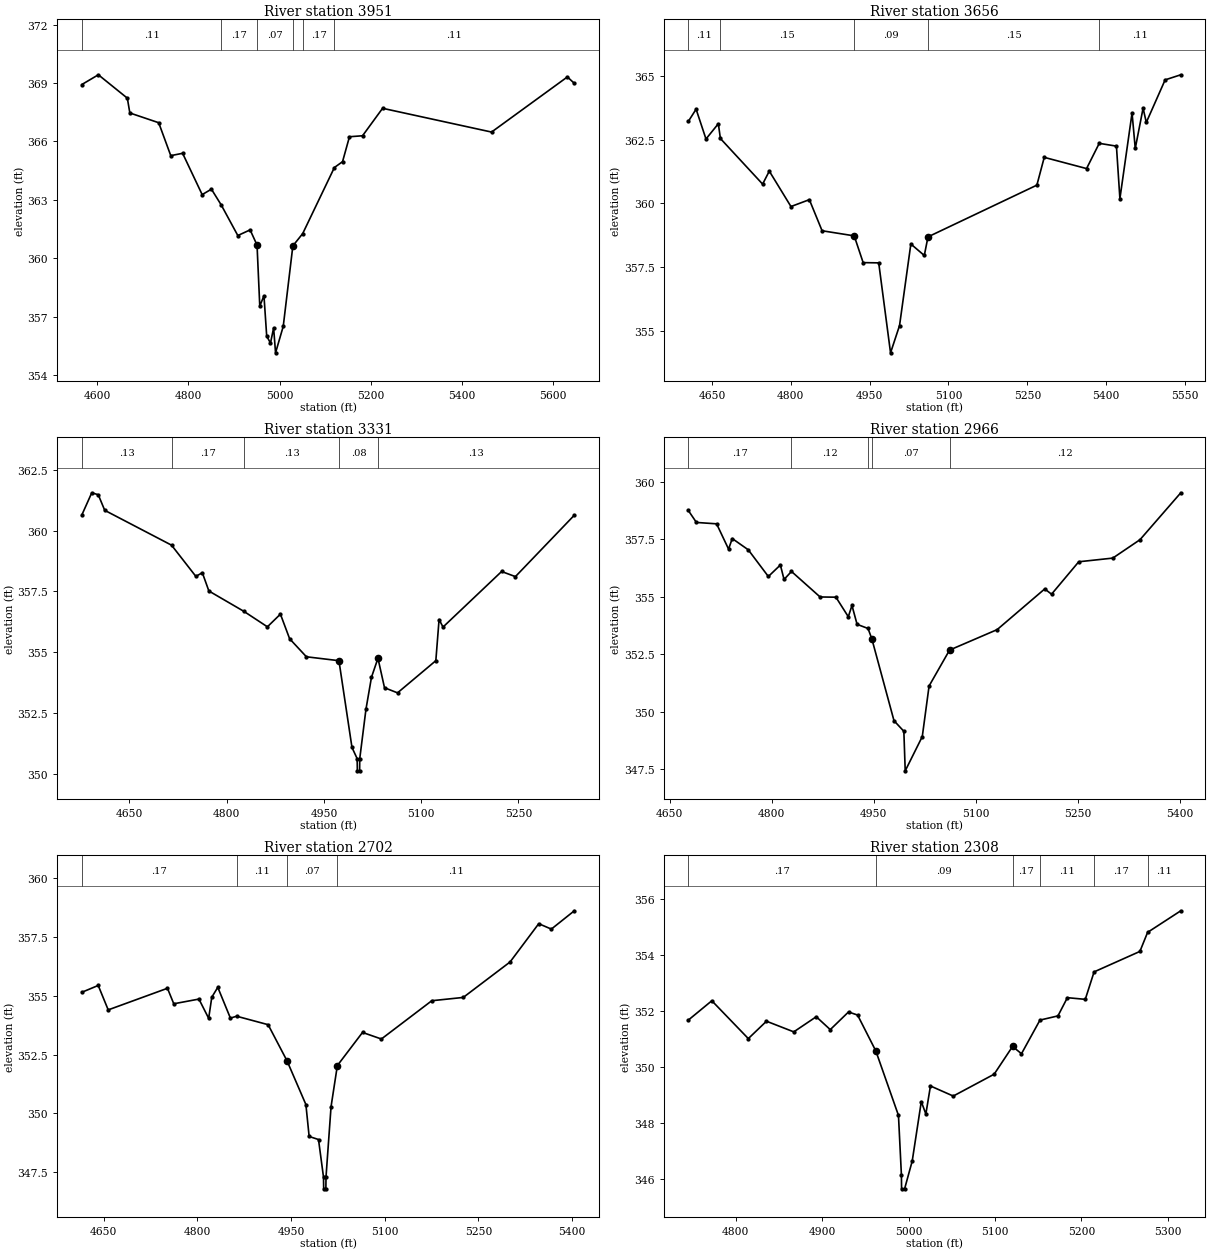
Type RM Length L Ch R = 1 ,3951    ,295,295,295
BEGIN DESCRIPTION:
WFSJR 063 5.0
END DESCRIPTION:
XS GIS Cut Line= 3
      3706783.98     10237671.09      3706692.25     10237392.46
      3706266.64     10236730.17
#Sta/Elev= 30
  4566.1  368.92  4602.3  369.42  4665.9  368.22  4671.4  367.46  4734.7  366.96
  4761.2  365.27  4787.2  365.39  4830.1  363.27  4850.4  363.55  4871.9  362.74
  4908.3  361.17  4935.3  361.46  4950.5  360.68  4956.5  357.55  4965.7  358.08
  4971.7  356.01    4980  355.65  4986.9  356.43  4991.1  355.15    5008  356.51
  5029.1  360.64  5050.7  361.27  5120.2  364.66  5138.1  364.96  5153.3  366.24
    5182  366.29    5226   367.7  5465.1  366.48  5631.5  369.31  5646.7  368.98
#Mann= 6 ,-1 , 0
  4566.1     .11       0  4871.9     .17       0  4950.5     .07       0
  5029.1     .11       0  5050.7     .17       0  5120.2     .11       0
Bank Sta=4950.5,5029.1
XS Rating Curve= 0 ,0
Exp/Cntr=0.3,0.1

Type RM Length L Ch R = 1 ,3656    ,325,325,325
BEGIN DESCRIPTION:
WFSJR 063 4.0
END DESCRIPTION:
XS GIS Cut Line= 3
      3707016.63     10237494.04      3706849.95     10237077.36
        3706573.     10236675.78
#Sta/Elev= 30
  4605.2  363.21    4620  363.69  4638.8  362.52  4662.3  363.12  4666.2  362.54
  4746.5  360.75  4759.2  361.26  4800.4  359.87  4835.4  360.14  4859.6  358.92
  4920.7  358.72  4937.7  357.67  4967.3  357.66  4989.8  354.13  5006.9   355.2
  5028.4   358.4    5054  357.95    5061  358.68  5268.1  360.71  5282.1   361.8
  5362.6  361.36  5386.7  362.35  5419.4  362.24    5426  360.18  5449.1  363.54
  5455.2  362.15  5470.1  363.73  5476.2  363.17    5512  364.84  5541.8  365.04
#Mann= 5 ,-1 , 0
  4605.2     .11       0  4666.2     .15       0  4920.7     .09       0
    5061     .15       0  5386.7     .11       0
Bank Sta=4920.7,5061
XS Rating Curve= 0 ,0
Exp/Cntr=0.3,0.1

Type RM Length L Ch R = 1 ,3331    ,365,365,365
BEGIN DESCRIPTION:
Mapping XS 901c870f
END DESCRIPTION:
XS GIS Cut Line= 2
      3707145.09     10237466.29      3707211.07     10236709.26
#Sta/Elev= 30
  4576.5  360.64  4591.8  361.55  4601.8  361.47  4611.8  360.83  4714.9   359.4
  4752.4  358.12  4762.4  358.27  4772.5  357.52  4826.8  356.68  4862.8  356.05
  4882.9  356.57  4897.1  355.56    4923  354.82  4973.2  354.66  4993.3   351.1
  5001.3  350.64  5001.6  350.14  5005.1  350.14  5005.3  350.64  5014.9  352.67
  5023.4  353.98  5033.4  354.76  5043.5  353.55  5063.6  353.34  5122.7  354.66
  5127.7  356.35  5133.8  356.04  5224.2  358.32  5245.5  358.11  5336.4  360.63
#Mann= 5 ,-1 , 0
  4576.5     .13       0  4714.9     .17       0  4826.8     .13       0
  4973.2     .08       0  5033.4     .13       0
Bank Sta=4973.2,5033.4
XS Rating Curve= 0 ,0
Exp/Cntr=0.3,0.1

Type RM Length L Ch R = 1 ,2966    ,264,264,264
BEGIN DESCRIPTION:
WFSJR 063 3.0
END DESCRIPTION:
XS GIS Cut Line= 3
      3707329.12      10237459.3      3707455.79      10237162.6
      3707467.85     10236761.08
#Sta/Elev= 30
  4677.4  358.76  4689.3  358.24    4719  358.18  4736.6  357.08    4742  357.54
  4765.6  357.05  4795.1  355.89  4812.8  356.39  4818.2  355.76  4829.1  356.11
  4871.2     355  4894.5  354.99  4912.7  354.14  4918.1  354.63  4925.6  353.81
  4941.7  353.63  4947.3  353.18  4979.9  349.62  4994.4  349.16  4996.4  347.44
  5021.5  348.93  5031.5  351.13  5061.6  352.69  5131.6  353.58  5201.6  355.35
  5211.6  355.12  5251.6  356.53  5301.7  356.69  5341.7  357.49  5401.7  359.53
#Mann= 5 ,-1 , 0
  4677.4     .17       0  4829.1     .12       0  4941.7     .11       0
  4947.3     .07       0  5061.6     .12       0
Bank Sta=4947.3,5061.6
XS Rating Curve= 0 ,0
Exp/Cntr=0.3,0.1

Type RM Length L Ch R = 1 ,2702    ,394,394,394
BEGIN DESCRIPTION:
WFSJR 063 2.0
END DESCRIPTION:
XS GIS Cut Line= 2
      3707738.22     10237507.08      3707639.95     10236724.53
#Sta/Elev= 30
    4615  355.15  4641.2  355.44  4657.2   354.4  4752.1  355.32  4762.2  354.66
  4802.5  354.86  4818.1  354.04  4823.1  354.94  4832.7  355.36  4852.9  354.05
  4862.9  354.13  4913.3  353.77  4943.6  352.23  4973.8  350.37    4979  349.01
    4994  348.88    5002  347.28  5002.3  346.78  5005.8  346.78    5006  347.28
  5014.1  350.28  5024.2  352.03  5064.5  353.44  5094.7  353.16  5175.4  354.79
  5225.8  354.93  5300.8  356.44  5346.7  358.07  5366.9  357.84  5403.7  358.62
#Mann= 4 ,-1 , 0
    4615     .17       0  4862.9     .11       0  4943.6     .07       0
  5024.2     .11       0
Bank Sta=4943.6,5024.2
XS Rating Curve= 0 ,0
Exp/Cntr=0.3,0.1

Type RM Length L Ch R = 1 ,2308    ,685,685,685
BEGIN DESCRIPTION:
Mapping XS e8442cc8
END DESCRIPTION:
XS GIS Cut Line= 2
      3708099.31     10237336.92      3707920.06     10236796.15
#Sta/Elev= 30
  4745.2  351.67  4772.4  352.36  4814.6  351.01  4835.6  351.63  4867.2  351.25
  4893.2  351.79  4909.4  351.33  4930.5  351.96    4941  351.85  4962.1  350.57
  4988.3  348.27  4991.7  346.15  4991.9  345.65  4995.4  345.65  5004.2  346.64
  5014.7  348.76    5020  348.32  5025.3  349.32  5051.7  348.96    5099  349.74
  5120.3  350.73  5130.6  350.47    5152  351.67  5172.8  351.82  5183.7  352.47
  5204.4  352.41  5214.6  353.39  5267.6  354.12  5276.5   354.8  5314.9  355.57
#Mann= 6 ,-1 , 0
  4745.2     .17       0  4962.1     .09       0  5120.3     .17       0
    5152     .11       0  5214.6     .17       0  5276.5     .11       0
Bank Sta=4962.1,5120.3
XS Rating Curve= 0 ,0
Exp/Cntr=0.3,0.1

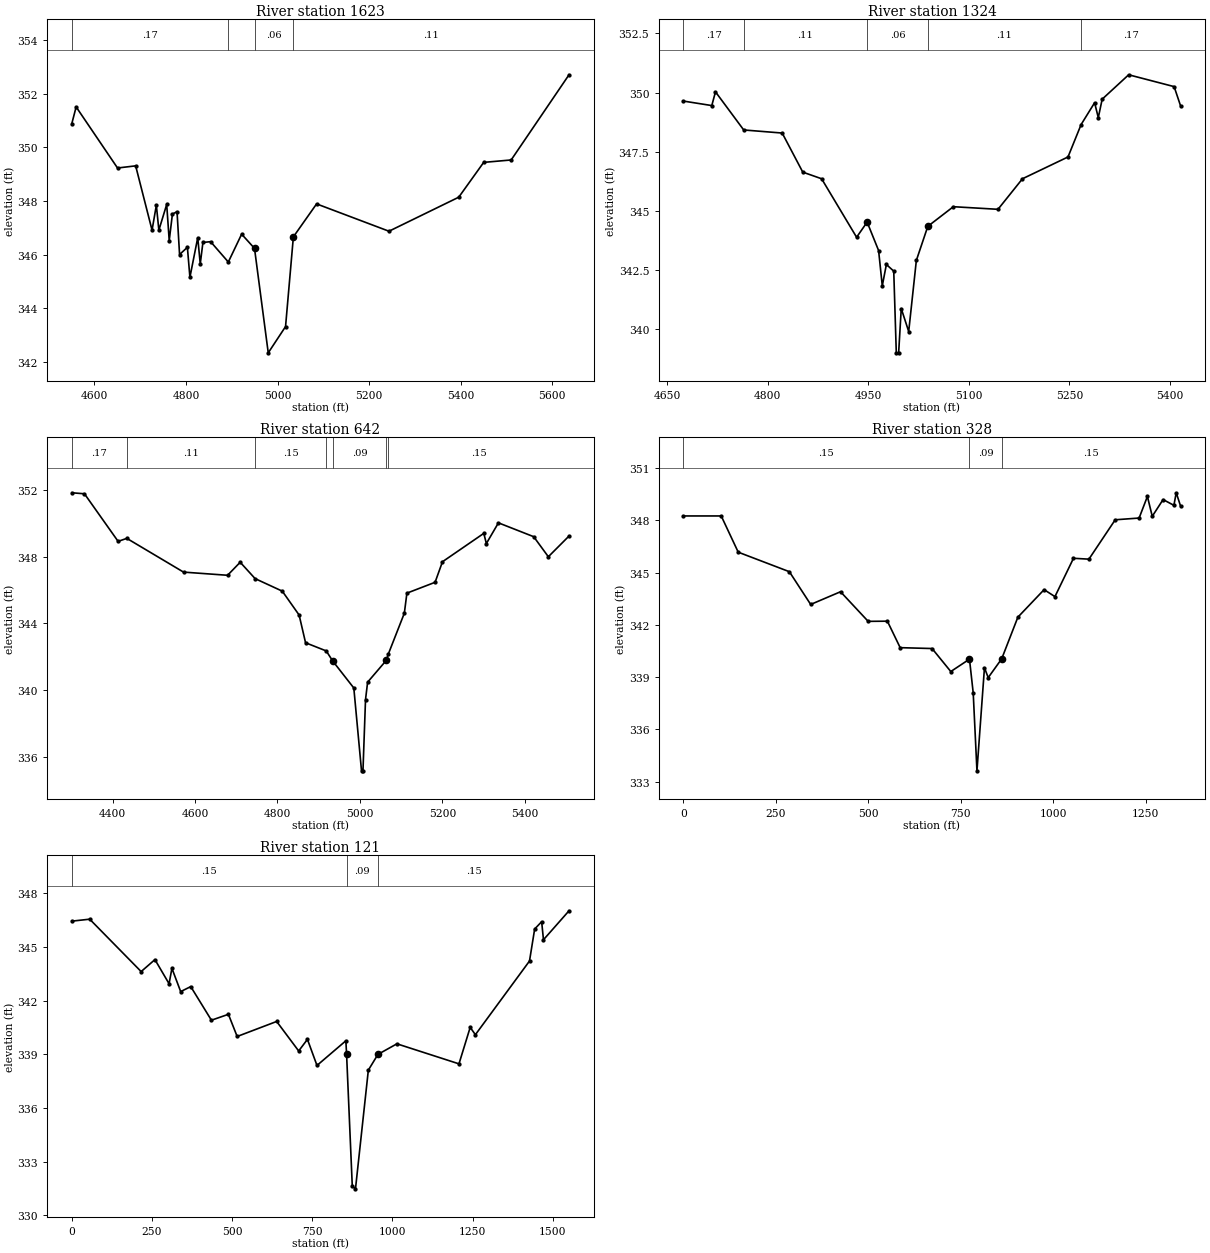
Type RM Length L Ch R = 1 ,1623    ,299,299,299
BEGIN DESCRIPTION:
Mapping XS 40b17007
END DESCRIPTION:
XS GIS Cut Line= 3
      3708220.83     10237488.82      3708533.76     10236841.68
      3708196.75     10236695.95
#Sta/Elev= 30
  4550.6  350.89    4560  351.51  4650.4  349.23    4690  349.31  4725.8  346.91
  4735.2  347.84  4740.7  346.91  4757.8  347.87  4763.3  346.52  4770.3  347.51
  4780.4   347.6  4785.9     346    4803  346.27  4808.5  345.15  4825.6  346.63
  4831.1  345.65  4836.9  346.45  4853.7  346.48  4892.4  345.72  4921.5  346.76
  4949.6  346.23  4979.6  342.33  5017.4  343.31  5034.5  346.66  5085.2  347.89
  5243.3  346.87  5395.7  348.14  5450.2  349.44  5510.2  349.53  5636.6  352.71
#Mann= 4 ,-1 , 0
  4550.6     .17       0  4892.4     .11       0  4949.6     .06       0
  5034.5     .11       0
Bank Sta=4949.6,5034.5
XS Rating Curve= 0 ,0
Exp/Cntr=0.3,0.1

Type RM Length L Ch R = 1 ,1324    ,682,682,682
BEGIN DESCRIPTION:
Mapping XS 1c251b4f
END DESCRIPTION:
XS GIS Cut Line= 2
      3708494.28     10237573.85      3708816.18     10236905.76
#Sta/Elev= 30
  4674.1  349.64  4716.5  349.45    4722  350.03  4764.1  348.42  4821.5  348.29
  4852.2  346.64  4880.3  346.36  4932.5  343.89  4948.2  344.53  4965.3  343.33
  4970.8  341.84  4976.9  342.74  4987.9  342.46  4991.7  339.01  4995.2  339.01
  4999.1  340.88  5010.2  339.91  5021.6  342.91  5038.7  344.35  5076.8  345.18
  5143.4  345.07  5179.9  346.36  5247.8  347.28  5267.4  348.65  5287.5  349.57
    5293  348.94  5298.8  349.72  5338.3  350.75  5406.1  350.25  5415.7  349.44
#Mann= 5 ,-1 , 0
  4674.1     .17       0  4764.1     .11       0  4948.2     .06       0
  5038.7     .11       0  5267.4     .17       0
Bank Sta=4948.2,5038.7
XS Rating Curve= 0 ,0
Exp/Cntr=0.3,0.1

Type RM Length L Ch R = 1 ,642     ,314,314,314
BEGIN DESCRIPTION:
WFSJR 063 1.0
END DESCRIPTION:
XS GIS Cut Line= 3
      3709017.85     10237961.08      3709196.09     10237099.93
      3708932.69     10236906.16
#Sta/Elev= 30
    4301  351.82  4331.6  351.76  4413.3  348.91  4434.4  349.09    4572  347.07
  4678.9  346.88  4709.5  347.66  4745.7  346.68  4811.6  345.93  4852.5   344.5
  4868.1  342.84  4918.3  342.35  4934.2  341.74  4985.2  340.13  5003.9  335.17
  5007.4  335.17  5013.6  339.44  5018.7  340.48  5063.8  341.78  5068.9  342.16
  5107.8  344.61    5114  345.81  5182.4  346.46  5200.3  347.69  5300.6  349.39
  5306.8  348.78  5336.1  350.02  5421.7  349.19  5457.2  347.99  5507.4  349.23
#Mann= 7 ,-1 , 0
    4301     .17       0  4434.4     .11       0  4745.7     .15       0
  4918.3     .12       0  4934.2     .09       0  5063.8     .12       0
  5068.9     .15       0
Bank Sta=4934.2,5063.8
XS Rating Curve= 0 ,0
Exp/Cntr=0.3,0.1

Type RM Length L Ch R = 1 ,328     ,207,207,207
XS GIS Cut Line= 4
       3709135.1     10237949.86       3709447.6     10237402.98
      3709413.74     10237173.82      3709025.72     10236887.36
#Sta/Elev= 30
       0  348.25   102.3  348.25   148.3  346.17   286.5  345.05   344.1  343.17
   424.8   343.9   499.5   342.2   551.4  342.21     586  340.69   672.2  340.64
   722.8  339.32   773.3  340.03   783.4  338.09   793.5  333.62   813.8  339.54
   823.9  338.97   860.4  340.05   904.1  342.44     975  344.02  1004.3  343.62
  1054.4  345.82  1096.1  345.77  1167.2  348.03  1231.8  348.13  1254.2  349.37
  1267.3  348.23  1296.6  349.19  1325.8  348.86  1332.1  349.58  1343.8  348.82
#Mann= 3 , 0 , 0
       0     .15       0   773.3     .09       0   860.4     .15       0
Bank Sta=773.3,860.4
XS Rating Curve= 0 ,0
Exp/Cntr=0.3,0.1

Type RM Length L Ch R = 1 ,121     ,0,0,0
XS GIS Cut Line= 4
      3709224.18     10237963.14      3709604.39     10237310.36
      3709613.88     10237093.29      3709106.13     10236815.57
#Sta/Elev= 30
       0  346.45    55.7  346.56   216.2  343.63   259.2   344.3   303.3  342.95
   312.2  343.81   339.5  342.51   370.9  342.79   435.4  340.91   488.4  341.24
   515.7     340   638.9  340.84   707.6  339.19   734.9  339.84   764.7  338.38
   854.8  339.76     857 339.014   874.8  331.63   884.8  331.48   924.9  338.12
   954.9     339    1014  339.59  1207.6  338.47  1242.6  340.51  1258.8   340.1
  1427.6  344.22  1443.7  346.01  1465.5  346.42  1471.2  345.41  1550.9  347.03
#Mann= 3 , 0 , 0
       0     .15       0     857     .09       0   954.9     .15       0
Bank Sta=857,954.9
XS Rating Curve= 0 ,0
Exp/Cntr=0.3,0.1

Chan Stop Cuts=-1
Use User Specified Reach Order=0
Composite Channel Slope=5