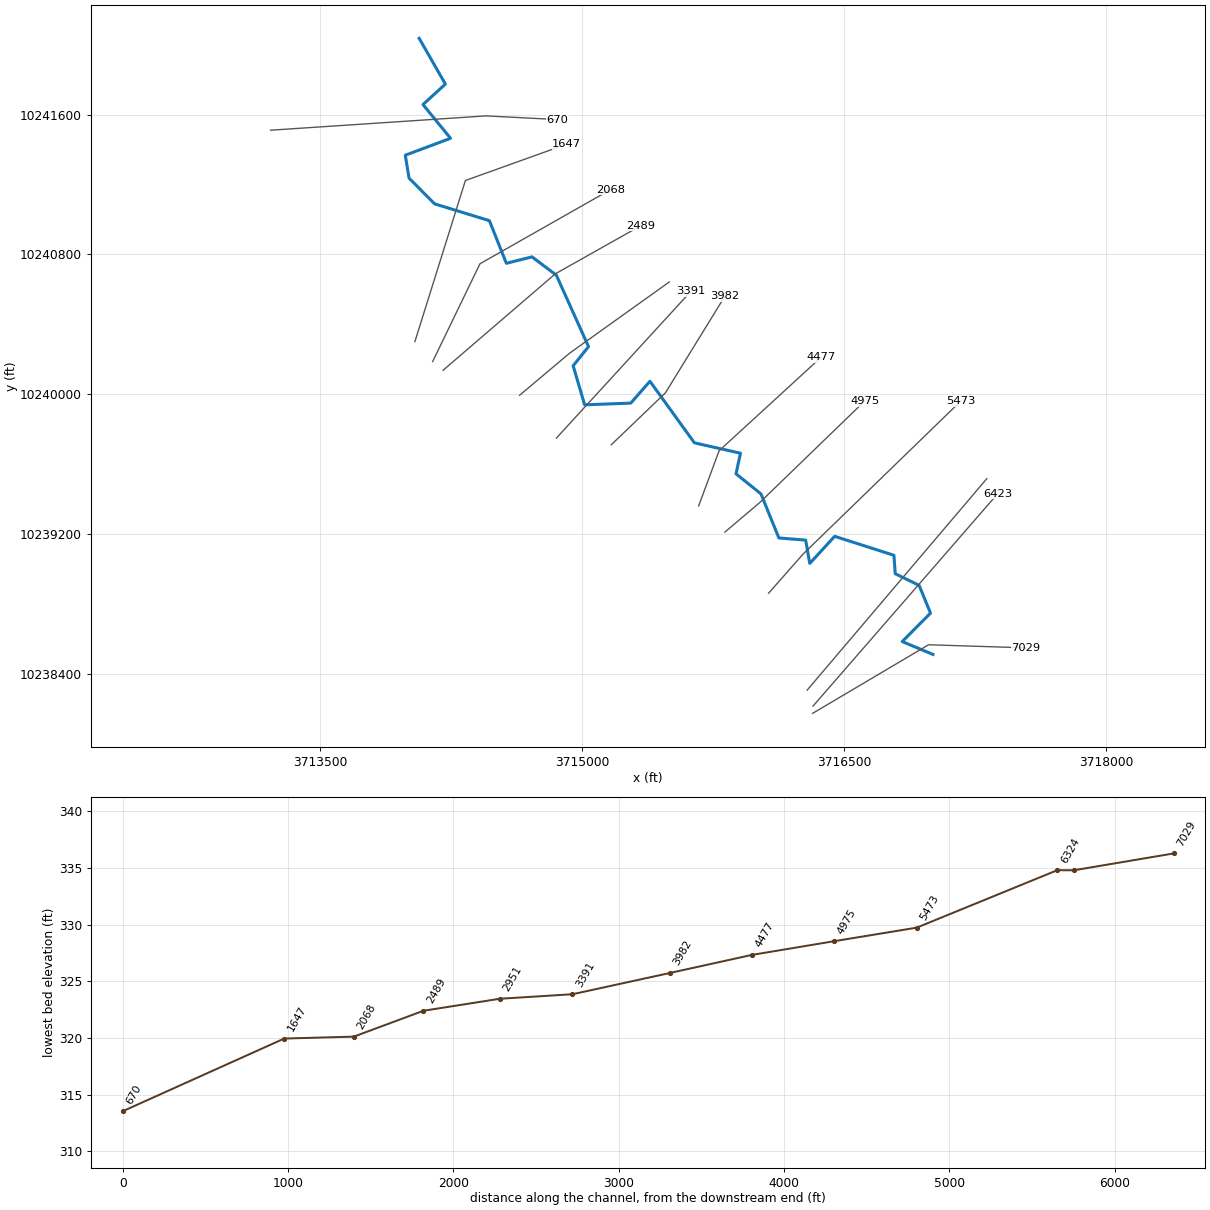
--- WFSJR 064.prj (project) ---

Proj Title=WFSJR 064 Base Level Engineering
Current Plan=p01
Default Exp/Contr=0.3,0.1
English Units
Geom File=g01
Flow File=f01
Plan File=p01
Y Axis Title=Elevation
X Axis Title(PF)=Main Channel Distance
X Axis Title(XS)=Station
BEGIN DESCRIPTION:
WFSJR 064
END DESCRIPTION:
DSS Export Rating Curves= 0
DSS Export Rating Curve Sorted= 0
DSS Export Volume Flow Curves= 0
DXF OffsetX= 0
DXF OffsetY= 0
DXF ScaleX= 1
DXF ScaleY= 10

--- WFSJR 064.p01 (plan) ---

Plan Title=Multiple Run
Program Version=4.10
Short Identifier=Multiple
Geom File=g01
Flow File=f01
Subcritical Flow
K Sum by GR= 0
Std Step Tol= 0.01
Critical Tol= 0.01
Num of Std Step Trials= 20
Max Error Tol= 0.3
Flow Tol Ratio= 0.001
Split Flow NTrial= 30
Split Flow Tol= 0.02
Split Flow Ratio= 0.02
Log Output Level= 0
Friction Slope Method= 1
Unsteady Friction Slope Method= 2
Unsteady Bridges Friction Slope Method= 1
Parabolic Critical Depth
Global Vel Dist= 1 , 1 , 1
Global Log Level= 0
CheckData=True
Encroach Param=-1 ,0,0, 0
BEGIN DESCRIPTION:
Multiple Run
END DESCRIPTION:
Computation Interval=1HOUR
Output Interval=1HOUR
Run HTab= 0
Run UNet= 0
Run PostProcess= 0
Run WQNet= 0
UNET Theta= 1
UNET Theta Warmup= 1
UNET ZTol= 0.02
UNET ZSATol= 0.05
UNET MxIter= 20
UNET MaxInSteps= 0
UNET DtIC= 0
UNET DtMin= 0
UNET MaxCRTS= 20
UNET WFStab= 2
UNET SFStab= 1
UNET WFX= 1
UNET SFX= 1
UNET DSS MLevel= 4
UNET DZMax Abort= 100
UNET Convert EG Bridges= 0
UNET Use Existing IB Tables=-1
UNET Froude Reduction=False
UNET Froude Limit= 1
UNET Froude Power= 10
UNET Time Slicing=0,0, 5
UNET Junction Losses=0
Instantaneous Interval=1HOUR
Write IC File= 0
Write IC File at Sim End=0
Echo Input=False
Echo Parameters=False
Echo Output=False
Write Detailed= 0
WQ AD Non Conservative
WQ ULTIMATE=-1
WQ Max Comp Step=1HOUR
WQ Output Interval=15MIN
WQ Output Selected Increments= 0
WQ Output face flow=0
WQ Output face velocity=0
WQ Output face area=0
WQ Output face dispersion=0
WQ Output cell volume=0
WQ Output cell surface area=0
WQ Output cell continuity=0
WQ Output cumulative cell continuity=0
WQ Output face conc=0
WQ Output face dconc_dx=0
WQ Output face courant=0
WQ Output face peclet=0
WQ Output face adv mass=0
WQ Output face disp mass=0
WQ Output cell mass=0
WQ Output cell source sink temp=0
WQ Output cell source sink nsm=0
WQ Output MaxMinRange=-1
WQ Daily Max Min Mean=-1
WQ Daily Range=0
WQ Daily Time=0
WQ Create Restart=0
WQ Fixed Restart=0
WQ System Summary=0
WQ Use Fixed Temperature=0
Sorting and Armoring Iterations= 10
XS Update Threshold= 0.02
Hydraulics Update Threshold= 0.02
Energy Slope Method= 1
Volume Change Method= 0
XS Weighting Method= 0
Number of US Weighted Cross Sections= 1
Number of DS Weighted Cross Sections= 1
Upstream XS Weight=0.25
Main XS Weight=0.5
Downstream XS Weight=0.25
Number of DS XS's Weighted with US Boundary= 1
Upstream Boundary Weight= 1
Weight of XSs Associated with US Boundary= 0
Number of US XS's Weighted with DS Boundary= 1
Downstream Boundary Weight= 0.5
Weight of XSs Associated with DS Boundary= 0.5
Sediment Output Level= 4
Mass or Volume Output= 0
Output Increment Type= 1
Profile and TS Output Increment= 10
XS Output Flag= 0
XS Output Increment= 10
Disregard all LS=0
Disregard all Conn=0
Disregard all Breaches=0
Disregard all Pumps=0

--- WFSJR 064.f01 (steady flow) ---

Flow Title=Multiple
Program Version=4.10
Number of Profiles= 7
Profile Names=10-year,25-year,50-year,1pct_min,100-year,1pct_plu,500-year
River Rch & RM=WFSJR 064,Reach-1         ,7029
     385     506     672     294     887    2679    1594
River Rch & RM=WFSJR 064,Reach-1         ,6423
     602     812    1094     484    1463    4418    2707
Boundary for River Rch & Prof#=WFSJR 064,Reach-1         , 1
Up Type= 0
Dn Type= 3
Dn Slope=0.003
Boundary for River Rch & Prof#=WFSJR 064,Reach-1         , 2
Up Type= 0
Dn Type= 3
Dn Slope=0.003
Boundary for River Rch & Prof#=WFSJR 064,Reach-1         , 3
Up Type= 0
Dn Type= 3
Dn Slope=0.003
Boundary for River Rch & Prof#=WFSJR 064,Reach-1         , 4
Up Type= 0
Dn Type= 3
Dn Slope=0.003
Boundary for River Rch & Prof#=WFSJR 064,Reach-1         , 5
Up Type= 0
Dn Type= 3
Dn Slope=0.003
Boundary for River Rch & Prof#=WFSJR 064,Reach-1         , 6
Up Type= 0
Dn Type= 3
Dn Slope=0.003
Boundary for River Rch & Prof#=WFSJR 064,Reach-1         , 7
Up Type= 0
Dn Type= 3
Dn Slope=0.003
DSS Import GetInterval= 0
DSS Import GetPeak= 0
DSS Import FillOption= 0

--- WFSJR 064.g01 (geometry) ---

Geom Title=Existing Conditions
Program Version=4.10

River Reach=WFSJR 064       ,Reach-1
Reach XY= 30
      3717008.66     10238510.96      3716832.88     10238584.74
      3716994.55      10238747.5      3716929.46     10238906.26
      3716792.75     10238972.93      3716785.19      10239078.4
      3716446.21     10239186.85      3716303.54     10239031.75
      3716280.07     10239165.25      3716126.88     10239177.63
      3716024.15     10239429.94      3715881.53     10239544.55
       3715907.1     10239662.52       3715643.5      10239721.9
      3715388.99     10240074.25      3715279.19     10239949.28
       3715015.3      10239939.4      3714949.53      10240162.8
      3715037.53     10240272.49      3714853.22     10240681.64
      3714713.92     10240786.24      3714567.27      10240749.3
      3714470.25     10240993.34      3714156.51     10241089.77
      3714010.26     10241236.89      3713988.84     10241367.96
      3714247.93     10241464.87      3714089.95     10241657.74
      3714218.29     10241775.05      3714068.23     10242036.84

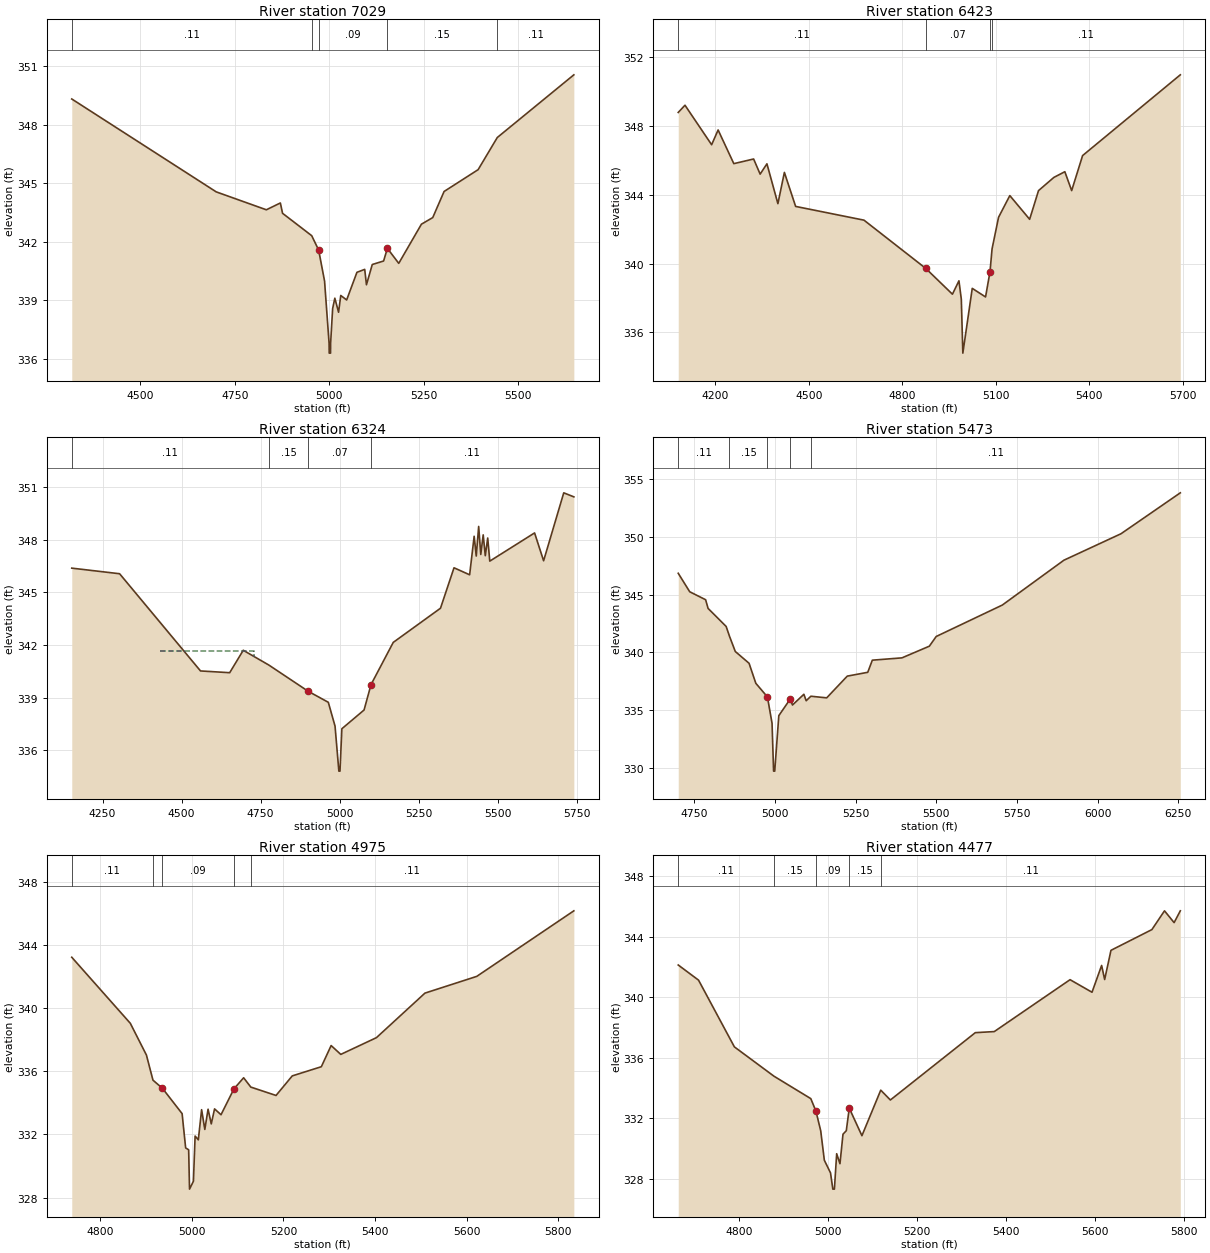
Type RM Length L Ch R = 1 ,7029    ,606,606,606
BEGIN DESCRIPTION:
WFSJR 064 14.0
END DESCRIPTION:
XS GIS Cut Line= 3
      3716319.78     10238173.67      3716983.61     10238566.34
      3717541.16     10238548.69
#Sta/Elev= 30
  4318.6  349.33    4701  344.56  4833.7  343.64  4870.8  343.99  4876.6  343.46
  4953.8  342.31  4972.2  341.57  4987.8  339.98  4999.8  336.78  5000.1  336.28
  5003.6  336.28  5003.8  336.78  5009.2  338.57    5015   339.1  5024.9  338.38
  5030.7  339.24  5046.3  339.01  5073.5  340.43  5094.1  340.58  5098.7  339.79
  5114.1  340.83  5144.1  341.01  5154.1  341.66  5184.2  340.89  5244.2   342.9
  5274.2  343.24  5304.2  344.58  5394.3   345.7    5445  347.35  5647.7  350.57
#Mann= 5 ,-1 , 0
  4318.6     .11       0  4953.8     .15       0  4972.2     .09       0
  5154.1     .15       0    5445     .11       0
Bank Sta=4972.2,5154.1
XS Rating Curve= 0 ,0
Exp/Cntr=0.3,0.1

Type RM Length L Ch R = 1 ,6423    ,99,99,99
BEGIN DESCRIPTION:
WFSJR 064 13.0
END DESCRIPTION:
XS GIS Cut Line= 2
      3716322.41     10238215.34      3717379.72      10239431.5
#Sta/Elev= 30
  4081.1   348.8  4102.8  349.22  4188.3  346.92  4209.1  347.78  4259.5  345.82
  4323.1  346.09    4344  345.21  4365.8  345.81    4401  343.49  4421.8  345.31
  4457.9  343.33  4677.3  342.53  4875.7  339.72  4961.2  338.22  4982.1     339
  4989.7  337.93  4994.6  334.79  5024.8  338.56  5067.5  338.06  5081.8  339.53
  5088.4  340.86  5109.3   342.7  5145.4  343.96    5209  342.58  5237.5  344.25
  5286.9  345.02    5322  345.35  5343.9  344.25    5379  346.29  5692.6  350.99
#Mann= 4 ,-1 , 0
  4081.1     .11       0  4875.7     .07       0  5081.8     .11       0
  5088.4     .11       0
Bank Sta=4875.7,5081.8
XS Rating Curve= 0 ,0
Exp/Cntr=0.3,0.1

Type RM Length L Ch R = 1 ,6324    ,851,851,851
BEGIN DESCRIPTION:
WFSJR 064 12.0
END DESCRIPTION:
XS GIS Cut Line= 2
      3716288.54     10238306.47      3717316.63     10239516.75
#Sta/Elev= 30
  4152.5  346.39  4303.8  346.07  4559.7  340.52    4652  340.42  4694.9   341.7
  4775.5  340.86  4900.2  339.36  4963.9  338.73  4985.2  337.37  4997.3   334.8
  5000.8   334.8  5006.8  337.22    5077  338.29    5099  339.74  5169.3  342.15
  5318.7   344.1  5361.5  346.41  5410.9  346.01  5425.2  348.21  5431.8  347.08
  5439.5  348.77  5446.1  347.17  5453.8  348.29  5460.4   347.1  5468.1  348.11
  5474.6  346.79  5616.3   348.4  5644.9  346.81  5708.6  350.69  5740.5  350.46
#Mann= 4 ,-1 , 0
  4152.5     .11       0  4775.5     .15       0  4900.2     .07       0
    5099     .11       0
#XS Ineff= 1 ,-1
    4430    4730  341.67
Permanent Ineff=
       F
Bank Sta=4900.2,5099
XS Rating Curve= 0 ,0
Exp/Cntr=0.3,0.1

Type RM Length L Ch R = 1 ,5473    ,498,498,498
BEGIN DESCRIPTION:
WFSJR 064 11.0
END DESCRIPTION:
XS GIS Cut Line= 3
      3716067.86     10238861.08      3716266.05     10239086.02
      3717167.88      10239961.1
#Sta/Elev= 30
  4700.2  346.85  4735.8  345.25  4785.1  344.56  4792.7  343.81  4848.7  342.25
  4859.1   341.4  4877.1  340.08  4919.8  339.06  4940.7  337.33  4976.7  336.15
    4991  333.87  4995.8  329.73  4999.3  329.73    5012  334.53  5047.2  335.96
  5054.4  335.45  5089.7  336.38  5096.8  335.82  5111.4  336.21  5160.4  336.07
  5224.2  337.95  5287.7  338.28  5301.9  339.33  5393.7  339.53  5478.6  340.54
  5499.9  341.38  5704.9   344.1  5895.8  347.98  6072.8  350.27  6256.6  353.81
#Mann= 5 ,-1 , 0
  4700.2     .11       0  4859.1     .15       0  4976.7     .09       0
  5047.2     .15       0  5111.4     .11       0
Bank Sta=4976.7,5047.2
XS Rating Curve= 0 ,0
Exp/Cntr=0.3,0.1

Type RM Length L Ch R = 1 ,4975    ,498,498,498
BEGIN DESCRIPTION:
WFSJR 064 10.0
END DESCRIPTION:
XS GIS Cut Line= 3
      3715817.89      10239211.1      3716018.09     10239380.87
      3716617.87     10239961.09
#Sta/Elev= 30
  4737.5  343.22  4865.4  339.04  4900.6  337.03  4914.9  335.44  4935.7  334.92
  4978.6  333.32  4986.3  331.15  4992.9  331.03  4994.8  328.54  5003.3  329.04
    5007   331.9    5014  331.66  5021.2  333.57  5028.2  332.32  5035.3   333.6
  5042.3  332.67  5049.5  333.62  5063.6  333.25  5091.9  334.89    5113  335.59
  5128.7     335  5183.8  334.47  5219.3  335.71  5282.8  336.29  5304.2  337.63
  5325.3  337.07  5403.2  338.13  5509.2  340.95  5622.4  342.01  5834.5  346.16
#Mann= 5 ,-1 , 0
  4737.5     .11       0  4914.9     .15       0  4935.7     .09       0
  5091.9     .15       0  5128.7     .11       0
Bank Sta=4935.7,5091.9
XS Rating Curve= 0 ,0
Exp/Cntr=0.3,0.1

Type RM Length L Ch R = 1 ,4477    ,495,495,495
BEGIN DESCRIPTION:
WFSJR 064 9.0
END DESCRIPTION:
XS GIS Cut Line= 3
      3715667.85     10239361.06      3715784.83     10239676.68
      3716367.87     10240211.08
#Sta/Elev= 30
  4663.4  342.14    4709  341.14  4789.5  336.73  4878.5  334.79  4961.1  333.31
  4972.7  332.48  4983.4  331.18  4991.5  329.24  5005.4   328.4  5010.6  327.33
  5014.1  327.33  5019.2  329.67  5026.6  329.01  5033.4  330.96  5040.8  331.19
  5047.5  332.68  5075.9  330.86  5118.2  333.87  5139.8  333.22  5330.6  337.67
  5373.1  337.74  5543.3  341.17  5592.6  340.34  5614.2  342.11    5621  341.18
  5635.2  343.11  5727.1  344.48  5755.4  345.72    5777  344.94  5790.9  345.72
#Mann= 5 ,-1 , 0
  4663.4     .11       0  4878.5     .15       0  4972.7     .09       0
  5047.5     .15       0  5118.2     .11       0
Bank Sta=4972.7,5047.5
XS Rating Curve= 0 ,0
Exp/Cntr=0.3,0.1

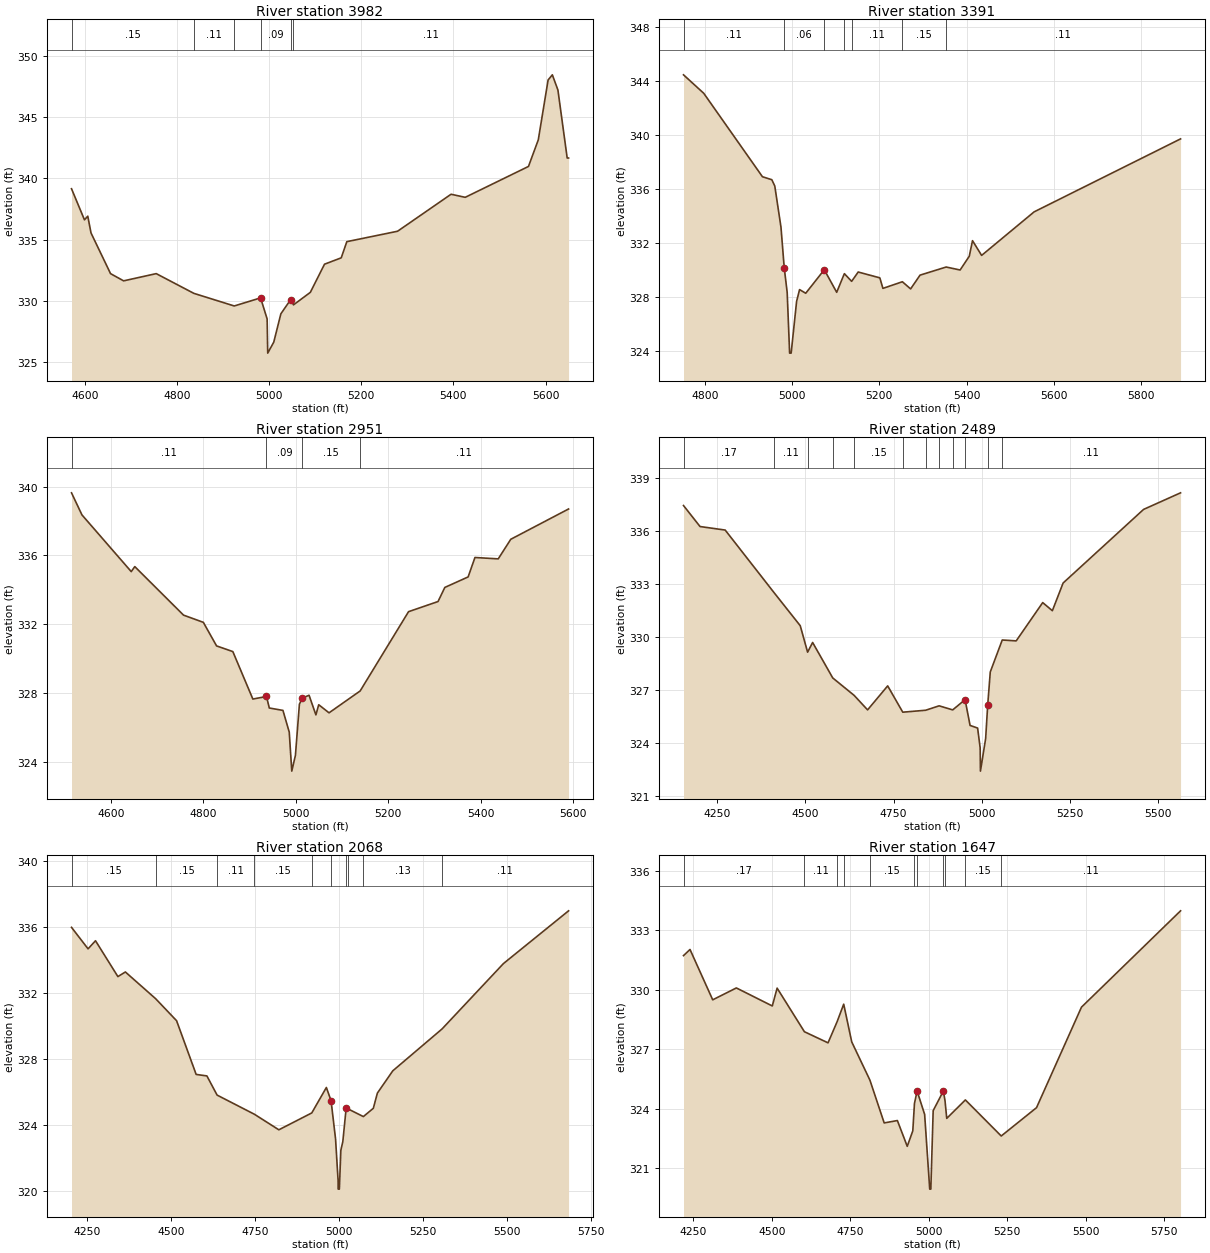
Type RM Length L Ch R = 1 ,3982    ,591,591,591
BEGIN DESCRIPTION:
WFSJR 064 8.0
END DESCRIPTION:
XS GIS Cut Line= 3
      3715167.89      10239711.1      3715477.31     10240007.68
      3715817.86     10240561.09
#Sta/Elev= 30
  4571.4  339.16  4599.5  336.62  4606.7  336.92  4613.7  335.55  4656.1  332.23
  4684.4  331.64  4755.2  332.23  4836.8  330.62  4924.5  329.59  4981.6  330.25
  4995.8  328.53  4997.1  325.74  5010.2  326.64  5025.6  328.95  5046.9  330.11
    5053  329.68  5089.5   330.7  5120.3     333  5156.6  333.52  5168.7  334.84
  5278.8  335.69  5394.8  338.71  5425.6  338.46  5562.8  340.98  5584.1  343.15
  5605.4  348.04  5614.6  348.46  5626.7  347.22  5646.8  341.67  5649.8  341.67
#Mann= 6 ,-1 , 0
  4571.4     .15       0  4836.8     .11       0  4924.5     .15       0
  4981.6     .09       0  5046.9     .15       0    5053     .11       0
Bank Sta=4981.6,5046.9
XS Rating Curve= 0 ,0
Exp/Cntr=0.3,0.1

Type RM Length L Ch R = 1 ,3391    ,440,440,440
BEGIN DESCRIPTION:
WFSJR 064 7.0
END DESCRIPTION:
XS GIS Cut Line= 2
      3714853.71     10239749.25      3715623.65     10240589.42
#Sta/Elev= 30
    4751  344.45  4797.5  343.08    4932  336.91  4953.5  336.69  4960.3  336.22
  4974.5  333.17  4981.9  330.18  4988.7  328.35  4994.3  323.86  4997.8  323.86
  5010.3  327.69  5017.1  328.56  5031.2  328.29  5073.8  330.03  5102.2  328.36
  5119.8  329.74  5136.5  329.17  5151.5  329.86  5201.1  329.43  5208.2  328.65
  5252.8  329.14  5271.7  328.61  5293.3  329.63  5353.2  330.23  5385.2  330.01
  5406.2  331.03  5413.6  332.18  5434.5  331.09  5554.8  334.31  5890.6  339.71
#Mann= 7 ,-1 , 0
    4751     .11       0  4981.9     .06       0  5073.8     .11       0
  5119.8     .15       0  5136.5     .11       0  5252.8     .15       0
  5353.2     .11       0
Bank Sta=4981.9,5073.8
XS Rating Curve= 0 ,0
Exp/Cntr=0.3,0.1

Type RM Length L Ch R = 1 ,2951    ,462,462,462
BEGIN DESCRIPTION:
WFSJR 064 6.0
END DESCRIPTION:
XS GIS Cut Line= 3
      3714642.73       10239994.       3714929.6     10240235.32
      3715499.54     10240642.46
#Sta/Elev= 30
  4514.7  339.64  4537.2  338.36  4643.9  335.06  4651.6  335.35    4757  332.53
  4799.9  332.11  4828.5  330.74  4863.7  330.41    4907  327.65  4936.5   327.8
  4942.6  327.13  4972.1  326.99  4985.7  325.73  4991.2  323.46  4999.1  324.38
  5007.7  327.35  5013.9  327.71  5028.6  327.87  5043.4  326.73  5049.5  327.32
  5071.8  326.85  5139.1  328.12  5243.8  332.73  5307.6  333.32  5322.3  334.14
  5372.7  334.75  5387.5  335.88  5437.8   335.8    5465  336.94    5590   338.7
#Mann= 4 ,-1 , 0
  4514.7     .11       0  4936.5     .09       0  5013.9     .15       0
  5139.1     .11       0
Bank Sta=4936.5,5013.9
XS Rating Curve= 0 ,0
Exp/Cntr=0.3,0.1

Type RM Length L Ch R = 1 ,2489    ,421,421,421
BEGIN DESCRIPTION:
WFSJR 064 5.0
END DESCRIPTION:
XS GIS Cut Line= 3
      3714205.24     10240137.24      3714846.72     10240688.64
      3715338.06     10240965.36
#Sta/Elev= 30
  4154.1  337.45    4201  336.26  4272.3  336.06  4411.1  332.51  4485.2  330.64
  4506.1  329.14  4520.3  329.69  4577.4  327.68  4638.2  326.69  4676.2  325.87
  4733.2  327.23    4776  325.74    4841  325.85  4879.1   326.1  4917.6  325.87
  4952.7  326.45  4966.9  324.99  4988.3  324.84  4995.5  323.72  4996.3   322.4
  5011.1  324.25  5016.8  326.12  5024.2  328.02  5058.1  329.83  5097.7  329.78
  5172.9  331.95  5200.3  331.49  5230.8  333.06    5459  337.23  5563.9  338.17
#Mann= 12 ,-1 , 0
  4154.1     .17       0  4411.1     .11       0  4506.1     .13       0
  4577.4     .15       0  4638.2     .15       0    4776     .15       0
    4841     .15       0  4879.1     .15       0  4917.6     .15       0
  4952.7     .09       0  5016.8     .15       0  5058.1     .11       0
Bank Sta=4952.7,5016.8
XS Rating Curve= 0 ,0
Exp/Cntr=0.3,0.1

Type RM Length L Ch R = 1 ,2068    ,421,421,421
BEGIN DESCRIPTION:
WFSJR 064 4.0
END DESCRIPTION:
XS GIS Cut Line= 3
      3714145.34     10240186.71      3714416.18     10240746.61
      3715163.23     10241170.89
#Sta/Elev= 30
  4202.9  335.96  4252.2  334.66  4274.4  335.15  4341.1  332.98  4363.4  333.26
  4453.7  331.64    4516  330.31  4574.3  327.06  4606.3  326.97  4636.7  325.81
  4747.9  324.65  4820.7  323.71  4918.8  324.73  4962.3  326.27  4976.3  325.47
  4989.7  323.15  4997.3  320.62  4997.5  320.12    5001  320.12  5005.5  322.48
  5011.3  322.99  5021.4  325.05  5027.2  324.97  5072.5  324.51  5102.2  325.01
  5114.3  325.93  5160.3  327.28  5306.9  329.81    5490  333.77    5684  336.96
#Mann= 10 ,-1 , 0
  4202.9     .15       0  4453.7     .15       0  4636.7     .11       0
  4747.9     .15       0  4918.8     .15       0  4976.3     .08       0
  5021.4     .11       0  5027.2     .15       0  5072.5     .13       0
  5306.9     .11       0
#XS Ineff= 1 ,-1
    4610  4962.3  326.27
Permanent Ineff=
       F
Bank Sta=4976.3,5021.4
XS Rating Curve= 0 ,0
Exp/Cntr=0.3,0.1

Type RM Length L Ch R = 1 ,1647    ,977,977,977
BEGIN DESCRIPTION:
WFSJR 064 3.0
END DESCRIPTION:
XS GIS Cut Line= 3
      3714043.79     10240301.31      3714332.84     10241223.17
      3714913.22     10241431.37
#Sta/Elev= 30
  4218.8  331.73  4239.5  332.04  4311.8   329.5  4387.1   330.1  4501.5  329.19
  4516.9  330.09  4603.8  327.89    4679  327.33    4708   328.4  4728.9  329.28
  4754.4  327.38  4812.3  325.45  4857.8  323.29  4899.8  323.41  4931.2  322.11
  4948.9  322.89  4954.2  324.27  4962.6   324.9  4986.6  323.72  5002.8  319.95
  5006.3  319.95  5013.8  323.91  5046.2   324.9  5051.5  324.41    5057  323.52
  5116.3  324.45  5230.5  322.63  5342.9  324.06    5486  329.13  5801.5  333.99
#Mann= 11 ,-1 , 0
  4218.8     .17       0  4603.8     .11       0    4708     .17       0
  4728.9     .11       0  4812.3     .15       0  4954.2     .12       0
  4962.6     .09       0  5046.2     .12       0  5051.5     .15       0
  5116.3     .15       0  5230.5     .11       0
#XS Ineff= 2 ,-1
    4785  4962.6   324.9  5046.2    5380   324.9
Permanent Ineff=
       T       T
Bank Sta=4962.6,5046.2
XS Rating Curve= 0 ,0
Exp/Cntr=0.3,0.1

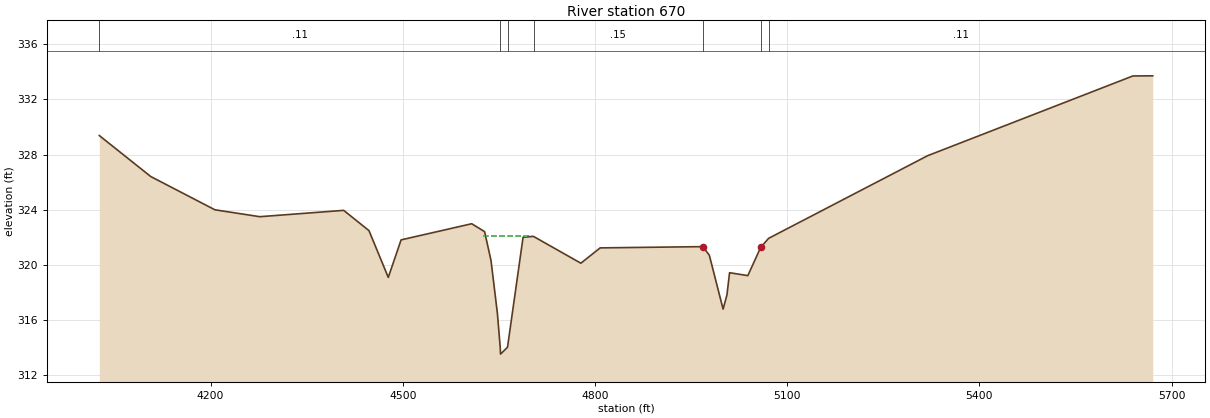
Type RM Length L Ch R = 1 ,670     ,0,0,0
BEGIN DESCRIPTION:
WFSJR 064 2.0
END DESCRIPTION:
XS GIS Cut Line= 3
      3713217.89     10241511.07      3714450.03     10241592.96
      3714858.84     10241572.13
#Sta/Elev= 30
  4026.4  329.38  4106.7  326.41  4206.8     324  4276.9   323.5  4407.8  323.96
  4447.3  322.49  4477.4   319.1  4497.4  321.82  4607.6  322.99  4627.7  322.42
  4637.7  320.34  4647.7   316.5  4652.1  314.04  4652.6  313.54  4663.5  314.04
  4687.8  322.01  4704.1  322.07    4778  320.13  4808.1  321.24  4968.4  321.33
  4978.5  320.71    5000   316.8    5006  317.83  5010.1  319.44  5038.6  319.23
  5058.6  321.27    5071  321.93  5319.2  327.92  5639.6   333.7  5670.6  333.71
#Mann= 7 ,-1 , 0
  4026.4     .11       0  4652.1     .12       0  4663.5     .11       0
  4704.1     .15       0  4968.4     .08       0  5058.6     .15       0
    5071     .11       0
#XS Ineff= 3 ,-1
    4400  4607.6  322.99    4625  4703.9  322.08    4725  4968.4  321.33
Permanent Ineff=
       T       T       F
Bank Sta=4968.4,5058.6
XS Rating Curve= 0 ,0
Exp/Cntr=0.3,0.1

Chan Stop Cuts=-1
Use User Specified Reach Order=0
Composite Channel Slope=5