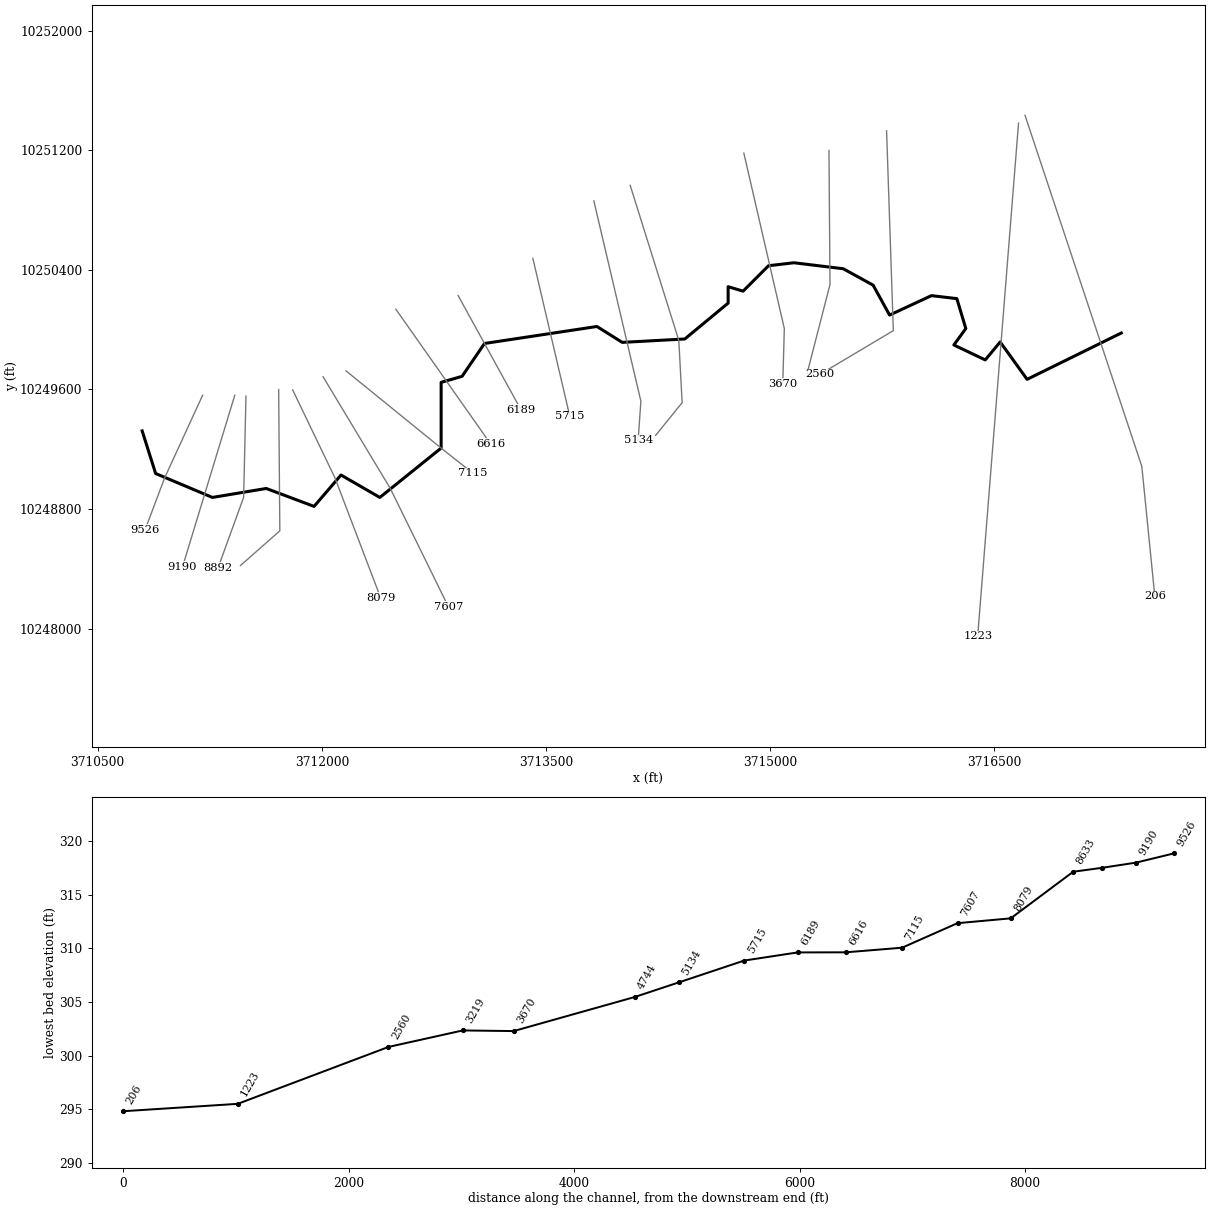
--- WFSJR 065.prj (project) ---

Proj Title=WFSJR 065 Base Level Engineering
Current Plan=p01
Default Exp/Contr=0.3,0.1
English Units
Geom File=g01
Flow File=f01
Plan File=p01
Y Axis Title=Elevation
X Axis Title(PF)=Main Channel Distance
X Axis Title(XS)=Station
BEGIN DESCRIPTION:
WFSJR 065
END DESCRIPTION:
DSS Export Rating Curves= 0
DSS Export Rating Curve Sorted= 0
DSS Export Volume Flow Curves= 0
DXF OffsetX= 0
DXF OffsetY= 0
DXF ScaleX= 1
DXF ScaleY= 10

--- WFSJR 065.p01 (plan) ---

Plan Title=Multiple Run
Program Version=4.10
Short Identifier=Multiple
Geom File=g01
Flow File=f01
Subcritical Flow
K Sum by GR= 0
Std Step Tol= 0.01
Critical Tol= 0.01
Num of Std Step Trials= 20
Max Error Tol= 0.3
Flow Tol Ratio= 0.001
Split Flow NTrial= 30
Split Flow Tol= 0.02
Split Flow Ratio= 0.02
Log Output Level= 0
Friction Slope Method= 1
Unsteady Friction Slope Method= 2
Unsteady Bridges Friction Slope Method= 1
Parabolic Critical Depth
Global Vel Dist= 1 , 1 , 1
Global Log Level= 0
CheckData=True
Encroach Param=-1 ,0,0, 0
BEGIN DESCRIPTION:
Multiple Run
END DESCRIPTION:
Computation Interval=1HOUR
Output Interval=1HOUR
Run HTab= 0
Run UNet= 0
Run PostProcess= 0
Run WQNet= 0
UNET Theta= 1
UNET Theta Warmup= 1
UNET ZTol= 0.02
UNET ZSATol= 0.05
UNET MxIter= 20
UNET MaxInSteps= 0
UNET DtIC= 0
UNET DtMin= 0
UNET MaxCRTS= 20
UNET WFStab= 2
UNET SFStab= 1
UNET WFX= 1
UNET SFX= 1
UNET DSS MLevel= 4
UNET DZMax Abort= 100
UNET Convert EG Bridges= 0
UNET Use Existing IB Tables=-1
UNET Froude Reduction=False
UNET Froude Limit= 1
UNET Froude Power= 10
UNET Time Slicing=0,0, 5
UNET Junction Losses=0
Instantaneous Interval=1HOUR
Write IC File= 0
Write IC File at Sim End=0
Echo Input=False
Echo Parameters=False
Echo Output=False
Write Detailed= 0
WQ AD Non Conservative
WQ ULTIMATE=-1
WQ Max Comp Step=1HOUR
WQ Output Interval=15MIN
WQ Output Selected Increments= 0
WQ Output face flow=0
WQ Output face velocity=0
WQ Output face area=0
WQ Output face dispersion=0
WQ Output cell volume=0
WQ Output cell surface area=0
WQ Output cell continuity=0
WQ Output cumulative cell continuity=0
WQ Output face conc=0
WQ Output face dconc_dx=0
WQ Output face courant=0
WQ Output face peclet=0
WQ Output face adv mass=0
WQ Output face disp mass=0
WQ Output cell mass=0
WQ Output cell source sink temp=0
WQ Output cell source sink nsm=0
WQ Output MaxMinRange=-1
WQ Daily Max Min Mean=-1
WQ Daily Range=0
WQ Daily Time=0
WQ Create Restart=0
WQ Fixed Restart=0
WQ System Summary=0
WQ Use Fixed Temperature=0
Sorting and Armoring Iterations= 10
XS Update Threshold= 0.02
Hydraulics Update Threshold= 0.02
Energy Slope Method= 1
Volume Change Method= 0
XS Weighting Method= 0
Number of US Weighted Cross Sections= 1
Number of DS Weighted Cross Sections= 1
Upstream XS Weight=0.25
Main XS Weight=0.5
Downstream XS Weight=0.25
Number of DS XS's Weighted with US Boundary= 1
Upstream Boundary Weight= 1
Weight of XSs Associated with US Boundary= 0
Number of US XS's Weighted with DS Boundary= 1
Downstream Boundary Weight= 0.5
Weight of XSs Associated with DS Boundary= 0.5
Sediment Output Level= 4
Mass or Volume Output= 0
Output Increment Type= 1
Profile and TS Output Increment= 10
XS Output Flag= 0
XS Output Increment= 10
Disregard all LS=0
Disregard all Conn=0
Disregard all Breaches=0
Disregard all Pumps=0

--- WFSJR 065.f01 (steady flow) ---

Flow Title=Multiple
Program Version=4.10
Number of Profiles= 7
Profile Names=10-year,25-year,50-year,1pct_min,100-year,1pct_plu,500-year
River Rch & RM=WFSJR 065,Reach-1         ,9526
     896    1226    1668     744    2248    6789    4226
Boundary for River Rch & Prof#=WFSJR 065,Reach-1         , 1
Up Type= 0
Dn Type= 3
Dn Slope=0.002
Boundary for River Rch & Prof#=WFSJR 065,Reach-1         , 2
Up Type= 0
Dn Type= 3
Dn Slope=0.002
Boundary for River Rch & Prof#=WFSJR 065,Reach-1         , 3
Up Type= 0
Dn Type= 3
Dn Slope=0.002
Boundary for River Rch & Prof#=WFSJR 065,Reach-1         , 4
Up Type= 0
Dn Type= 3
Dn Slope=0.002
Boundary for River Rch & Prof#=WFSJR 065,Reach-1         , 5
Up Type= 0
Dn Type= 3
Dn Slope=0.002
Boundary for River Rch & Prof#=WFSJR 065,Reach-1         , 6
Up Type= 0
Dn Type= 3
Dn Slope=0.002
Boundary for River Rch & Prof#=WFSJR 065,Reach-1         , 7
Up Type= 0
Dn Type= 3
Dn Slope=0.002
DSS Import GetInterval= 0
DSS Import GetPeak= 0
DSS Import FillOption= 0

--- WFSJR 065.g01 (geometry) ---

Geom Title=Existing Conditions
Program Version=4.10

River Reach=WFSJR 065       ,Reach-1
Reach XY= 30
      3710798.23     10249321.84      3710888.23     10249036.84
      3711268.23     10248876.84      3711628.23     10248936.84
      3711948.23     10248816.84      3712128.23     10249026.84
      3712388.23     10248876.84      3712798.23     10249206.84
      3712798.23     10249646.84      3712938.23     10249686.84
      3713088.23     10249906.84      3713840.42      10250020.5
       3714009.7     10249914.16      3714428.23     10249936.84
      3714718.23     10250176.84      3714718.23     10250286.84
      3714818.23     10250256.84      3714988.23     10250426.84
      3715158.23     10250446.84      3715488.23     10250406.84
      3715688.23     10250296.84      3715798.23     10250096.84
      3716078.23     10250226.84      3716248.23     10250206.84
      3716308.23     10250006.84      3716228.23     10249896.84
      3716438.23     10249796.84      3716538.23     10249916.84
      3716718.23     10249666.84      3717348.23     10249976.84

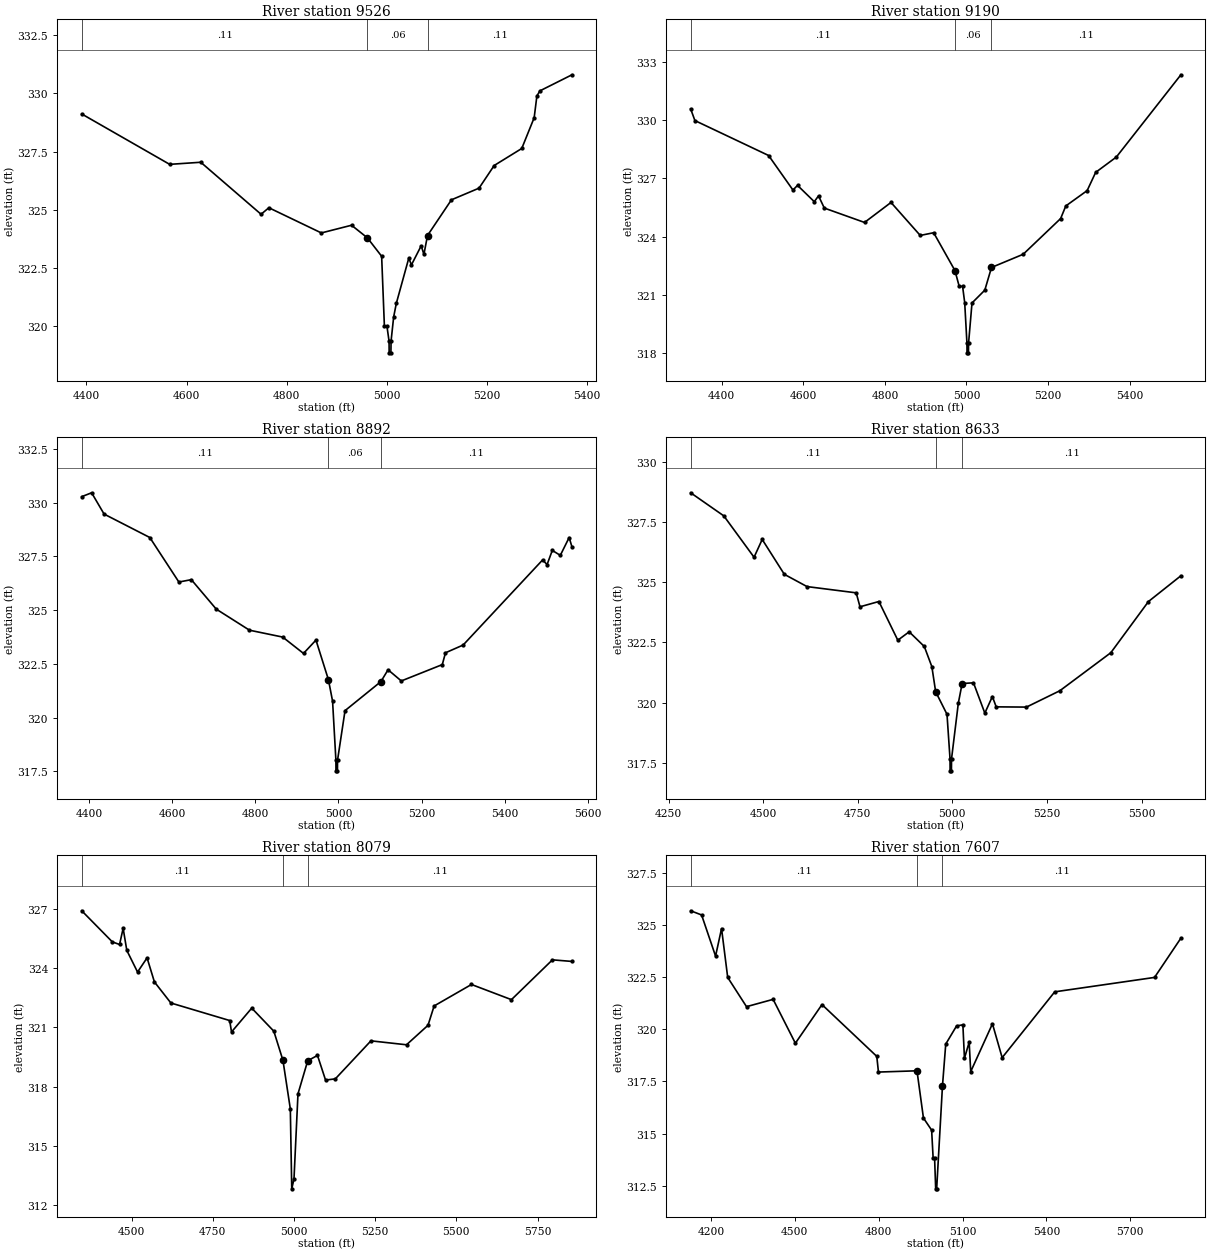
Type RM Length L Ch R = 1 ,9526    ,336,336,336
BEGIN DESCRIPTION:
WFSJR 065 13.0
END DESCRIPTION:
XS GIS Cut Line= 3
      3711202.76     10249560.65      3710948.23     10249006.84
      3710817.86     10248661.11
#Sta/Elev= 30
  4390.5  329.11  4566.1  326.95  4628.2  327.04  4748.6  324.81  4764.2  325.09
    4869  324.01  4929.3  324.34  4960.9   323.8  4989.4  323.01  4994.9  320.01
    5000  320.01  5004.2  319.37  5004.4  318.87  5007.9  318.87  5008.2  319.37
  5013.4  320.41  5018.7  320.99  5043.6  322.93  5048.9  322.64  5068.4  323.46
  5073.8  323.09    5081   323.9  5128.8  325.43  5183.9  325.93  5214.1   326.9
  5269.2  327.63    5294  328.95  5299.4  329.88  5305.4   330.1  5369.5  330.79
#Mann= 3 , 0 , 0
  4390.5     .11       0  4960.9     .06       0    5081     .11       0
Bank Sta=4960.9,5081
XS Rating Curve= 0 ,0
Exp/Cntr=0.3,0.1

Type RM Length L Ch R = 1 ,9190    ,298,298,298
BEGIN DESCRIPTION:
WFSJR 065 12.0
END DESCRIPTION:
XS GIS Cut Line= 2
      3711417.84     10249561.02      3711067.86      10248411.1
#Sta/Elev= 30
  4323.8  330.58  4334.2  329.98  4514.9  328.18  4574.6   326.4  4585.8  326.64
  4626.9   325.8  4637.3   326.1  4651.5  325.47  4750.1  324.73    4815  325.76
  4886.7  324.06  4919.6   324.2  4971.8  322.25  4982.3  321.43  4990.5  321.44
  4995.7   320.6  5001.2  318.51  5001.4  318.01  5004.9  318.01  5005.2  318.51
  5013.6  320.58    5045  321.24  5061.4  322.41  5139.1  323.09  5230.9  324.93
  5243.6  325.58  5295.9  326.37  5316.8  327.31  5367.5   328.1  5525.8  332.34
#Mann= 3 , 0 , 0
  4323.8     .11       0  4971.8     .06       0  5061.4     .11       0
Bank Sta=4971.8,5061.4
XS Rating Curve= 0 ,0
Exp/Cntr=0.3,0.1

Type RM Length L Ch R = 1 ,8892    ,259,259,259
BEGIN DESCRIPTION:
WFSJR 065 11.0
END DESCRIPTION:
XS GIS Cut Line= 3
       3711492.6     10249554.88      3711476.94     10248877.29
      3711305.55     10248404.68
#Sta/Elev= 30
  4381.8  330.28  4405.6  330.46  4435.6  329.47  4545.7  328.38  4615.7  326.31
  4645.7  326.42  4705.7  325.05  4785.7  324.07  4865.7  323.75  4915.8  322.99
  4945.8  323.61  4975.8  321.77  4985.8  320.77  4993.8  318.03    4994  317.53
  4997.5  317.53  4997.8  318.03  5015.8  320.33  5102.2  321.68  5119.4  322.23
  5151.3  321.71    5250  322.47  5257.7  323.02  5300.2  323.38  5491.7  327.34
  5502.3  327.12  5514.9  327.78  5534.2  327.55  5555.5  328.38  5562.3  327.94
#Mann= 3 ,-1 , 0
  4381.8     .11       0  4975.8     .06       0  5102.2     .11       0
Bank Sta=4975.8,5102.2
XS Rating Curve= 0 ,0
Exp/Cntr=0.3,0.1

Type RM Length L Ch R = 1 ,8633    ,554,554,554
BEGIN DESCRIPTION:
Mapping XS 27b77be2
END DESCRIPTION:
XS GIS Cut Line= 3
      3711711.32     10249598.62      3711719.13     10248653.33
       3711456.1     10248421.55
#Sta/Elev= 30
  4308.2  328.72  4395.8  327.76  4475.8  326.04  4497.3  326.78  4555.8  325.33
  4615.8  324.82  4745.8  324.56  4755.8  323.98  4805.8   324.2  4855.8  322.59
  4885.8  322.94  4925.8  322.33  4945.8  321.49  4955.8  320.45  4985.8  319.51
  4993.8  317.66    4994  317.16  4997.5  317.16  4997.8  317.66  5015.8  319.98
  5025.8  320.79  5055.8  320.82  5085.8  319.56  5105.8  320.25  5115.8  319.82
  5195.8  319.81  5284.1  320.49  5418.8  322.07  5518.4   324.2  5604.1  325.27
#Mann= 3 , 0 , 0
  4308.2     .11       0  4955.8     .06       0  5025.8     .11       0
Bank Sta=4955.8,5025.8
XS Rating Curve= 0 ,0
Exp/Cntr=0.3,0.1

Type RM Length L Ch R = 1 ,8079    ,472,472,472
BEGIN DESCRIPTION:
WFSJR 065 10.0
END DESCRIPTION:
XS GIS Cut Line= 3
      3711805.07     10249596.03      3712088.23     10249006.84
       3712393.1     10248206.76
#Sta/Elev= 30
  4346.3  326.92  4440.6  325.34  4462.8  325.21  4473.8  326.03  4485.1  324.91
  4518.2  323.81  4547.5  324.53  4570.1  323.31  4620.9  322.24    4802  321.35
  4807.6  320.77  4869.9  321.98  4937.9  320.81    4966  319.33  4988.7  316.87
  4993.1  312.81    5000  313.31  5012.3  317.63  5042.3  319.31  5072.4  319.58
  5097.2  318.33  5127.3  318.39    5237  320.32  5346.6  320.12  5412.8  321.11
  5431.6  322.09  5546.6  323.18  5669.7  322.41    5796  324.43  5856.2  324.35
#Mann= 3 , 0 , 0
  4346.3     .11       0    4966     .06       0  5042.3     .11       0
Bank Sta=4966,5042.3
XS Rating Curve= 0 ,0
Exp/Cntr=0.3,0.1

Type RM Length L Ch R = 1 ,7607    ,492,492,492
BEGIN DESCRIPTION:
WFSJR 065 9.0
END DESCRIPTION:
XS GIS Cut Line= 3
       3712008.2     10249684.56      3712458.23     10248936.84
      3712846.58     10248145.83
#Sta/Elev= 30
  4127.3  325.67  4166.4  325.47  4216.4   323.5  4237.8  324.82  4259.8  322.48
  4327.1  321.08  4422.3  321.43  4501.9  319.33  4597.1  321.18  4793.2   318.7
  4799.1  317.95    4937  318.01  4960.1  315.75  4989.4  315.17  4994.8  313.83
    5000  313.83  5003.9  312.36  5007.4  312.36  5028.2  317.29  5039.9  319.29
  5078.7  320.16  5101.2  320.21  5106.8  318.61  5123.7  319.38  5129.2  317.97
    5207  320.26  5241.7  318.64  5429.8  321.79  5786.9  322.48  5881.2  324.36
#Mann= 3 , 0 , 0
  4127.3     .11       0    4937     .06       0  5028.2     .11       0
#XS Ineff= 2 ,-1
    4300  4597.1  321.18  5101.2    5350  320.21
Permanent Ineff=
       F       F
Bank Sta=4937,5028.2
XS Rating Curve= 0 ,0
Exp/Cntr=0.3,0.1

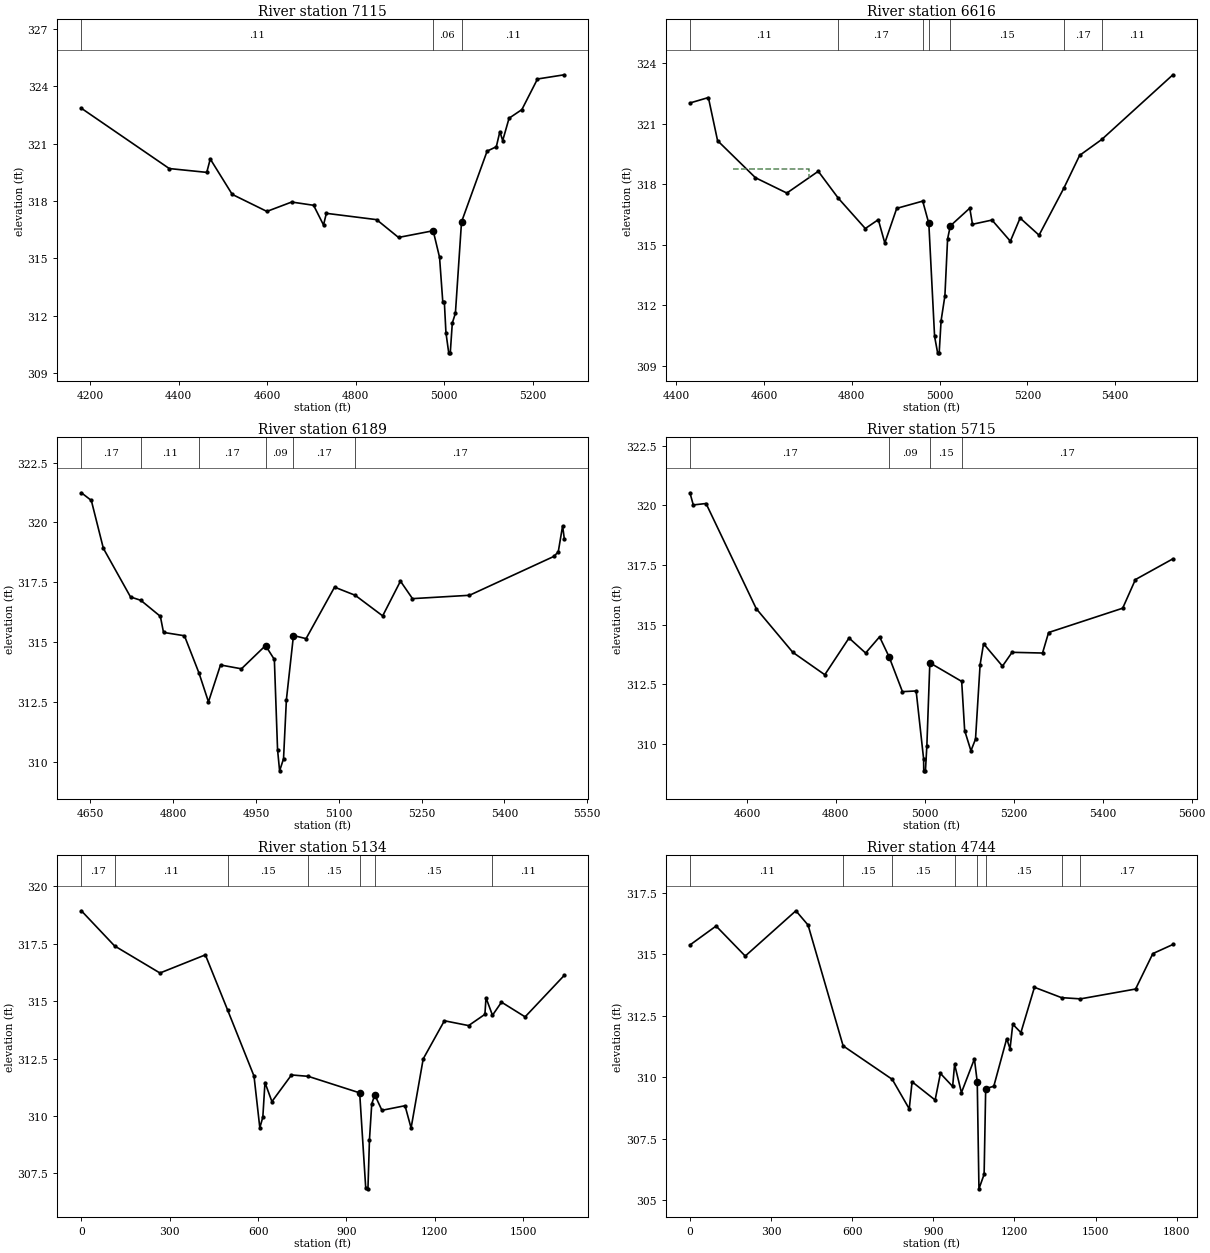
Type RM Length L Ch R = 1 ,7115    ,499,499,499
BEGIN DESCRIPTION:
WFSJR 065 8.0
END DESCRIPTION:
XS GIS Cut Line= 3
      3712161.84     10249723.64      3712798.23     10249206.84
       3713010.8     10249038.75
#Sta/Elev= 30
  4180.2  322.85  4378.7   319.7  4463.4   319.5  4471.3   320.2  4520.9  318.35
  4599.2  317.46  4655.2  317.95  4704.7  317.78  4727.1  316.75  4733.5  317.36
    4847  317.03  4896.5   316.1  4974.8  316.45  4989.2  315.06  4996.5  312.73
    5000  312.73  5003.6  311.13  5009.9  310.07  5013.4  310.07    5018  311.63
    5025  312.14  5038.8  316.91  5096.6  320.61  5117.4  320.84  5125.4  321.63
  5131.8  321.16  5146.2  322.33  5175.1  322.78  5210.4  324.38    5271   324.6
#Mann= 3 , 0 , 0
  4180.2     .11       0  4974.8     .06       0  5038.8     .11       0
Bank Sta=4974.8,5038.8
XS Rating Curve= 0 ,0
Exp/Cntr=0.3,0.1

Type RM Length L Ch R = 1 ,6616    ,427,427,427
BEGIN DESCRIPTION:
WFSJR 065 7.0
END DESCRIPTION:
XS GIS Cut Line= 2
      3712495.42     10250135.83        3713128.     10249236.65
#Sta/Elev= 30
  4431.7  322.04  4473.7  322.31  4494.6  320.17  4580.9  318.33  4652.3  317.57
  4723.8  318.65  4769.6  317.31  4830.9  315.81  4860.5  316.25  4875.3  315.09
  4902.4  316.81  4961.6  317.17  4975.5  316.06  4988.6  310.46  4995.5  309.64
  4999.1  309.64  5003.4  311.23  5012.1  312.47  5018.2  315.29  5024.4  315.94
  5068.7  316.82  5074.9  316.02  5119.3  316.23  5161.1  315.18  5183.3  316.33
  5226.4  315.48  5282.8  317.81  5318.8  319.44  5369.2  320.23  5531.1  323.44
#Mann= 7 ,-1 , 0
  4431.7     .11       0  4769.6     .17       0  4961.6     .15       0
  4975.5     .09       0  5024.4     .15       0  5282.8     .17       0
  5369.2     .11       0
#XS Ineff= 1 ,-1
    4530  4702.9  318.76
Permanent Ineff=
       F
Bank Sta=4975.5,5024.4
XS Rating Curve= 0 ,0
Exp/Cntr=0.3,0.1

Type RM Length L Ch R = 1 ,6189    ,474,474,474
BEGIN DESCRIPTION:
WFSJR 065 6.0
END DESCRIPTION:
XS GIS Cut Line= 3
      3712911.83     10250227.53      3713088.23     10249906.84
      3713333.29      10249461.4
#Sta/Elev= 30
    4634  321.24    4652  320.92  4673.8  318.92    4723  316.89  4741.6  316.75
    4777  316.08  4782.7  315.41  4820.6  315.27    4847  313.71  4864.1  312.51
  4885.9  314.05  4923.8  313.89  4967.4  314.86  4983.4  314.28  4989.2  310.51
  4992.9  309.63    5000  310.13  5005.2   312.6    5018  315.28  5040.8  315.15
  5092.4   317.3  5129.8  316.96  5179.5   316.1  5211.7  317.55  5233.5  316.82
  5336.7  316.96  5489.2  318.58  5497.4  318.77  5505.3  319.86  5508.4  319.31
#Mann= 6 ,-1 , 0
    4634     .17       0  4741.6     .11       0    4847     .17       0
  4967.4     .09       0    5018     .17       0  5129.8     .17       0
#XS Ineff= 1 ,-1
  5092.4    5400   317.3
Permanent Ineff=
       F
Bank Sta=4967.4,5018
XS Rating Curve= 0 ,0
Exp/Cntr=0.3,0.1

Type RM Length L Ch R = 1 ,5715    ,581,581,581
BEGIN DESCRIPTION:
WFSJR 065 5.0
END DESCRIPTION:
XS GIS Cut Line= 2
      3713411.83     10250476.29      3713659.23     10249418.95
#Sta/Elev= 30
  4471.9  320.53  4479.4  320.02  4508.1  320.08    4621  315.67  4703.2  313.84
  4775.1   312.9  4829.6  314.44  4866.9  313.81  4898.3  314.49  4919.7  313.65
  4949.7  312.19  4980.5  312.22  4997.3  309.37  4997.6  308.87  5001.4  308.87
  5004.6  309.92  5011.3   313.4  5082.9  312.62  5089.6  310.56  5103.7  309.71
    5114   310.2  5124.3  313.32  5132.1   314.2  5174.6  313.26  5196.2  313.84
  5264.7  313.81  5278.3  314.67  5444.9  315.69  5473.5  316.89  5557.8  317.76
#Mann= 4 ,-1 , 0
  4471.9     .17       0  4919.7     .09       0  5011.3     .15       0
  5082.9     .17       0
Bank Sta=4919.7,5011.3
XS Rating Curve= 0 ,0
Exp/Cntr=0.3,0.1

Type RM Length L Ch R = 1 ,5134    ,390,390,390
BEGIN DESCRIPTION:
Mapping XS 01d7ee30
END DESCRIPTION:
XS GIS Cut Line= 3
      3713819.82      10250860.8      3714134.53     10249520.97
      3714116.06      10249258.3
#Sta/Elev= 30
       0  318.94   112.7  317.41   266.8  316.23   420.9  317.02   496.1  314.63
   586.1  311.74   605.8  309.49     616  309.95   623.3  311.46   646.9  310.63
   713.3  311.79   770.1  311.73   944.8  311.01   965.3  306.88   972.9  306.83
     978  308.96   985.8  310.53   996.1  310.92  1020.4  310.25  1098.8  310.45
  1119.4  309.48  1160.5  312.49  1232.4  314.15  1314.6  313.94    1370  314.43
  1373.7  315.15  1395.7  314.39  1426.3  314.96  1506.5  314.32  1639.6  316.13
#Mann= 7 ,-1 , 0
       0     .17       0   112.7     .11       0   496.1     .15       0
   770.1     .15       0   944.8     .09       0   996.1     .15       0
  1395.7     .11       0
Bank Sta=944.8,996.1
XS Rating Curve= 0 ,0
Exp/Cntr=0.3,0.1

Type RM Length L Ch R = 1 ,4744    ,1074,1074,1074
BEGIN DESCRIPTION:
WFSJR 065 4.0
END DESCRIPTION:
XS GIS Cut Line= 4
      3714062.88     10250964.97      3714388.23     10249926.84
      3714410.57     10249510.96      3714233.24     10249292.15
#Sta/Elev= 30
       0  315.38    96.7  316.15   204.5  314.93   391.8  316.77   436.8  316.19
   566.5  311.28   748.1  309.92     811  308.72   821.5  309.82   906.7  309.08
   926.3  310.16   971.5  309.63   978.7  310.53    1004  309.38    1052  310.75
  1062.5  309.81  1068.8  305.47  1087.9  306.06  1093.7  309.54  1123.7  309.64
  1171.4  311.57  1183.8  311.16  1193.8  312.16  1223.9  311.82    1274  313.66
  1374.1  313.24  1444.2  313.19    1648  313.59  1711.9  315.03    1786   315.4
#Mann= 8 ,-1 , 0
       0     .11       0   566.5     .15       0   748.1     .15       0
   978.7     .15       0  1062.5     .09       0  1093.7     .15       0
  1374.1     .15       0  1444.2     .17       0
Bank Sta=1062.5,1093.7
XS Rating Curve= 0 ,0
Exp/Cntr=0.3,0.1

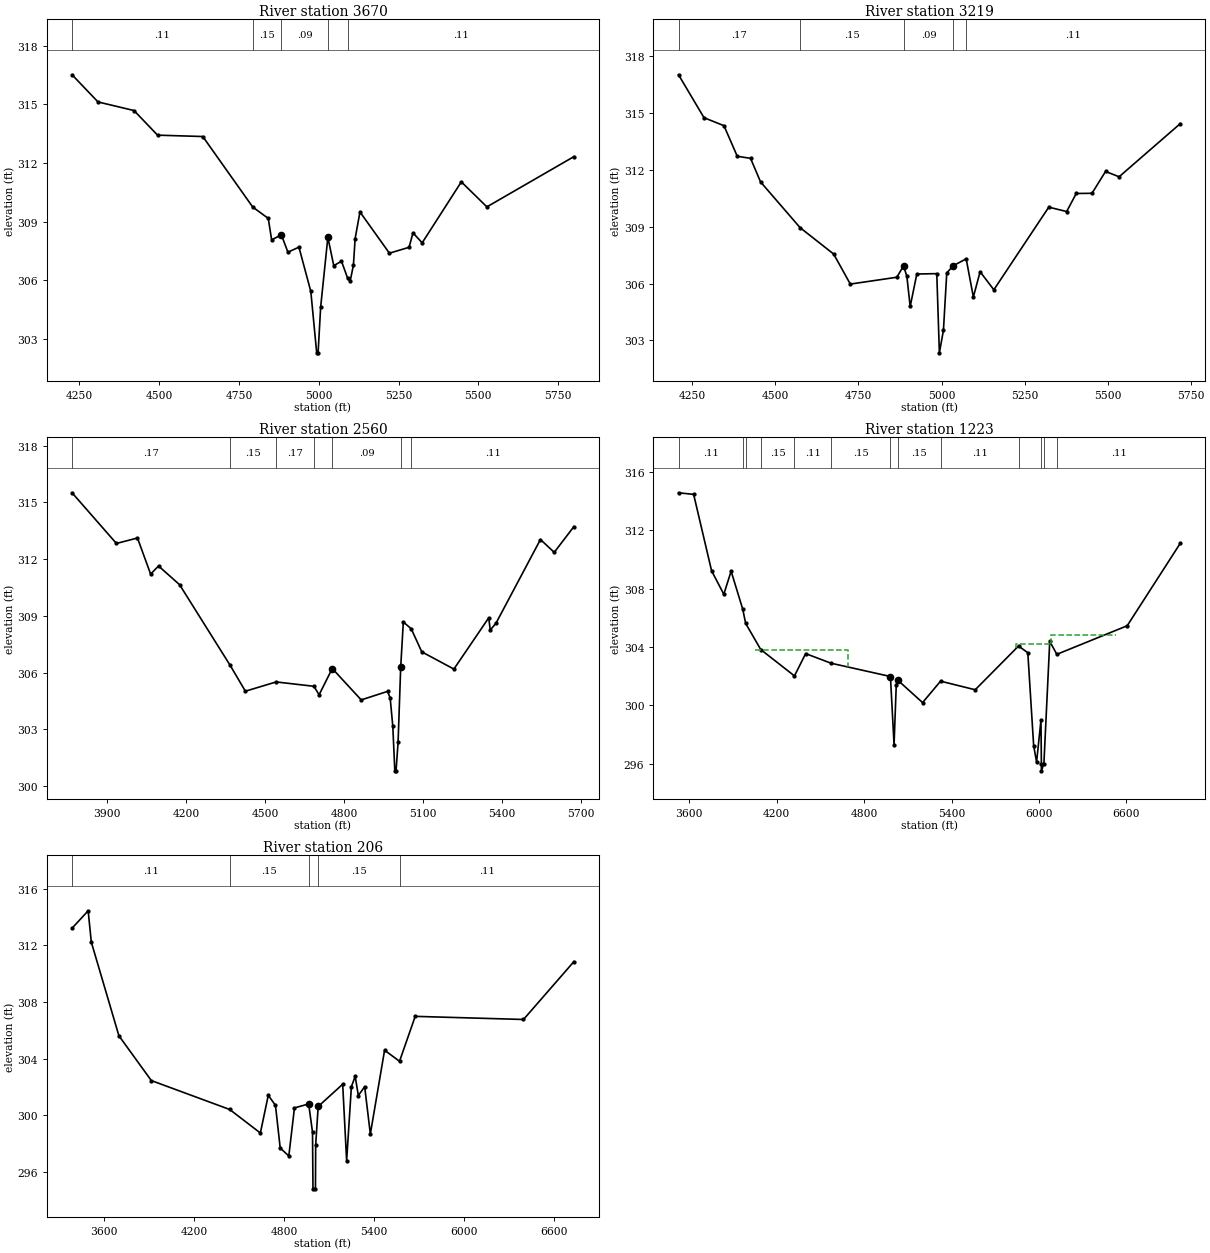
Type RM Length L Ch R = 1 ,3670    ,451,451,451
BEGIN DESCRIPTION:
Mapping XS a56285a5
END DESCRIPTION:
XS GIS Cut Line= 3
       3714823.3     10251180.24      3715094.13     10250006.63
      3715083.71     10249638.54
#Sta/Elev= 30
  4226.8  316.52  4308.1  315.13  4420.9  314.69  4494.8  313.43  4636.5  313.36
  4793.1  309.75  4841.7  309.17  4852.3  308.07  4882.8  308.33  4903.3  307.44
  4937.8   307.7  4975.1  305.43  4993.5  302.29  4997.9  302.29  5005.9  304.63
  5028.5   308.2    5047  306.75  5071.2  306.98  5090.2  306.12  5098.3  305.95
  5108.6  306.78    5114  308.14  5129.1   309.5  5221.4  307.39    5283  307.69
  5295.3  308.43  5324.1  307.92  5446.8  311.04  5526.9  309.76  5799.5  312.33
#Mann= 5 ,-1 , 0
  4226.8     .11       0  4793.1     .15       0  4882.8     .09       0
  5028.5     .15       0  5090.2     .11       0
Bank Sta=4882.8,5028.5
XS Rating Curve= 0 ,0
Exp/Cntr=0.3,0.1

Type RM Length L Ch R = 1 ,3219    ,659,659,659
BEGIN DESCRIPTION:
WFSJR 065 3.0
END DESCRIPTION:
XS GIS Cut Line= 3
      3715392.74     10251197.62      3715399.68     10250301.77
       3715246.9     10249707.99
#Sta/Elev= 30
  4209.2  316.99  4285.8  314.73  4345.8  314.31  4385.8   312.7  4425.8  312.59
  4455.8  311.35  4574.8  308.94  4675.8  307.55  4725.8  305.97  4865.8  306.33
  4885.8  306.93  4895.8  306.38  4905.8  304.79  4925.8   306.5  4985.8  306.52
  4993.6  302.35  5005.8  303.53  5015.8  306.56  5035.8  306.94  5074.2   307.3
  5095.8  305.29  5116.1  306.62  5157.4  305.67  5322.6  310.02  5376.4  309.79
  5405.2  310.74  5452.6  310.75  5493.3   311.9  5534.1  311.62  5718.2  314.42
#Mann= 5 ,-1 , 0
  4209.2     .17       0  4574.8     .15       0  4885.8     .09       0
  5035.8     .15       0  5074.2     .11       0
Bank Sta=4885.8,5035.8
XS Rating Curve= 0 ,0
Exp/Cntr=0.3,0.1

Type RM Length L Ch R = 1 ,2560    ,1337,1337,1337
BEGIN DESCRIPTION:
WFSJR 065 2.0
END DESCRIPTION:
XS GIS Cut Line= 3
      3715778.16     10251329.54       3715823.3     10249992.74
      3715333.75      10249701.1
#Sta/Elev= 30
  3766.6  315.51  3935.2  312.83  4015.2  313.12  4065.2  311.21  4095.3  311.64
  4175.3  310.65  4367.8  306.38  4425.4  305.02  4542.4  305.51  4685.9  305.28
  4705.6  304.83  4755.6  306.22  4865.7  304.56  4965.8  305.01  4975.8  304.66
  4985.8  303.16  4993.4  300.81  4998.1  300.81  5005.8  302.31  5015.8   306.3
  5025.8  308.68  5055.8  308.32  5095.9   307.1    5218  306.19  5350.4   308.9
  5356.2  308.25  5378.2  308.62    5547  313.04  5599.4  312.36    5674  313.72
#Mann= 7 ,-1 , 0
  3766.6     .17       0  4367.8     .15       0  4542.4     .17       0
  4685.9     .15       0  4755.6     .09       0  5015.8     .15       0
  5055.8     .11       0
#XS Ineff= 1 ,-1
  5025.8    5410  308.68
Permanent Ineff=
       F
Bank Sta=4755.6,5015.8
XS Rating Curve= 0 ,0
Exp/Cntr=0.3,0.1

Type RM Length L Ch R = 1 ,1223    ,1017,1017,1017
BEGIN DESCRIPTION:
Mapping XS 657a5918
END DESCRIPTION:
XS GIS Cut Line= 2
      3716660.97      10251380.8      3716387.53     10247947.57
#Sta/Elev= 30
  3525.7  314.57  3629.4  314.46  3752.5  309.22  3836.4  307.61  3886.6  309.19
    3966   306.6  3986.5  305.61  4089.9  303.82  4321.4  302.01  4398.2  303.54
  4572.8  302.88    4980  301.97    5005   297.3  5020.1   301.4  5030.2  301.72
  5200.7  300.18  5324.2  301.65  5561.9  301.06  5859.3  304.06    5923   303.6
  5963.1  297.23  5983.2   296.1  6013.3  298.98  6016.1     296  6016.6   295.5
  6033.4     296  6073.5  304.38  6122.2  303.49  6605.1  305.45  6969.8  311.11
#Mann= 13 ,-1 , 0
  3525.7     .11       0    3966     .17       0  3986.5     .11       0
  4089.9     .15       0  4321.4     .11       0  4572.8     .15       0
    4980     .09       0  5030.2     .15       0  5324.2     .11       0
  5859.3     .15       0  6016.1     .12       0  6033.4     .15       0
  6122.2     .11       0
#XS Ineff= 3 ,-1
    4050  4689.1  303.81  5842.7    6075  304.22  6083.5    6525  304.82
Permanent Ineff=
       F       F       F
Bank Sta=4980,5030.2
XS Rating Curve= 0 ,0
Exp/Cntr=0.3,0.1

Type RM Length L Ch R = 1 ,206     ,0,0,0
BEGIN DESCRIPTION:
WFSJR 065 1.0
END DESCRIPTION:
XS GIS Cut Line= 3
      3716704.37     10251432.85      3717485.62     10249084.76
      3717572.42     10248216.73
#Sta/Elev= 30
  3386.9   313.2  3494.2  314.43  3515.2  312.22  3699.3  305.61  3915.5  302.45
  4438.2  300.41  4642.9  298.75  4695.6  301.41  4743.6   300.7  4775.2  297.69
  4832.6  297.13  4870.2  300.52  4965.1   300.8  4990.7  298.81  4993.8  294.81
  5010.3  294.81  5011.8   297.9  5028.4  300.62  5191.9  302.19  5218.3  296.79
  5249.9  302.01  5275.3  302.75  5296.3  301.39  5338.5  302.02  5376.5  298.68
  5471.4  304.59  5571.1  303.81  5675.7  306.98  6397.9  306.76  6733.9  310.84
#Mann= 5 ,-1 , 0
  3386.9     .11       0  4438.2     .15       0  4965.1     .09       0
  5028.4     .15       0  5571.1     .11       0
#XS Ineff= 1 ,-1
  5191.9    5445  302.19
Permanent Ineff=
       F
Bank Sta=4965.1,5028.4
XS Rating Curve= 0 ,0
Exp/Cntr=0.3,0.1

Chan Stop Cuts=-1
Use User Specified Reach Order=0
Composite Channel Slope=5