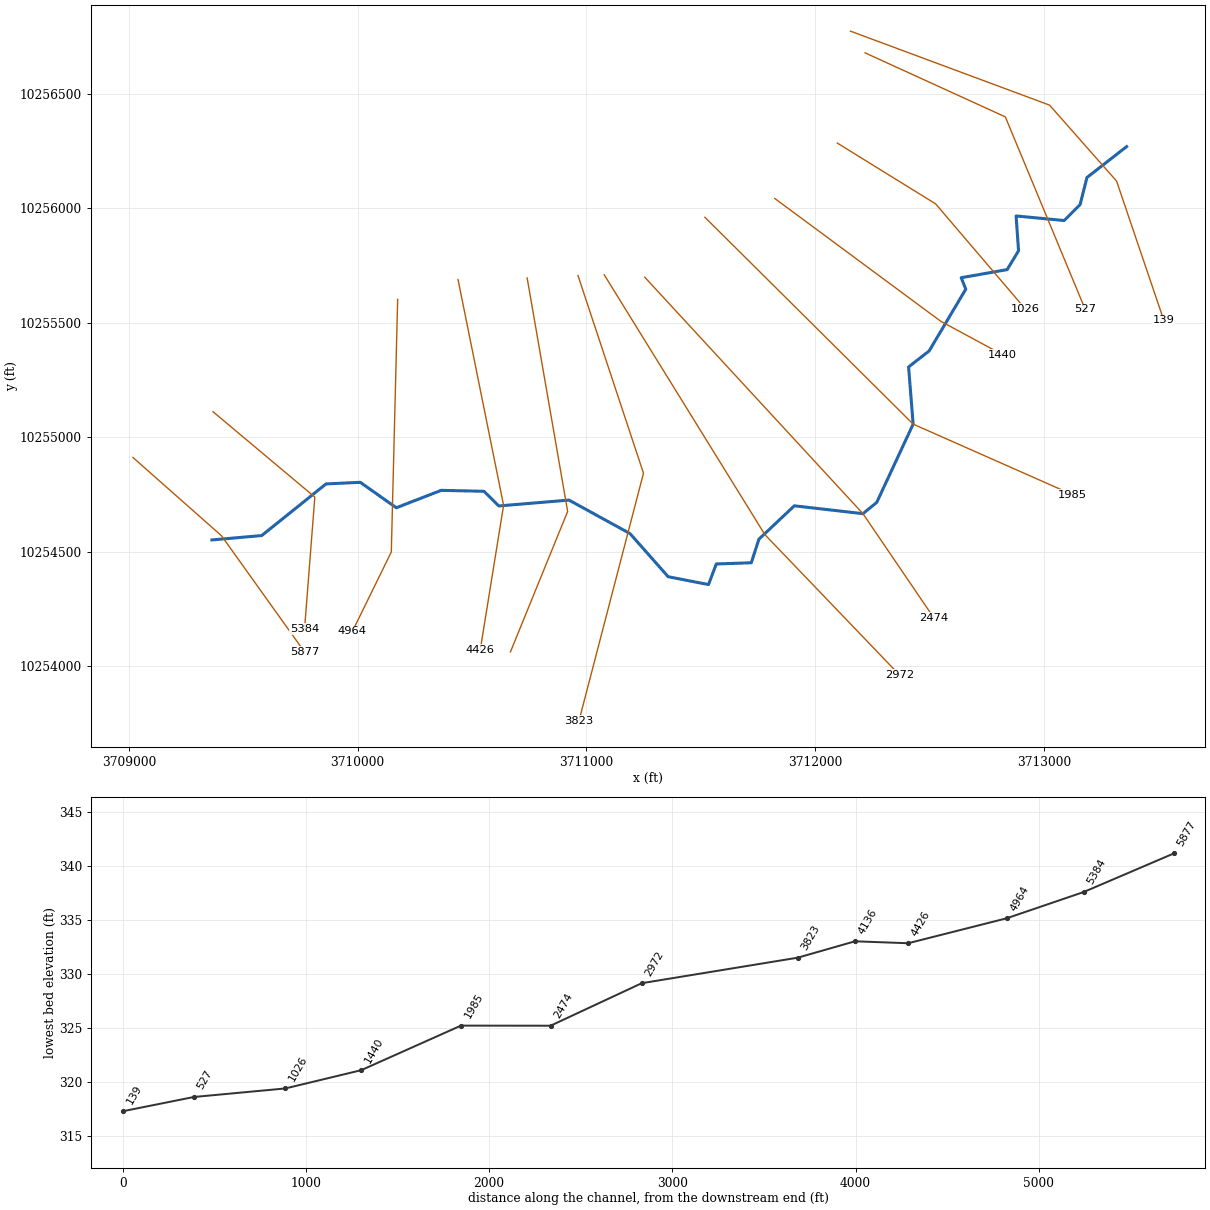
--- WFSJR 066.prj (project) ---

Proj Title=WFSJR 066 Base Level Engineering
Current Plan=p01
Default Exp/Contr=0.3,0.1
English Units
Geom File=g01
Flow File=f01
Plan File=p01
Y Axis Title=Elevation
X Axis Title(PF)=Main Channel Distance
X Axis Title(XS)=Station
BEGIN DESCRIPTION:
WFSJR 066
END DESCRIPTION:
DSS Export Rating Curves= 0
DSS Export Rating Curve Sorted= 0
DSS Export Volume Flow Curves= 0
DXF OffsetX= 0
DXF OffsetY= 0
DXF ScaleX= 1
DXF ScaleY= 10

--- WFSJR 066.p01 (plan) ---

Plan Title=Multiple Run
Program Version=4.10
Short Identifier=Multiple
Geom File=g01
Flow File=f01
Subcritical Flow
K Sum by GR= 0
Std Step Tol= 0.01
Critical Tol= 0.01
Num of Std Step Trials= 20
Max Error Tol= 0.3
Flow Tol Ratio= 0.001
Split Flow NTrial= 30
Split Flow Tol= 0.02
Split Flow Ratio= 0.02
Log Output Level= 0
Friction Slope Method= 1
Unsteady Friction Slope Method= 2
Unsteady Bridges Friction Slope Method= 1
Parabolic Critical Depth
Global Vel Dist= 1 , 1 , 1
Global Log Level= 0
CheckData=True
Encroach Param=-1 ,0,0, 0
BEGIN DESCRIPTION:
Multiple Run
END DESCRIPTION:
Computation Interval=1HOUR
Output Interval=1HOUR
Run HTab= 0
Run UNet= 0
Run PostProcess= 0
Run WQNet= 0
UNET Theta= 1
UNET Theta Warmup= 1
UNET ZTol= 0.02
UNET ZSATol= 0.05
UNET MxIter= 20
UNET MaxInSteps= 0
UNET DtIC= 0
UNET DtMin= 0
UNET MaxCRTS= 20
UNET WFStab= 2
UNET SFStab= 1
UNET WFX= 1
UNET SFX= 1
UNET DSS MLevel= 4
UNET DZMax Abort= 100
UNET Convert EG Bridges= 0
UNET Use Existing IB Tables=-1
UNET Froude Reduction=False
UNET Froude Limit= 1
UNET Froude Power= 10
UNET Time Slicing=0,0, 5
UNET Junction Losses=0
Instantaneous Interval=1HOUR
Write IC File= 0
Write IC File at Sim End=0
Echo Input=False
Echo Parameters=False
Echo Output=False
Write Detailed= 0
WQ AD Non Conservative
WQ ULTIMATE=-1
WQ Max Comp Step=1HOUR
WQ Output Interval=15MIN
WQ Output Selected Increments= 0
WQ Output face flow=0
WQ Output face velocity=0
WQ Output face area=0
WQ Output face dispersion=0
WQ Output cell volume=0
WQ Output cell surface area=0
WQ Output cell continuity=0
WQ Output cumulative cell continuity=0
WQ Output face conc=0
WQ Output face dconc_dx=0
WQ Output face courant=0
WQ Output face peclet=0
WQ Output face adv mass=0
WQ Output face disp mass=0
WQ Output cell mass=0
WQ Output cell source sink temp=0
WQ Output cell source sink nsm=0
WQ Output MaxMinRange=-1
WQ Daily Max Min Mean=-1
WQ Daily Range=0
WQ Daily Time=0
WQ Create Restart=0
WQ Fixed Restart=0
WQ System Summary=0
WQ Use Fixed Temperature=0
Sorting and Armoring Iterations= 10
XS Update Threshold= 0.02
Hydraulics Update Threshold= 0.02
Energy Slope Method= 1
Volume Change Method= 0
XS Weighting Method= 0
Number of US Weighted Cross Sections= 1
Number of DS Weighted Cross Sections= 1
Upstream XS Weight=0.25
Main XS Weight=0.5
Downstream XS Weight=0.25
Number of DS XS's Weighted with US Boundary= 1
Upstream Boundary Weight= 1
Weight of XSs Associated with US Boundary= 0
Number of US XS's Weighted with DS Boundary= 1
Downstream Boundary Weight= 0.5
Weight of XSs Associated with DS Boundary= 0.5
Sediment Output Level= 4
Mass or Volume Output= 0
Output Increment Type= 1
Profile and TS Output Increment= 10
XS Output Flag= 0
XS Output Increment= 10
Disregard all LS=0
Disregard all Conn=0
Disregard all Breaches=0
Disregard all Pumps=0

--- WFSJR 066.f01 (steady flow) ---

Flow Title=Multiple
Program Version=4.10
Number of Profiles= 7
Profile Names=10-year,25-year,50-year,1pct_min,100-year,1pct_plu,500-year
River Rch & RM=WFSJR 066,Reach-1         ,5877
     348     453     596     258     780    2356    1381
River Rch & RM=WFSJR 066,Reach-1         ,1985
     490     653     872     383    1157    3494    2109
Boundary for River Rch & Prof#=WFSJR 066,Reach-1         , 1
Up Type= 0
Dn Type= 3
Dn Slope=0.004
Boundary for River Rch & Prof#=WFSJR 066,Reach-1         , 2
Up Type= 0
Dn Type= 3
Dn Slope=0.004
Boundary for River Rch & Prof#=WFSJR 066,Reach-1         , 3
Up Type= 0
Dn Type= 3
Dn Slope=0.004
Boundary for River Rch & Prof#=WFSJR 066,Reach-1         , 4
Up Type= 0
Dn Type= 3
Dn Slope=0.004
Boundary for River Rch & Prof#=WFSJR 066,Reach-1         , 5
Up Type= 0
Dn Type= 3
Dn Slope=0.004
Boundary for River Rch & Prof#=WFSJR 066,Reach-1         , 6
Up Type= 0
Dn Type= 3
Dn Slope=0.004
Boundary for River Rch & Prof#=WFSJR 066,Reach-1         , 7
Up Type= 0
Dn Type= 3
Dn Slope=0.004
DSS Import GetInterval= 0
DSS Import GetPeak= 0
DSS Import FillOption= 0

--- WFSJR 066.g01 (geometry) ---

Geom Title=Existing Conditions
Program Version=4.10

River Reach=WFSJR 066       ,Reach-1
Reach XY= 30
      3709362.82     10254550.59      3709580.83     10254569.77
      3709861.79     10254795.48      3710011.44     10254802.43
      3710169.08     10254691.32      3710365.26     10254767.36
      3710552.01     10254763.32      3710617.11     10254699.25
      3710923.89     10254724.77      3711190.55     10254578.42
      3711357.22     10254389.88      3711533.78      10254355.5
      3711567.64     10254445.61      3711720.76     10254450.82
      3711754.09     10254553.94      3711908.78     10254699.77
      3712208.78      10254665.4       3712269.2     10254714.88
      3712428.23     10255056.84      3712408.23     10255306.84
      3712498.23     10255376.84      3712658.23     10255646.84
      3712638.23     10255696.84      3712839.05     10255732.18
      3712888.96     10255814.64      3712878.23     10255966.84
      3713088.23     10255946.84      3713158.23     10256016.84
      3713187.96     10256134.85      3713361.39     10256270.01

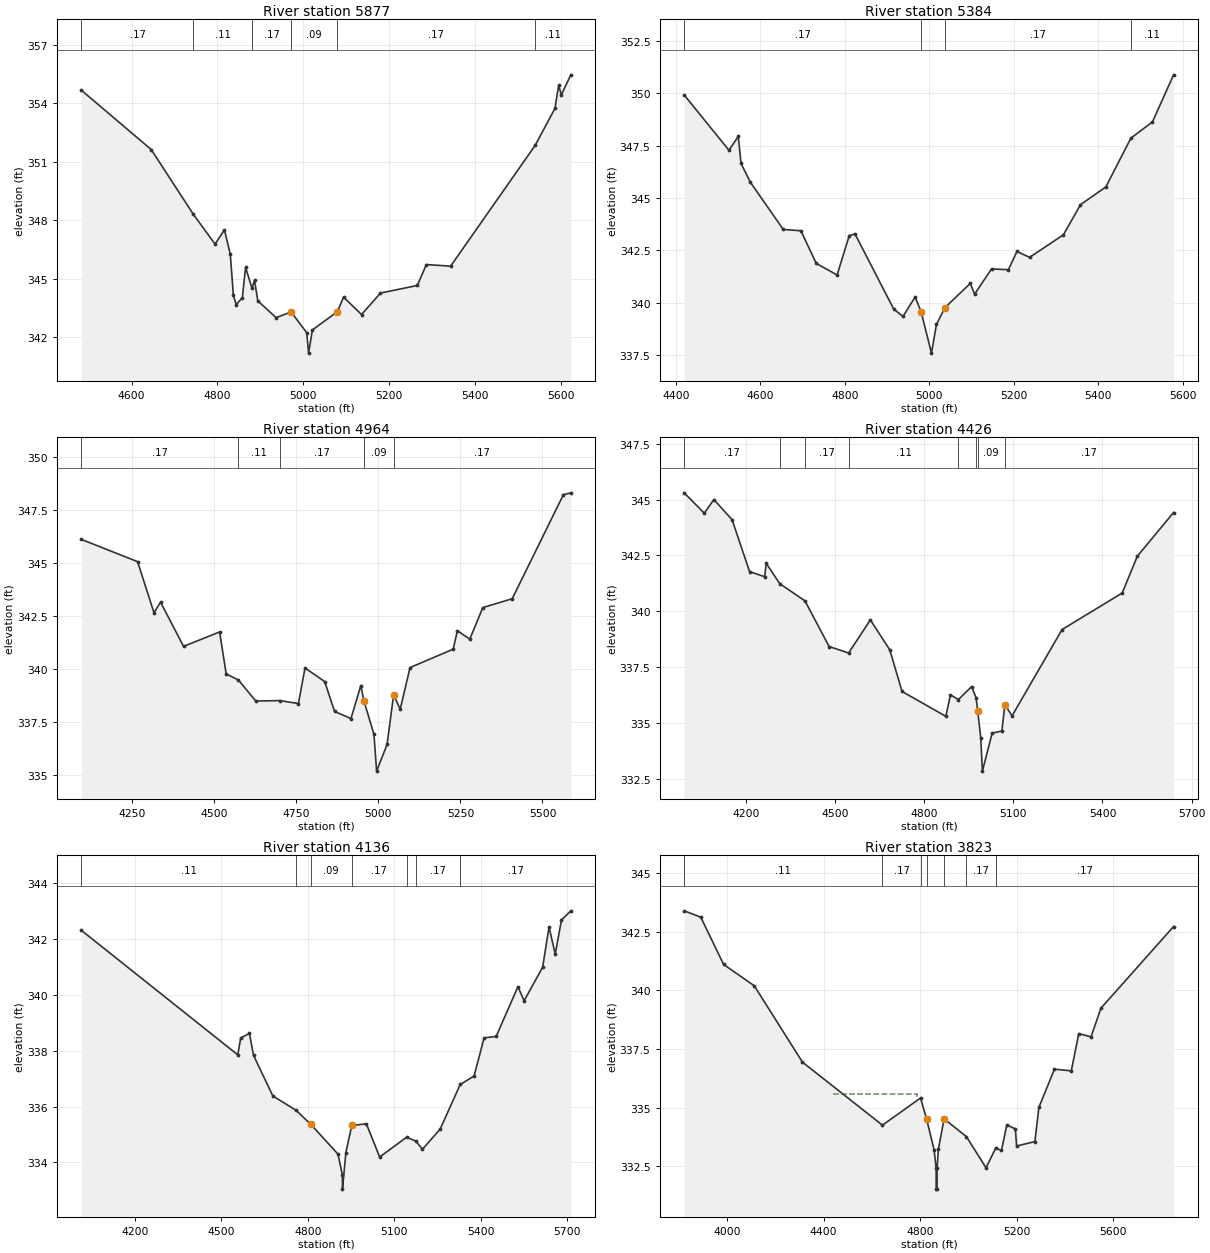
Type RM Length L Ch R = 1 ,5877    ,493,493,493
BEGIN DESCRIPTION:
WFSJR 066 12.0
END DESCRIPTION:
XS GIS Cut Line= 3
      3709017.84     10254911.08      3709405.02     10254568.63
      3709767.85     10254061.08
#Sta/Elev= 30
  4483.1  354.66  4645.8  351.62  4744.3  348.29  4794.7  346.77  4816.5   347.5
  4830.2  346.25  4837.4  344.14    4844  343.66  4858.3  344.03  4865.8  345.58
  4880.8   344.5  4886.7  344.92  4894.3  343.86  4936.9     343    4972  343.29
  5008.3  342.23  5012.7  341.18  5021.6  342.37  5079.6   343.3  5094.3  344.05
  5136.1  343.16  5180.3  344.26  5266.3  344.65  5287.2  345.72  5343.8  345.64
  5540.8  351.83    5587  353.73  5595.6  354.91  5601.8  354.42  5623.9  355.45
#Mann= 6 ,-1 , 0
  4483.1     .17       0  4744.3     .11       0  4880.8     .17       0
    4972     .09       0  5079.6     .17       0  5540.8     .11       0
#XS Ineff= 1 ,-1
    4820  4865.8  345.58
Permanent Ineff=
       F
Bank Sta=4972,5079.6
XS Rating Curve= 0 ,0
Exp/Cntr=0.3,0.1

Type RM Length L Ch R = 1 ,5384    ,420,420,420
BEGIN DESCRIPTION:
WFSJR 066 11.0
END DESCRIPTION:
XS GIS Cut Line= 3
      3709367.84     10255111.08      3709812.83     10254737.84
      3709767.85     10254161.09
#Sta/Elev= 30
  4419.2  349.92  4525.3  347.28  4547.4  347.94  4553.9  346.65  4575.8  345.76
    4654   343.5  4695.7  343.44  4732.1  341.88  4781.5  341.33  4810.1   343.2
  4823.8  343.29  4915.6   339.7  4937.6  339.35  4966.3  340.28  4980.5  339.57
    5005   337.6  5016.8  338.97  5036.9  339.77  5097.1  340.93  5107.1  340.41
  5147.2  341.62  5187.3  341.58  5207.4  342.45  5237.5  342.17  5317.7  343.25
  5357.9  344.68    5418  345.53  5477.4  347.86  5528.4  348.63  5578.5  350.88
#Mann= 4 ,-1 , 0
  4419.2     .17       0  4980.5     .09       0  5036.9     .17       0
  5477.4     .11       0
#XS Ineff= 1 ,-1
    4640  4823.8  343.29
Permanent Ineff=
       F
Bank Sta=4980.5,5036.9
XS Rating Curve= 0 ,0
Exp/Cntr=0.3,0.1

Type RM Length L Ch R = 1 ,4964    ,538,538,538
BEGIN DESCRIPTION:
WFSJR 066 10.0
END DESCRIPTION:
XS GIS Cut Line= 3
       3710174.9     10255602.17      3710147.12     10254497.97
      3709976.99     10254150.76
#Sta/Elev= 30
  4095.1  346.11  4266.3  345.06  4316.3  342.65  4336.3  343.15  4406.3  341.06
  4516.3  341.74  4536.3  339.76  4573.8  339.47  4626.4  338.48  4699.8   338.5
  4756.4  338.36  4776.4  340.04  4836.4   339.4  4866.4  337.99  4916.5  337.65
  4946.5  339.21  4956.5  338.46  4986.5  336.91  4994.7  335.17  5026.5  336.43
  5046.5  338.77  5066.5  338.09  5096.5  340.06  5228.1  340.93  5240.7   341.8
  5278.6   341.4  5318.1  342.89  5407.8  343.31  5563.7  348.22  5586.3  348.31
#Mann= 5 ,-1 , 0
  4095.1     .17       0  4573.8     .11       0  4699.8     .17       0
  4956.5     .09       0  5046.5     .17       0
#XS Ineff= 1 ,-1
    4526  4776.4  340.04
Permanent Ineff=
       F
Bank Sta=4956.5,5046.5
XS Rating Curve= 0 ,0
Exp/Cntr=0.3,0.1

Type RM Length L Ch R = 1 ,4426    ,290,290,290
BEGIN DESCRIPTION:
WFSJR 066 9.0
END DESCRIPTION:
XS GIS Cut Line= 3
      3710438.79     10255688.97      3710637.95     10254701.86
      3710536.01     10254070.84
#Sta/Elev= 30
    3993   345.3  4060.6  344.39  4092.9     345  4154.1   344.1    4213  341.78
  4263.8  341.55  4268.9  342.15  4314.5  341.24  4399.4  340.47  4480.5  338.43
  4546.1  338.14  4619.3  339.62  4684.6  338.28  4725.9  336.42  4873.2  335.31
  4888.6  336.27  4915.5  336.06    4960  336.64  4974.8  336.14  4980.4  335.55
  4990.6  334.35  4996.1  332.86    5029  334.56  5061.6  334.65  5071.7  335.83
  5095.8  335.33  5264.2  339.19  5466.3  340.82  5517.4  342.47  5639.2  344.42
#Mann= 8 ,-1 , 0
    3993     .17       0  4314.5     .11       0  4399.4     .17       0
  4546.1     .11       0  4915.5     .17       0  4974.8     .12       0
  4980.4     .09       0  5071.7     .17       0
Bank Sta=4980.4,5071.7
XS Rating Curve= 0 ,0
Exp/Cntr=0.3,0.1

Type RM Length L Ch R = 1 ,4136    ,313,313,313
BEGIN DESCRIPTION:
WFSJR 066 8.0
END DESCRIPTION:
XS GIS Cut Line= 3
      3710740.87     10255695.91      3710917.96     10254675.05
      3710667.84     10254061.04
#Sta/Elev= 30
  4013.8  342.31  4556.8  337.85  4566.8  338.45  4597.2  338.62  4611.5  337.83
  4678.4  336.38  4759.6  335.86  4810.4  335.36  4904.9  334.29    4920  333.54
  4920.2  333.04  4932.1  334.35  4952.4  335.32  5003.2  335.38  5049.4  334.19
    5143   334.9  5174.9  334.76    5198  334.47  5259.4  335.19    5329  336.79
  5377.1  337.09    5412  338.46  5453.7  338.51  5529.3  340.29  5550.9  339.79
  5615.2  340.99  5637.3  342.43  5658.9  341.46  5680.5  342.68  5712.9  343.01
#Mann= 7 ,-1 , 0
  4013.8     .11       0  4759.6     .15       0  4810.4     .09       0
  4952.4     .17       0    5143     .17       0  5174.9     .17       0
    5329     .17       0
Bank Sta=4810.4,4952.4
XS Rating Curve= 0 ,0
Exp/Cntr=0.3,0.1

Type RM Length L Ch R = 1 ,3823    ,851,851,851
BEGIN DESCRIPTION:
WFSJR 066 7.0
END DESCRIPTION:
XS GIS Cut Line= 3
       3710963.1      10255706.3      3711249.42     10254842.47
      3710967.85     10253761.07
#Sta/Elev= 30
  3822.2   343.4  3890.9  343.13  3985.7  341.11  4112.5   340.2  4312.3  336.94
  4643.6  334.25  4801.4  335.41  4826.7   334.5  4857.7  333.19    4866  332.42
  4866.3  331.52  4869.8  331.52    4870  332.42  4875.3  333.22    4899  334.52
  4991.6  333.76  5072.7  332.43  5113.2  333.28  5136.7  333.17  5158.8  334.26
  5194.2  334.09  5199.4  333.36  5275.2  333.55  5291.7  335.01  5356.2  336.64
    5426  336.57    5457  338.16  5507.9  338.02  5548.5  339.24  5849.7  342.73
#Mann= 7 ,-1 , 0
  3822.2     .11       0  4643.6     .17       0  4801.4     .15       0
  4826.7     .09       0    4899     .15       0  4991.6     .17       0
  5113.2     .17       0
#XS Ineff= 1 ,-1
    4440  4785.4  335.58
Permanent Ineff=
       F
Bank Sta=4826.7,4899
XS Rating Curve= 0 ,0
Exp/Cntr=0.3,0.1

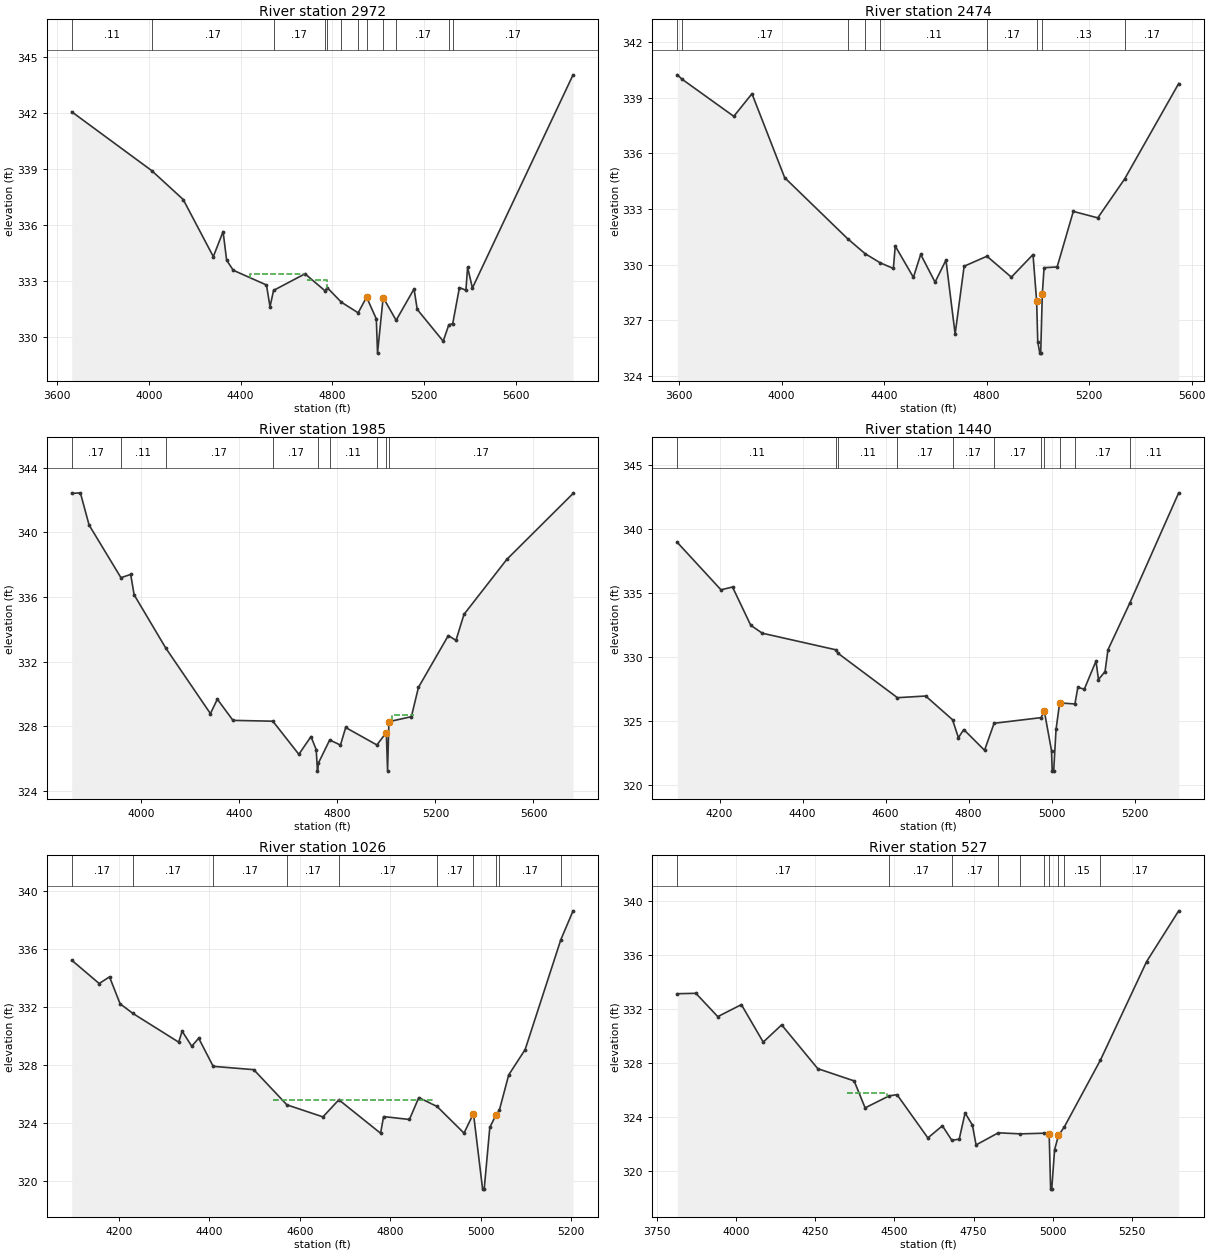
Type RM Length L Ch R = 1 ,2972    ,498,498,498
BEGIN DESCRIPTION:
WFSJR 066 6.0
END DESCRIPTION:
XS GIS Cut Line= 3
      3711077.67     10255709.79      3711780.14     10254573.73
      3712367.87     10253961.06
#Sta/Elev= 30
  3664.3  342.09  4012.6  338.94  4150.1  337.39  4281.3  334.33  4323.9  335.67
  4339.3  334.14  4368.2   333.6    4513  332.81  4528.4  331.64  4543.8  332.52
  4680.9  333.41    4768   332.5  4778.2  332.66  4839.2  331.89  4912.5  331.32
  4949.2  332.16  4991.7  330.99  4996.9  329.16  5021.4  332.14    5078  330.92
    5156   332.6    5170   331.5  5283.1   329.8  5307.6  330.68  5324.6  330.74
  5353.8  332.67  5382.1  332.53  5389.4  333.76  5410.4  332.65    5849  344.07
#Mann= 12 ,-1 , 0
  3664.3     .11       0  4012.6     .17       0  4543.8     .17       0
    4768     .11       0  4778.2     .17       0  4839.2     .15       0
  4912.5     .15       0  4949.2     .09       0  5021.4     .15       0
    5078     .17       0  5307.6     .11       0  5324.6     .17       0
#XS Ineff= 3 ,-1
    4440  4680.9  333.41    4690  4775.4  333.07    5156    5430   332.6
Permanent Ineff=
       F       F       T
Bank Sta=4949.2,5021.4
XS Rating Curve= 0 ,0
Exp/Cntr=0.3,0.1

Type RM Length L Ch R = 1 ,2474    ,489,489,489
BEGIN DESCRIPTION:
WFSJR 066 5.0
END DESCRIPTION:
XS GIS Cut Line= 3
      3711254.79     10255699.32      3712208.78      10254665.4
      3712517.86     10254211.06
#Sta/Elev= 30
  3593.2  340.24  3610.9  340.01  3813.4     338  3884.3  339.22  4011.9  334.69
    4258  331.39  4325.6  330.59  4385.3  330.09  4436.1  329.79  4443.4     331
  4514.3  329.31  4542.7  330.55  4598.8  329.05  4641.3  330.24  4677.1  326.25
  4712.2  329.91  4801.3  330.45  4896.5  329.32    4981  330.54  4995.2  328.02
  4999.5  325.84  5007.5  325.22    5011  325.22  5017.3  328.42  5024.2  329.83
  5075.1  329.87  5138.3  332.87  5233.7  332.52  5338.1  334.61  5549.5  339.77
#Mann= 9 ,-1 , 0
  3593.2     .11       0  3610.9     .17       0    4258     .11       0
  4325.6     .17       0  4385.3     .11       0  4801.3     .17       0
  4995.2     .07       0  5017.3     .13       0  5338.1     .17       0
#XS Ineff= 1 ,-1
    4200    4981  330.54
Permanent Ineff=
       T
Bank Sta=4995.2,5017.3
XS Rating Curve= 0 ,0
Exp/Cntr=0.3,0.1

Type RM Length L Ch R = 1 ,1985    ,545,545,545
BEGIN DESCRIPTION:
WFSJR 066 4.0
END DESCRIPTION:
XS GIS Cut Line= 3
      3711517.87     10255961.05      3712428.23     10255056.84
       3713124.6     10254748.71
#Sta/Elev= 30
  3716.9  342.41  3752.2  342.45  3787.6  340.46  3917.6   337.2  3957.3   337.4
  3971.4  336.14  4099.8  332.86  4282.5  328.79  4310.8  329.68  4374.5  328.37
  4537.1  328.32  4643.2  326.27  4692.7  327.37  4713.9  326.56  4719.2  325.23
    4723  325.73    4769  327.16  4812.9  326.84  4834.1  327.93  4961.4  326.85
    5000  327.62    5005  325.26  5010.5  328.29  5102.1   328.6  5130.9  330.41
  5252.8  333.62  5283.9  333.32  5316.7  334.93  5491.2  338.33  5761.5  342.41
#Mann= 9 ,-1 , 0
  3716.9     .17       0  3917.6     .11       0  4099.8     .17       0
  4537.1     .17       0    4723     .17       0    4769     .11       0
  4961.4     .17       0    5000     .08       0  5010.5     .17       0
#XS Ineff= 1 ,-1
  5021.3    5111  328.68
Permanent Ineff=
       F
Bank Sta=5000,5010.5
XS Rating Curve= 0 ,0
Exp/Cntr=0.3,0.1

Type RM Length L Ch R = 1 ,1440    ,414,414,414
BEGIN DESCRIPTION:
WFSJR 066 3.0
END DESCRIPTION:
XS GIS Cut Line= 3
      3711823.33     10256043.11      3712548.23     10255506.84
      3712817.85     10255361.07
#Sta/Elev= 30
  4098.3  338.97  4203.4  335.27  4231.2  335.49  4275.1   332.5  4302.9  331.88
  4480.6  330.58  4484.7  330.33  4628.6  326.84  4696.7  326.97  4761.4  325.12
  4775.6  323.71  4788.5  324.35  4838.6  322.73  4861.6  324.84  4974.7  325.28
  4982.7  325.78    5000   322.7  5001.7   321.1  5005.2   321.1  5010.9  324.36
  5019.6  326.43  5056.4  326.35  5063.4  327.64  5079.1  327.51  5107.2   329.7
  5113.2  328.26    5129  328.88    5136  330.58    5189  334.26  5306.5  342.85
#Mann= 11 ,-1 , 0
  4098.3     .11       0  4480.6     .17       0  4484.7     .11       0
  4628.6     .17       0  4761.4     .17       0  4861.6     .17       0
  4974.7     .15       0  4982.7     .08       0  5019.6     .15       0
  5056.4     .17       0    5189     .11       0
Bank Sta=4982.7,5019.6
XS Rating Curve= 0 ,0
Exp/Cntr=0.3,0.1

Type RM Length L Ch R = 1 ,1026    ,499,499,499
BEGIN DESCRIPTION:
WFSJR 066 2.0
END DESCRIPTION:
XS GIS Cut Line= 3
      3712096.81     10256285.27      3712526.46     10256019.67
      3712917.83     10255561.09
#Sta/Elev= 30
  4096.1  335.22  4156.8  333.61  4179.6  334.07    4203  332.21  4231.5  331.54
  4332.5  329.56  4340.1  330.32  4361.3  329.28  4376.7  329.83  4408.7  327.89
  4498.4  327.66  4571.7  325.23  4651.3   324.4  4686.5  325.58  4778.7  323.27
  4785.3  324.42  4842.4  324.22  4863.2  325.73  4903.5  325.12  4963.1  323.28
    4984  324.63  5004.2  319.41  5007.7  319.41  5020.1  323.67  5033.4  324.51
  5041.1  324.85  5061.9   327.3  5098.2  329.05  5177.1  336.64  5204.1  338.63
#Mann= 10 ,-1 , 0
  4096.1     .17       0  4231.5     .17       0  4408.7     .17       0
  4571.7     .17       0  4686.5     .17       0  4903.5     .17       0
    4984     .08       0  5033.4     .15       0  5041.1     .17       0
  5177.1     .11       0
#XS Ineff= 1 ,-1
    4540  4891.8  325.56
Permanent Ineff=
       F
Bank Sta=4984,5033.4
XS Rating Curve= 0 ,0
Exp/Cntr=0.3,0.1

Type RM Length L Ch R = 1 ,527     ,388,388,388
BEGIN DESCRIPTION:
WFSJR 066 1.0
END DESCRIPTION:
XS GIS Cut Line= 3
      3712218.03     10256679.75      3712831.15     10256399.88
       3713180.1     10255558.76
#Sta/Elev= 30
  3813.9  333.12  3872.5  333.15  3941.6  331.42  4016.2  332.31  4085.3  329.53
  4143.5  330.81  4257.6  327.56  4372.7  326.65  4407.3  324.65  4483.3  325.54
  4508.2  325.63  4605.7  322.42  4651.6  323.32  4681.5  322.24  4704.8  322.33
  4723.3  324.27  4746.4  323.38    4758   321.9  4828.4   322.8    4898  322.72
  4973.7  322.77  4989.1  322.71  4993.7  318.62  4997.2  318.62  5006.2  321.54
  5018.4   322.6  5036.8  323.23    5151  328.19  5297.2  335.51  5398.5  339.27
#Mann= 10 ,-1 , 0
  3813.9     .17       0  4483.3     .17       0  4681.5     .17       0
  4828.4     .17       0    4898     .15       0  4973.7     .15       0
  4989.1     .07       0  5018.4     .15       0  5036.8     .15       0
    5151     .17       0
#XS Ineff= 2 ,-1
    4350  4475.9  325.75    4510  4723.3  324.27
Permanent Ineff=
       F       F
Bank Sta=4989.1,5018.4
XS Rating Curve= 0 ,0
Exp/Cntr=0.3,0.1

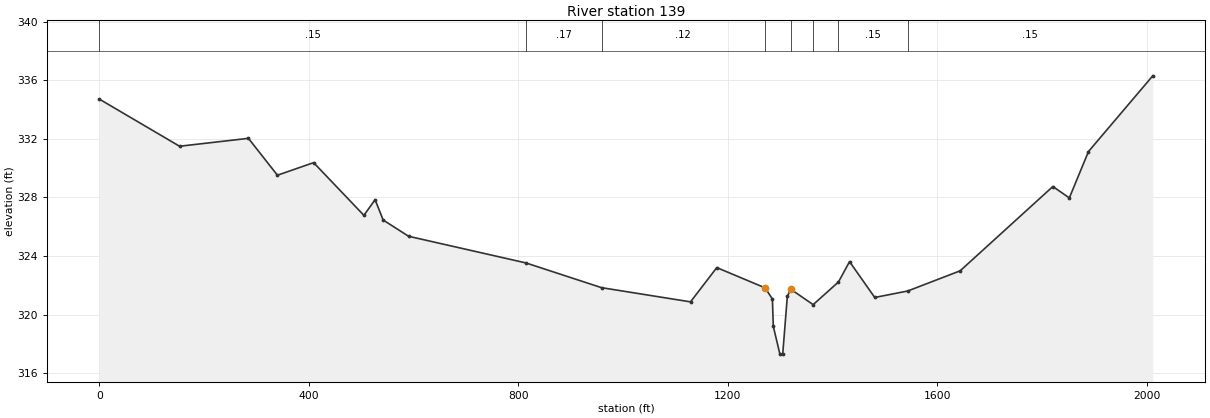
Type RM Length L Ch R = 1 ,139     ,0,0,0
XS GIS Cut Line= 4
      3712154.26     10256774.62      3713024.48     10256451.27
      3713317.45     10256119.24      3713523.61      10255511.6
#Sta/Elev= 30
       0  334.72   153.2   331.5   284.7  332.04   340.1  329.52   409.2  330.38
   505.2  326.78   526.6  327.85     542  326.46   590.6  325.35   814.6  323.53
     959  321.84  1128.9  320.87  1179.1  323.21  1271.1  321.83  1285.3  321.07
    1287   319.2  1299.6   317.3    1305   317.3  1313.8  321.25  1320.5  321.73
  1363.1  320.68  1411.5  322.23  1432.6  323.62  1480.7  321.17  1543.5  321.61
  1643.8  322.99  1820.9  328.75  1852.3  327.97  1888.9  331.14  2011.6  336.31
#Mann= 8 ,-1 , 0
       0     .15       0   814.6     .17       0     959     .12       0
  1271.1     .06       0  1320.5     .12       0  1363.1     .12       0
  1411.5     .15       0  1543.5     .15       0
Bank Sta=1271.1,1320.5
XS Rating Curve= 0 ,0
Exp/Cntr=0.3,0.1

Chan Stop Cuts=-1
Use User Specified Reach Order=0
Composite Channel Slope=5