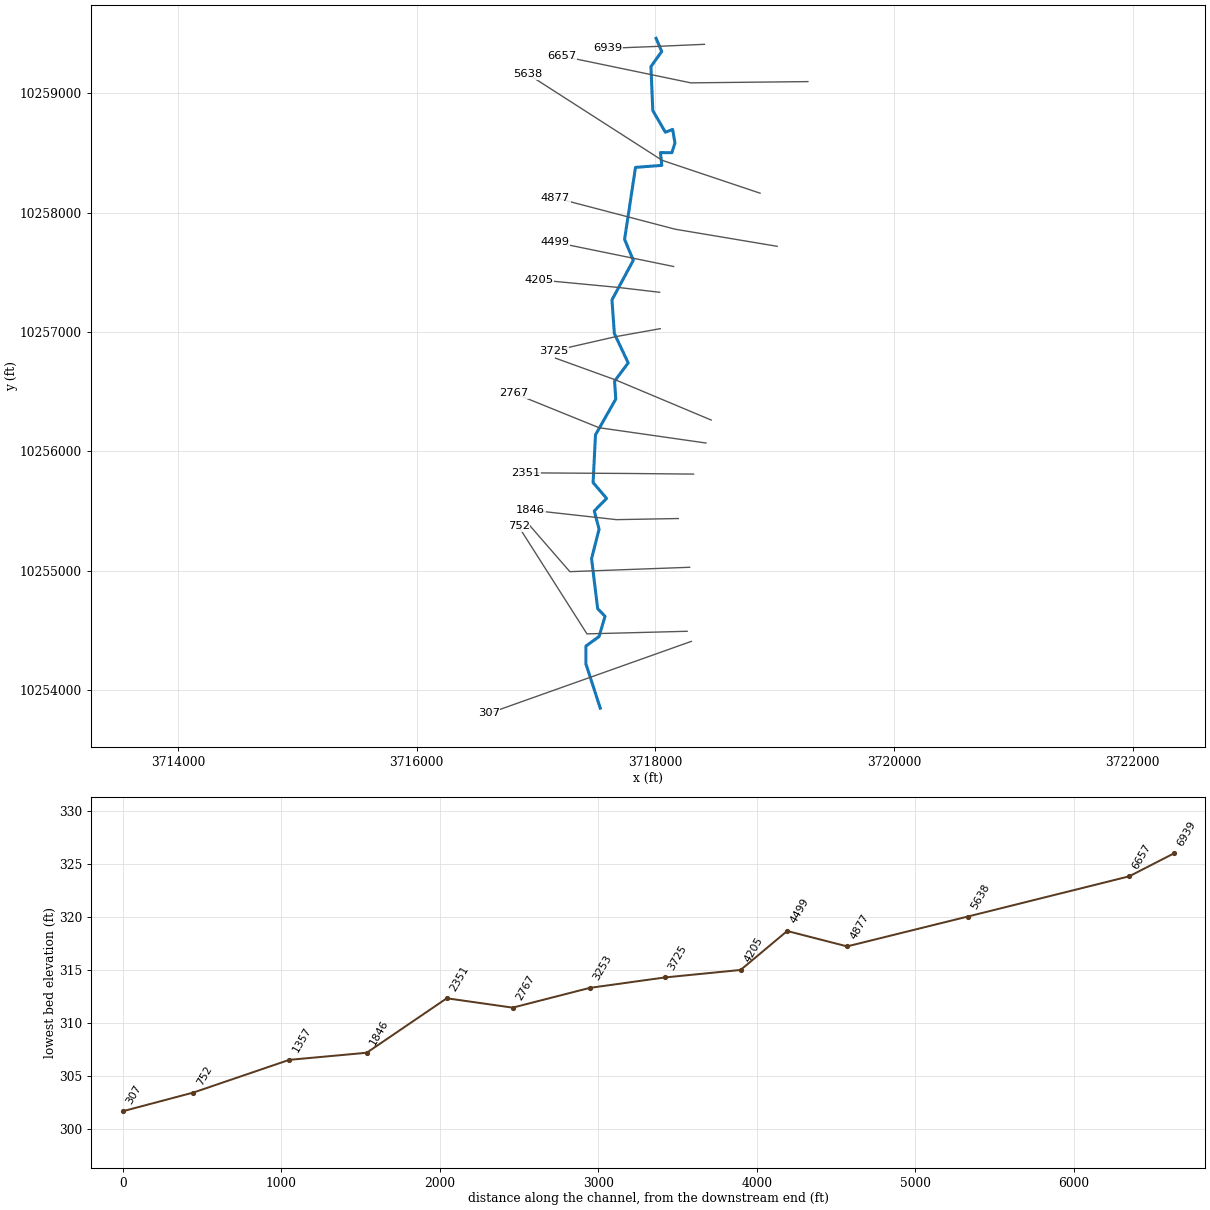
--- WFSJR 068.prj (project) ---

Proj Title=WFSJR 068 Base Level Engineering
Current Plan=p01
Default Exp/Contr=0.3,0.1
English Units
Geom File=g01
Flow File=f01
Plan File=p01
Y Axis Title=Elevation
X Axis Title(PF)=Main Channel Distance
X Axis Title(XS)=Station
BEGIN DESCRIPTION:
WFSJR 068
END DESCRIPTION:
DSS Export Rating Curves= 0
DSS Export Rating Curve Sorted= 0
DSS Export Volume Flow Curves= 0
DXF OffsetX= 0
DXF OffsetY= 0
DXF ScaleX= 1
DXF ScaleY= 10

--- WFSJR 068.p01 (plan) ---

Plan Title=Multiple Run
Program Version=4.10
Short Identifier=Multiple
Geom File=g01
Flow File=f01
Subcritical Flow
K Sum by GR= 0
Std Step Tol= 0.01
Critical Tol= 0.01
Num of Std Step Trials= 20
Max Error Tol= 0.3
Flow Tol Ratio= 0.001
Split Flow NTrial= 30
Split Flow Tol= 0.02
Split Flow Ratio= 0.02
Log Output Level= 0
Friction Slope Method= 1
Unsteady Friction Slope Method= 2
Unsteady Bridges Friction Slope Method= 1
Parabolic Critical Depth
Global Vel Dist= 1 , 1 , 1
Global Log Level= 0
CheckData=True
Encroach Param=-1 ,0,0, 0
BEGIN DESCRIPTION:
Multiple Run
END DESCRIPTION:
Computation Interval=1HOUR
Output Interval=1HOUR
Run HTab= 0
Run UNet= 0
Run PostProcess= 0
Run WQNet= 0
UNET Theta= 1
UNET Theta Warmup= 1
UNET ZTol= 0.02
UNET ZSATol= 0.05
UNET MxIter= 20
UNET MaxInSteps= 0
UNET DtIC= 0
UNET DtMin= 0
UNET MaxCRTS= 20
UNET WFStab= 2
UNET SFStab= 1
UNET WFX= 1
UNET SFX= 1
UNET DSS MLevel= 4
UNET DZMax Abort= 100
UNET Convert EG Bridges= 0
UNET Use Existing IB Tables=-1
UNET Froude Reduction=False
UNET Froude Limit= 1
UNET Froude Power= 10
UNET Time Slicing=0,0, 5
UNET Junction Losses=0
Instantaneous Interval=1HOUR
Write IC File= 0
Write IC File at Sim End=0
Echo Input=False
Echo Parameters=False
Echo Output=False
Write Detailed= 0
WQ AD Non Conservative
WQ ULTIMATE=-1
WQ Max Comp Step=1HOUR
WQ Output Interval=15MIN
WQ Output Selected Increments= 0
WQ Output face flow=0
WQ Output face velocity=0
WQ Output face area=0
WQ Output face dispersion=0
WQ Output cell volume=0
WQ Output cell surface area=0
WQ Output cell continuity=0
WQ Output cumulative cell continuity=0
WQ Output face conc=0
WQ Output face dconc_dx=0
WQ Output face courant=0
WQ Output face peclet=0
WQ Output face adv mass=0
WQ Output face disp mass=0
WQ Output cell mass=0
WQ Output cell source sink temp=0
WQ Output cell source sink nsm=0
WQ Output MaxMinRange=-1
WQ Daily Max Min Mean=-1
WQ Daily Range=0
WQ Daily Time=0
WQ Create Restart=0
WQ Fixed Restart=0
WQ System Summary=0
WQ Use Fixed Temperature=0
Sorting and Armoring Iterations= 10
XS Update Threshold= 0.02
Hydraulics Update Threshold= 0.02
Energy Slope Method= 1
Volume Change Method= 0
XS Weighting Method= 0
Number of US Weighted Cross Sections= 1
Number of DS Weighted Cross Sections= 1
Upstream XS Weight=0.25
Main XS Weight=0.5
Downstream XS Weight=0.25
Number of DS XS's Weighted with US Boundary= 1
Upstream Boundary Weight= 1
Weight of XSs Associated with US Boundary= 0
Number of US XS's Weighted with DS Boundary= 1
Downstream Boundary Weight= 0.5
Weight of XSs Associated with DS Boundary= 0.5
Sediment Output Level= 4
Mass or Volume Output= 0
Output Increment Type= 1
Profile and TS Output Increment= 10
XS Output Flag= 0
XS Output Increment= 10
Disregard all LS=0
Disregard all Conn=0
Disregard all Breaches=0
Disregard all Pumps=0

--- WFSJR 068.f01 (steady flow) ---

Flow Title=Multiple
Program Version=4.10
Number of Profiles= 7
Profile Names=10-year,25-year,50-year,1pct_min,100-year,1pct_plu,500-year
River Rch & RM=WFSJR 068,Reach-1         ,6939
     361     470     619     268     809    2443    1431
River Rch & RM=WFSJR 068,Reach-1         ,3725
     482     640     852     374    1128    3407    2043
Boundary for River Rch & Prof#=WFSJR 068,Reach-1         , 1
Up Type= 0
Dn Type= 3
Dn Slope=0.0016
Boundary for River Rch & Prof#=WFSJR 068,Reach-1         , 2
Up Type= 0
Dn Type= 3
Dn Slope=0.0016
Boundary for River Rch & Prof#=WFSJR 068,Reach-1         , 3
Up Type= 0
Dn Type= 3
Dn Slope=0.0016
Boundary for River Rch & Prof#=WFSJR 068,Reach-1         , 4
Up Type= 0
Dn Type= 3
Dn Slope=0.0016
Boundary for River Rch & Prof#=WFSJR 068,Reach-1         , 5
Up Type= 0
Dn Type= 3
Dn Slope=0.0016
Boundary for River Rch & Prof#=WFSJR 068,Reach-1         , 6
Up Type= 0
Dn Type= 3
Dn Slope=0.0016
Boundary for River Rch & Prof#=WFSJR 068,Reach-1         , 7
Up Type= 0
Dn Type= 3
Dn Slope=0.0016
DSS Import GetInterval= 0
DSS Import GetPeak= 0
DSS Import FillOption= 0

--- WFSJR 068.g01 (geometry) ---

Geom Title=Existing Conditions
Program Version=4.10

River Reach=WFSJR 068       ,Reach-1
Reach XY= 30
      3718006.13     10259459.88       3718053.3     10259349.41
      3717963.07     10259223.49      3717978.56     10258854.48
      3718084.28     10258672.67      3718144.88     10258696.92
      3718164.41     10258583.12      3718138.15     10258501.64
      3718042.53     10258502.31      3718053.98     10258395.25
      3717833.59     10258378.55       3717742.2     10257775.51
      3717815.03     10257599.99      3717636.34     10257267.95
      3717656.37     10256985.89      3717772.46     10256739.93
      3717658.23     10256586.84      3717668.23     10256436.84
      3717498.23     10256136.84      3717478.23     10255736.84
      3717591.43      10255604.6      3717488.23     10255499.26
      3717528.23     10255346.84       3717465.5     10255098.91
      3717516.66      10254679.8      3717578.23     10254616.84
      3717528.23     10254446.84      3717418.23     10254366.84
      3717418.23     10254216.84      3717538.23     10253846.84

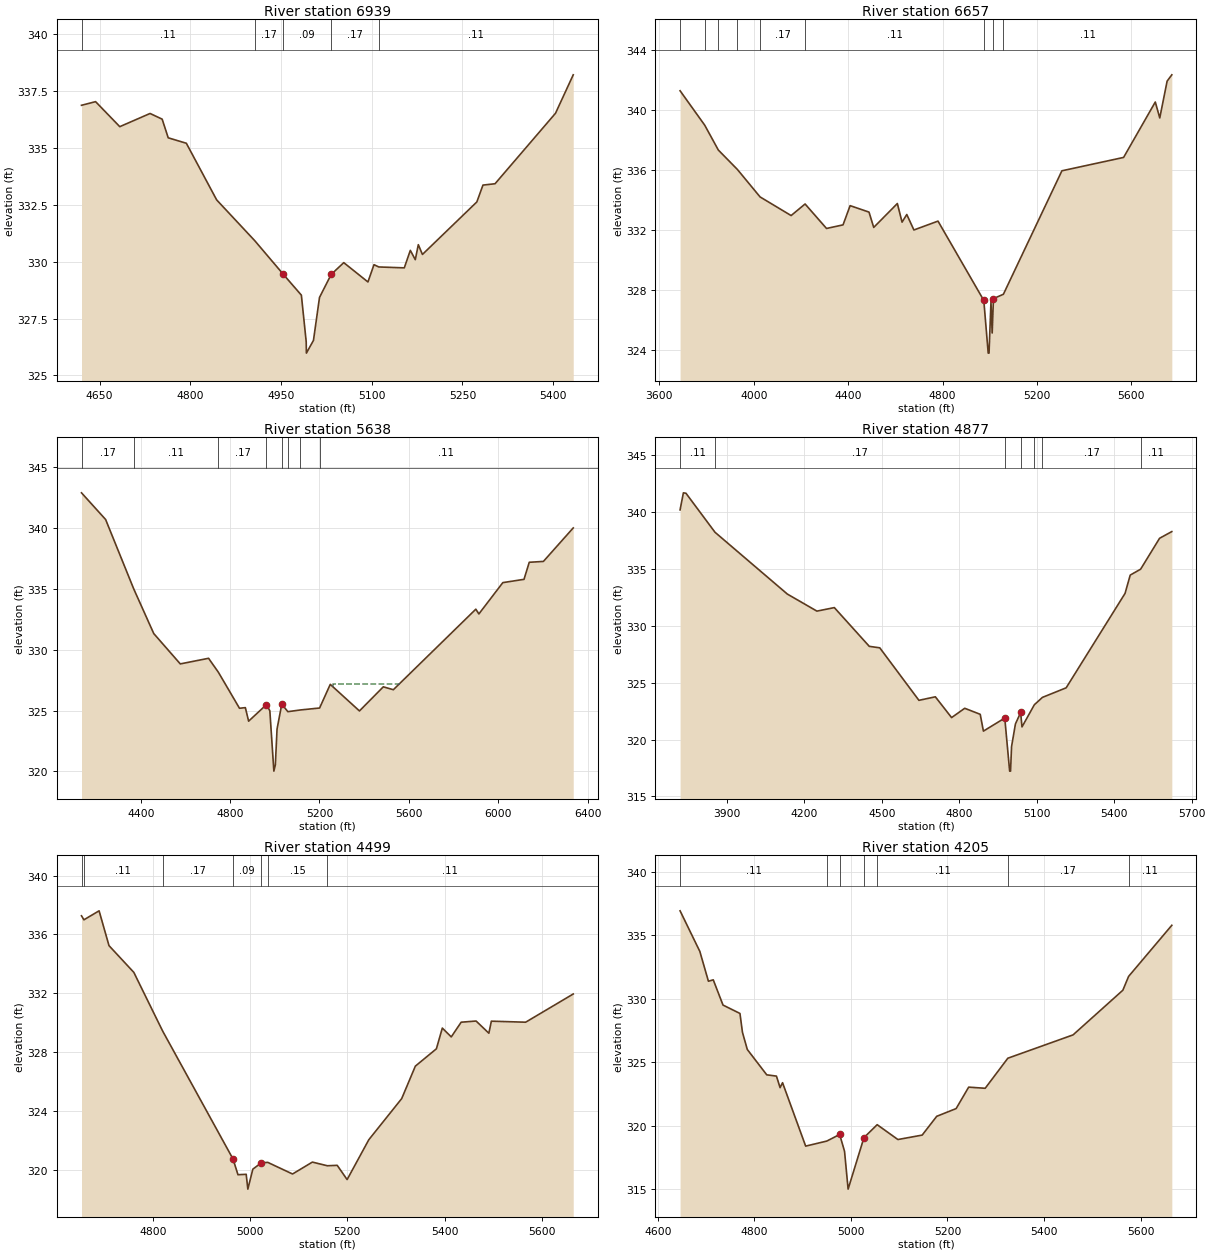
Type RM Length L Ch R = 1 ,6939    ,282,282,282
BEGIN DESCRIPTION:
WFSJR 068 12.0
END DESCRIPTION:
XS GIS Cut Line= 3
      3718411.12     10259409.75      3717994.45     10259391.52
      3717598.62      10259375.9
#Sta/Elev= 30
  4620.1  336.88  4643.4  337.04  4683.4  335.94  4733.5  336.52  4753.5  336.27
  4763.5  335.45  4793.5  335.21  4843.6  332.72  4906.8  330.92  4953.7  329.45
  4983.7  328.53  4991.7  326.48    4992  325.98  5003.7  326.54  5013.7  328.43
    5033  329.44  5053.8  329.96  5093.8  329.11  5103.8  329.87  5111.7  329.77
  5153.9  329.73  5163.9   330.5  5172.1  330.09  5177.1  330.75  5183.9  330.32
  5273.9  332.63    5284  333.37    5304  333.43    5404  336.53  5433.3  338.22
#Mann= 5 ,-1 , 0
  4620.1     .11       0  4906.8     .17       0  4953.7     .09       0
    5033     .17       0  5111.7     .11       0
Bank Sta=4953.7,5033
XS Rating Curve= 0 ,0
Exp/Cntr=0.3,0.1

Type RM Length L Ch R = 1 ,6657    ,1019,1019,1019
BEGIN DESCRIPTION:
WFSJR 068 11.0
END DESCRIPTION:
XS GIS Cut Line= 3
      3719278.35     10259097.25      3718296.54     10259086.83
      3717217.87     10259311.07
#Sta/Elev= 30
  3687.8  341.29  3792.1     339    3850  337.34  3930.6  336.05  4026.8  334.22
  4158.3  332.98  4217.5  333.75  4308.3  332.12  4378.3  332.36  4408.3  333.64
  4488.3  333.21  4508.3  332.19  4608.4  333.78  4628.4  332.54  4648.4  333.05
  4678.5  332.02  4780.7  332.61  4974.7  327.33  4993.4  323.82  4996.9  323.82
  5005.1  327.22  5010.2  325.16  5015.6  327.45  5057.8  327.74  5305.7  335.96
  5567.1  336.85  5701.4  340.54  5720.3  339.48  5751.5  341.93  5771.4  342.35
#Mann= 9 ,-1 , 0
  3687.8     .17       0  3792.1     .11       0    3850     .17       0
  3930.6     .11       0  4026.8     .17       0  4217.5     .11       0
  4974.7     .07       0  5015.6     .17       0  5057.8     .11       0
Bank Sta=4974.7,5015.6
XS Rating Curve= 0 ,0
Exp/Cntr=0.3,0.1

Type RM Length L Ch R = 1 ,5638    ,761,761,761
BEGIN DESCRIPTION:
WFSJR 068 10.0
END DESCRIPTION:
XS GIS Cut Line= 3
      3718877.22     10258162.37      3718056.67     10258437.67
      3716932.42     10259159.45
#Sta/Elev= 30
  4134.5  342.87  4242.5  340.68  4368.2  334.99    4458  331.32  4576.8  328.83
  4703.4  329.29  4747.5  328.14  4841.8  325.19  4868.1  325.24  4882.7  324.13
  4962.7  325.49  4977.7  324.98  4995.7  320.03  5002.3  320.53    5010  323.49
  5031.2  325.53  5058.3  324.91  5114.6  325.05  5200.5  325.21  5248.2  327.15
  5378.9  324.97  5485.8  326.95  5530.6  326.71  5899.9  333.32  5913.6  332.93
  6020.8   335.5  6115.6  335.77  6139.1  337.17  6202.5  337.24    6336  339.99
#Mann= 8 ,-1 , 0
  4134.5     .17       0  4368.2     .11       0  4747.5     .17       0
  4962.7     .09       0  5031.2     .17       0  5058.3     .15       0
  5114.6     .17       0  5200.5     .11       0
#XS Ineff= 1 ,-1
  5261.1    5560  327.19
Permanent Ineff=
       F
Bank Sta=4962.7,5031.2
XS Rating Curve= 0 ,0
Exp/Cntr=0.3,0.1

Type RM Length L Ch R = 1 ,4877    ,378,378,378
BEGIN DESCRIPTION:
WFSJR 068 9.0
END DESCRIPTION:
XS GIS Cut Line= 3
      3719020.48     10257717.04      3718166.33     10257860.27
      3717162.02     10258123.06
#Sta/Elev= 30
    3719  340.21  3731.8  341.71  3741.9  341.67  3854.2  338.24  4134.4   332.8
  4248.9   331.3  4316.3  331.61  4451.7   328.2  4492.3  328.07  4643.9  323.45
  4707.5  323.76  4770.4  321.93  4821.2  322.75  4881.3  322.22  4893.6  320.74
  4976.3  321.89  4995.2  317.22  4998.7  317.22  5002.6  319.38  5017.6  321.37
  5037.8  322.38    5043  321.11  5090.8  323.06  5122.2  323.71    5214  324.55
  5442.1  332.86  5462.1  334.47  5502.4  334.99  5575.8  337.71  5623.2   338.3
#Mann= 7 ,-1 , 0
    3719     .11       0  3854.2     .17       0  4976.3     .09       0
  5037.8     .15       0  5090.8     .11       0  5122.2     .17       0
  5502.4     .11       0
Bank Sta=4976.3,5037.8
XS Rating Curve= 0 ,0
Exp/Cntr=0.3,0.1

Type RM Length L Ch R = 1 ,4499    ,294,294,294
BEGIN DESCRIPTION:
WFSJR 068 8.0
END DESCRIPTION:
XS GIS Cut Line= 2
      3718153.32     10257547.77      3717161.98     10257750.72
#Sta/Elev= 30
    4653  337.27    4658     337  4689.2  337.61  4709.6  335.24  4760.7  333.42
  4819.8  329.44  4964.8  320.72    4975  319.65  4991.9  319.68  4995.3  318.67
  5005.6  320.03    5023  320.46  5036.3  320.49  5087.3   319.7  5128.1  320.51
  5158.9  320.26  5179.2  320.29  5199.6  319.32  5244.2  322.03  5311.9  324.83
    5340  327.04  5383.3  328.22  5395.5  329.63  5413.9  329.03  5434.3  330.03
    5465  330.11  5491.3  329.28  5496.4   330.1    5567  330.03  5664.9  331.95
#Mann= 7 ,-1 , 0
    4653     .17       0    4658     .11       0  4819.8     .17       0
  4964.8     .09       0    5023     .17       0  5036.3     .15       0
  5158.9     .11       0
Bank Sta=4964.8,5023
XS Rating Curve= 0 ,0
Exp/Cntr=0.3,0.1

Type RM Length L Ch R = 1 ,4205    ,480,480,480
BEGIN DESCRIPTION:
WFSJR 068 7.0
END DESCRIPTION:
XS GIS Cut Line= 3
      3718036.13     10257331.62      3717684.75      10257372.9
      3717023.13     10257435.79
#Sta/Elev= 30
  4646.2  336.94  4687.1  333.74  4704.9  331.39  4714.9   331.5  4735.1  329.51
  4770.2  328.85  4775.4  327.36  4785.4  326.01  4825.7  324.01  4845.8  323.91
  4853.3     323  4858.4  323.39  4906.3  318.39  4950.2  318.79  4976.7  319.31
  4986.8  317.98  4994.2     315    5027  319.06  5054.4  320.08  5097.3  318.91
  5147.6  319.26  5177.7  320.74  5217.9  321.35  5243.9  323.04  5278.1  322.95
    5325  325.32  5460.1  327.16  5563.2  330.68  5575.1  331.77  5664.6   335.8
#Mann= 7 ,-1 , 0
  4646.2     .11       0  4950.2     .15       0  4976.7     .09       0
    5027     .15       0  5054.4     .11       0    5325     .17       0
  5575.1     .11       0
Bank Sta=4976.7,5027
XS Rating Curve= 0 ,0
Exp/Cntr=0.3,0.1

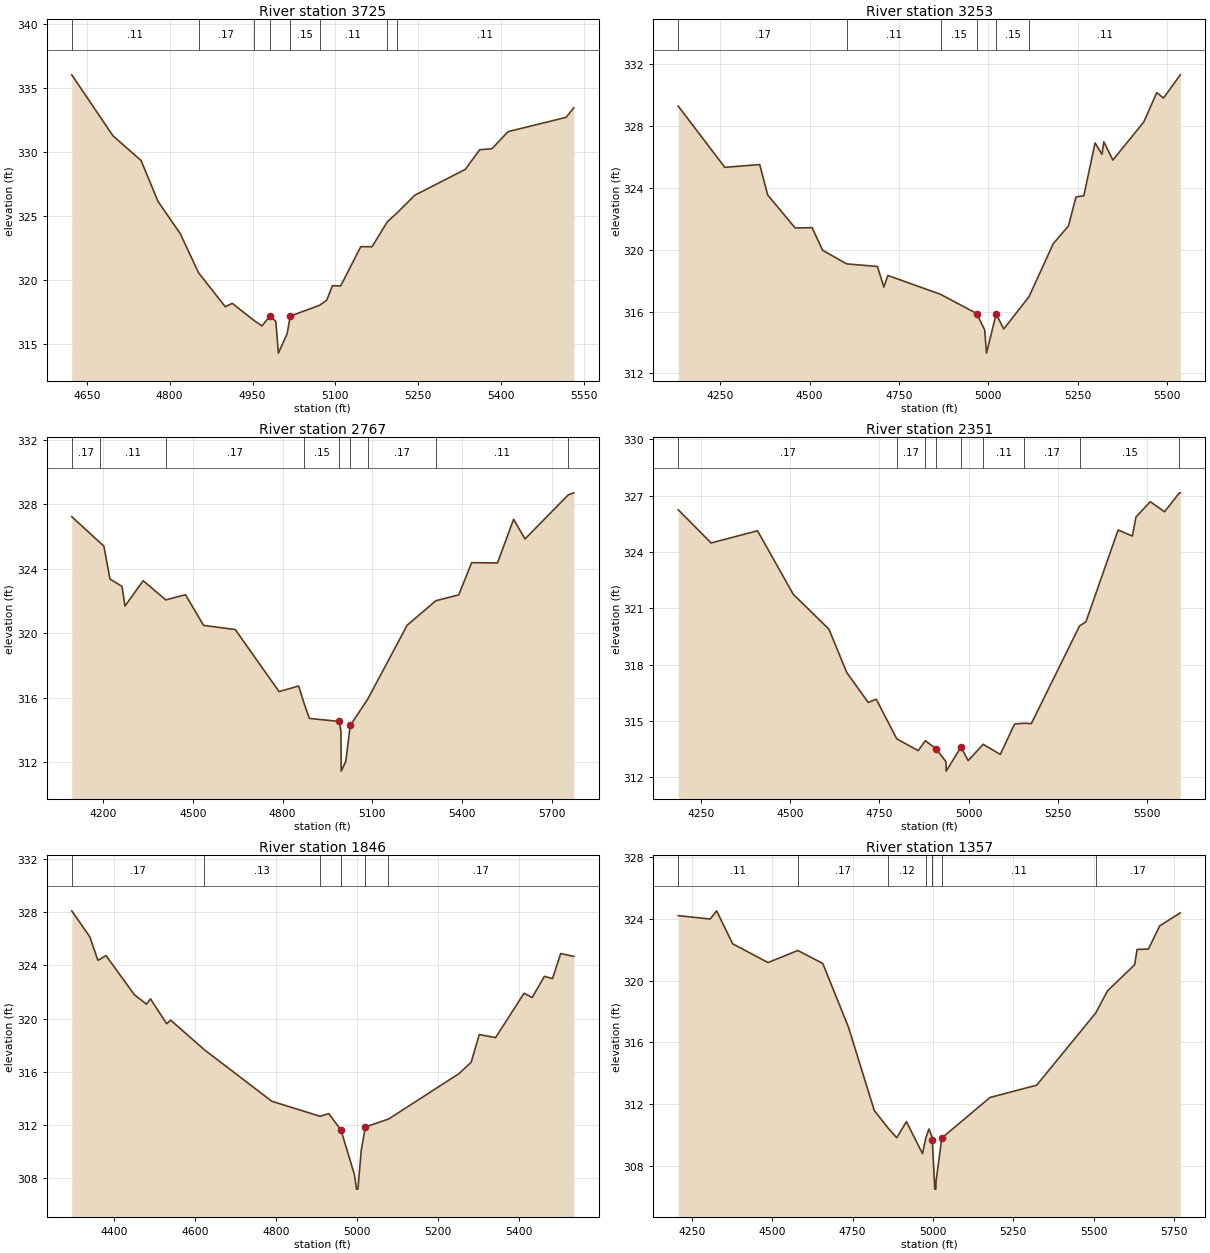
Type RM Length L Ch R = 1 ,3725    ,472,472,472
BEGIN DESCRIPTION:
WFSJR 068 6.0
END DESCRIPTION:
XS GIS Cut Line= 3
      3718041.31     10257026.93      3717670.14     10256960.31
       3717151.8     10256842.29
#Sta/Elev= 30
  4622.9     336  4697.5  331.24  4748.3  329.32  4778.8  326.14  4819.4   323.6
  4852.4  320.56  4900.7  317.91  4913.4  318.17  4952.1  316.86  4967.1  316.41
    4982  317.21  4992.2  316.76  4996.9  314.29  5012.6  315.79  5018.4  317.18
  5071.3  318.02  5084.4  318.42  5094.6  319.55  5109.6  319.53  5145.9  322.59
  5166.4  322.59  5193.9  324.53  5210.7  325.19  5243.8  326.61    5335  328.62
  5361.3  330.16  5383.2  330.23  5412.6  331.57  5517.4  332.68  5531.6  333.43
#Mann= 8 ,-1 , 0
  4622.9     .11       0  4852.4     .17       0  4952.1     .15       0
    4982     .09       0  5018.4     .15       0  5071.3     .11       0
  5193.9     .17       0  5210.7     .11       0
Bank Sta=4982,5018.4
XS Rating Curve= 0 ,0
Exp/Cntr=0.3,0.1

Type RM Length L Ch R = 1 ,3253    ,486,486,486
BEGIN DESCRIPTION:
WFSJR 068 5.0
END DESCRIPTION:
XS GIS Cut Line= 3
      3718467.89     10256261.06      3717668.23     10256596.84
      3717163.69     10256779.55
#Sta/Elev= 30
  4132.7  329.28  4262.9  325.32  4360.5   325.5  4382.9  323.53  4459.6   321.4
  4507.1  321.42  4536.3  319.96  4603.6  319.08  4689.7  318.91  4707.6  317.58
  4718.9  318.33  4866.3  317.11  4967.3  315.87  4989.6  314.81  4994.7  313.31
  5021.7  315.85  5042.9  314.87  5113.6  316.96  5181.2  320.38  5223.7  321.53
    5245  323.41  5266.8  323.48  5298.2   326.9  5317.5  326.16  5322.8  326.97
  5348.1  325.79  5434.7  328.26  5470.7  330.15  5489.6   329.8  5536.6   331.3
#Mann= 6 ,-1 , 0
  4132.7     .17       0  4603.6     .11       0  4866.3     .15       0
  4967.3     .09       0  5021.7     .15       0  5113.6     .11       0
Bank Sta=4967.3,5021.7
XS Rating Curve= 0 ,0
Exp/Cntr=0.3,0.1

Type RM Length L Ch R = 1 ,2767    ,416,416,416
BEGIN DESCRIPTION:
WFSJR 068 4.0
END DESCRIPTION:
XS GIS Cut Line= 3
       3718424.1     10256068.61      3717528.23     10256196.84
      3716811.19     10256487.21
#Sta/Elev= 30
    4095  327.23  4187.9  325.65  4202.3  325.41  4222.9  323.36  4262.9  322.91
    4273  321.69  4333.7  323.26  4409.3  322.07  4475.1  322.39  4535.7  320.49
  4641.7  320.23  4788.2  316.38  4853.6  316.73  4871.9  315.64  4889.3  314.72
  4989.9  314.53  4994.9  313.91  4995.9  311.45  5011.2  312.06    5026  314.28
  5084.7  315.92  5216.3   320.5  5312.3  322.02  5388.8  322.38    5432  324.38
  5518.3  324.36  5572.2  327.07  5610.3  325.85  5755.3  328.59  5773.6  328.71
#Mann= 9 ,-1 , 0
    4095     .17       0  4187.9     .11       0  4409.3     .17       0
  4871.9     .15       0  4989.9     .09       0    5026     .15       0
  5084.7     .17       0  5312.3     .11       0  5755.3     .17       0
Bank Sta=4989.9,5026
XS Rating Curve= 0 ,0
Exp/Cntr=0.3,0.1

Type RM Length L Ch R = 1 ,2351    ,505,505,505
BEGIN DESCRIPTION:
WFSJR 068 3.0
END DESCRIPTION:
XS GIS Cut Line= 3
      3718319.95     10255808.19      3717767.89      10255813.4
      3716913.69      10255818.6
#Sta/Elev= 30
  4186.4  326.25  4278.5  324.48  4408.5  325.13  4508.5  321.75  4608.5  319.89
  4658.5  317.58  4718.5  315.99    4741  316.16  4798.5  314.05  4858.5  313.42
  4878.5  313.95  4908.5  313.52  4936.5  312.83  4936.8  312.33  4978.5  313.61
  4998.5  312.89  5040.6  313.76  5088.5  313.22  5128.5  314.84  5155.7  314.88
  5175.4  314.86  5310.4  320.06  5328.5  320.29  5418.5  325.17  5458.5  324.85
  5468.5  325.86  5508.5  326.68  5548.5  326.14  5590.1  327.15  5592.7  327.15
#Mann= 9 ,-1 , 0
  4186.4     .17       0  4798.5     .17       0  4878.5     .15       0
  4908.5     .09       0  4978.5     .15       0  5040.6     .11       0
  5155.7     .17       0  5310.4     .15       0  5590.1     .17       0
Bank Sta=4908.5,4978.5
XS Rating Curve= 0 ,0
Exp/Cntr=0.3,0.1

Type RM Length L Ch R = 1 ,1846    ,489,489,489
BEGIN DESCRIPTION:
WFSJR 068 2.0
END DESCRIPTION:
XS GIS Cut Line= 3
       3718192.4     10255435.79      3717674.58     10255426.36
       3716955.5     10255506.09
#Sta/Elev= 30
  4294.6   328.1  4339.2  326.15  4359.2  324.38  4379.2  324.74  4449.2  321.81
  4479.2  321.09  4489.2  321.49  4529.2  319.62  4539.2  319.89  4622.3  317.67
  4789.2   313.8  4908.6  312.67    4930  312.87  4960.1  311.65  4993.4   308.3
  4998.6   307.2  5002.1   307.2  5010.4  310.13  5020.5  311.87  5077.7  312.46
  5251.9  315.87  5282.1  316.73  5302.2  318.81  5342.5  318.58  5412.9  321.91
    5433  321.59  5463.2  323.18  5483.3  323.01  5503.4  324.89    5536  324.68
#Mann= 6 ,-1 , 0
  4294.6     .17       0  4622.3     .13       0  4908.6     .15       0
  4960.1     .09       0  5020.5     .15       0  5077.7     .17       0
Bank Sta=4960.1,5020.5
XS Rating Curve= 0 ,0
Exp/Cntr=0.3,0.1

Type RM Length L Ch R = 1 ,1357    ,605,605,605
BEGIN DESCRIPTION:
WFSJR 068 1.0
END DESCRIPTION:
XS GIS Cut Line= 3
      3718287.11     10255027.22      3717283.52     10254990.48
      3716917.84     10255411.08
#Sta/Elev= 30
  4207.9  324.19  4307.2  323.97  4327.2   324.5  4377.3  322.37  4487.3  321.16
  4579.9  321.94  4657.5   321.1  4737.5  316.98  4817.6  311.61  4860.7  310.47
  4887.6  309.85  4917.6  310.89  4967.7  308.82  4977.7  309.82  4987.7  310.41
  4997.7  309.88  4998.2   309.7  5005.9  306.53  5009.4  306.53  5009.7  307.03
  5027.7  309.83  5177.8  312.45  5322.7  313.24  5506.3   317.9    5543  319.33
  5627.5  321.02  5635.1  322.01  5670.3  322.03  5705.4  323.53  5769.5  324.37
#Mann= 8 ,-1 , 0
  4207.9     .11       0  4579.9     .17       0  4860.7     .12       0
  4977.7     .11       0  4997.7     .11       0  4998.2     .06       0
  5027.7     .11       0  5506.3     .17       0
#XS Ineff= 1 ,-1
    4840  4917.6  310.89
Permanent Ineff=
       F
Bank Sta=4998.2,5027.7
XS Rating Curve= 0 ,0
Exp/Cntr=0.3,0.1

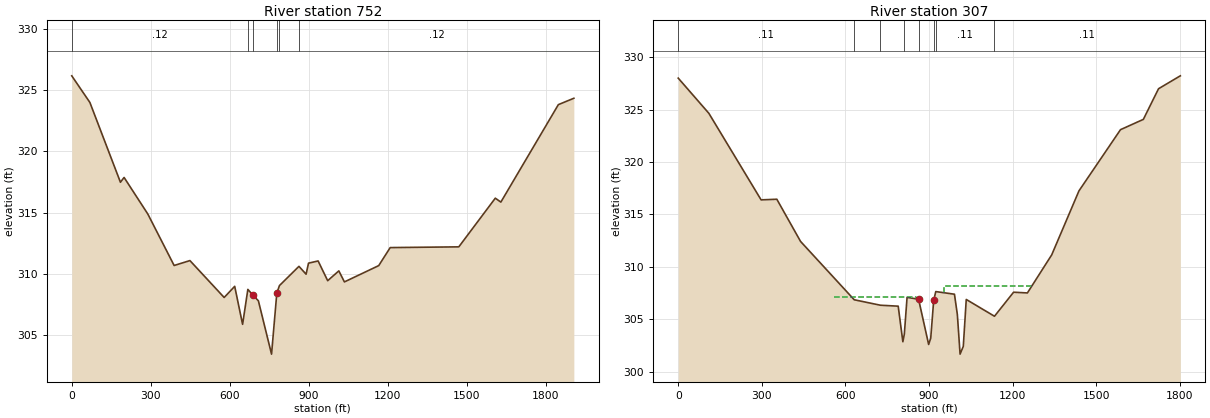
Type RM Length L Ch R = 1 ,752     ,445,445,445
XS GIS Cut Line= 3
      3718266.61     10254490.88      3717426.77     10254469.17
      3716853.85     10255369.78
#Sta/Elev= 30
       0  326.15    68.8  323.98   184.9  317.47   198.8  317.86   288.9  314.88
   388.9  310.68   448.9  311.08     579  308.07     619  308.98     649  305.88
     669  308.73     689  308.24     709   307.8     759  303.45     779  308.42
     789  309.04   863.1  310.61   890.2  309.97   899.5  310.87   935.9  311.05
   972.3  309.44  1014.7  310.24  1035.8  309.34  1166.2  310.67  1209.8  312.14
  1470.5   312.2  1609.1  316.17  1630.2  315.85  1848.7   323.8  1907.5  324.32
#Mann= 6 ,-1 , 0
       0     .12       0     669     .11       0     689     .06       0
     779     .11       0     789     .11       0   863.1     .12       0
#XS Ineff= 1 ,-1
     490     669  308.73
Permanent Ineff=
       F
Bank Sta=689,779
XS Rating Curve= 0 ,0
Exp/Cntr=0.3,0.1

Type RM Length L Ch R = 1 ,307     ,0,0,0
XS GIS Cut Line= 2
      3718301.33     10254406.24      3716604.28     10253802.94
#Sta/Elev= 30
       0  327.99   109.8  324.64   297.3  316.39   353.7  316.45   438.8  312.43
   631.3  306.87   725.4  306.35   789.1  306.26   805.8  302.87   811.1   303.6
   820.9   307.1   862.2  306.92   898.3  302.61   905.8  303.21   916.4  306.81
   923.9  307.65   990.9   307.4  1001.3  305.46  1011.1  301.69  1022.6  302.43
  1033.2   306.9  1134.5   305.3    1203  307.59  1252.6  307.52  1339.8  311.15
  1437.6  317.25  1586.6  323.08  1668.5  324.06    1723  326.98  1801.1  328.21
#Mann= 8 ,-1 , 0
       0     .11       0   631.3     .11       0   725.4     .11       0
   811.1     .11       0   862.2     .06       0   916.4     .11       0
   923.9     .11       0  1134.5     .11       0
#XS Ineff= 2 ,-1
     560   852.7  307.17   954.7    1270  308.18
Permanent Ineff=
       T       T
Bank Sta=862.2,916.4
XS Rating Curve= 0 ,0
Exp/Cntr=0.3,0.1

Chan Stop Cuts=-1
Use User Specified Reach Order=0
Composite Channel Slope=5