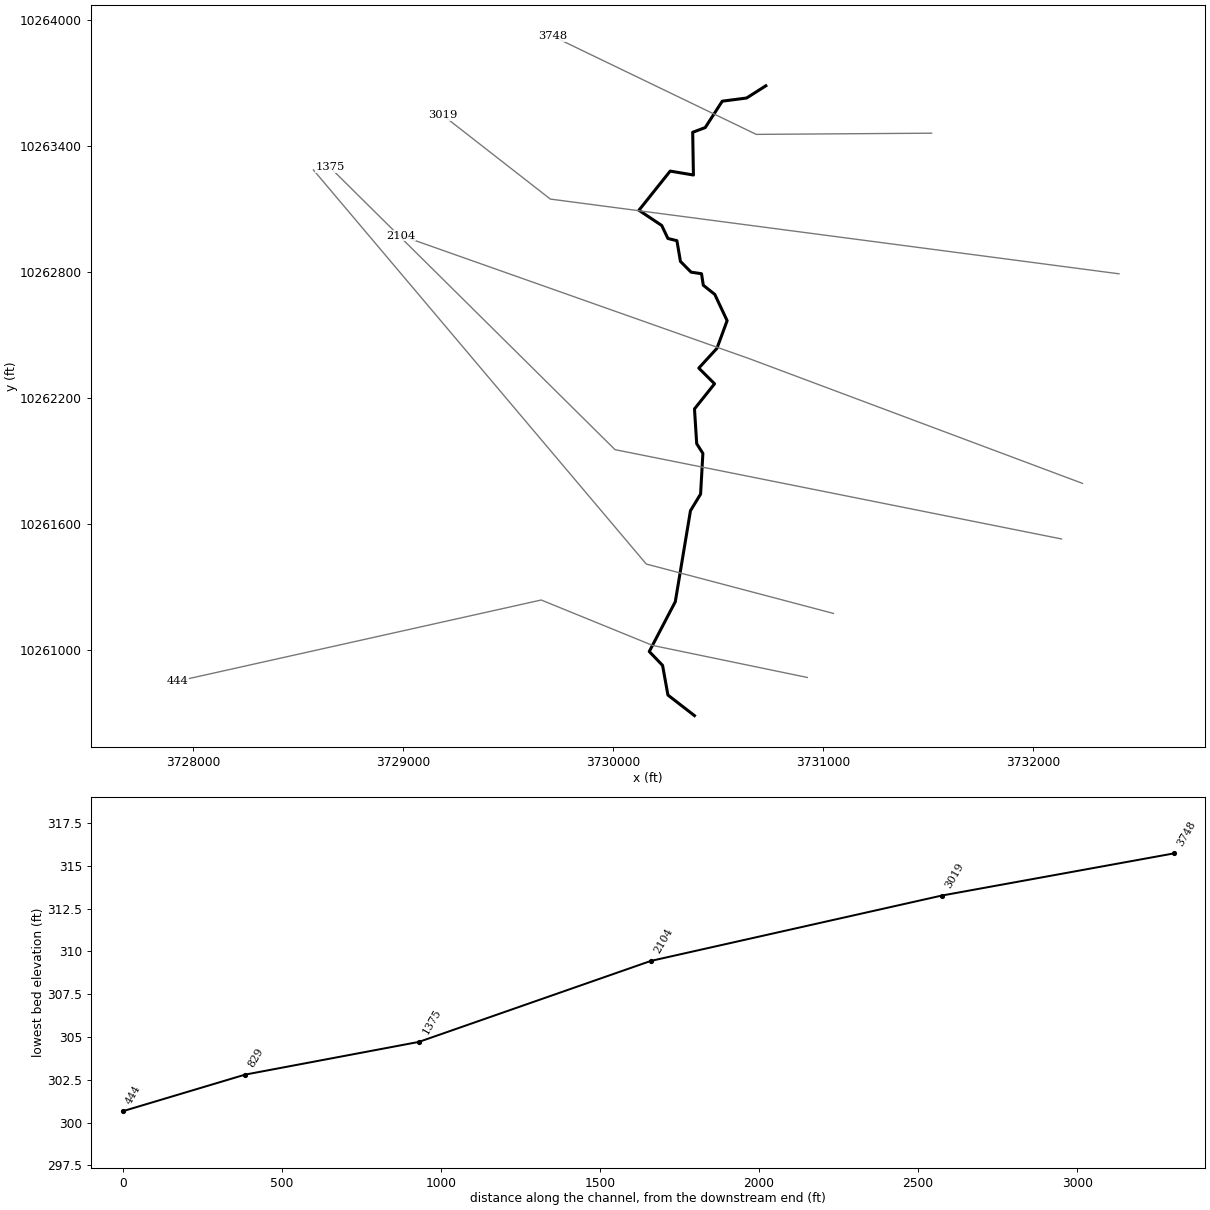
--- WFSJR 071.prj (project) ---

Proj Title=WFSJR 071 Base Level Engineering
Current Plan=p01
Default Exp/Contr=0.3,0.1
English Units
Geom File=g01
Flow File=f01
Plan File=p01
Y Axis Title=Elevation
X Axis Title(PF)=Main Channel Distance
X Axis Title(XS)=Station
BEGIN DESCRIPTION:
WFSJR 071
END DESCRIPTION:
DSS Export Rating Curves= 0
DSS Export Rating Curve Sorted= 0
DSS Export Volume Flow Curves= 0
DXF OffsetX= 0
DXF OffsetY= 0
DXF ScaleX= 1
DXF ScaleY= 10

--- WFSJR 071.p01 (plan) ---

Plan Title=Multiple Run
Program Version=4.10
Short Identifier=Multiple
Geom File=g01
Flow File=f01
Subcritical Flow
K Sum by GR= 0
Std Step Tol= 0.01
Critical Tol= 0.01
Num of Std Step Trials= 20
Max Error Tol= 0.3
Flow Tol Ratio= 0.001
Split Flow NTrial= 30
Split Flow Tol= 0.02
Split Flow Ratio= 0.02
Log Output Level= 0
Friction Slope Method= 1
Unsteady Friction Slope Method= 2
Unsteady Bridges Friction Slope Method= 1
Parabolic Critical Depth
Global Vel Dist= 1 , 1 , 1
Global Log Level= 0
CheckData=True
Encroach Param=-1 ,0,0, 0
BEGIN DESCRIPTION:
Multiple Run
END DESCRIPTION:
Computation Interval=1HOUR
Output Interval=1HOUR
Run HTab= 0
Run UNet= 0
Run PostProcess= 0
Run WQNet= 0
UNET Theta= 1
UNET Theta Warmup= 1
UNET ZTol= 0.02
UNET ZSATol= 0.05
UNET MxIter= 20
UNET MaxInSteps= 0
UNET DtIC= 0
UNET DtMin= 0
UNET MaxCRTS= 20
UNET WFStab= 2
UNET SFStab= 1
UNET WFX= 1
UNET SFX= 1
UNET DSS MLevel= 4
UNET DZMax Abort= 100
UNET Convert EG Bridges= 0
UNET Use Existing IB Tables=-1
UNET Froude Reduction=False
UNET Froude Limit= 1
UNET Froude Power= 10
UNET Time Slicing=0,0, 5
UNET Junction Losses=0
Instantaneous Interval=1HOUR
Write IC File= 0
Write IC File at Sim End=0
Echo Input=False
Echo Parameters=False
Echo Output=False
Write Detailed= 0
WQ AD Non Conservative
WQ ULTIMATE=-1
WQ Max Comp Step=1HOUR
WQ Output Interval=15MIN
WQ Output Selected Increments= 0
WQ Output face flow=0
WQ Output face velocity=0
WQ Output face area=0
WQ Output face dispersion=0
WQ Output cell volume=0
WQ Output cell surface area=0
WQ Output cell continuity=0
WQ Output cumulative cell continuity=0
WQ Output face conc=0
WQ Output face dconc_dx=0
WQ Output face courant=0
WQ Output face peclet=0
WQ Output face adv mass=0
WQ Output face disp mass=0
WQ Output cell mass=0
WQ Output cell source sink temp=0
WQ Output cell source sink nsm=0
WQ Output MaxMinRange=-1
WQ Daily Max Min Mean=-1
WQ Daily Range=0
WQ Daily Time=0
WQ Create Restart=0
WQ Fixed Restart=0
WQ System Summary=0
WQ Use Fixed Temperature=0
Sorting and Armoring Iterations= 10
XS Update Threshold= 0.02
Hydraulics Update Threshold= 0.02
Energy Slope Method= 1
Volume Change Method= 0
XS Weighting Method= 0
Number of US Weighted Cross Sections= 1
Number of DS Weighted Cross Sections= 1
Upstream XS Weight=0.25
Main XS Weight=0.5
Downstream XS Weight=0.25
Number of DS XS's Weighted with US Boundary= 1
Upstream Boundary Weight= 1
Weight of XSs Associated with US Boundary= 0
Number of US XS's Weighted with DS Boundary= 1
Downstream Boundary Weight= 0.5
Weight of XSs Associated with DS Boundary= 0.5
Sediment Output Level= 4
Mass or Volume Output= 0
Output Increment Type= 1
Profile and TS Output Increment= 10
XS Output Flag= 0
XS Output Increment= 10
Disregard all LS=0
Disregard all Conn=0
Disregard all Breaches=0
Disregard all Pumps=0

--- WFSJR 071.f01 (steady flow) ---

Flow Title=Multiple
Program Version=4.10
Number of Profiles= 7
Profile Names=10-year,25-year,50-year,1pct_min,100-year,1pct_plu,500-year
River Rch & RM=WFSJR 071,Reach-1         ,3748
     730    1002    1365     613    1850    5587    3509
River Rch & RM=WFSJR 071,Reach-1         ,829
     762    1048    1431     642    1940    5859    3691
Boundary for River Rch & Prof#=WFSJR 071,Reach-1         , 1
Up Type= 0
Dn Type= 3
Dn Slope=0.005
Boundary for River Rch & Prof#=WFSJR 071,Reach-1         , 2
Up Type= 0
Dn Type= 3
Dn Slope=0.005
Boundary for River Rch & Prof#=WFSJR 071,Reach-1         , 3
Up Type= 0
Dn Type= 3
Dn Slope=0.005
Boundary for River Rch & Prof#=WFSJR 071,Reach-1         , 4
Up Type= 0
Dn Type= 3
Dn Slope=0.005
Boundary for River Rch & Prof#=WFSJR 071,Reach-1         , 5
Up Type= 0
Dn Type= 3
Dn Slope=0.005
Boundary for River Rch & Prof#=WFSJR 071,Reach-1         , 6
Up Type= 0
Dn Type= 3
Dn Slope=0.005
Boundary for River Rch & Prof#=WFSJR 071,Reach-1         , 7
Up Type= 0
Dn Type= 3
Dn Slope=0.005
DSS Import GetInterval= 0
DSS Import GetPeak= 0
DSS Import FillOption= 0

--- WFSJR 071.g01 (geometry) ---

Geom Title=Existing Conditions
Program Version=4.10

River Reach=WFSJR 071       ,Reach-1
Reach XY= 30
      3730728.23     10263686.84      3730636.53     10263628.66
      3730520.57      10263613.5      3730439.54     10263487.83
      3730379.81      10263465.4      3730383.24     10263261.86
      3730272.54     10263280.53      3730123.64     10263093.98
      3730232.22     10263021.53      3730261.82     10262959.58
      3730304.61     10262949.01      3730321.45      10262850.4
      3730372.09     10262799.14      3730421.84     10262791.69
      3730430.29     10262736.81      3730484.99     10262693.19
      3730543.78     10262568.03       3730495.3      10262436.3
      3730408.87     10262342.24      3730483.95     10262267.44
      3730388.33     10262147.75       3730398.9     10261982.01
      3730428.33     10261935.84      3730417.41      10261742.1
      3730369.15      10261662.6      3730296.91     10261229.29
      3730172.92     10260992.07      3730236.31     10260926.05
      3730261.87     10260784.64      3730388.23     10260686.84

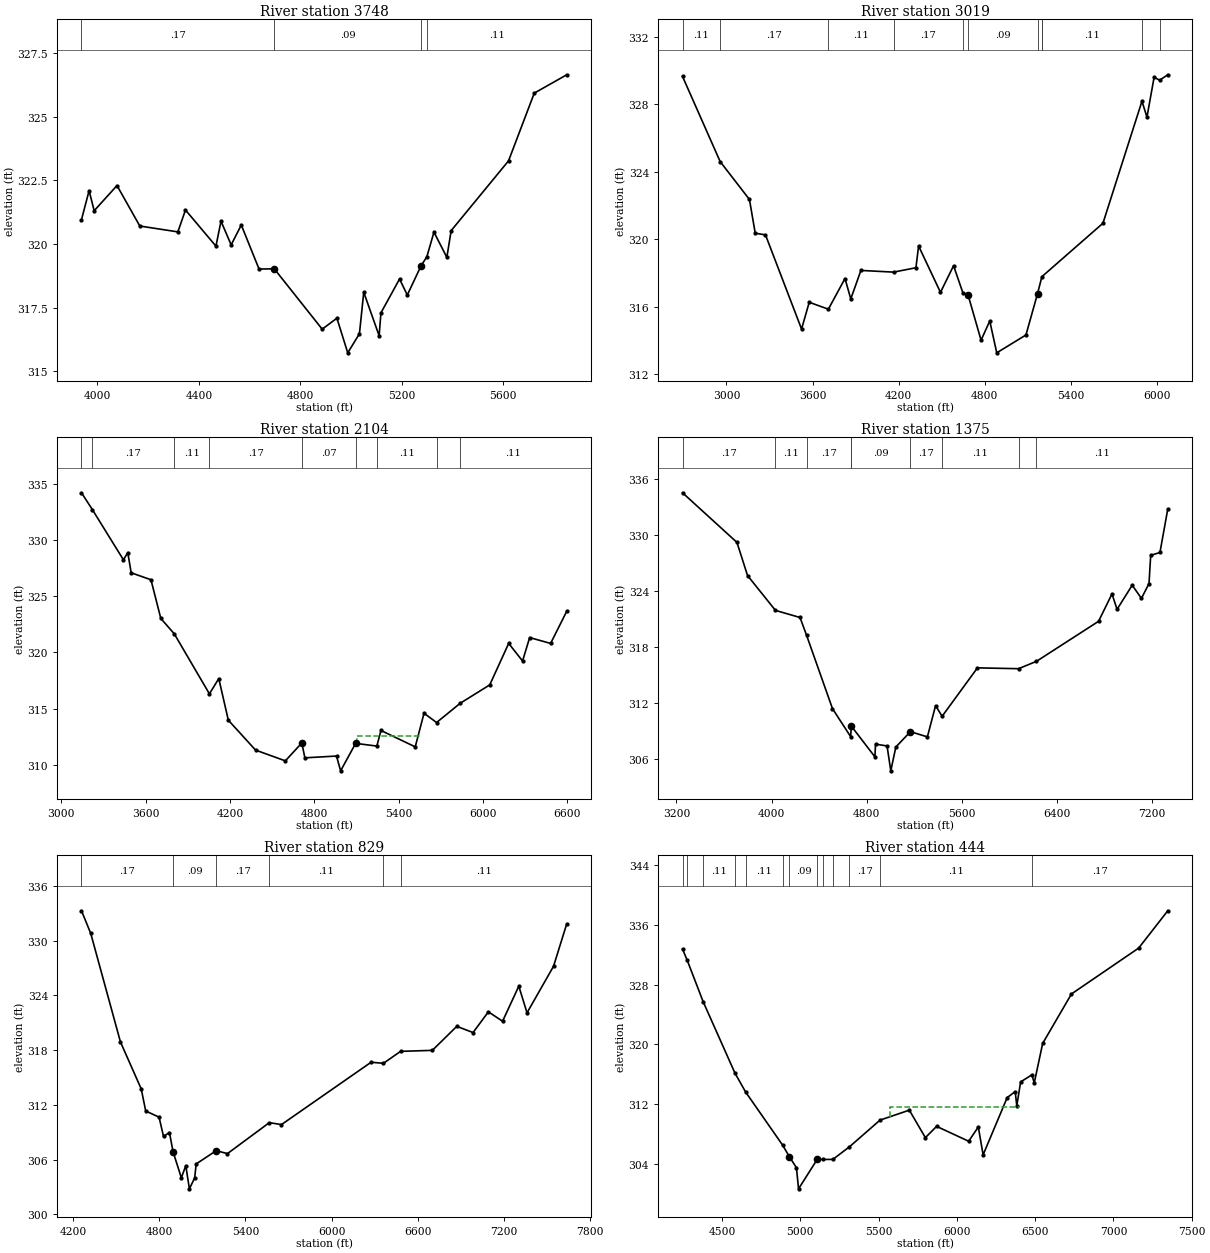
Type RM Length L Ch R = 1 ,3748    ,729,729,729
BEGIN DESCRIPTION:
WFSJR 071 5.0
END DESCRIPTION:
XS GIS Cut Line= 3
      3731517.89     10263461.07      3730682.59      10263455.4
      3729711.58     10263923.57
#Sta/Elev= 30
  3937.1  320.95  3967.1  322.09  3987.1   321.3  4077.1  322.29  4167.1   320.7
  4317.1  320.47  4347.1  321.33  4467.2  319.91  4487.2  320.89  4527.2  319.96
  4567.2  320.74  4637.2  319.01  4697.2  319.02  4886.1  316.65  4944.2  317.08
  4986.9  315.72    5033  316.47    5050   318.1  5110.7  316.39  5117.8  317.29
  5191.2  318.62  5221.7  317.99  5276.1  319.14  5298.7  319.49  5326.9  320.46
  5377.7  319.47  5394.7  320.52  5620.9  323.26  5722.4  325.92  5850.4  326.64
#Mann= 4 ,-1 , 0
  3937.1     .17       0  4697.2     .09       0  5276.1     .17       0
  5298.7     .11       0
Bank Sta=4697.2,5276.1
XS Rating Curve= 0 ,0
Exp/Cntr=0.3,0.1

Type RM Length L Ch R = 1 ,3019    ,915,915,915
BEGIN DESCRIPTION:
Mapping XS d32e86f5
END DESCRIPTION:
XS GIS Cut Line= 3
      3732410.07     10262791.33      3729701.69     10263147.24
      3729189.84     10263546.31
#Sta/Elev= 30
  2694.1  329.66  2956.2  324.61  3160.3  322.36  3200.6  320.36    3272  320.26
  3523.4  314.67  3576.8  316.26  3710.1  315.85    3826  317.67  3866.3  316.46
  3936.9  318.15  4164.6  318.05  4320.2  318.31  4338.8   319.6  4491.2  316.85
  4582.4  318.43  4648.6  316.79  4683.3   316.7    4774  314.01  4834.6  315.15
  4883.2  313.26  5086.7  314.32  5167.4  316.77  5197.7  317.78  5623.1  320.95
  5894.9  328.19  5929.8  327.25  5979.5  329.61  6018.6  329.44  6074.8  329.76
#Mann= 11 ,-1 , 0
  2694.1     .11       0  2956.2     .17       0  3710.1     .11       0
  4164.6     .17       0  4648.6     .11       0  4683.3     .09       0
  5167.4     .11       0  5197.7     .17       0  5197.7     .11       0
  5894.9     .17       0  6018.6     .11       0
#XS Ineff= 1 ,-1
    3180  4338.8   319.6
Permanent Ineff=
       F
Bank Sta=4683.3,5167.4
XS Rating Curve= 0 ,0
Exp/Cntr=0.3,0.1

Type RM Length L Ch R = 1 ,2104    ,729,729,729
BEGIN DESCRIPTION:
WFSJR 071 4.0
END DESCRIPTION:
XS GIS Cut Line= 3
      3732236.44     10261793.06      3730647.87     10262387.69
      3728991.39      10262973.1
#Sta/Elev= 30
  3143.9  334.25  3221.2  332.75  3442.2  328.27  3473.4  328.91  3497.4  327.11
  3638.2  326.49  3708.3  323.04  3804.4  321.66  4054.2  316.31  4120.9  317.67
  4188.8  313.96  4382.7  311.29  4594.6  310.33    4712  311.93  4733.4   310.6
  4958.7  310.76  4987.9  309.44  5094.7  311.89  5245.7  311.65    5275  313.04
  5518.9  311.58  5581.4  314.58  5670.7  313.75  5839.1  315.47  6049.2  317.11
  6183.8  320.81  6282.6  319.24  6333.1  321.33  6482.3  320.81    6597  323.68
#Mann= 9 ,-1 , 0
  3143.9     .11       0  3221.2     .17       0  3804.4     .11       0
  4054.2     .17       0    4712     .07       0  5094.7     .17       0
  5245.7     .11       0  5670.7     .17       0  5839.1     .11       0
#XS Ineff= 1 ,-1
    5108    5550  312.53
Permanent Ineff=
       F
Bank Sta=4712,5094.7
XS Rating Curve= 0 ,0
Exp/Cntr=0.3,0.1

Type RM Length L Ch R = 1 ,1375    ,546,546,546
BEGIN DESCRIPTION:
WFSJR 071 3.0
END DESCRIPTION:
XS GIS Cut Line= 3
      3732136.56     10261528.32      3730009.85     10261953.67
       3728652.1     10263298.41
#Sta/Elev= 30
  3251.6  334.52  3709.2   329.2  3798.4  325.64    4033  321.91  4239.5  321.15
  4295.1  319.22  4512.3  311.38  4665.3  308.37  4670.4  309.51  4869.2  306.21
  4874.3  307.57  4971.2  307.38  5002.6  304.71  5045.1  307.26  5167.5  308.91
  5310.3  308.35  5379.1   311.7  5434.2  310.56  5731.2  315.75  6076.9  315.66
  6227.3  316.45  6749.4  320.74  6862.5  323.68  6904.9  322.02  7032.2  324.61
    7110   323.2  7173.6  324.79  7187.8  327.81  7265.6  328.12  7331.4  332.78
#Mann= 9 ,-1 , 0
  3251.6     .17       0    4033     .11       0  4295.1     .17       0
  4665.3     .12       0  4670.4     .09       0  5167.5     .17       0
  5434.2     .11       0  6076.9     .17       0  6227.3     .11       0
Bank Sta=4670.4,5167.5
XS Rating Curve= 0 ,0
Exp/Cntr=0.3,0.1

Type RM Length L Ch R = 1 ,829     ,385,385,385
BEGIN DESCRIPTION:
WFSJR 071 2.0
END DESCRIPTION:
XS GIS Cut Line= 3
      3731050.16     10261173.64      3730158.61     10261408.96
      3728573.26     10263286.08
#Sta/Elev= 30
  4258.8  333.26  4323.2  330.78  4530.1  318.89  4674.9  313.74  4705.9  311.33
    4799  310.65    4830  308.54  4871.4  308.97  4896.3  306.87  4954.1  304.01
  4985.2  305.34  5010.1   302.8    5047     304  5057.6  305.53  5196.7  306.98
  5275.3  306.66  5566.8  310.05  5651.5  309.84  6275.6  316.67  6361.5  316.55
  6480.7  317.86    6702  317.97  6872.2   320.6  6985.5  319.92  7092.1  322.19
    7191  321.16  7304.1     325  7361.3  322.08  7545.9  327.18  7637.9  331.83
#Mann= 6 ,-1 , 0
  4258.8     .17       0  4896.3     .09       0  5196.7     .17       0
  5566.8     .11       0  6361.5     .17       0  6480.7     .11       0
Bank Sta=4896.3,5196.7
XS Rating Curve= 0 ,0
Exp/Cntr=0.3,0.1

Type RM Length L Ch R = 1 ,444     ,0,0,0
BEGIN DESCRIPTION:
WFSJR 071 1.0
END DESCRIPTION:
XS GIS Cut Line= 4
      3730925.63      10260868.6      3730188.96     10261021.16
      3729658.29     10261237.52      3727926.53     10260851.24
#Sta/Elev= 30
  4247.7  332.74  4277.9  331.23  4379.5   325.7  4582.8  316.14  4650.6  313.62
  4887.7  306.49  4930.2  304.96  4975.3  303.49  4988.8  300.66  5109.2  304.64
  5146.2  304.59    5208   304.6  5313.7  306.28  5509.6  309.86  5696.5  311.19
  5798.9  307.51  5870.7  309.02  6075.6  307.03  6137.1  308.94  6167.8  305.21
  6321.5  312.87  6372.7  313.67  6382.9  311.78  6407.5  314.97  6479.1  315.91
  6494.5  314.84  6548.2  320.12  6732.2  326.74  7161.6  332.88  7347.4  337.87
#Mann= 13 ,-1 , 0
  4247.7     .11       0  4277.9     .17       0  4379.5     .11       0
  4582.8     .17       0  4650.6     .11       0  4887.7     .17       0
  4930.2     .09       0  5109.2     .17       0  5146.2     .17       0
    5208     .11       0  5313.7     .17       0  5509.6     .11       0
  6479.1     .17       0
#XS Ineff= 1 ,-1
  5575.9    6400  311.63
Permanent Ineff=
       F
Bank Sta=4930.2,5109.2
XS Rating Curve= 0 ,0
Exp/Cntr=0.3,0.1

Chan Stop Cuts=-1
Use User Specified Reach Order=0
Composite Channel Slope=5