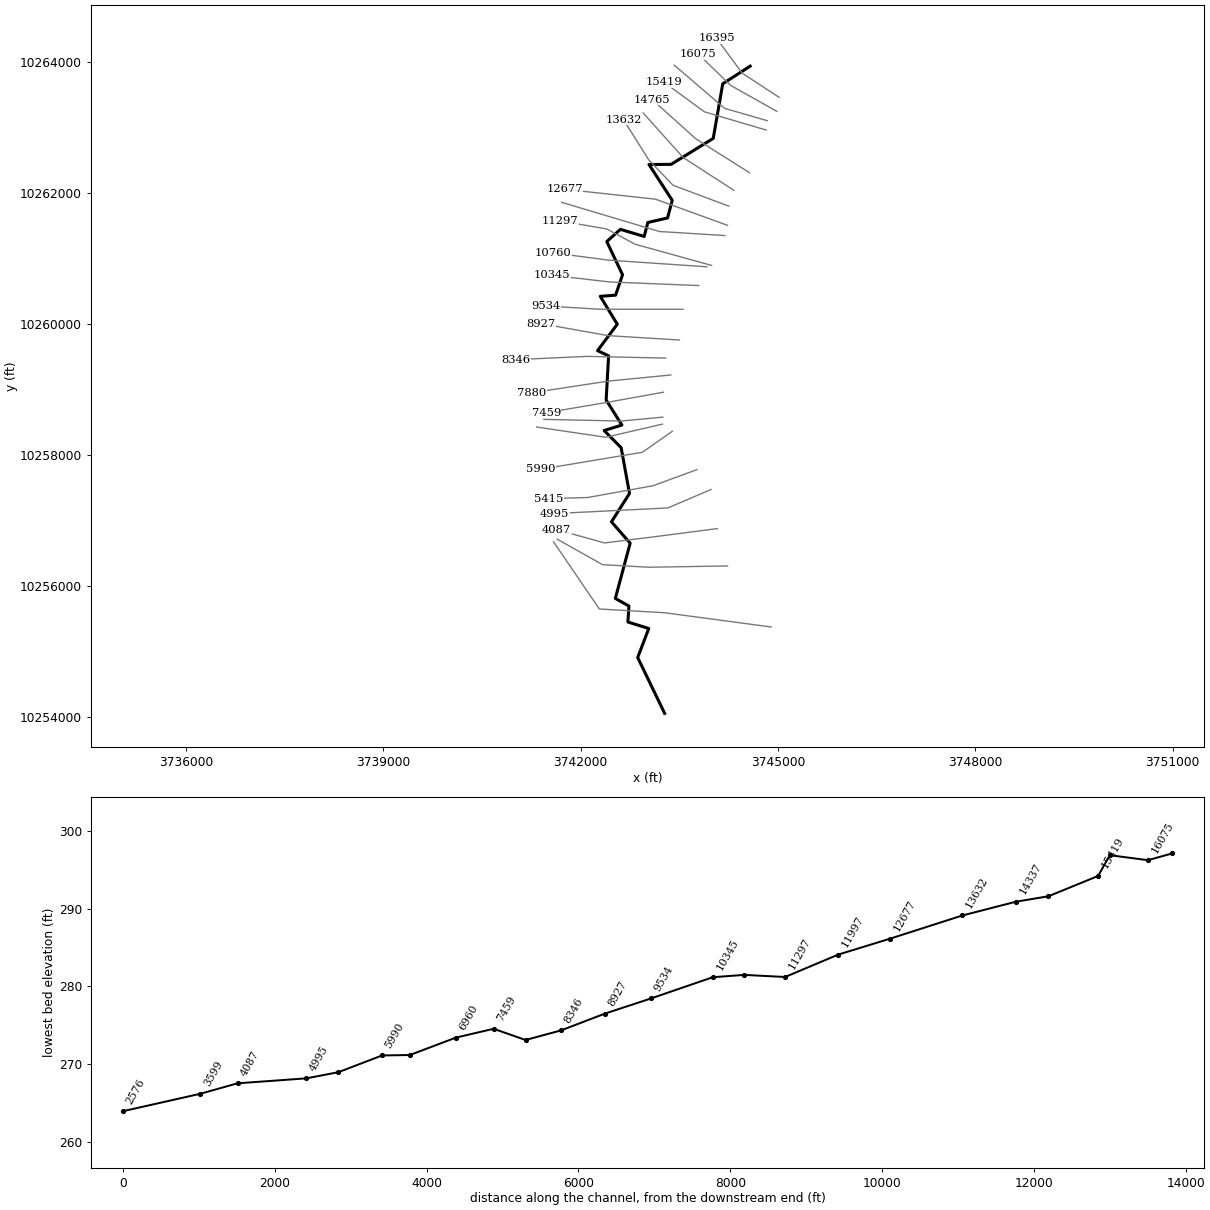
--- WFSJR 075.prj (project) ---

Proj Title=WFSJR 075 Base Level Engineering
Current Plan=p01
Default Exp/Contr=0.3,0.1
English Units
Geom File=g01
Flow File=f01
Plan File=p01
Y Axis Title=Elevation
X Axis Title(PF)=Main Channel Distance
X Axis Title(XS)=Station
BEGIN DESCRIPTION:
WFSJR 075
END DESCRIPTION:
DSS Export Rating Curves= 0
DSS Export Rating Curve Sorted= 0
DSS Export Volume Flow Curves= 0
DXF OffsetX= 0
DXF OffsetY= 0
DXF ScaleX= 1
DXF ScaleY= 10

--- WFSJR 075.p01 (plan) ---

Plan Title=Multiple Run
Program Version=4.10
Short Identifier=Multiple
Geom File=g01
Flow File=f01
Subcritical Flow
K Sum by GR= 0
Std Step Tol= 0.01
Critical Tol= 0.01
Num of Std Step Trials= 20
Max Error Tol= 0.3
Flow Tol Ratio= 0.001
Split Flow NTrial= 30
Split Flow Tol= 0.02
Split Flow Ratio= 0.02
Log Output Level= 0
Friction Slope Method= 1
Unsteady Friction Slope Method= 2
Unsteady Bridges Friction Slope Method= 1
Parabolic Critical Depth
Global Vel Dist= 1 , 1 , 1
Global Log Level= 0
CheckData=True
Encroach Param=-1 ,0,0, 0
BEGIN DESCRIPTION:
Multiple Run
END DESCRIPTION:
Computation Interval=1HOUR
Output Interval=1HOUR
Run HTab= 0
Run UNet= 0
Run PostProcess= 0
Run WQNet= 0
UNET Theta= 1
UNET Theta Warmup= 1
UNET ZTol= 0.02
UNET ZSATol= 0.05
UNET MxIter= 20
UNET MaxInSteps= 0
UNET DtIC= 0
UNET DtMin= 0
UNET MaxCRTS= 20
UNET WFStab= 2
UNET SFStab= 1
UNET WFX= 1
UNET SFX= 1
UNET DSS MLevel= 4
UNET DZMax Abort= 100
UNET Convert EG Bridges= 0
UNET Use Existing IB Tables=-1
UNET Froude Reduction=False
UNET Froude Limit= 1
UNET Froude Power= 10
UNET Time Slicing=0,0, 5
UNET Junction Losses=0
Instantaneous Interval=1HOUR
Write IC File= 0
Write IC File at Sim End=0
Echo Input=False
Echo Parameters=False
Echo Output=False
Write Detailed= 0
WQ AD Non Conservative
WQ ULTIMATE=-1
WQ Max Comp Step=1HOUR
WQ Output Interval=15MIN
WQ Output Selected Increments= 0
WQ Output face flow=0
WQ Output face velocity=0
WQ Output face area=0
WQ Output face dispersion=0
WQ Output cell volume=0
WQ Output cell surface area=0
WQ Output cell continuity=0
WQ Output cumulative cell continuity=0
WQ Output face conc=0
WQ Output face dconc_dx=0
WQ Output face courant=0
WQ Output face peclet=0
WQ Output face adv mass=0
WQ Output face disp mass=0
WQ Output cell mass=0
WQ Output cell source sink temp=0
WQ Output cell source sink nsm=0
WQ Output MaxMinRange=-1
WQ Daily Max Min Mean=-1
WQ Daily Range=0
WQ Daily Time=0
WQ Create Restart=0
WQ Fixed Restart=0
WQ System Summary=0
WQ Use Fixed Temperature=0
Sorting and Armoring Iterations= 10
XS Update Threshold= 0.02
Hydraulics Update Threshold= 0.02
Energy Slope Method= 1
Volume Change Method= 0
XS Weighting Method= 0
Number of US Weighted Cross Sections= 1
Number of DS Weighted Cross Sections= 1
Upstream XS Weight=0.25
Main XS Weight=0.5
Downstream XS Weight=0.25
Number of DS XS's Weighted with US Boundary= 1
Upstream Boundary Weight= 1
Weight of XSs Associated with US Boundary= 0
Number of US XS's Weighted with DS Boundary= 1
Downstream Boundary Weight= 0.5
Weight of XSs Associated with DS Boundary= 0.5
Sediment Output Level= 4
Mass or Volume Output= 0
Output Increment Type= 1
Profile and TS Output Increment= 10
XS Output Flag= 0
XS Output Increment= 10
Disregard all LS=0
Disregard all Conn=0
Disregard all Breaches=0
Disregard all Pumps=0

--- WFSJR 075.f01 (steady flow) ---

Flow Title=Multiple
Program Version=4.10
Number of Profiles= 7
Profile Names=10-year,25-year,50-year,1pct_min,100-year,1pct_plu,500-year
River Rch & RM=WFSJR 075,Reach-1         ,16395
     738     998    1347     597    1802    5442    3342
River Rch & RM=WFSJR 075,Reach-1         ,11297
     901    1234    1680     751    2267    6846    4272
River Rch & RM=WFSJR 075,Reach-1         ,7880
     967    1326    1806     807    2436    7357    4591
River Rch & RM=WFSJR 075,Reach-1         ,4087
    1009    1383    1884     842    2542    7677    4788
Boundary for River Rch & Prof#=WFSJR 075,Reach-1         , 1
Up Type= 0
Dn Type= 3
Dn Slope=0.002
Boundary for River Rch & Prof#=WFSJR 075,Reach-1         , 2
Up Type= 0
Dn Type= 3
Dn Slope=0.002
Boundary for River Rch & Prof#=WFSJR 075,Reach-1         , 3
Up Type= 0
Dn Type= 3
Dn Slope=0.002
Boundary for River Rch & Prof#=WFSJR 075,Reach-1         , 4
Up Type= 0
Dn Type= 3
Dn Slope=0.002
Boundary for River Rch & Prof#=WFSJR 075,Reach-1         , 5
Up Type= 0
Dn Type= 3
Dn Slope=0.002
Boundary for River Rch & Prof#=WFSJR 075,Reach-1         , 6
Up Type= 0
Dn Type= 3
Dn Slope=0.002
Boundary for River Rch & Prof#=WFSJR 075,Reach-1         , 7
Up Type= 0
Dn Type= 3
Dn Slope=0.002
DSS Import GetInterval= 0
DSS Import GetPeak= 0
DSS Import FillOption= 0

--- WFSJR 075.g01 (geometry) ---

Geom Title=Existing Conditions
Program Version=4.10

River Reach=WFSJR 075       ,Reach-1
Reach XY= 30
      3744578.23     10263936.84      3744161.06     10263667.57
      3744016.66     10262834.61      3743376.77     10262438.28
      3743039.79     10262436.13      3743393.73     10261889.17
      3743322.09     10261620.46      3743022.75     10261551.08
      3742966.82     10261338.25      3742605.64     10261446.62
      3742398.52     10261259.79      3742638.07     10260753.88
      3742532.19     10260442.03       3742299.7     10260424.32
      3742558.39     10259999.19       3742258.3     10259595.67
      3742426.16     10259516.26      3742388.88      10258842.1
      3742628.45     10258459.81      3742357.99     10258377.17
      3742616.54     10258115.25      3742744.11     10257417.38
      3742469.66     10256983.66      3742753.77     10256657.39
      3742528.42     10255814.74      3742735.26     10255698.51
      3742719.37     10255455.22      3743036.58     10255356.22
      3742868.44     10254913.02      3743278.13     10254060.94

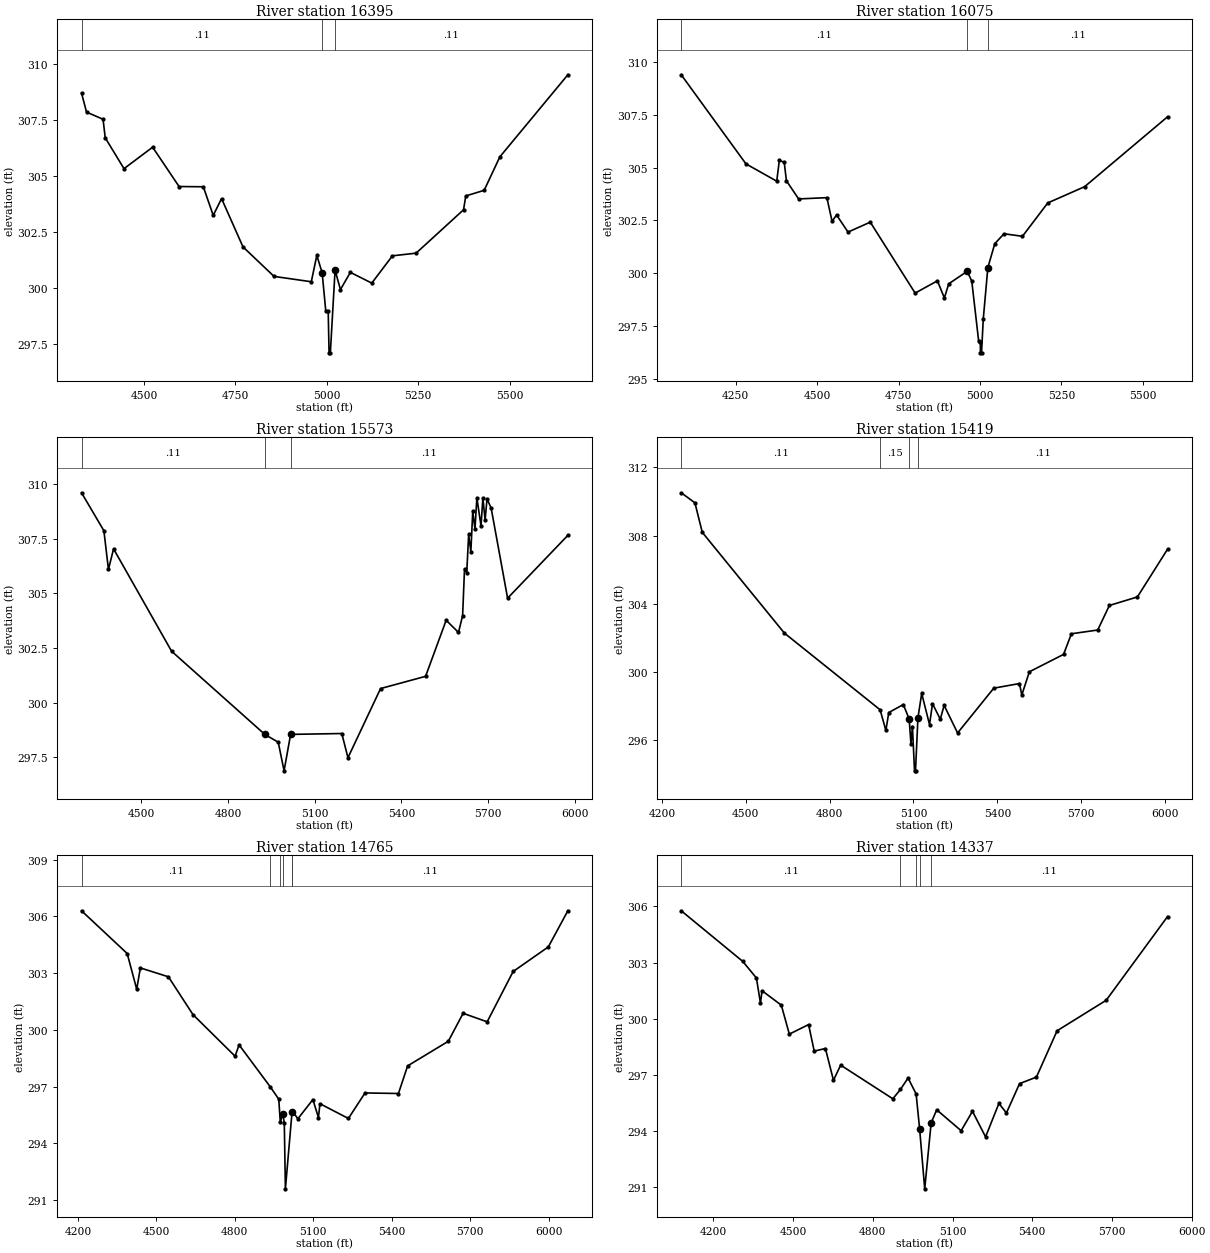
Type RM Length L Ch R = 1 ,16395   ,320,320,320
BEGIN DESCRIPTION:
WFSJR 075 19.0
END DESCRIPTION:
XS GIS Cut Line= 3
      3745017.88     10263461.05      3744457.17     10263829.27
      3744067.84     10264361.09
#Sta/Elev= 30
  4329.2  308.72  4342.8  307.87    4388  307.55    4394  306.72  4445.3  305.34
  4523.6   306.3  4595.9  304.54  4662.2  304.53  4689.3  303.25  4712.1     304
  4770.7  301.84  4855.6  300.52  4957.5  300.28  4972.6  301.46  4987.2  300.68
  4997.1  298.97  5003.7  298.97  5006.1   297.1  5009.6   297.1  5022.5   300.8
  5037.2  299.93  5064.3   300.7  5122.9  300.22  5179.3  301.44  5244.1  301.56
  5373.8   303.5    5380  304.12  5430.2  304.37  5473.2  305.87  5659.1  309.54
#Mann= 3 , 0 , 0
  4329.2     .11       0  4987.2     .06       0  5022.5     .11       0
Bank Sta=4987.2,5022.5
XS Rating Curve= 0 ,0
Exp/Cntr=0.3,0.1

Type RM Length L Ch R = 1 ,16075   ,502,502,502
BEGIN DESCRIPTION:
WFSJR 075 18.0
END DESCRIPTION:
XS GIS Cut Line= 3
      3744983.19     10263246.92       3744281.8     10263642.75
      3743788.75     10264121.91
#Sta/Elev= 30
  4082.9   309.4  4281.6  305.18  4376.1  304.36  4384.1  305.35  4399.1  305.25
  4405.8  304.38  4443.3  303.52    4530  303.58  4545.9  302.46  4559.8  302.76
  4594.9  301.95  4663.2  302.42  4800.9  299.06  4869.4  299.64  4890.7  298.83
  4904.1   299.5  4960.7  300.09  4974.8  299.63  4995.9  296.79  5001.1  296.73
  5001.3  296.23  5004.8  296.23  5010.1  297.83  5024.2  300.27  5045.5   301.4
  5073.8  301.87  5130.4  301.75  5208.1  303.33  5321.3   304.1  5575.8  307.41
#Mann= 3 , 0 , 0
  4082.9     .11       0  4960.7     .06       0  5024.2     .11       0
Bank Sta=4960.7,5024.2
XS Rating Curve= 0 ,0
Exp/Cntr=0.3,0.1

Type RM Length L Ch R = 1 ,15573   ,154,154,154
BEGIN DESCRIPTION:
Mapping XS 04e58269
END DESCRIPTION:
XS GIS Cut Line= 3
      3744837.34     10263104.56      3744191.52     10263292.05
       3743424.2     10263951.75
#Sta/Elev= 30
  4292.4  309.61  4369.8  307.87  4385.6   306.1  4403.3  307.04  4604.3  302.35
  4927.1  298.54  4973.7  298.18  4993.9  296.87  5016.5  298.54  5193.9  298.58
  5215.1  297.47  5328.1  300.64    5484   301.2  5555.3  303.77    5598  303.21
  5612.3  303.98  5618.9  306.13  5626.6  305.95  5633.2   307.7  5640.8   306.9
  5647.4  308.76  5655.1  307.95  5661.7  309.38    5676  308.09  5682.5  309.37
  5690.2  308.36  5696.8  309.33  5711.1  308.91  5768.1  304.78  5976.8  307.66
#Mann= 3 ,-1 , 0
  4292.4     .11       0  4927.1     .06       0  5016.5     .11       0
Bank Sta=4927.1,5016.5
XS Rating Curve= 0 ,0
Exp/Cntr=0.3,0.1

Type RM Length L Ch R = 1 ,15419   ,654,654,654
BEGIN DESCRIPTION:
WFSJR 075 17.0
END DESCRIPTION:
XS GIS Cut Line= 3
      3744820.02     10262962.18       3743882.5     10263239.97
      3743267.88     10263691.39
#Sta/Elev= 30
  4268.8  310.51  4317.8  309.92  4344.1  308.19  4637.9  302.28  4980.6  297.78
  5001.1  296.57  5011.6  297.62  5063.7  298.09  5084.6  297.23  5090.9  295.79
  5096.2   296.8  5103.7   294.2  5107.2   294.2  5115.9  297.31  5129.4  298.74
  5157.4  296.91    5168  298.14  5195.9  297.23  5209.7  298.04  5257.8  296.42
  5387.4  299.05  5479.2  299.32  5487.7  298.65  5514.7  300.01    5637  301.03
  5665.2  302.24  5759.3  302.46    5801   303.9  5901.3   304.4  6009.2   307.2
#Mann= 4 ,-1 , 0
  4268.8     .11       0  4980.6     .15       0  5084.6     .09       0
  5115.9     .11       0
Bank Sta=5084.6,5115.9
XS Rating Curve= 0 ,0
Exp/Cntr=0.3,0.1

Type RM Length L Ch R = 1 ,14765   ,428,428,428
BEGIN DESCRIPTION:
WFSJR 075 16.0
END DESCRIPTION:
XS GIS Cut Line= 3
      3744567.85     10262311.07      3743754.02     10262826.78
      3743088.13     10263426.77
#Sta/Elev= 30
    4214  306.29  4388.6  304.03    4425  302.14  4438.9  303.27  4546.2   302.8
  4640.2   300.8  4801.3   298.6  4816.5   299.2  4935.9  296.98  4968.2  296.33
  4974.1  295.11  4983.5  295.57  4989.4  295.07  4993.6  291.59    5019  295.65
  5020.7  295.71  5041.1  295.29  5098.7  296.31  5119.9  295.36  5125.8  296.09
  5234.5  295.31  5298.1  296.66  5425.9  296.63    5461  298.09  5616.5  299.39
  5673.2  300.87  5765.2  300.42  5864.6  303.08  5999.1  304.38  6073.8  306.29
#Mann= 7 ,-1 , 0
    4214     .11       0  4935.9     .15       0  4974.1     .12       0
  4983.5     .09       0    5019     .12       0  5020.7     .15       0
  5020.7     .11       0
Bank Sta=4983.5,5019
XS Rating Curve= 0 ,0
Exp/Cntr=0.3,0.1

Type RM Length L Ch R = 1 ,14337   ,705,705,705
BEGIN DESCRIPTION:
WFSJR 075 15.0
END DESCRIPTION:
XS GIS Cut Line= 3
      3744330.45     10262042.03      3743557.81     10262543.84
      3742952.36     10263222.14
#Sta/Elev= 30
  4078.7  305.77  4310.4  303.06  4361.8  302.17  4376.9  300.83  4382.9  301.49
  4455.4  300.72  4485.6  299.17  4558.1  299.68  4579.2  298.26  4621.4   298.4
  4651.7   296.7  4678.8  297.51  4875.2  295.71  4903.8  296.21  4932.5  296.82
  4962.8  295.97  4976.1  294.09  4995.2  290.89  5019.4  294.42  5040.3  295.12
  5132.3     294  5174.9  295.04  5224.3  293.67  5274.4  295.46  5302.8  294.95
  5352.2  296.52  5415.7  296.87  5493.5  299.35  5678.2  300.98  5909.2  305.46
#Mann= 5 ,-1 , 0
  4078.7     .11       0  4903.8     .17       0  4962.8     .11       0
  4976.1     .06       0  5019.4     .11       0
#XS Ineff= 1 ,-1
    4720  4932.5  296.82
Permanent Ineff=
       F
Bank Sta=4976.1,5019.4
XS Rating Curve= 0 ,0
Exp/Cntr=0.3,0.1

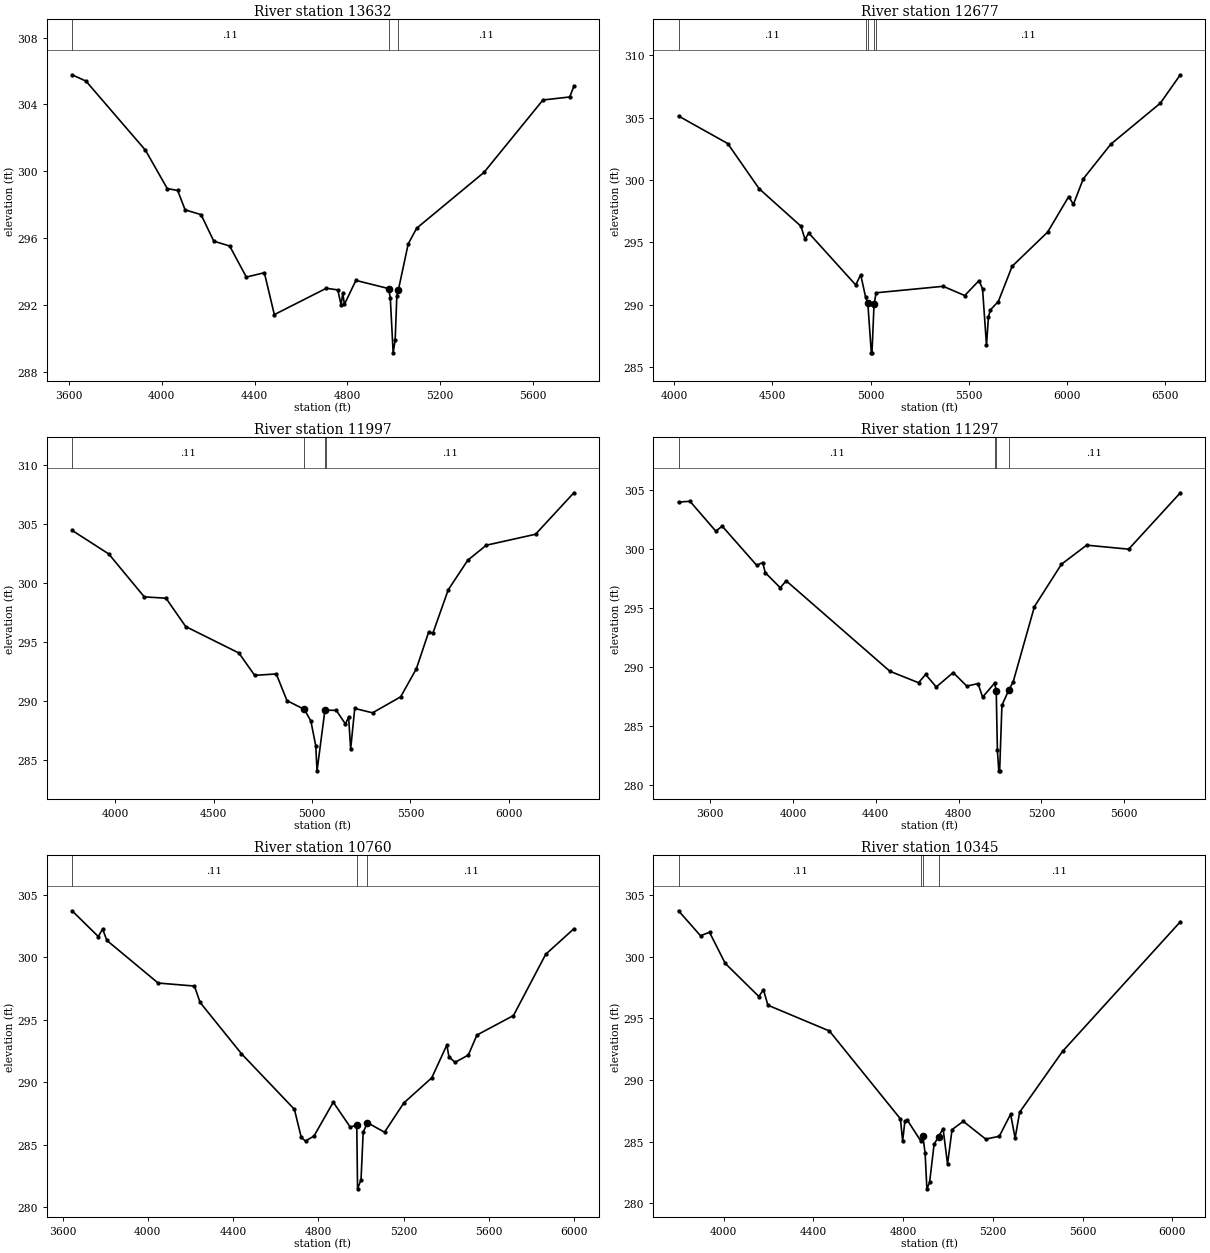
Type RM Length L Ch R = 1 ,13632   ,955,955,955
BEGIN DESCRIPTION:
WFSJR 075 14.0
END DESCRIPTION:
XS GIS Cut Line= 4
      3744254.05     10261799.86      3743405.07     10262120.18
      3743035.27      10262508.2      3742652.66     10263119.87
#Sta/Elev= 30
  3612.8  305.78  3672.9   305.4  3929.4  301.26  4023.6  298.96  4068.3  298.85
  4100.4  297.69  4169.3   297.4  4224.3  295.81  4292.8  295.52  4364.6  293.66
  4442.4  293.92  4485.4  291.41  4709.9  292.99  4759.3  292.89  4773.4  291.99
  4780.7  292.71  4787.6  292.02  4837.3  293.46  4978.5  292.97  4985.7  292.42
  4998.1  289.12  5006.8  289.89    5014  292.55  5020.9  292.91  5063.1  295.65
  5099.7  296.59  5389.9  299.93  5644.4  304.27  5759.9  304.45  5777.7  305.09
#Mann= 3 , 0 , 0
  3612.8     .11       0  4978.5     .06       0  5020.9     .11       0
Bank Sta=4978.5,5020.9
XS Rating Curve= 0 ,0
Exp/Cntr=0.3,0.1

Type RM Length L Ch R = 1 ,12677   ,680,680,680
BEGIN DESCRIPTION:
WFSJR 075 13.0
END DESCRIPTION:
XS GIS Cut Line= 3
      3744233.22     10261508.19      3743139.44     10261906.64
      3741756.66     10262057.68
#Sta/Elev= 30
  4022.3  305.14  4272.8  302.93  4432.4  299.31  4645.3   296.3  4666.6  295.24
  4685.3  295.75  4924.6  291.58  4949.8   292.4  4975.1  290.59  4985.9  290.16
  5003.9  286.13  5007.4  286.13  5017.8  290.02  5028.4  290.95  5369.7  291.47
  5479.7  290.73  5552.4  291.93  5570.3  291.27  5590.4  286.74  5600.4  289.03
  5610.5  289.58  5650.7  290.25  5721.1  293.08  5902.2  295.83  6008.9  298.67
    6033  298.05  6083.3   300.1  6224.1  302.89  6475.6  306.17  6577.4  308.45
#Mann= 5 ,-1 , 0
  4022.3     .11       0  4975.1     .09       0  4985.9     .06       0
  5017.8     .09       0  5028.4     .11       0
#XS Ineff= 1 ,-1
  5552.4    5720  291.93
Permanent Ineff=
       F
Bank Sta=4985.9,5017.8
XS Rating Curve= 0 ,0
Exp/Cntr=0.3,0.1

Type RM Length L Ch R = 1 ,11997   ,700,700,700
BEGIN DESCRIPTION:
WFSJR 075 12.0
END DESCRIPTION:
XS GIS Cut Line= 3
       3744194.1     10261351.95      3743198.79     10261413.56
      3741711.26     10261859.31
#Sta/Elev= 30
  3780.5  304.44  3967.1  302.44  4147.5  298.81  4257.7   298.7  4357.9   296.3
  4628.4  294.06  4708.5  292.17  4818.3  292.29  4872.7  290.03    4961  289.29
  4994.1   288.3  5018.8  286.22  5025.4  284.09  5065.5  289.22    5071  289.22
  5123.2  289.21  5169.9  288.05  5185.8  288.65  5196.3  285.94  5217.1  289.37
  5307.5     289  5450.2  290.35  5530.3  292.73    5593  295.85  5613.8  295.72
  5692.2  299.41  5791.3  301.91  5885.3  303.18  6135.8  304.11  6330.6  307.62
#Mann= 4 ,-1 , 0
  3780.5     .11       0    4961     .06       0  5065.5     .09       0
    5071     .11       0
Bank Sta=4961,5065.5
XS Rating Curve= 0 ,0
Exp/Cntr=0.3,0.1

Type RM Length L Ch R = 1 ,11297   ,537,537,537
BEGIN DESCRIPTION:
WFSJR 075 11.0
END DESCRIPTION:
XS GIS Cut Line= 4
      3743991.02     10260896.22      3742829.55     10261219.14
      3742394.65     10261453.51      3741682.02     10261575.75
#Sta/Elev= 30
  3447.8  303.99    3503  304.06  3627.5  301.53  3658.7  301.95  3825.3  298.63
  3854.3  298.87  3866.3  298.01  3938.9  296.73  3967.4  297.32  4468.3  289.65
  4606.5  288.68  4640.7  289.38    4692  288.32  4773.9  289.54  4839.6  288.39
  4893.8  288.61  4915.9  287.46  4973.3  288.64  4981.6  288.02  4987.2  282.94
    4994  281.21  4998.1  281.21  5009.1  286.76  5041.5  288.03  5063.5  288.76
    5166  295.13  5296.3  298.72  5418.1  300.34    5621     300  5870.4  304.78
#Mann= 4 ,-1 , 0
  3447.8     .11       0  4973.3     .09       0  4981.6     .06       0
  5041.5     .11       0
Bank Sta=4981.6,5041.5
XS Rating Curve= 0 ,0
Exp/Cntr=0.3,0.1

Type RM Length L Ch R = 1 ,10760   ,415,415,415
BEGIN DESCRIPTION:
WFSJR 075 10.0
END DESCRIPTION:
XS GIS Cut Line= 3
       3743920.7     10260875.39      3742420.69     10260976.95
      3741576.93     10261088.93
#Sta/Elev= 30
  3644.6  303.72  3767.7  301.66  3787.8  302.26  3807.8  301.35  4048.4  297.94
  4218.8   297.7  4245.3  296.39  4439.3  292.29  4687.9  287.84  4719.9   285.6
    4740   285.3    4780  285.71  4870.2  288.41  4950.4  286.41  4980.5   286.6
  4984.2  281.48  5000.5  282.21  5010.6  286.01  5030.6  286.77  5110.8  286.01
  5201.3  288.35  5332.5  290.36  5403.1  292.98  5413.2  292.03  5441.9   291.6
    5504  292.18  5544.3  293.78  5715.8  295.34  5867.1  300.24  5999.2  302.28
#Mann= 3 , 0 , 0
  3644.6     .11       0  4980.5     .06       0  5030.6     .11       0
#XS Ineff= 1 ,-1
    4580  4870.2  288.41
Permanent Ineff=
       F
Bank Sta=4980.5,5030.6
XS Rating Curve= 0 ,0
Exp/Cntr=0.3,0.1

Type RM Length L Ch R = 1 ,10345   ,811,811,811
BEGIN DESCRIPTION:
WFSJR 075 9.0
END DESCRIPTION:
XS GIS Cut Line= 3
      3743795.71     10260588.93      3742444.13     10260643.62
      3741566.57     10260745.17
#Sta/Elev= 30
  3798.8  303.71  3896.7  301.69  3936.8  301.97  4006.8  299.45  4156.9  296.76
    4177  297.32    4197  296.06  4471.2  293.97  4787.5  286.85  4797.5  285.06
  4807.5  286.65  4817.5  286.77  4877.5  285.08  4887.5  285.47  4897.6  284.07
  4905.5  281.18  4917.6   281.7  4937.6  284.79  4957.6  285.41  4977.6  286.06
  4997.6  283.18  5017.7  285.98  5067.7  286.65  5167.8  285.21  5228.3  285.44
  5278.6  287.23  5298.7  285.29  5318.9  287.39  5510.1  292.32  6034.9  302.82
#Mann= 4 ,-1 , 0
  3798.8     .11       0  4877.5     .09       0  4887.5     .06       0
  4957.6     .11       0
Bank Sta=4887.5,4957.6
XS Rating Curve= 0 ,0
Exp/Cntr=0.3,0.1

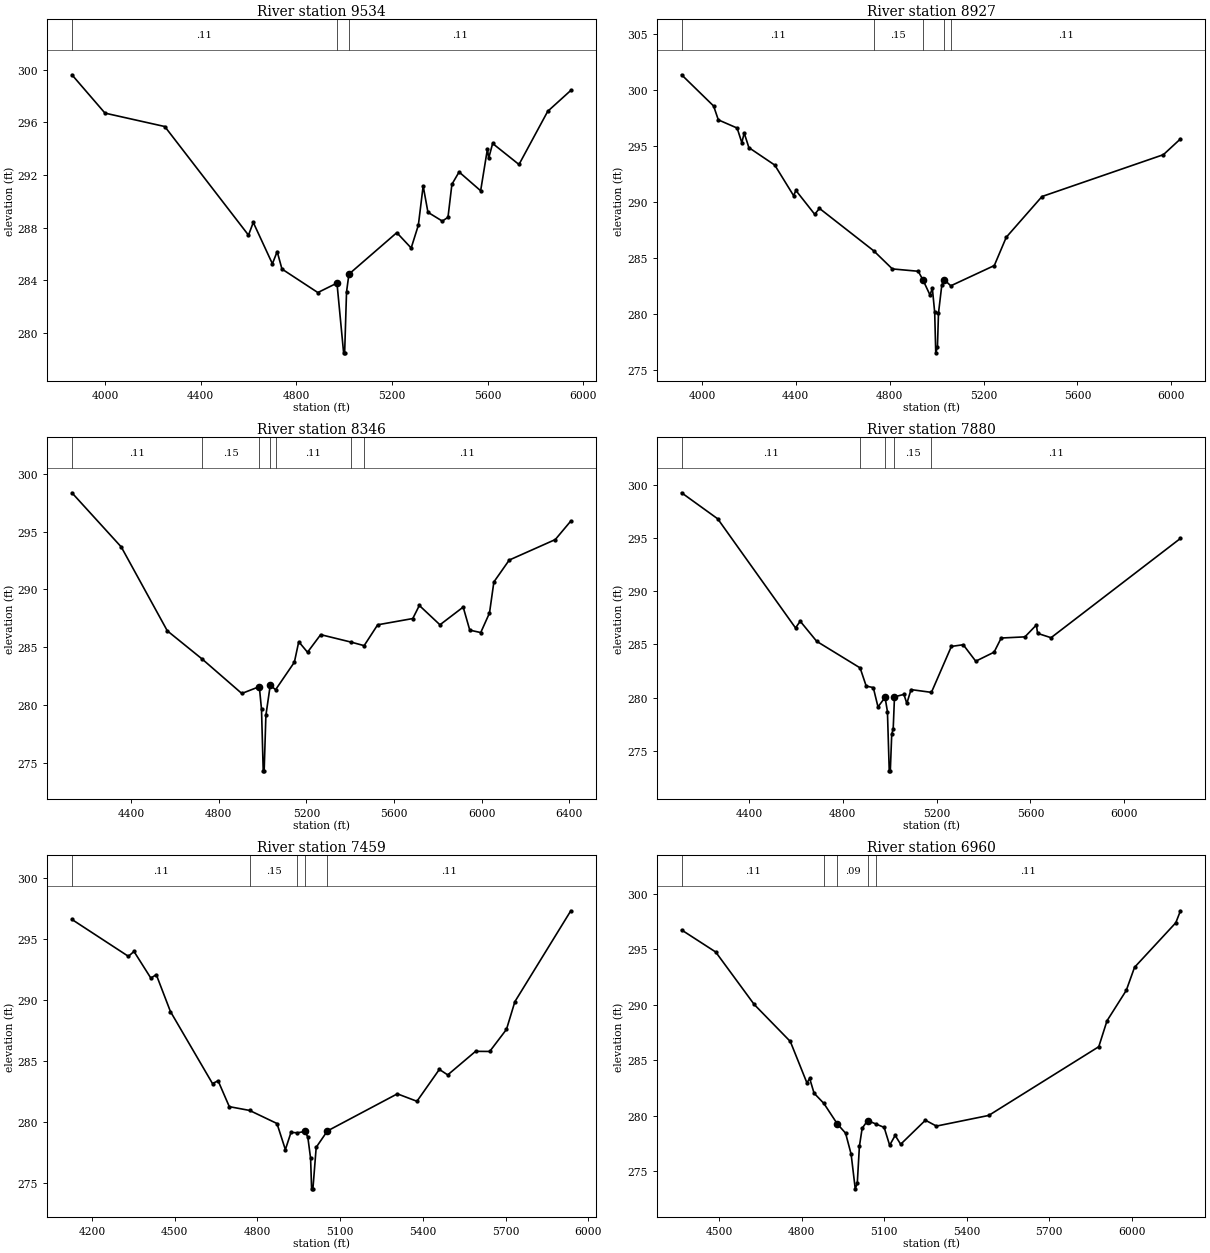
Type RM Length L Ch R = 1 ,9534    ,607,607,607
BEGIN DESCRIPTION:
WFSJR 075 8.0
END DESCRIPTION:
XS GIS Cut Line= 3
      3743556.15     10260227.51       3742300.9     10260227.51
      3741471.49     10260276.35
#Sta/Elev= 30
    3862  299.63  4000.3  296.71  4250.3  295.69  4600.3  287.42  4620.3  288.39
  4700.3  285.24  4720.3  286.17  4740.3  284.84  4890.3  283.05  4970.3  283.77
  4998.1  278.46  5002.4  278.46  5010.3   283.1  5020.3  284.45  5220.5  287.61
  5280.6  286.44  5310.6  288.18  5330.7  291.17  5350.7  289.16  5410.8  288.49
  5434.5  288.78  5450.9  291.29  5480.9  292.23  5571.1   290.8  5599.6     294
  5604.6  293.27  5621.2   294.4  5731.4   292.8  5851.6  296.85  5948.1  298.44
#Mann= 3 , 0 , 0
    3862     .11       0  4970.3     .06       0  5020.3     .11       0
Bank Sta=4970.3,5020.3
XS Rating Curve= 0 ,0
Exp/Cntr=0.3,0.1

Type RM Length L Ch R = 1 ,8927    ,581,581,581
BEGIN DESCRIPTION:
WFSJR 075 7.0
END DESCRIPTION:
XS GIS Cut Line= 3
      3743504.03      10259758.2      3742419.55     10259824.48
      3741397.23      10260008.2
#Sta/Elev= 30
  3913.5  301.36  4049.9  298.57    4070  297.33  4150.1   296.6  4170.2  295.29
  4180.2  296.16  4200.2  294.85  4310.4  293.29  4390.6  290.56  4400.6  291.02
  4480.7  288.89  4500.8  289.42  4731.9  285.63  4811.3  284.01  4921.6   283.8
  4941.6  283.03  4971.6  281.68  4981.7  282.28  4991.7  280.13  4996.2  276.51
  5003.4  277.01  5007.9  280.06    5022  282.56  5032.2  283.05  5060.3   282.5
  5245.6  284.31  5296.6  286.84  5448.8  290.48    5966  294.22  6038.7  295.63
#Mann= 5 ,-1 , 0
  3913.5     .11       0  4731.9     .15       0  4941.6     .09       0
  5032.2     .15       0  5060.3     .11       0
Bank Sta=4941.6,5032.2
XS Rating Curve= 0 ,0
Exp/Cntr=0.3,0.1

Type RM Length L Ch R = 1 ,8346    ,466,466,466
BEGIN DESCRIPTION:
WFSJR 075 6.0
END DESCRIPTION:
XS GIS Cut Line= 3
      3743293.13     10259482.16      3742102.37     10259508.39
      3741017.06     10259458.72
#Sta/Elev= 30
  4129.7  298.35    4355  293.67  4565.1  286.43  4723.8     284  4905.2  281.02
  4985.2  281.61  4995.2  279.65    5003  274.34  5007.3  274.34  5015.2  279.13
  5035.2  281.75  5059.3  281.34  5145.2  283.72  5165.2  285.49  5205.2  284.58
  5265.3   286.1  5405.2  285.45  5463.7  285.15  5525.5  286.95  5685.7  287.49
  5715.7  288.62  5809.8  286.95  5915.9  288.48  5945.9  286.49    5996  286.28
    6036  287.97    6056  290.65  6126.1  292.54  6336.3  294.31  6407.2  295.91
#Mann= 7 ,-1 , 0
  4129.7     .11       0  4723.8     .15       0  4985.2     .09       0
  5035.2     .15       0  5059.3     .11       0  5405.2     .17       0
  5463.7     .11       0
Bank Sta=4985.2,5035.2
XS Rating Curve= 0 ,0
Exp/Cntr=0.3,0.1

Type RM Length L Ch R = 1 ,7880    ,421,421,421
BEGIN DESCRIPTION:
WFSJR 075 5.0
END DESCRIPTION:
XS GIS Cut Line= 3
      3743371.19     10259224.34      3742418.09      10259130.6
      3741262.36     10258953.59
#Sta/Elev= 30
  4112.6  299.26  4266.7  296.81  4598.3  286.55  4618.4  287.18  4688.7  285.29
  4873.7  282.79  4899.7  281.08  4929.9  280.94    4950  279.12  4980.1  280.02
  4990.2  278.68  4997.9  273.11  5002.5  273.11 5008.52  276.56  5014.8  277.07
  5020.3  280.07  5060.5   280.3  5072.9  279.45  5090.8  280.75  5177.8  280.49
  5262.8  284.81  5313.3  284.97  5366.7  283.42  5444.9  284.27  5475.2   285.6
  5576.4  285.71  5625.3  286.83  5630.3  286.04  5687.7  285.63  6239.5  294.97
#Mann= 5 ,-1 , 0
  4112.6     .11       0  4873.7     .15       0  4980.1     .09       0
  5020.3     .15       0  5177.8     .11       0
Bank Sta=4980.1,5020.3
XS Rating Curve= 0 ,0
Exp/Cntr=0.3,0.1

Type RM Length L Ch R = 1 ,7459    ,499,499,499
BEGIN DESCRIPTION:
WFSJR 075 4.0
END DESCRIPTION:
XS GIS Cut Line= 3
      3743259.28     10258961.33      3742401.01     10258806.06
        3741478.     10258648.83
#Sta/Elev= 30
  4127.8  296.61  4332.5  293.59  4352.8  293.99  4413.8  291.81  4433.6  292.09
  4484.9  289.07  4637.4  283.17  4657.7   283.4  4698.3  281.28  4771.9  280.97
  4871.1   279.9  4901.6  277.76  4921.9  279.17  4945.5  279.14  4972.7  279.25
  4982.9  278.79    4993  277.05  4996.7  274.55  5001.4  274.55  5013.3  277.95
  5053.9  279.29  5307.5  282.33  5378.5  281.72  5459.7  284.33  5490.1  283.88
    5591  285.81  5642.3   285.8  5703.1  287.61  5733.6  289.88  5936.3  297.32
#Mann= 5 ,-1 , 0
  4127.8     .11       0  4771.9     .15       0  4945.5     .11       0
  4972.7     .06       0  5053.9     .11       0
Bank Sta=4972.7,5053.9
XS Rating Curve= 0 ,0
Exp/Cntr=0.3,0.1

Type RM Length L Ch R = 1 ,6960    ,603,603,603
BEGIN DESCRIPTION:
WFSJR 075 3.0
END DESCRIPTION:
XS GIS Cut Line= 3
      3743251.43     10258581.12      3742618.21     10258521.74
      3741440.88     10258547.22
#Sta/Elev= 30
    4364  296.76  4488.1  294.77    4628  290.04  4759.3   286.7  4819.6  282.97
  4829.6  283.37  4845.6  282.04  4881.4  281.11    4930  279.27  4960.2  278.43
  4980.3  276.54  4995.3  273.41  5002.7  273.91  5010.4  277.24  5020.4  278.87
  5040.4  279.57  5070.4  279.26  5100.4  278.95  5120.4  277.34  5140.4  278.23
  5160.4  277.43  5250.4   279.6  5290.4  279.07  5480.5  280.03  5880.6  286.23
  5910.6  288.57  5980.6  291.31  6010.6  293.39  6160.6  297.41  6177.6  298.49
#Mann= 5 ,-1 , 0
    4364     .11       0  4881.4     .15       0    4930     .09       0
  5040.4     .15       0  5070.4     .11       0
Bank Sta=4930,5040.4
XS Rating Curve= 0 ,0
Exp/Cntr=0.3,0.1

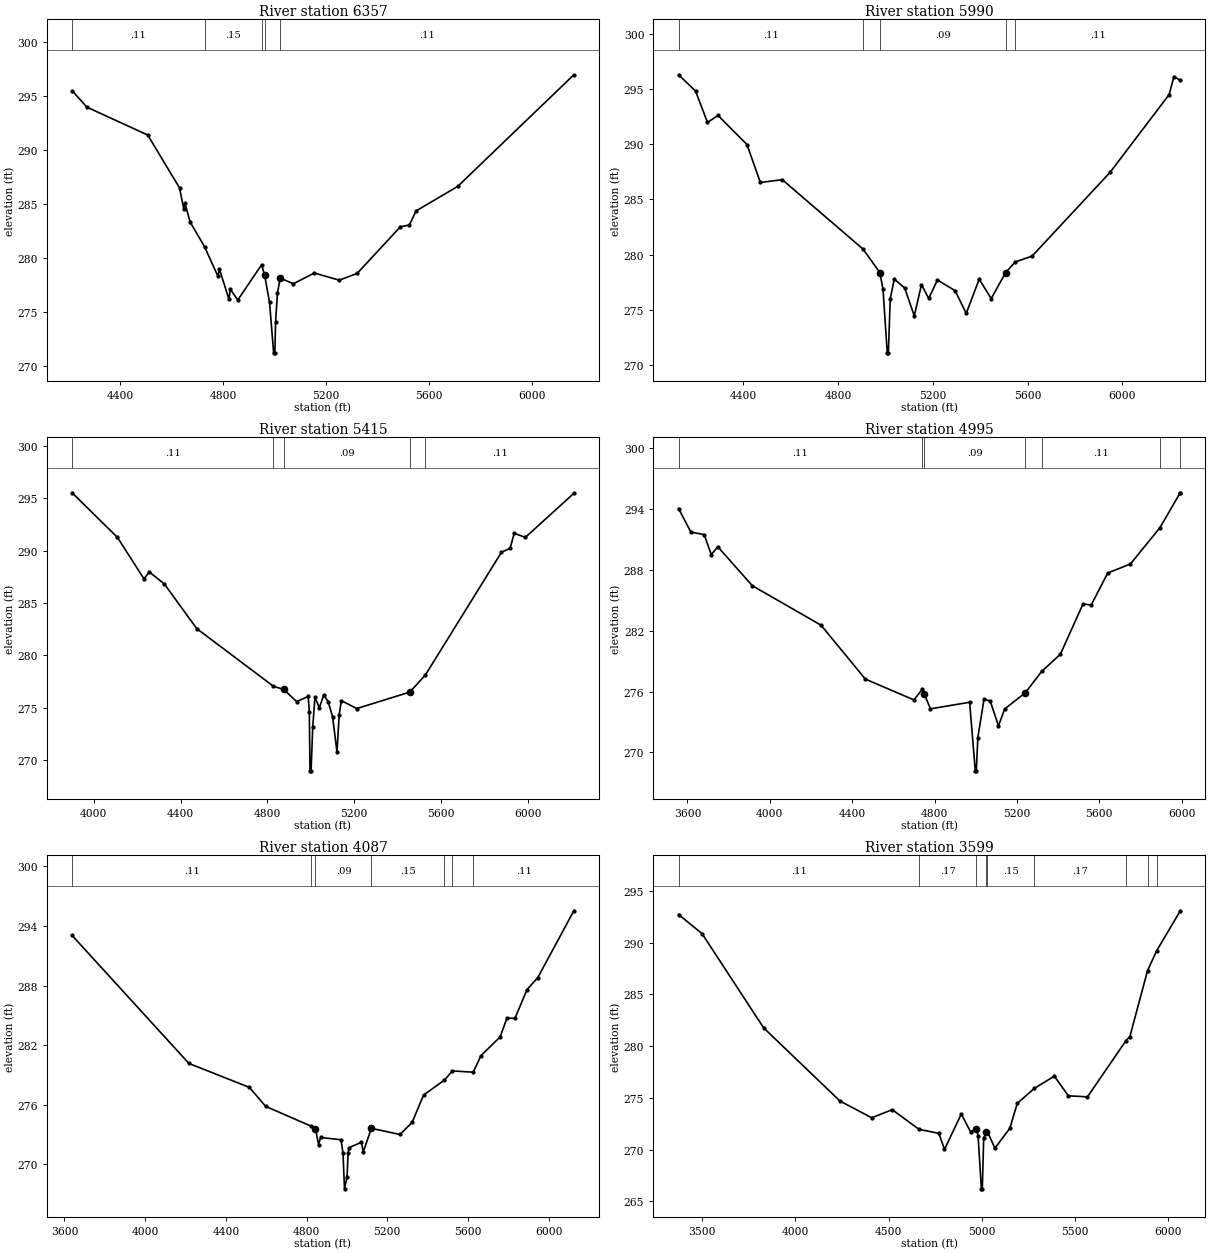
Type RM Length L Ch R = 1 ,6357    ,367,367,367
BEGIN DESCRIPTION:
WFSJR 075 2.0
END DESCRIPTION:
XS GIS Cut Line= 3
      3743243.62     10258474.35      3742381.63     10258273.83
       3741332.5     10258430.02
#Sta/Elev= 30
  4214.8   295.5  4272.1  293.97  4508.2  291.38  4631.4  286.48  4647.7  284.56
  4652.8  285.04  4672.5  283.32  4728.8  281.01  4780.6  278.27  4785.7  278.98
  4823.2  276.15  4828.3  277.08  4857.3  276.08  4949.7  279.35  4961.3   278.4
  4980.5  275.86  4996.4  271.18  5001.1  271.18  5003.9  274.05  5011.3  276.72
  5021.5  278.11  5072.9  277.59  5154.2  278.58  5250.6  277.92  5319.9  278.54
  5487.8  282.87  5522.9  283.04  5548.5  284.34  5710.2  286.62  6160.5  296.97
#Mann= 5 ,-1 , 0
  4214.8     .11       0  4728.8     .15       0  4949.7     .11       0
  4961.3     .06       0  5021.5     .11       0
Bank Sta=4961.3,5021.5
XS Rating Curve= 0 ,0
Exp/Cntr=0.3,0.1

Type RM Length L Ch R = 1 ,5990    ,575,575,575
BEGIN DESCRIPTION:
Mapping XS f63fc1c2
END DESCRIPTION:
XS GIS Cut Line= 3
      3743394.62     10258364.95      3742938.92     10258044.66
      3741401.34     10257787.09
#Sta/Elev= 30
    4128  296.27  4199.6   294.8  4250.1  291.96  4294.5  292.59  4416.5  289.96
  4473.1  286.53  4565.5  286.78  4906.3   280.5  4977.1  278.37  4990.3  276.87
  5008.1  271.12  5012.9  271.12  5020.7  276.02  5037.8  277.78  5081.5  276.99
  5122.1  274.46  5152.5  277.29  5182.9  276.04  5219.8  277.71  5294.4  276.74
  5341.2  274.69  5395.8  277.78  5446.5  276.03  5507.4  278.38  5547.9  279.34
  5618.9  279.87    5948  287.45  6196.8  294.48  6217.1  296.11    6244  295.77
#Mann= 5 ,-1 , 0
    4128     .11       0  4906.3     .15       0  4977.1     .09       0
  5507.4     .15       0  5547.9     .11       0
Bank Sta=4977.1,5507.4
XS Rating Curve= 0 ,0
Exp/Cntr=0.3,0.1

Type RM Length L Ch R = 1 ,5415    ,420,420,420
BEGIN DESCRIPTION:
Mapping XS efb74d3c
END DESCRIPTION:
XS GIS Cut Line= 4
      3743767.01     10257779.02      3743100.38     10257534.24
      3742108.19     10257354.55      3741514.48     10257338.93
#Sta/Elev= 30
  3900.1  295.53  4109.3  291.27  4231.3  287.31  4256.4  287.96  4325.3  286.82
  4474.5  282.56  4827.9  277.05  4876.3  276.74  4934.8  275.58  4988.3  276.08
  4993.4  274.58  4996.6  268.97  5001.5  268.97  5009.2  273.18  5019.3     276
  5039.7     275    5060  276.21  5080.3  275.57  5100.3  274.16    5121  270.76
  5131.1  274.35  5141.3  275.67  5212.3  274.92  5456.3  276.49  5527.5   278.1
    5879  289.85    5919  290.23  5937.5  291.66    5989  291.27  6212.5  295.48
#Mann= 5 ,-1 , 0
  3900.1     .11       0  4827.9     .15       0  4876.3     .09       0
  5456.3     .15       0  5527.5     .11       0
Bank Sta=4876.3,5456.3
XS Rating Curve= 0 ,0
Exp/Cntr=0.3,0.1

Type RM Length L Ch R = 1 ,4995    ,908,908,908
BEGIN DESCRIPTION:
Mapping XS f78c1519
END DESCRIPTION:
XS GIS Cut Line= 3
      3743983.15     10257476.93      3743326.94      10257195.7
      3741605.62     10257109.76
#Sta/Elev= 30
  3556.5  294.04  3616.7  291.71  3681.1  291.47  3715.5   289.5  3747.2  290.27
    3915  286.43  4248.6  282.54  4464.2  277.22  4700.1  275.17  4739.4   276.2
  4750.1  275.76  4780.2  274.29  4970.4  274.94    4998  268.18  5002.9  268.18
  5010.4  271.46  5040.5  275.27  5070.5  275.05  5110.6  272.62  5140.6  274.28
  5240.7  275.87  5320.8  277.99  5410.9  279.66  5521.1  284.63  5561.1  284.53
  5641.2  287.68  5751.4  288.57  5894.6  292.14  5993.2  295.59  5993.9  295.59
#Mann= 7 ,-1 , 0
  3556.5     .11       0  4739.4     .15       0  4750.1     .09       0
  5240.7     .15       0  5320.8     .11       0  5894.6     .17       0
  5993.2     .11       0
Bank Sta=4750.1,5240.7
XS Rating Curve= 0 ,0
Exp/Cntr=0.3,0.1

Type RM Length L Ch R = 1 ,4087    ,488,488,488
BEGIN DESCRIPTION:
Mapping XS 2b0f1f1f
END DESCRIPTION:
XS GIS Cut Line= 4
      3744079.52     10256880.59      3743079.55     10256750.39
        3742366.     10256661.85      3741634.21     10256864.98
#Sta/Elev= 30
  3637.9  293.05  4217.2  280.16  4516.9  277.75  4597.4  275.84  4823.7  273.84
  4844.2  273.59  4859.6     272  4869.7  272.71  4970.5  272.48  4980.6  271.15
  4988.1  267.54  5000.7  268.75    5006  271.16    5011  271.69  5071.2  272.22
  5081.3  271.29  5121.6  273.63  5262.7  273.01  5323.2  274.22  5380.1  276.98
  5483.6  278.49  5522.7  279.41  5626.3  279.28  5664.4  280.95    5759  282.82
  5793.3  284.73  5832.7   284.7  5892.7   287.6  5945.9   288.8  6124.8  295.53
#Mann= 7 ,-1 , 0
  3637.9     .11       0  4823.7     .15       0  4844.2     .09       0
  5121.6     .15       0  5483.6     .11       0  5522.7     .17       0
  5626.3     .11       0
Bank Sta=4844.2,5121.6
XS Rating Curve= 0 ,0
Exp/Cntr=0.3,0.1

Type RM Length L Ch R = 1 ,3599    ,1023,1023,1023
BEGIN DESCRIPTION:
Mapping XS cecf9c46
END DESCRIPTION:
XS GIS Cut Line= 4
      3744234.16     10256310.33      3743040.54      10256290.8
      3742335.25     10256329.86      3741645.13     10256718.32
#Sta/Elev= 30
  3373.2  292.71  3499.5  290.86  3829.6  281.76  4239.6  274.68  4409.7  273.07
  4519.7  273.85  4663.5  271.95    4770  271.56    4800  270.01  4890.2  273.43
  4940.2   271.7  4970.3  271.99  4980.3  271.33  4997.8   266.2  5002.9   266.2
  5010.4  271.11  5024.7  271.71  5030.4  271.73  5070.4  270.13  5150.6  272.05
  5190.6  274.46  5282.4  275.91  5389.4  277.09  5464.6  275.19  5567.2  275.09
  5774.1  280.53  5794.1  280.88  5889.3  287.28  5937.8  289.19  6065.3  293.07
#Mann= 9 ,-1 , 0
  3373.2     .11       0  4663.5     .17       0  4970.3     .09       0
  5024.7     .12       0  5030.4     .15       0  5282.4     .17       0
  5774.1     .11       0  5889.3     .17       0  5937.8     .11       0
#XS Ineff= 1 ,-1
    4310  4519.7  273.85
Permanent Ineff=
       F
Bank Sta=4970.3,5024.7
XS Rating Curve= 0 ,0
Exp/Cntr=0.3,0.1

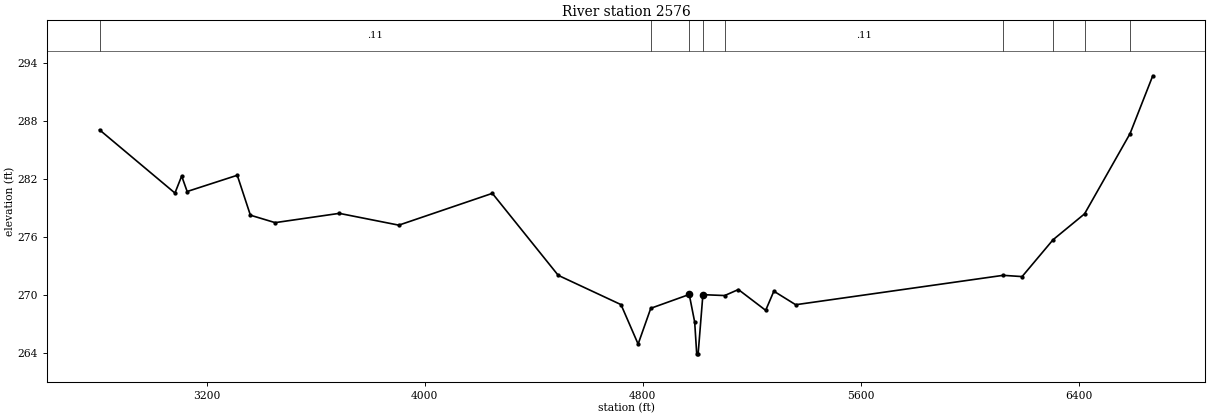
Type RM Length L Ch R = 1 ,2576    ,0,0,0
BEGIN DESCRIPTION:
WFSJR 075 1.0
END DESCRIPTION:
XS GIS Cut Line= 4
      3744896.63     10255379.12       3743280.5     10255596.31
      3742285.71      10255653.6      3741589.82     10256677.63
#Sta/Elev= 30
  2806.5  287.12  3083.3  280.58    3108  282.34  3128.1  280.74    3312  282.42
  3360.2  278.29    3451  277.52  3686.4  278.48  3904.9  277.26  4248.1  280.55
  4489.9  272.07  4720.3  269.04  4783.1  264.96  4829.5  268.66  4970.7  270.09
  4990.7  267.23  4998.1  263.95  5003.3  263.95  5020.8  270.07  5100.9  269.98
    5151   270.6  5251.2  268.45  5281.2  270.43  5361.3  269.03  6122.6  272.07
  6192.2  271.94  6305.8  275.75  6421.5  278.43  6588.4  286.73  6671.7  292.71
#Mann= 9 ,-1 , 0
  2806.5     .11       0  4829.5     .15       0  4970.7     .09       0
  5020.8     .15       0  5100.9     .11       0  6122.6     .17       0
  6305.8     .15       0  6421.5     .17       0  6588.4     .11       0
Bank Sta=4970.7,5020.8
XS Rating Curve= 0 ,0
Exp/Cntr=0.3,0.1

Chan Stop Cuts=-1
Use User Specified Reach Order=0
Composite Channel Slope=5