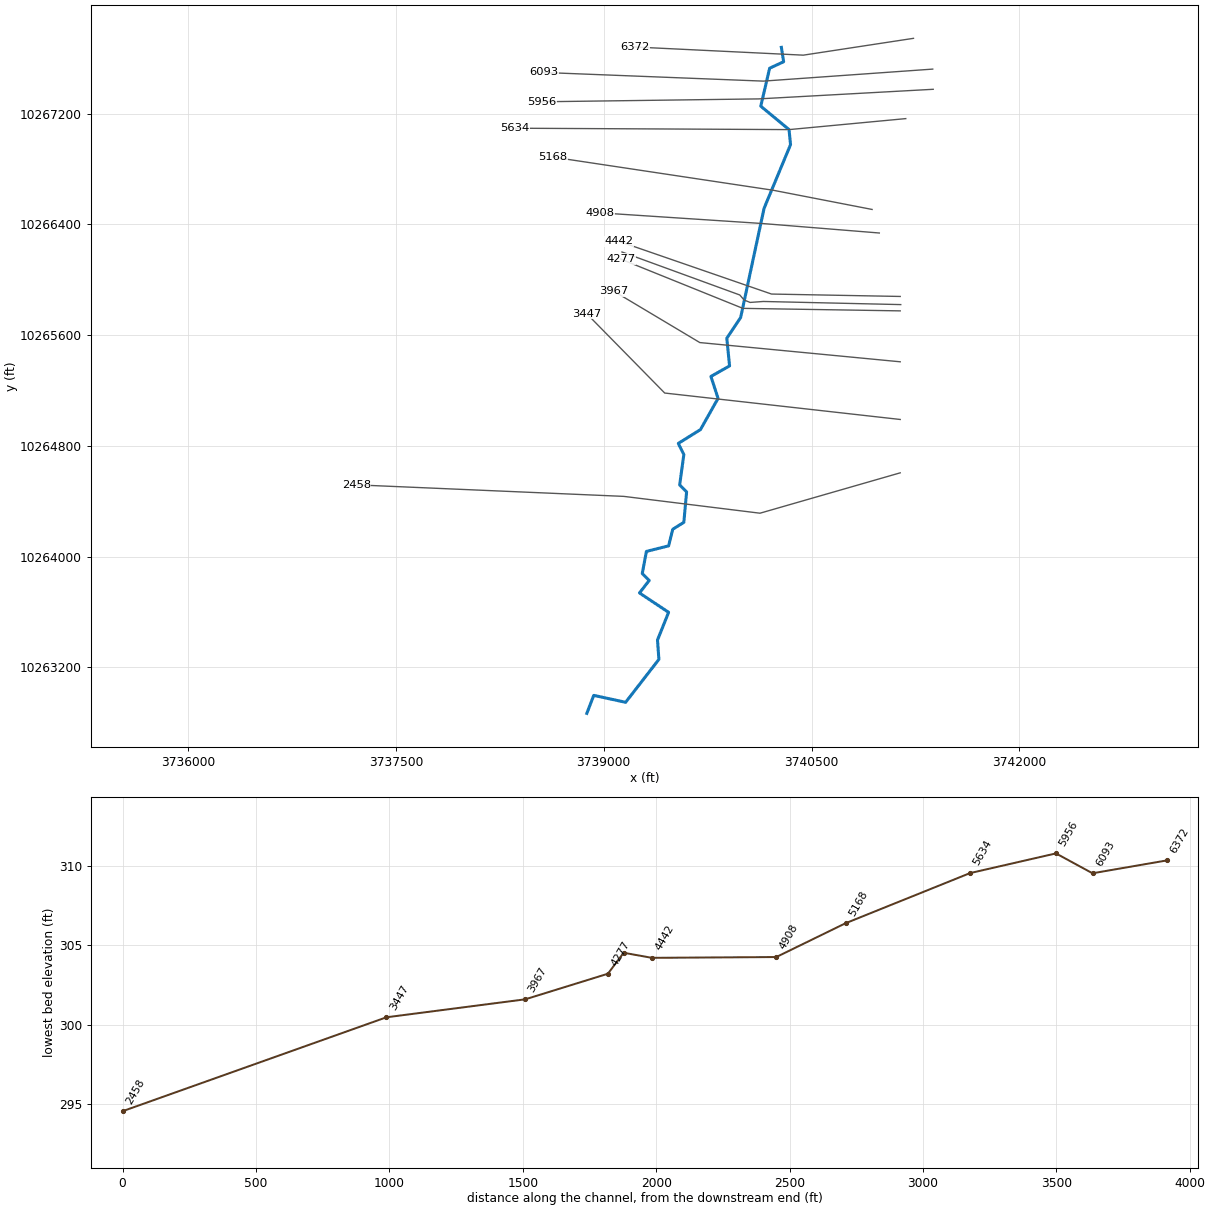
--- WFSJR 076.prj (project) ---

Proj Title=WFSJR 076 Base Level Engineering
Current Plan=p01
Default Exp/Contr=0.3,0.1
English Units
Geom File=g01
Flow File=f01
Plan File=p01
Y Axis Title=Elevation
X Axis Title(PF)=Main Channel Distance
X Axis Title(XS)=Station
BEGIN DESCRIPTION:
WFSJR 076
END DESCRIPTION:
DSS File=dss
DSS Export Rating Curves= 0
DSS Export Rating Curve Sorted= 0
DSS Export Volume Flow Curves= 0
DXF OffsetX= 0
DXF OffsetY= 0
DXF ScaleX= 1
DXF ScaleY= 10

--- WFSJR 076.p01 (plan) ---

Plan Title=Multiple Run
Program Version=4.10
Short Identifier=Multiple Run
Geom File=g01
Flow File=f01
Subcritical Flow
K Sum by GR= 0
Std Step Tol= 0.01
Critical Tol= 0.01
Num of Std Step Trials= 20
Max Error Tol= 0.3
Flow Tol Ratio= 0.001
Split Flow NTrial= 30
Split Flow Tol= 0.02
Split Flow Ratio= 0.02
Log Output Level= 0
Friction Slope Method= 1
Unsteady Friction Slope Method= 2
Unsteady Bridges Friction Slope Method= 1
Parabolic Critical Depth
Global Vel Dist= 1 , 1 , 1
Global Log Level= 0
CheckData=True
Encroach Param=-1 ,0,0, 0
BEGIN DESCRIPTION:
Multiple Run
END DESCRIPTION:
Computation Interval=1HOUR
Output Interval=1HOUR
Run HTab= 0
Run UNet= 0
Run PostProcess= 0
Run WQNet= 0
UNET Theta= 1
UNET Theta Warmup= 1
UNET ZTol= 0.02
UNET ZSATol= 0.05
UNET MxIter= 20
UNET MaxInSteps= 0
UNET DtIC= 0
UNET DtMin= 0
UNET MaxCRTS= 20
UNET WFStab= 2
UNET SFStab= 1
UNET WFX= 1
UNET SFX= 1
UNET DSS MLevel= 4
UNET DZMax Abort= 100
UNET Convert EG Bridges= 0
UNET Use Existing IB Tables=-1
UNET Froude Reduction=False
UNET Froude Limit= 1
UNET Froude Power= 10
UNET Time Slicing=0,0, 5
UNET Junction Losses=0
Instantaneous Interval=1HOUR
DSS File=dss
Write IC File= 0
Write IC File at Sim End=0
Echo Input=False
Echo Parameters=False
Echo Output=False
Write Detailed= 0
WQ AD Non Conservative
WQ ULTIMATE=-1
WQ Max Comp Step=1HOUR
WQ Output Interval=15MIN
WQ Output Selected Increments= 0
WQ Output face flow=0
WQ Output face velocity=0
WQ Output face area=0
WQ Output face dispersion=0
WQ Output cell volume=0
WQ Output cell surface area=0
WQ Output cell continuity=0
WQ Output cumulative cell continuity=0
WQ Output face conc=0
WQ Output face dconc_dx=0
WQ Output face courant=0
WQ Output face peclet=0
WQ Output face adv mass=0
WQ Output face disp mass=0
WQ Output cell mass=0
WQ Output cell source sink temp=0
WQ Output cell source sink nsm=0
WQ Output MaxMinRange=-1
WQ Daily Max Min Mean=-1
WQ Daily Range=0
WQ Daily Time=0
WQ Create Restart=0
WQ Fixed Restart=0
WQ System Summary=0
WQ Use Fixed Temperature=0
Sorting and Armoring Iterations= 10
XS Update Threshold= 0.02
Hydraulics Update Threshold= 0.02
Energy Slope Method= 1
Volume Change Method= 0
XS Weighting Method= 0
Number of US Weighted Cross Sections= 1
Number of DS Weighted Cross Sections= 1
Upstream XS Weight=0.25
Main XS Weight=0.5
Downstream XS Weight=0.25
Number of DS XS's Weighted with US Boundary= 1
Upstream Boundary Weight= 1
Weight of XSs Associated with US Boundary= 0
Number of US XS's Weighted with DS Boundary= 1
Downstream Boundary Weight= 0.5
Weight of XSs Associated with DS Boundary= 0.5
Sediment Output Level= 4
Mass or Volume Output= 0
Output Increment Type= 1
Profile and TS Output Increment= 10
XS Output Flag= 0
XS Output Increment= 10
Disregard all LS=0
Disregard all Conn=0
Disregard all Breaches=0
Disregard all Pumps=0

--- WFSJR 076.f01 (steady flow) ---

Flow Title=Multiple
Program Version=4.10
Number of Profiles= 7
Profile Names=10-year,25-year,50-year,1pct_min,100-year,1pct_plu,500-year
River Rch & RM=WFSJR 076,Reach-1         ,6372
     654     882    1190     527    1593    4811    2950
Boundary for River Rch & Prof#=WFSJR 076,Reach-1         , 1
Up Type= 0
Dn Type= 3
Dn Slope=0.0013
Boundary for River Rch & Prof#=WFSJR 076,Reach-1         , 2
Up Type= 0
Dn Type= 3
Dn Slope=0.0013
Boundary for River Rch & Prof#=WFSJR 076,Reach-1         , 3
Up Type= 0
Dn Type= 3
Dn Slope=0.0013
Boundary for River Rch & Prof#=WFSJR 076,Reach-1         , 4
Up Type= 0
Dn Type= 3
Dn Slope=0.0013
Boundary for River Rch & Prof#=WFSJR 076,Reach-1         , 5
Up Type= 0
Dn Type= 3
Dn Slope=0.0013
Boundary for River Rch & Prof#=WFSJR 076,Reach-1         , 6
Up Type= 0
Dn Type= 3
Dn Slope=0.0013
Boundary for River Rch & Prof#=WFSJR 076,Reach-1         , 7
Up Type= 0
Dn Type= 3
Dn Slope=0.0013
DSS Import GetInterval= 0
DSS Import GetPeak= 0
DSS Import FillOption= 0

--- WFSJR 076.g01 (geometry) ---

Geom Title=Existing Conditions
Program Version=4.10

River Reach=WFSJR 076       ,Reach-1
Reach XY= 30
      3740282.05     10267678.15      3740298.32     10267573.98
      3740197.41     10267527.33      3740133.33     10267253.12
      3740337.33     10267083.85      3740348.18     10266975.34
      3740157.21     10266515.27      3739988.23     10265726.84
      3739888.23     10265576.84      3739908.23     10265376.84
      3739773.69     10265300.68       3739825.2     10265142.54
      3739698.23     10264916.84      3739538.23     10264816.84
      3739578.23     10264736.84      3739548.23     10264516.84
      3739598.23     10264466.84      3739578.23     10264246.84
      3739498.23     10264196.84      3739468.23     10264076.84
      3739308.23     10264036.84      3739278.23     10263876.84
      3739328.23     10263826.84      3739258.23     10263736.84
      3739468.23     10263596.84      3739388.23     10263396.84
      3739398.23     10263256.84      3739158.23     10262946.84
      3738928.23     10262996.84      3738878.23     10262866.84

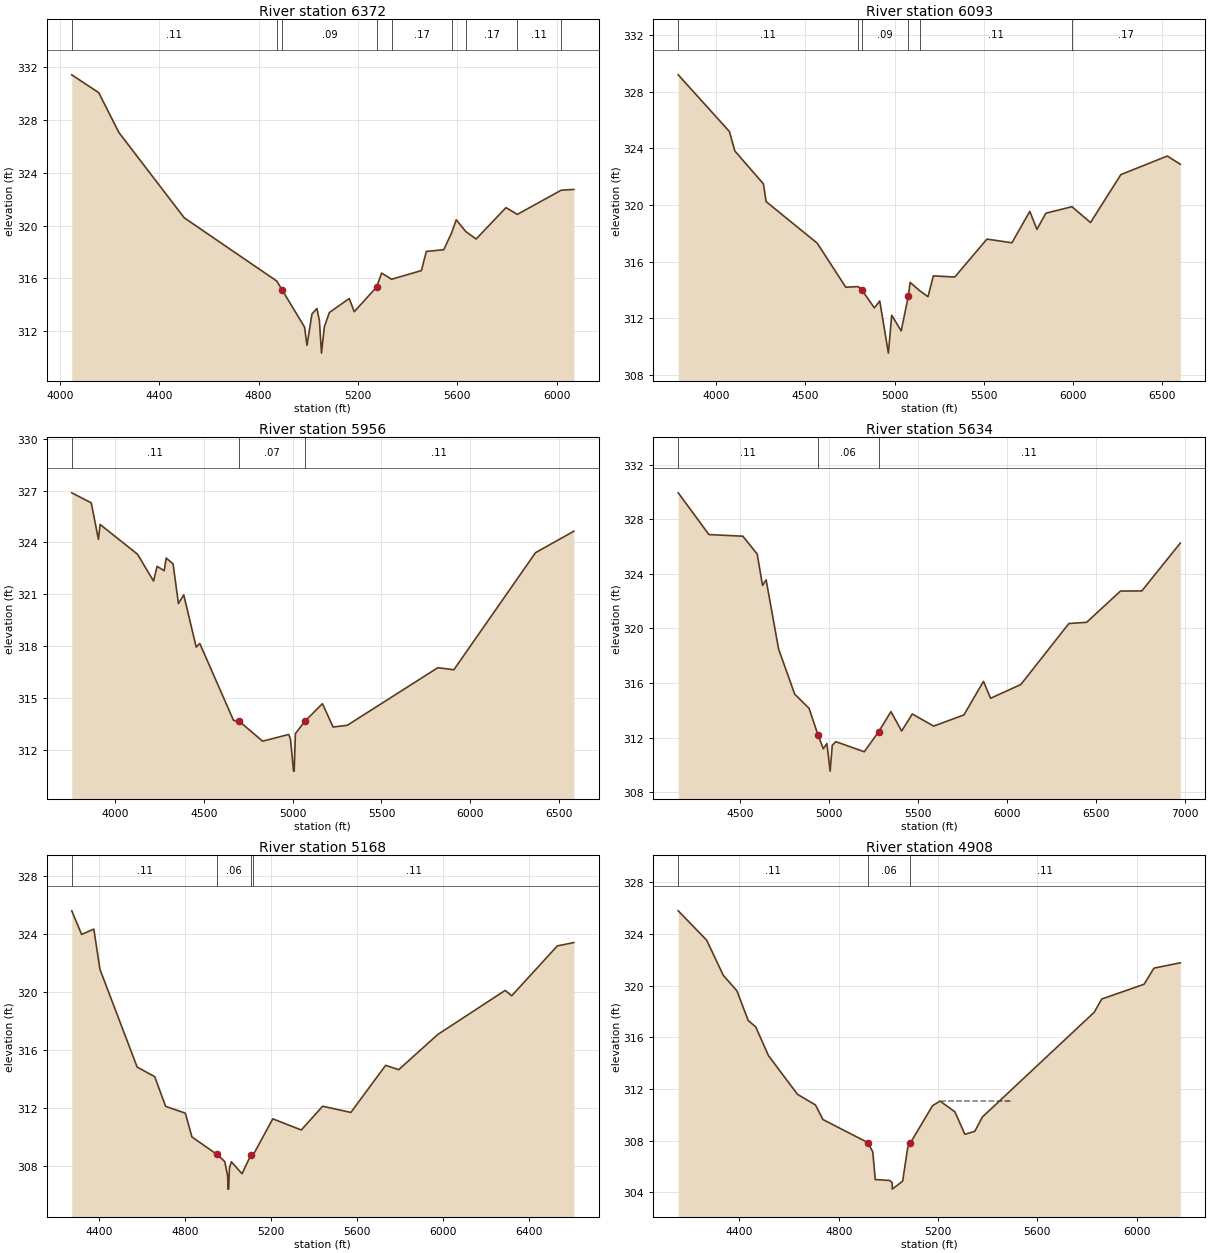
Type RM Length L Ch R = 1 ,6372    ,279,279,279
BEGIN DESCRIPTION:
WFSJR 076 8.0
END DESCRIPTION:
XS GIS Cut Line= 3
      3741235.33     10267743.18      3740440.15     10267621.64
       3739224.9     10267680.67
#Sta/Elev= 30
    4048  331.44  4156.4  330.09  4237.7  327.07  4500.7   320.6  4873.5   315.8
  4894.8  315.13  4984.9  312.32  4994.9  310.93  5014.9  313.31  5034.9  313.73
  5044.9   312.8  5053.2  310.34    5065  312.35    5085  313.42  5165.1  314.48
  5185.1  313.48  5275.2  315.35  5295.2  316.41  5335.3  315.94  5455.4   316.6
  5475.4  318.05  5545.5  318.18  5577.1  319.46  5595.6  320.45    5634  319.56
  5675.7  318.99  5795.8  321.37  5841.7  320.86  6017.9  322.69  6069.1  322.75
#Mann= 9 ,-1 , 0
    4048     .11       0  4873.5     .17       0  4894.8     .09       0
  5275.2     .17       0  5335.3     .17       0  5577.1     .11       0
    5634     .17       0  5841.7     .11       0  6017.9     .17       0
Bank Sta=4894.8,5275.2
XS Rating Curve= 0 ,0
Exp/Cntr=0.3,0.1

Type RM Length L Ch R = 1 ,6093    ,137,137,137
BEGIN DESCRIPTION:
Mapping XS 07729ca5
END DESCRIPTION:
XS GIS Cut Line= 3
       3741374.2     10267520.95      3740151.95     10267434.14
       3738565.1     10267496.64
#Sta/Elev= 30
  3787.3   329.2  4074.4  325.19  4104.4  323.82  4264.8  321.49  4279.7  320.24
  4566.3   317.3    4726  314.19  4796.2  314.23  4816.2  313.99  4886.4  312.73
  4916.5  313.22  4964.9  309.53  4983.5  312.21  5036.7   311.1  5076.8  313.57
  5086.8  314.53  5141.5  313.93  5186.9  313.52  5216.9  314.99    5337  314.91
  5517.1  317.59  5657.2  317.33  5757.3  319.55  5797.3  318.28  5847.4  319.42
  5993.5  319.88  6097.6  318.76  6267.7  322.15  6527.9  323.46  6600.7  322.88
#Mann= 6 ,-1 , 0
  3787.3     .11       0  4796.2     .17       0  4816.2     .09       0
  5076.8     .17       0  5141.5     .11       0  5993.5     .17       0
Bank Sta=4816.2,5076.8
XS Rating Curve= 0 ,0
Exp/Cntr=0.3,0.1

Type RM Length L Ch R = 1 ,5956    ,322,322,322
BEGIN DESCRIPTION:
Mapping XS 013cd14f
END DESCRIPTION:
XS GIS Cut Line= 3
      3741377.63     10267375.11      3740117.23     10267305.67
      3738552.08     10267284.85
#Sta/Elev= 30
  3755.7  326.87  3865.6  326.29  3905.7  324.18  3915.4  325.04    4126  323.32
  4216.2  321.77  4236.2  322.62  4276.3  322.37  4287.4   323.1  4326.3  322.76
  4356.4  320.47  4386.4  320.97  4456.5  317.95  4476.6  318.16  4666.9  313.71
  4696.9  313.68  4830.5  312.51  4977.3   312.9  4987.3  312.64  5004.8  310.78
  5008.3  310.78  5015.2  312.95  5067.4  313.65  5167.4  314.68  5227.4  313.33
  5307.4  313.43  5817.5  316.76  5907.5  316.64  6367.5  323.41  6583.3  324.65
#Mann= 3 , 0 , 0
  3755.7     .11       0  4696.9     .07       0  5067.4     .11       0
#XS Ineff= 1 ,-1
  5167.4    5600  314.68
Permanent Ineff=
       F
Bank Sta=4696.9,5067.4
XS Rating Curve= 0 ,0
Exp/Cntr=0.3,0.1

Type RM Length L Ch R = 1 ,5634    ,466,466,466
BEGIN DESCRIPTION:
WFSJR 076 7.0
END DESCRIPTION:
XS GIS Cut Line= 3
      3741179.69      10267163.3      3740337.33     10267083.85
      3738361.55     10267093.86
#Sta/Elev= 30
  4153.9  329.94  4326.5  326.88  4517.3  326.76  4597.7  325.45  4627.8  323.15
  4647.9  323.56  4718.2  318.48  4808.6  315.18    4889  314.15  4939.2   312.2
  4969.3  311.18  4989.4  311.56  5007.7  309.54  5019.5  311.43  5039.5   311.7
  5199.5  310.96  5279.5  312.41  5349.5   313.9  5409.5  312.48  5469.5  313.73
  5589.5  312.84  5759.5  313.66  5869.5  316.12  5909.5  314.88  6079.5  315.89
  6349.5  320.36  6449.5  320.45  6639.5  322.74  6759.5  322.75  6975.8  326.26
#Mann= 3 ,-1 , 0
  4153.9     .11       0  4939.2     .06       0  5279.5     .11       0
#XS Ineff= 1 ,-1
  5349.5    5800   313.9
Permanent Ineff=
       F
Bank Sta=4939.2,5279.5
XS Rating Curve= 0 ,0
Exp/Cntr=0.3,0.1

Type RM Length L Ch R = 1 ,5168    ,260,260,260
BEGIN DESCRIPTION:
WFSJR 076 6.0
END DESCRIPTION:
XS GIS Cut Line= 3
      3740936.65     10266507.06      3740224.48     10266645.48
      3738631.95      10266885.4
#Sta/Elev= 30
  4274.5  325.59  4320.4  323.96  4377.2  324.33  4405.7  321.55  4578.8  314.81
  4660.4  314.15  4711.3   312.1    4803  311.63  4833.6  309.99  4950.7  308.78
  4986.4  308.29    5000  307.28  5001.1  306.39  5004.6  306.39  5007.9  307.82
  5016.8  308.28  5066.7  307.45  5107.8  308.75  5117.9  308.73  5209.7  311.24
  5342.5  310.47  5441.6  312.11    5573  311.68  5734.8  314.93  5795.5  314.63
  5977.5  317.06    6291   320.1  6321.4  319.73  6533.7  323.17  6610.5   323.4
#Mann= 4 ,-1 , 0
  4274.5     .11       0  4950.7     .06       0  5107.8     .09       0
  5117.9     .11       0
Bank Sta=4950.7,5107.8
XS Rating Curve= 0 ,0
Exp/Cntr=0.3,0.1

Type RM Length L Ch R = 1 ,4908    ,466,466,466
BEGIN DESCRIPTION:
WFSJR 076 5.0
END DESCRIPTION:
XS GIS Cut Line= 3
      3740988.75     10266336.92      3740145.34     10266405.48
      3738972.07     10266482.71
#Sta/Elev= 30
  4153.8  325.78  4268.4  323.51  4335.3  320.79  4390.3  319.59  4435.6   317.3
  4465.7  316.81  4517.3  314.58  4634.1  311.59  4706.5  310.77  4736.6  309.64
  4917.2  307.86  4937.3  307.14  4947.3     305  5005.7  304.93  5015.5  304.76
  5015.8  304.26  5057.6  304.88  5077.7  307.44  5087.7   307.8  5177.9  310.71
  5207.9  311.07  5268.1  310.24  5308.1   308.5  5348.2  308.73  5378.3  309.83
  5829.3  317.94  5859.3  318.96  6029.7   320.1  6069.8  321.35  6175.8  321.76
#Mann= 3 , 0 , 0
  4153.8     .11       0  4917.2     .06       0  5087.7     .11       0
#XS Ineff= 1 ,-1
    5218    5500  311.06
Permanent Ineff=
       F
Bank Sta=4917.2,5087.7
XS Rating Curve= 0 ,0
Exp/Cntr=0.3,0.1

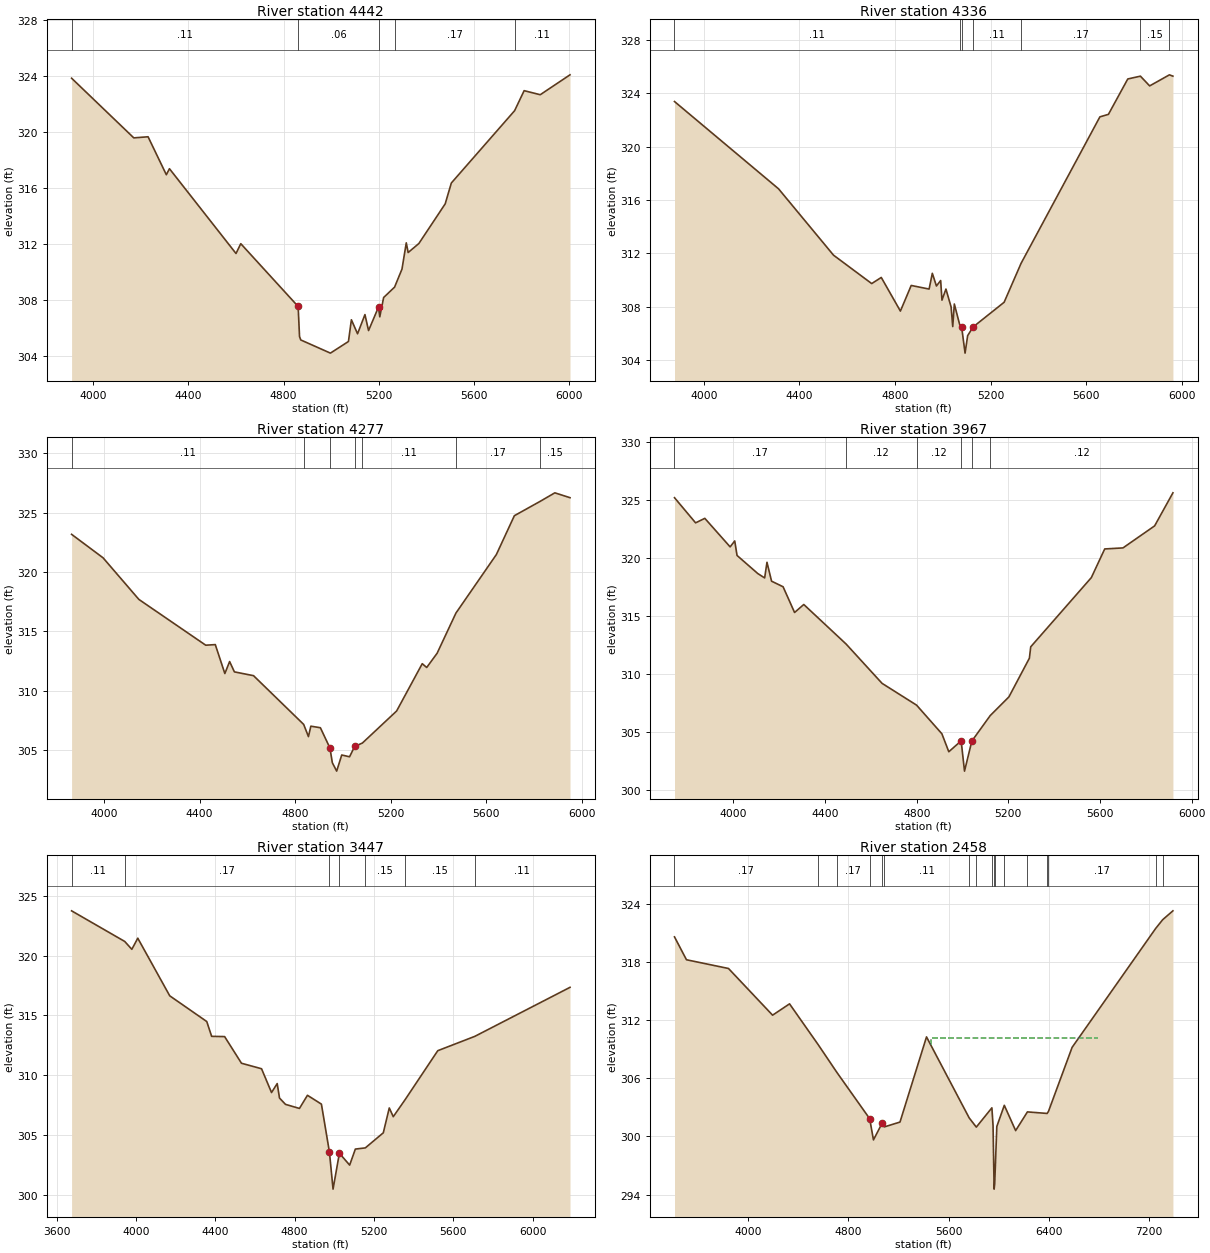
Type RM Length L Ch R = 1 ,4442    ,106,106,106
BEGIN DESCRIPTION:
Mapping XS da99418e
END DESCRIPTION:
XS GIS Cut Line= 3
      3741139.58     10265878.58      3740210.98     10265895.95
      3739106.83     10266277.88
#Sta/Elev= 30
  3908.1  323.83  4169.9  319.57  4229.9  319.65  4306.8  316.94  4319.9  317.37
  4599.9  311.32    4620  312.02  4861.3  307.54  4867.2  305.39  4872.5  305.15
  4997.1  304.21    5073  305.04  5085.4  306.59  5111.3  305.59  5142.4  306.96
  5157.6  305.82  5199.5   307.5  5204.8   306.8  5221.1  308.18  5267.1  308.92
  5298.3  310.21  5316.3  312.08  5324.2  311.39  5369.2  312.03    5480  314.86
  5505.9  316.35  5772.1  321.51  5812.2  322.94  5879.9  322.65  6005.2  324.07
#Mann= 5 ,-1 , 0
  3908.1     .11       0  4861.3     .06       0  5199.5     .11       0
  5267.1     .17       0  5772.1     .11       0
Bank Sta=4861.3,5199.5
XS Rating Curve= 0 ,0
Exp/Cntr=0.3,0.1

Type RM Length L Ch R = 1 ,4336    ,59,59,59
BEGIN DESCRIPTION:
Mapping XS 795c4667
END DESCRIPTION:
XS GIS Cut Line= 6
      3741143.46     10265819.77       3740152.1     10265842.34
      3740056.61      10265835.4      3740013.21     10265852.76
      3739981.96     10265889.22      3739132.01     10266199.71
#Sta/Elev= 30
  3876.7  323.38  4312.4  316.84  4542.5  311.87  4702.5  309.74  4742.5   310.2
  4822.6  307.68  4867.9   309.6  4942.8  309.33  4956.3  310.51  4973.5  309.56
  4991.2  309.97  4996.6   308.5  5013.3  309.33  5034.9  307.99  5041.8  306.52
  5048.4  308.21  5073.7  306.47    5079  306.49  5093.4  304.53  5104.2  305.84
  5127.1  306.49  5256.9  308.34    5328  311.26  5657.9  322.23  5693.7  322.42
  5774.7  325.07  5827.6  325.28  5866.3  324.55  5949.1  325.38  5963.7  325.28
#Mann= 7 ,-1 , 0
  3876.7     .11       0  5073.7     .09       0    5079     .06       0
  5127.1     .11       0    5328     .17       0  5827.6     .15       0
  5949.1     .11       0
#XS Ineff= 1 ,-1
    4640  4956.3  310.51
Permanent Ineff=
       F
Bank Sta=5079,5127.1
XS Rating Curve= 0 ,0
Exp/Cntr=0.3,0.1

Type RM Length L Ch R = 1 ,4277    ,310,310,310
BEGIN DESCRIPTION:
WFSJR 076 4.0
END DESCRIPTION:
XS GIS Cut Line= 3
      3741139.61     10265774.42      3740004.05     10265792.57
      3739121.82     10266148.97
#Sta/Elev= 30
  3864.3  323.18  3996.1   321.2  4146.1  317.69  4426.1  313.83  4466.1  313.88
  4506.1  311.44  4526.1  312.45  4546.1  311.58  4626.2  311.26  4836.2  307.15
  4856.2  306.12  4866.2     307  4906.2  306.87  4946.2  305.16  4956.2  303.92
  4974.4  303.21  4995.6  304.57  5028.3  304.42  5049.8  305.29  5082.2  305.58
  5225.4  308.28  5332.7  312.27  5351.4  311.95    5395  313.15  5473.8  316.54
    5643  321.47  5718.5  324.75  5827.3  325.97    5888  326.68  5951.5  326.27
#Mann= 7 ,-1 , 0
  3864.3     .11       0  4836.2     .11       0  4946.2     .07       0
  5049.8     .11       0  5082.2     .11       0  5473.8     .17       0
  5827.3     .15       0
Bank Sta=4946.2,5049.8
XS Rating Curve= 0 ,0
Exp/Cntr=0.3,0.1

Type RM Length L Ch R = 1 ,3967    ,520,520,520
BEGIN DESCRIPTION:
WFSJR 076 3.0
END DESCRIPTION:
XS GIS Cut Line= 3
      3741139.57     10265406.58      3739693.65     10265545.47
      3739073.22     10265916.34
#Sta/Elev= 30
  3742.9  325.18    3835  323.01  3875.2   323.4  3985.7  320.94  4005.8  321.45
  4015.9   320.2  4106.3  318.64  4136.4  318.26  4146.5  319.61  4166.6  317.98
  4216.8   317.5    4267  315.28  4307.2  315.97  4491.9  312.56  4648.8  309.17
  4799.5  307.29    4910  304.82  4940.1  303.27    4994  304.21  5008.7   301.6
  5040.6  304.19  5120.9  306.39  5202.4     308  5291.9  311.34  5297.7  312.32
  5562.3  318.29  5620.6  320.76  5700.4  320.85  5838.5  322.75  5918.3   325.6
#Mann= 6 ,-1 , 0
  3742.9     .17       0  4491.9     .12       0  4799.5     .12       0
    4994     .07       0  5040.6     .12       0  5120.9     .12       0
Bank Sta=4994,5040.6
XS Rating Curve= 0 ,0
Exp/Cntr=0.3,0.1

Type RM Length L Ch R = 1 ,3447    ,989,989,989
BEGIN DESCRIPTION:
WFSJR 076 2.0
END DESCRIPTION:
XS GIS Cut Line= 3
      3741139.61     10264989.91      3739440.18     10265180.89
       3738877.7     10265753.78
#Sta/Elev= 30
  3675.5  323.75  3943.3  321.19  3979.2  320.53  4009.3  321.46  4170.4  316.64
    4357  314.49  4381.7  313.25  4447.1  313.23  4532.1     311  4633.3  310.54
  4683.6  308.55  4712.2   309.3  4723.8  308.09    4754  307.56  4824.4  307.22
  4864.7  308.32  4935.1  307.58  4975.4  303.59  4993.8  300.47  5025.7  303.47
  5077.5  302.48  5106.2  303.82  5156.5  303.92  5247.1  305.18  5277.3  307.26
  5297.4  306.53  5357.8  307.97  5521.8  312.05  5708.7  313.25  6188.5  317.35
#Mann= 7 ,-1 , 0
  3675.5     .11       0  3943.3     .17       0  4975.4     .09       0
  5025.7     .17       0  5156.5     .15       0  5357.8     .15       0
  5708.7     .11       0
Bank Sta=4975.4,5025.7
XS Rating Curve= 0 ,0
Exp/Cntr=0.3,0.1

Type RM Length L Ch R = 1 ,2458    ,0,0,0
BEGIN DESCRIPTION:
WFSJR 076 1.0
END DESCRIPTION:
XS GIS Cut Line= 4
       3741139.6      10264604.5      3740127.68     10264312.83
      3739145.04     10264434.36      3737214.48     10264517.69
#Sta/Elev= 30
  3413.4  320.59  3508.9  318.23  3844.1  317.33  4195.8  312.51    4331  313.68
    4560  309.46  4709.5  306.59  4970.2  301.83  5000.4  299.64  5070.9   301.4
  5086.7  300.98    5212  301.48  5423.6  310.27  5763.9  301.91  5820.8  300.96
    5945  302.95  5954.3  301.12  5962.2  295.06  5962.6  294.56  5967.3  295.06
  5984.3  301.02    6044  303.21  6134.5   300.6  6228.5  302.53  6385.3  302.37
    6396  302.57  6584.9  309.19  7251.4  321.46  7307.8  322.37    7389  323.28
#Mann= 17 ,-1 , 0
  3413.4     .17       0    4560     .11       0  4709.5     .17       0
  4970.2     .09       0  5070.9     .17       0  5086.7     .11       0
  5763.9     .17       0  5820.8     .11       0    5945     .17       0
  5962.2     .12       0  5967.3     .17       0    6044     .11       0
  6228.5     .17       0  6385.3     .11       0    6396     .17       0
  7251.4     .11       0  7307.8     .17       0
#XS Ineff= 1 ,-1
  5456.6    6790  310.13
Permanent Ineff=
       F
Bank Sta=4970.2,5070.9
XS Rating Curve= 0 ,0
Exp/Cntr=0.3,0.1

Chan Stop Cuts=-1
Use User Specified Reach Order=0
Composite Channel Slope=5