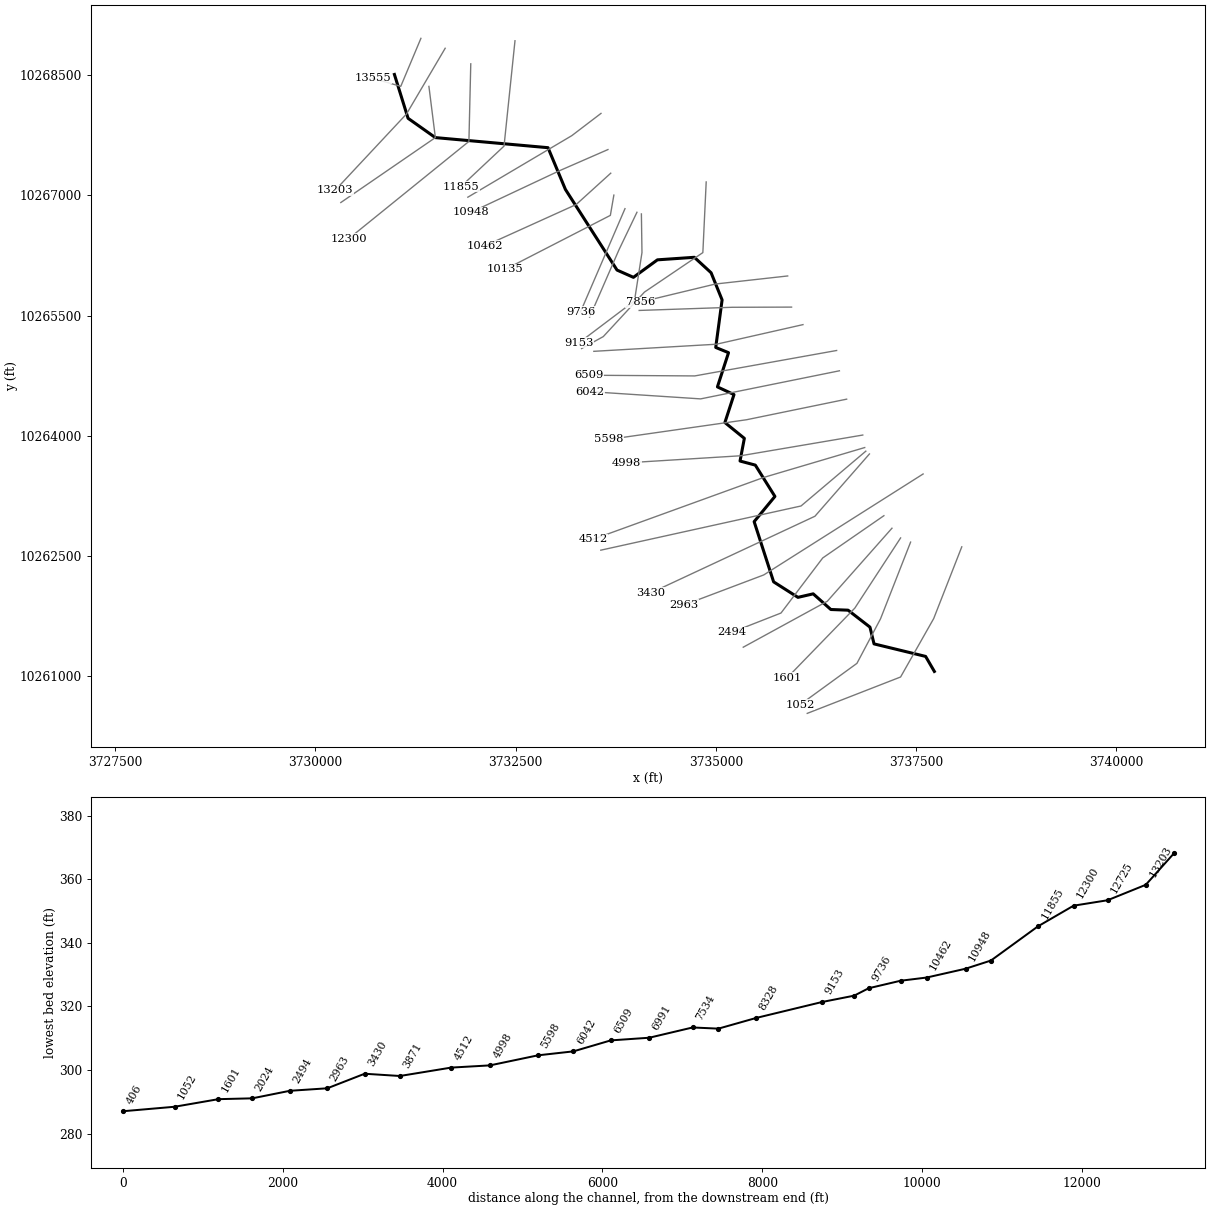
--- WFSJR 078.prj (project) ---

Proj Title=WFSJR 078 Base Level Engineering
Current Plan=p01
Default Exp/Contr=0.3,0.1
English Units
Geom File=g01
Flow File=f01
Plan File=p01
Y Axis Title=Elevation
X Axis Title(PF)=Main Channel Distance
X Axis Title(XS)=Station
BEGIN DESCRIPTION:
WFSJR 078
END DESCRIPTION:
DSS Export Rating Curves= 0
DSS Export Rating Curve Sorted= 0
DSS Export Volume Flow Curves= 0
DXF OffsetX= 0
DXF OffsetY= 0
DXF ScaleX= 1
DXF ScaleY= 10

--- WFSJR 078.p01 (plan) ---

Plan Title=Multiple Run
Program Version=4.10
Short Identifier=Multiple
Geom File=g01
Flow File=f01
Subcritical Flow
K Sum by GR= 0
Std Step Tol= 0.01
Critical Tol= 0.01
Num of Std Step Trials= 20
Max Error Tol= 0.3
Flow Tol Ratio= 0.001
Split Flow NTrial= 30
Split Flow Tol= 0.02
Split Flow Ratio= 0.02
Log Output Level= 0
Friction Slope Method= 1
Unsteady Friction Slope Method= 2
Unsteady Bridges Friction Slope Method= 1
Parabolic Critical Depth
Global Vel Dist= 1 , 1 , 1
Global Log Level= 0
CheckData=True
Encroach Param=-1 ,0,0, 0
BEGIN DESCRIPTION:
Multiple Run
END DESCRIPTION:
Computation Interval=1HOUR
Output Interval=1HOUR
Run HTab= 0
Run UNet= 0
Run PostProcess= 0
Run WQNet= 0
UNET Theta= 1
UNET Theta Warmup= 1
UNET ZTol= 0.02
UNET ZSATol= 0.05
UNET MxIter= 20
UNET MaxInSteps= 0
UNET DtIC= 0
UNET DtMin= 0
UNET MaxCRTS= 20
UNET WFStab= 2
UNET SFStab= 1
UNET WFX= 1
UNET SFX= 1
UNET DSS MLevel= 4
UNET DZMax Abort= 100
UNET Convert EG Bridges= 0
UNET Use Existing IB Tables=-1
UNET Froude Reduction=False
UNET Froude Limit= 1
UNET Froude Power= 10
UNET Time Slicing=0,0, 5
UNET Junction Losses=0
Instantaneous Interval=1HOUR
Write IC File= 0
Write IC File at Sim End=0
Echo Input=False
Echo Parameters=False
Echo Output=False
Write Detailed= 0
WQ AD Non Conservative
WQ ULTIMATE=-1
WQ Max Comp Step=1HOUR
WQ Output Interval=15MIN
WQ Output Selected Increments= 0
WQ Output face flow=0
WQ Output face velocity=0
WQ Output face area=0
WQ Output face dispersion=0
WQ Output cell volume=0
WQ Output cell surface area=0
WQ Output cell continuity=0
WQ Output cumulative cell continuity=0
WQ Output face conc=0
WQ Output face dconc_dx=0
WQ Output face courant=0
WQ Output face peclet=0
WQ Output face adv mass=0
WQ Output face disp mass=0
WQ Output cell mass=0
WQ Output cell source sink temp=0
WQ Output cell source sink nsm=0
WQ Output MaxMinRange=-1
WQ Daily Max Min Mean=-1
WQ Daily Range=0
WQ Daily Time=0
WQ Create Restart=0
WQ Fixed Restart=0
WQ System Summary=0
WQ Use Fixed Temperature=0
Sorting and Armoring Iterations= 10
XS Update Threshold= 0.02
Hydraulics Update Threshold= 0.02
Energy Slope Method= 1
Volume Change Method= 0
XS Weighting Method= 0
Number of US Weighted Cross Sections= 1
Number of DS Weighted Cross Sections= 1
Upstream XS Weight=0.25
Main XS Weight=0.5
Downstream XS Weight=0.25
Number of DS XS's Weighted with US Boundary= 1
Upstream Boundary Weight= 1
Weight of XSs Associated with US Boundary= 0
Number of US XS's Weighted with DS Boundary= 1
Downstream Boundary Weight= 0.5
Weight of XSs Associated with DS Boundary= 0.5
Sediment Output Level= 4
Mass or Volume Output= 0
Output Increment Type= 1
Profile and TS Output Increment= 10
XS Output Flag= 0
XS Output Increment= 10
Disregard all LS=0
Disregard all Conn=0
Disregard all Breaches=0
Disregard all Pumps=0

--- WFSJR 078.f01 (steady flow) ---

Flow Title=Multiple
Program Version=4.10
Number of Profiles= 7
Profile Names=10-year,25-year,50-year,1pct_min,100-year,1pct_plu,500-year
River Rch & RM=WFSJR 078,Reach-1         ,13555
     502     674     905     400    1209    3651    2233
River Rch & RM=WFSJR 078,Reach-1         ,5598
     788    1083    1478     663    2002    6046    3803
Boundary for River Rch & Prof#=WFSJR 078,Reach-1         , 1
Up Type= 0
Dn Type= 3
Dn Slope=0.002
Boundary for River Rch & Prof#=WFSJR 078,Reach-1         , 2
Up Type= 0
Dn Type= 3
Dn Slope=0.002
Boundary for River Rch & Prof#=WFSJR 078,Reach-1         , 3
Up Type= 0
Dn Type= 3
Dn Slope=0.002
Boundary for River Rch & Prof#=WFSJR 078,Reach-1         , 4
Up Type= 0
Dn Type= 3
Dn Slope=0.002
Boundary for River Rch & Prof#=WFSJR 078,Reach-1         , 5
Up Type= 0
Dn Type= 3
Dn Slope=0.002
Boundary for River Rch & Prof#=WFSJR 078,Reach-1         , 6
Up Type= 0
Dn Type= 3
Dn Slope=0.002
Boundary for River Rch & Prof#=WFSJR 078,Reach-1         , 7
Up Type= 0
Dn Type= 3
Dn Slope=0.002
DSS Import GetInterval= 0
DSS Import GetPeak= 0
DSS Import FillOption= 0

--- WFSJR 078.g01 (geometry) ---

Geom Title=Existing Conditions
Program Version=4.10

River Reach=WFSJR 078       ,Reach-1
Reach XY= 30
      3730987.07     10268510.02      3731157.55     10267962.62
      3731498.26     10267721.74      3732904.51     10267595.87
      3733122.01     10267074.62      3733766.38     10266067.81
      3733971.29     10265977.16      3734270.75     10266195.62
      3734731.33     10266227.26      3734940.68     10266034.62
      3735078.22      10265695.5      3734998.59     10265101.77
      3735158.43     10265036.59      3735019.74     10264609.15
      3735226.77     10264513.43      3735113.06     10264164.35
      3735355.94     10263966.88       3735302.1     10263683.68
      3735493.11      10263632.7      3735737.63     10263241.69
      3735478.27     10262926.85      3735721.38     10262175.26
      3736025.17     10261981.72      3736215.66      10262025.5
      3736435.64     10261830.07      3736651.04     10261821.58
      3736924.41     10261609.85      3736975.11     10261400.74
      3737619.02     10261244.33      3737728.23     10261056.84

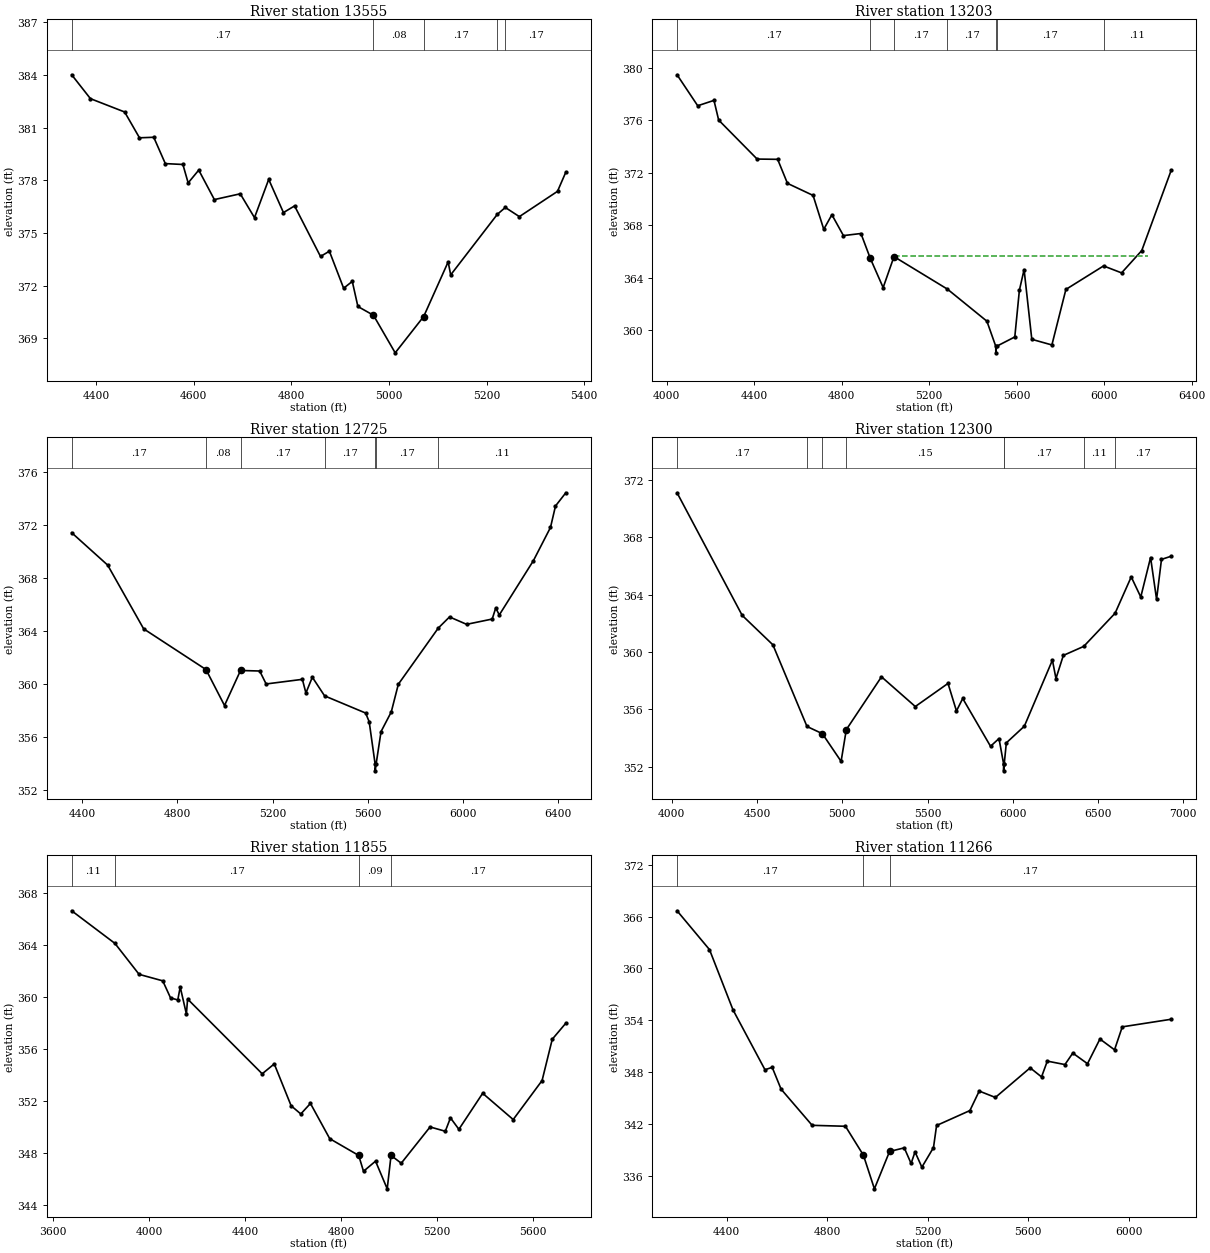
Type RM Length L Ch R = 1 ,13555   ,352,352,352
BEGIN DESCRIPTION:
WFSJR 078 27.0
END DESCRIPTION:
XS GIS Cut Line= 3
      3731317.87      10268961.1      3731066.41     10268361.93
      3730717.83     10268461.08
#Sta/Elev= 30
  4350.2  384.01  4388.6  382.65  4458.7  381.89  4489.1  380.42  4518.3  380.45
    4542  378.95    4578   378.9  4588.8  377.85  4610.5  378.58  4642.5   376.9
  4695.5  377.23  4724.7  375.87  4753.8  378.05    4784  376.16  4806.8  376.54
  4859.9  373.66  4878.1  373.96  4907.3  371.85    4925  372.24  4936.5  370.81
  4968.4  370.31  5012.9  368.17  5071.3  370.24  5121.4  373.35  5126.6  372.61
  5222.1  376.06  5238.5  376.45  5267.3  375.93  5345.4  377.37  5362.4  378.46
#Mann= 5 ,-1 , 0
  4350.2     .17       0  4968.4     .08       0  5071.3     .17       0
  5222.1     .11       0  5238.5     .17       0
Bank Sta=4968.4,5071.3
XS Rating Curve= 0 ,0
Exp/Cntr=0.3,0.1

Type RM Length L Ch R = 1 ,13203   ,478,478,478
BEGIN DESCRIPTION:
WFSJR 078 26.0
END DESCRIPTION:
XS GIS Cut Line= 3
       3731620.9     10268837.21      3731138.02     10268016.88
      3730245.91     10267062.92
#Sta/Elev= 30
  4048.1  379.47  4142.5  377.11  4216.8  377.52  4238.2  376.02    4414  373.05
  4507.8  373.03  4552.6   371.2  4669.7  370.28  4718.5   367.7  4755.6  368.81
  4808.4  367.22  4888.4  367.38  4931.3  365.48  4989.9  363.26  5039.5  365.62
  5283.8  363.14    5464   360.7  5504.5  358.79  5504.8  358.29  5508.5  358.79
  5591.5   359.5  5612.5  363.06    5634  364.63  5669.2  359.32    5761  358.89
    5825  363.12  5997.1  364.91  6079.5  364.38  6171.7  366.08  6306.1  372.19
#Mann= 7 ,-1 , 0
  4048.1     .17       0  4931.3     .08       0  5039.5     .17       0
  5283.8     .17       0  5504.5     .12       0  5508.5     .17       0
  5997.1     .11       0
#XS Ineff= 1 ,-1
  5053.7    6200  365.63
Permanent Ineff=
       T
Bank Sta=4931.3,5039.5
XS Rating Curve= 0 ,0
Exp/Cntr=0.3,0.1

Type RM Length L Ch R = 1 ,12725   ,425,425,425
BEGIN DESCRIPTION:
WFSJR 078 25.0
END DESCRIPTION:
XS GIS Cut Line= 3
      3731417.85      10268361.1      3731498.26     10267721.74
      3730317.83     10266911.06
#Sta/Elev= 30
  4355.6  371.44  4506.8  368.99    4658  364.17    4920  361.09  4997.8  358.37
 5065.12  361.02  5145.7  360.98  5172.7     360    5325  360.35  5339.9  359.32
  5366.9  360.51  5418.4   359.1  5590.9   357.8  5605.8  357.14  5630.8  353.93
  5631.1  353.43  5634.8  353.93  5655.6   356.4  5698.5  357.88  5728.3  359.98
  5896.2  364.23  5943.4  365.07  6015.2  364.51  6122.7  364.91  6137.6  365.75
  6152.5  365.22    6296  369.33  6367.7  371.84  6388.7  373.46    6432  374.46
#Mann= 7 ,-1 , 0
  4355.6     .17       0    4920     .08       0 5065.12     .17       0
  5418.4     .17       0  5630.8     .12       0  5634.8     .17       0
  5896.2     .11       0
#XS Ineff= 1 ,-1
  5136.8    5820   360.5
Permanent Ineff=
       T
Bank Sta=4920,5065.12
XS Rating Curve= 0 ,0
Exp/Cntr=0.3,0.1

Type RM Length L Ch R = 1 ,12300   ,445,445,445
BEGIN DESCRIPTION:
WFSJR 078 24.0
END DESCRIPTION:
XS GIS Cut Line= 3
      3731940.35     10268642.82       3731917.1       10267674.
      3730417.82     10266461.04
#Sta/Elev= 30
  4030.9  371.09  4412.8  362.55  4592.8   360.5  4792.9  354.81  4882.9  354.31
  4992.9  352.38  5023.4  354.59  5229.7  358.27    5428   356.2  5619.8  357.81
  5669.4  355.89  5706.1  356.76  5869.2  353.43  5918.8  353.97  5945.6  352.22
  5945.8  351.72  5949.6  352.22  5961.9  353.67  6067.5  354.83  6232.1  359.43
  6252.9  358.15  6296.1  359.76  6415.9  360.39  6599.7   362.7  6694.2  365.23
  6750.2  363.83  6807.7  366.58  6842.9  363.67  6871.7  366.45  6928.5  366.67
#Mann= 8 ,-1 , 0
  4030.9     .17       0  4792.9     .15       0  4882.9     .09       0
  5023.4     .15       0  5945.6     .12       0  5949.6     .17       0
  6415.9     .11       0  6599.7     .17       0
#XS Ineff= 1 ,-1
  5229.7    6210  358.27
Permanent Ineff=
       F
Bank Sta=4882.9,5023.4
XS Rating Curve= 0 ,0
Exp/Cntr=0.3,0.1

Type RM Length L Ch R = 1 ,11855   ,589,589,589
BEGIN DESCRIPTION:
WFSJR 078 23.0
END DESCRIPTION:
XS GIS Cut Line= 3
      3732492.43     10268930.99      3732355.47      10267615.4
      3731817.88      10267111.1
#Sta/Elev= 30
  3677.3  366.62  3857.6  364.11  3958.3  361.73  4056.9  361.23  4089.4  359.92
  4119.6  359.76  4129.7  360.76  4155.5  358.68  4160.5  359.83  4471.5  354.08
  4521.8  354.84  4592.1  351.62  4632.4  350.99  4672.6   351.8    4753  349.09
  4873.7   347.8  4893.8  346.58    4944  347.36  4992.6  345.23  5008.6   347.8
  5051.1   347.2  5171.3  349.99  5234.8  349.66  5256.3  350.69  5291.4  349.81
  5390.6  352.58  5517.8  350.56  5638.2  353.56  5680.7  356.74  5737.1  357.97
#Mann= 4 ,-1 , 0
  3677.3     .11       0  3857.6     .17       0  4873.7     .09       0
  5008.6     .17       0
Bank Sta=4873.7,5008.6
XS Rating Curve= 0 ,0
Exp/Cntr=0.3,0.1

Type RM Length L Ch R = 1 ,11266   ,318,318,318
BEGIN DESCRIPTION:
WFSJR 078 22.0
END DESCRIPTION:
XS GIS Cut Line= 3
       3733566.2     10268023.84      3733201.63     10267746.08
      3731903.89     10266977.85
#Sta/Elev= 30
  4202.9  366.68    4332  362.18  4425.5   355.2  4552.8  348.26  4581.5  348.54
  4616.9  346.01  4740.5  341.82  4873.1  341.71  4944.5  338.36  4988.3  334.46
  5048.6  338.79  5107.1  339.21  5134.3   337.4  5149.9  338.74  5177.2  336.97
  5223.4  339.24  5235.7   341.8  5368.3  343.53  5405.4  345.79  5469.7  345.05
  5608.1  348.48  5653.4  347.43  5676.4  349.26  5746.5  348.86  5777.8  350.19
  5836.3  348.96  5885.8  351.82  5943.9  350.57  5974.7  353.23  6169.3  354.11
#Mann= 3 , 0 , 0
  4202.9     .17       0  4944.5     .09       0  5048.6     .17       0
Bank Sta=4944.5,5048.6
XS Rating Curve= 0 ,0
Exp/Cntr=0.3,0.1

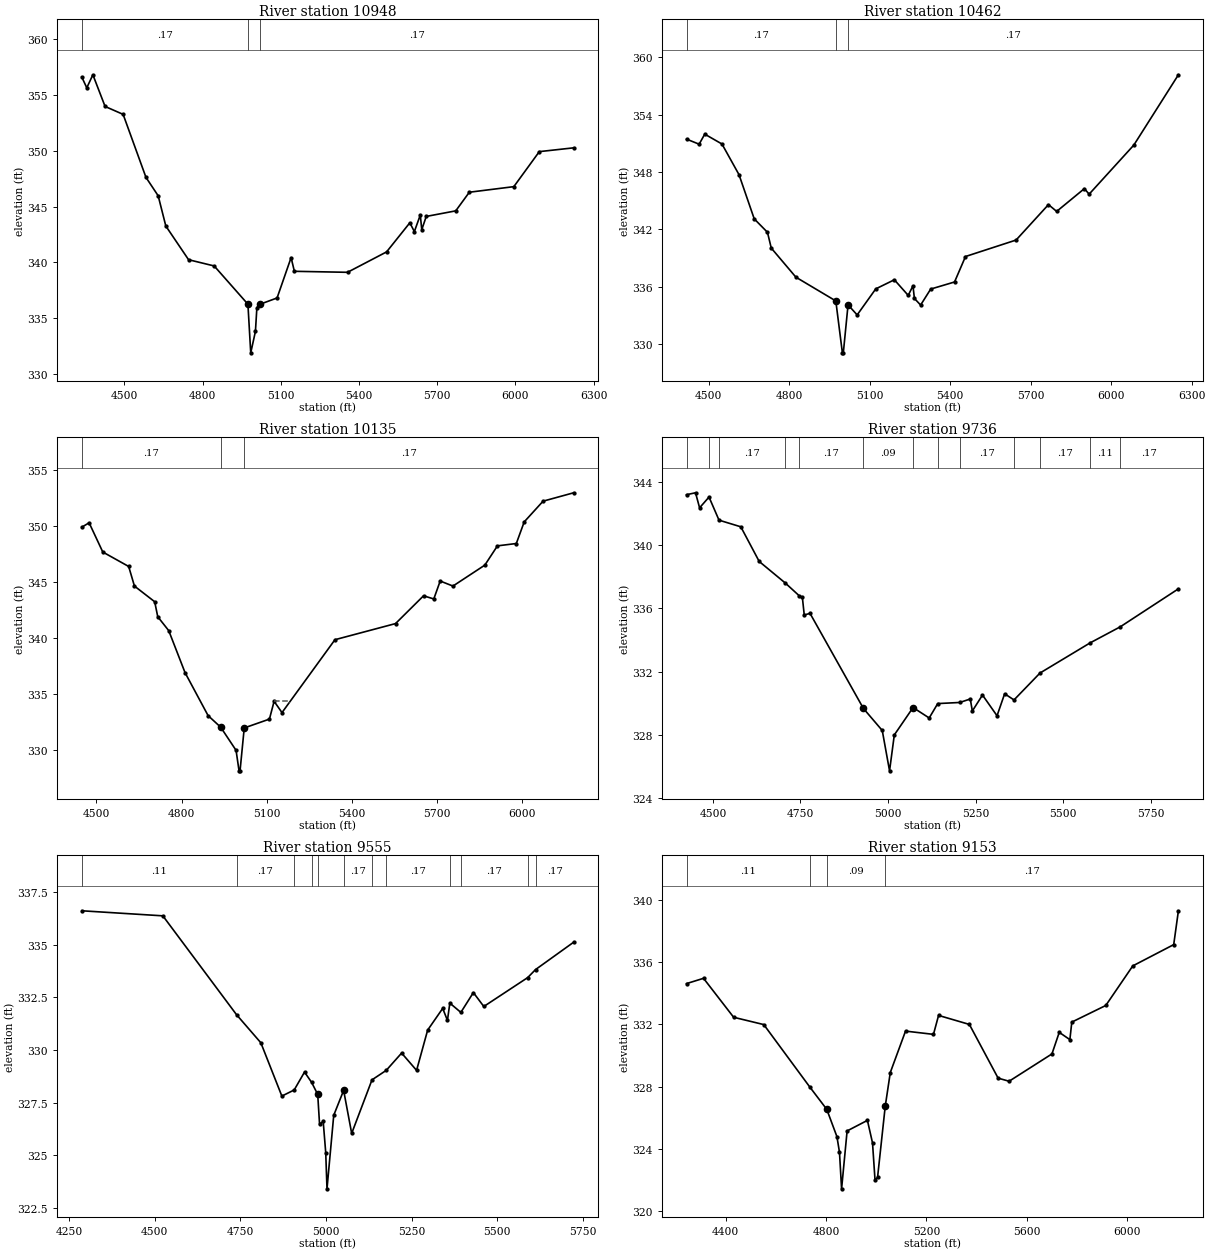
Type RM Length L Ch R = 1 ,10948   ,486,486,486
BEGIN DESCRIPTION:
WFSJR 078 21.0
END DESCRIPTION:
XS GIS Cut Line= 3
        3733653.     10267572.45      3733045.57     10267307.24
      3731938.58     10266786.86
#Sta/Elev= 30
  4337.2   356.6  4356.2  355.64  4379.6  356.81  4426.4  353.97  4495.6  353.26
  4583.2  347.61    4630  345.96  4659.3  343.25  4746.5  340.23  4844.7  339.67
  4974.1  336.24  4984.9  331.88  5002.9   333.8  5008.5  335.94  5019.6  336.23
  5085.9   336.8  5139.7  340.42  5152.2  339.19    5356   339.1  5505.8  340.93
    5595  343.54  5612.3  342.75  5635.1  344.24  5640.7  342.92  5657.9  344.11
    5771  344.61  5823.1  346.28  5993.7  346.78  6091.4  349.92  6223.2  350.26
#Mann= 3 , 0 , 0
  4337.2     .17       0  4974.1     .09       0  5019.6     .17       0
Bank Sta=4974.1,5019.6
XS Rating Curve= 0 ,0
Exp/Cntr=0.3,0.1

Type RM Length L Ch R = 1 ,10462   ,327,327,327
BEGIN DESCRIPTION:
WFSJR 078 20.0
END DESCRIPTION:
XS GIS Cut Line= 3
      3733687.77     10267277.35      3733255.99     10266885.92
      3732116.57     10266370.21
#Sta/Elev= 30
  4417.2  351.43  4464.1   350.9    4485  351.95  4549.2  350.92  4612.7  347.72
  4669.5   343.1  4718.8   341.7    4733  340.05  4824.9  337.01  4973.6  334.53
  4998.1  329.11  5001.6  329.11  5019.2  334.12  5053.2  333.07  5122.5  335.79
  5191.8  336.74  5243.5  335.11  5261.2  336.11  5266.6  334.79  5289.7   334.1
  5327.3  335.77  5416.2  336.51    5457  339.17  5645.6  340.89  5766.3  344.59
  5796.9  343.88  5900.2  346.26  5917.9  345.68  6084.6  350.81  6250.7  358.15
#Mann= 3 , 0 , 0
  4417.2     .17       0  4973.6     .09       0  5019.2     .17       0
#XS Ineff= 1 ,-1
  5191.8    5440  336.74
Permanent Ineff=
       F
Bank Sta=4973.6,5019.2
XS Rating Curve= 0 ,0
Exp/Cntr=0.3,0.1

Type RM Length L Ch R = 1 ,10135   ,399,399,399
BEGIN DESCRIPTION:
WFSJR 078 19.0
END DESCRIPTION:
XS GIS Cut Line= 3
       3733726.8     10267003.85      3733683.04     10266750.68
      3732369.27     10266075.57
#Sta/Elev= 30
  4448.5  349.86  4474.2  350.25  4522.4  347.64  4613.7  346.35    4634   344.6
  4705.4   343.2  4716.2  341.86  4754.9  340.62  4812.4  336.87  4893.7  333.03
    4938     332  4992.3  329.93  5002.8   328.1  5006.3   328.1  5021.1  331.93
  5109.9  332.72  5126.4  334.31  5154.2   333.3  5340.9  339.81  5554.5  341.25
  5653.2  343.73  5689.4  343.45  5711.9  345.05  5756.9   344.6  5869.3  346.47
  5913.7  348.19  5980.3   348.4  6008.1  350.33  6074.6  352.18  6182.5  352.93
#Mann= 3 , 0 , 0
  4448.5     .17       0    4938     .09       0  5021.1     .17       0
#XS Ineff= 1 ,-1
  5126.4    5180  334.31
Permanent Ineff=
       F
Bank Sta=4938,5021.1
XS Rating Curve= 0 ,0
Exp/Cntr=0.3,0.1

Type RM Length L Ch R = 1 ,9736    ,181,181,181
BEGIN DESCRIPTION:
Mapping XS 1ed0f3fb
END DESCRIPTION:
XS GIS Cut Line= 2
      3733865.69      10266834.6      3733310.25      10265545.8
#Sta/Elev= 30
  4424.9  343.19  4450.5  343.31  4462.1  342.36    4489  343.04  4517.5  341.58
  4579.7  341.16  4632.2  338.97  4706.5  337.61  4746.5   336.8  4755.3  336.71
  4760.7  335.59  4777.2  335.69  4929.6  329.68  4983.3  328.29  5004.1  325.74
  5017.7  328.01  5071.2  329.74  5117.2  329.08  5141.6  329.99  5204.4  330.06
  5234.5  330.28  5240.3  329.52  5269.3  330.53  5310.8  329.22  5332.5  330.61
  5359.2  330.22  5433.4  331.92  5576.8  333.83  5662.4  334.84  5828.3  337.24
#Mann= 13 ,-1 , 0
  4424.9     .17       0    4489     .11       0  4517.5     .17       0
  4706.5     .11       0  4746.5     .17       0  4929.6     .09       0
  5071.2     .17       0  5141.6     .11       0  5204.4     .17       0
  5359.2     .11       0  5433.4     .17       0  5576.8     .11       0
  5662.4     .17       0
#XS Ineff= 1 ,-1
  5269.3    5400  330.53
Permanent Ineff=
       F
Bank Sta=4929.6,5071.2
XS Rating Curve= 0 ,0
Exp/Cntr=0.3,0.1

Type RM Length L Ch R = 1 ,9555    ,402,402,402
BEGIN DESCRIPTION:
WFSJR 078 18.0
END DESCRIPTION:
XS GIS Cut Line= 3
      3734015.01      10266789.5      3733790.09     10266319.99
      3733424.72     10265480.45
#Sta/Elev= 30
  4286.9   336.6  4523.5  336.36  4738.7  331.67  4809.6  330.34    4871  327.81
    4907   328.1  4937.2  328.95  4957.9  328.46  4975.7  327.89  4981.1  326.47
  4991.7  326.61  4999.1  325.13  5002.8  323.41  5022.5   326.9  5051.4  328.08
  5074.9  326.04  5134.2  328.58  5175.8  329.03  5220.7  329.85  5264.4  329.03
  5296.7  330.94  5340.7  331.97  5354.5   331.4  5361.5  332.22  5393.7  331.78
  5430.2  332.72  5460.7  332.06  5588.8  333.43  5611.7  333.81  5723.1  335.11
#Mann= 12 ,-1 , 0
  4286.9     .11       0  4738.7     .17       0    4907     .11       0
  4957.9     .17       0  4975.7     .09       0  5051.4     .17       0
  5134.2     .11       0  5175.8     .17       0  5361.5     .11       0
  5393.7     .17       0  5588.8     .11       0  5611.7     .17       0
#XS Ineff= 1 ,-1
  5220.7    5290  329.85
Permanent Ineff=
       F
Bank Sta=4975.7,5051.4
XS Rating Curve= 0 ,0
Exp/Cntr=0.3,0.1

Type RM Length L Ch R = 1 ,9153    ,825,825,825
BEGIN DESCRIPTION:
WFSJR 078 17.0
END DESCRIPTION:
XS GIS Cut Line= 4
      3734070.56     10266768.62      3734077.81     10266286.32
      3733984.05     10265682.94      3733292.83     10265161.04
#Sta/Elev= 30
  4244.6  334.63  4312.2  334.97  4432.2  332.46  4552.2  331.99  4735.4  327.97
  4803.1  326.53  4843.6  324.77  4853.7  323.77  4862.1  321.41  4884.1  325.14
    4965  325.82  4985.3  324.37  4995.4  321.95  5005.5  322.16  5035.9  326.72
  5056.1   328.9  5116.8  331.57  5228.1  331.36  5248.4  332.58  5371.1     332
  5485.6  328.54  5529.3  328.34    5700   330.1  5729.1  331.49  5771.4  331.02
  5779.1  332.15  5914.4  333.22    6022  335.77    6185  337.14  6203.7  339.32
#Mann= 4 ,-1 , 0
  4244.6     .11       0  4735.4     .17       0  4803.1     .09       0
  5035.9     .17       0
Bank Sta=4803.1,5035.9
XS Rating Curve= 0 ,0
Exp/Cntr=0.3,0.1

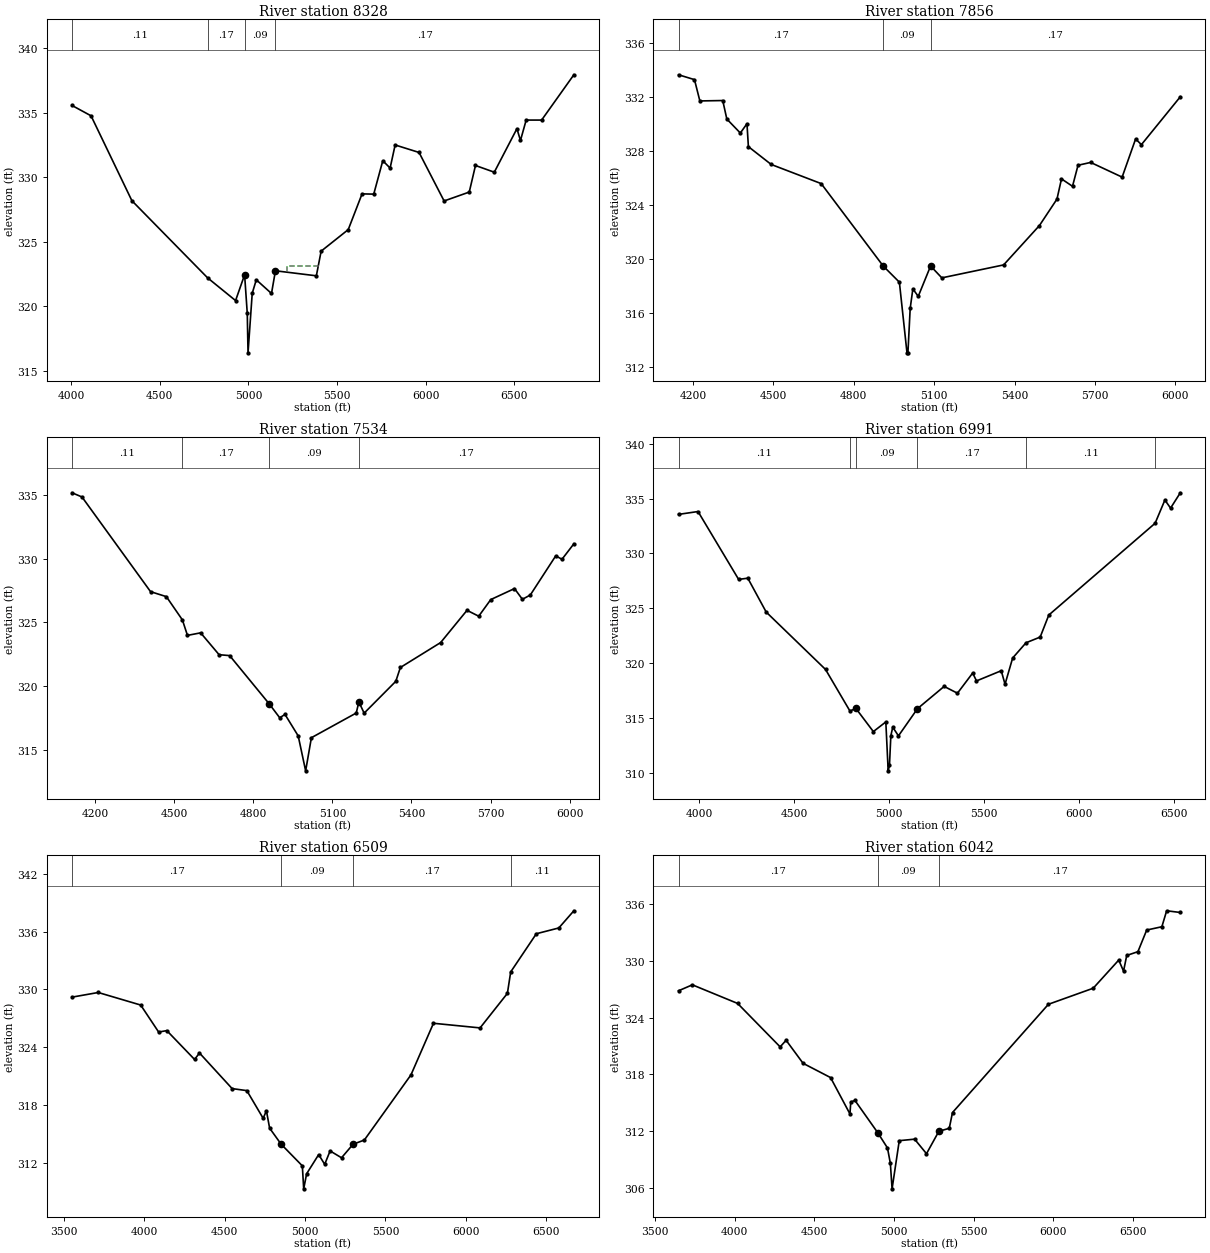
Type RM Length L Ch R = 1 ,8328    ,472,472,472
BEGIN DESCRIPTION:
Mapping XS 6bdec2cc
END DESCRIPTION:
XS GIS Cut Line= 5
      3734879.59     10267167.95      3734837.92     10266286.01
      3734108.75     10265792.95      3733594.86      10265237.4
      3733324.03     10265088.09
#Sta/Elev= 30
  4005.7  335.56  4112.7  334.76    4343  328.18    4770   322.2  4927.6  320.44
  4978.5  322.44  4993.5  319.45  4997.8  316.39  5021.5  321.01  5044.4  322.05
  5130.1  320.99  5152.3  322.75    5383  322.36    5410  324.27  5562.8  325.94
  5640.7  328.71  5706.6  328.69  5757.6  331.28  5798.9  330.71  5827.2   332.5
  5962.1  331.92  6103.3  328.16  6245.1  328.85  6280.2  330.91  6386.3  330.39
  6513.8  333.76  6533.9  332.85    6566  334.43  6653.1  334.43  6834.9  337.94
#Mann= 4 ,-1 , 0
  4005.7     .11       0    4770     .17       0  4978.5     .09       0
  5152.3     .17       0
#XS Ineff= 1 ,-1
  5215.3    5400  323.11
Permanent Ineff=
       F
Bank Sta=4978.5,5152.3
XS Rating Curve= 0 ,0
Exp/Cntr=0.3,0.1

Type RM Length L Ch R = 1 ,7856    ,322,322,322
BEGIN DESCRIPTION:
WFSJR 078 16.0
END DESCRIPTION:
XS GIS Cut Line= 3
      3735896.98     10265994.34      3734994.17     10265893.65
      3734056.66     10265667.95
#Sta/Elev= 30
  4145.7  333.65  4205.2  333.29  4225.3  331.71  4310.7  331.74  4325.9  330.37
  4376.3  329.33  4401.1  330.02  4406.4  328.32  4491.5     327  4678.1  325.58
  4909.5  319.47  4969.9  318.27  4998.3  313.03  5001.8  313.03  5010.2  316.32
  5020.2  317.77  5040.3  317.22  5086.4  319.47  5128.3  318.59  5358.9  319.55
  5492.6  322.47    5558  324.43  5574.9  325.93    5616  325.38  5636.6  326.94
  5683.8  327.15  5801.2  326.06  5851.5  328.89  5873.2  328.47  6018.4  332.02
#Mann= 3 , 0 , 0
  4145.7     .17       0  4909.5     .09       0  5086.4     .17       0
Bank Sta=4909.5,5086.4
XS Rating Curve= 0 ,0
Exp/Cntr=0.3,0.1

Type RM Length L Ch R = 1 ,7534    ,543,543,543
BEGIN DESCRIPTION:
WFSJR 078 15.0
END DESCRIPTION:
XS GIS Cut Line= 3
      3735945.54     10265605.45      3735202.97     10265603.24
      3734042.81     10265563.79
#Sta/Elev= 30
  4112.6  335.14  4150.3  334.81  4410.3  327.41  4470.3  327.02  4531.1   325.2
  4550.3  323.99  4600.3  324.19  4670.3  322.48  4710.3  322.41  4860.3  318.64
  4900.3  317.55  4920.3  317.81  4970.4  316.13  4998.6   313.4  5020.4  315.99
  5190.5  317.92  5200.5  318.79  5220.5  317.91  5340.6   320.4  5357.9  321.48
  5510.7  323.43  5610.7  325.95  5655.1  325.49  5700.8  326.79  5790.8  327.65
  5820.8  326.81  5850.9  327.15  5947.3  330.21  5970.9  329.94    6016  331.15
#Mann= 4 ,-1 , 0
  4112.6     .11       0  4531.1     .17       0  4860.3     .09       0
  5200.5     .17       0
Bank Sta=4860.3,5200.5
XS Rating Curve= 0 ,0
Exp/Cntr=0.3,0.1

Type RM Length L Ch R = 1 ,6991    ,482,482,482
BEGIN DESCRIPTION:
WFSJR 078 14.0
END DESCRIPTION:
XS GIS Cut Line= 3
       3736087.9      10265386.7      3735007.24     10265142.09
       3733476.8     10265053.37
#Sta/Elev= 30
    3892  333.56  3994.6  333.82  4208.3  327.63  4256.6  327.74  4353.4  324.65
  4665.5  319.42  4794.3  315.62  4825.1  315.87  4917.3  313.75    4983  314.63
  4995.4  310.17  5002.2  310.67  5009.4  313.37  5019.4  314.15  5049.5  313.36
  5149.6  315.84  5289.9  317.87    5360  317.25  5440.1  319.09  5460.2  318.37
  5590.4   319.3  5610.4  318.07  5650.5  320.46  5720.8  321.85  5795.4  322.37
  5840.8  324.38  6400.3  332.75  6451.8  334.87  6481.6  334.13    6533  335.53
#Mann= 6 ,-1 , 0
    3892     .11       0  4794.3     .17       0  4825.1     .09       0
  5149.6     .17       0  5720.8     .11       0  6400.3     .17       0
Bank Sta=4825.1,5149.6
XS Rating Curve= 0 ,0
Exp/Cntr=0.3,0.1

Type RM Length L Ch R = 1 ,6509    ,467,467,467
BEGIN DESCRIPTION:
WFSJR 078 13.0
END DESCRIPTION:
XS GIS Cut Line= 3
      3736508.07     10265063.79      3734736.82     10264746.24
      3733414.34     10264754.76
#Sta/Elev= 30
  3550.3   329.2  3713.1  329.68  3977.2  328.38    4089  325.58  4139.8  325.73
  4312.5  322.74    4343  323.41  4546.1  319.72  4637.6  319.51  4739.2  316.64
  4759.5  317.42  4779.4  315.62  4850.9  313.96    4983  311.71  4991.4  309.33
  5009.6  310.89  5084.6  312.88  5122.1  311.87  5155.7  313.26  5226.8  312.55
  5298.5  313.95  5368.8  314.39  5658.8  321.14  5798.8  326.49  6088.8  326.01
  6258.8  329.59  6279.3  331.81  6438.8  335.77  6578.8  336.37  6672.3  338.15
#Mann= 4 ,-1 , 0
  3550.3     .17       0  4850.9     .09       0  5298.5     .17       0
  6279.3     .11       0
Bank Sta=4850.9,5298.5
XS Rating Curve= 0 ,0
Exp/Cntr=0.3,0.1

Type RM Length L Ch R = 1 ,6042    ,444,444,444
BEGIN DESCRIPTION:
WFSJR 078 12.0
END DESCRIPTION:
XS GIS Cut Line= 3
      3736542.79     10264810.31      3734810.14     10264459.62
      3733432.28     10264549.86
#Sta/Elev= 30
    3648  326.85  3734.7  327.48  4018.7  325.51  4285.6  320.91    4323  321.61
  4429.5  319.17  4601.9  317.66  4723.6  313.81  4728.7  315.07  4754.9  315.24
  4897.8  311.83    4959  310.21  4977.1  308.58  4987.9  305.88    5033  310.98
  5129.3  311.14  5203.9   309.6  5281.4  311.97  5346.7  312.29  5367.1  313.96
  5968.9  325.42  6249.9  327.12  6410.2   330.1  6440.3  328.93  6460.3  330.59
  6530.5  330.99  6585.6  333.28  6680.8  333.63  6710.8  335.32  6796.6  335.14
#Mann= 3 ,-1 , 0
    3648     .17       0  4897.8     .09       0  5281.4     .17       0
Bank Sta=4897.8,5281.4
XS Rating Curve= 0 ,0
Exp/Cntr=0.3,0.1

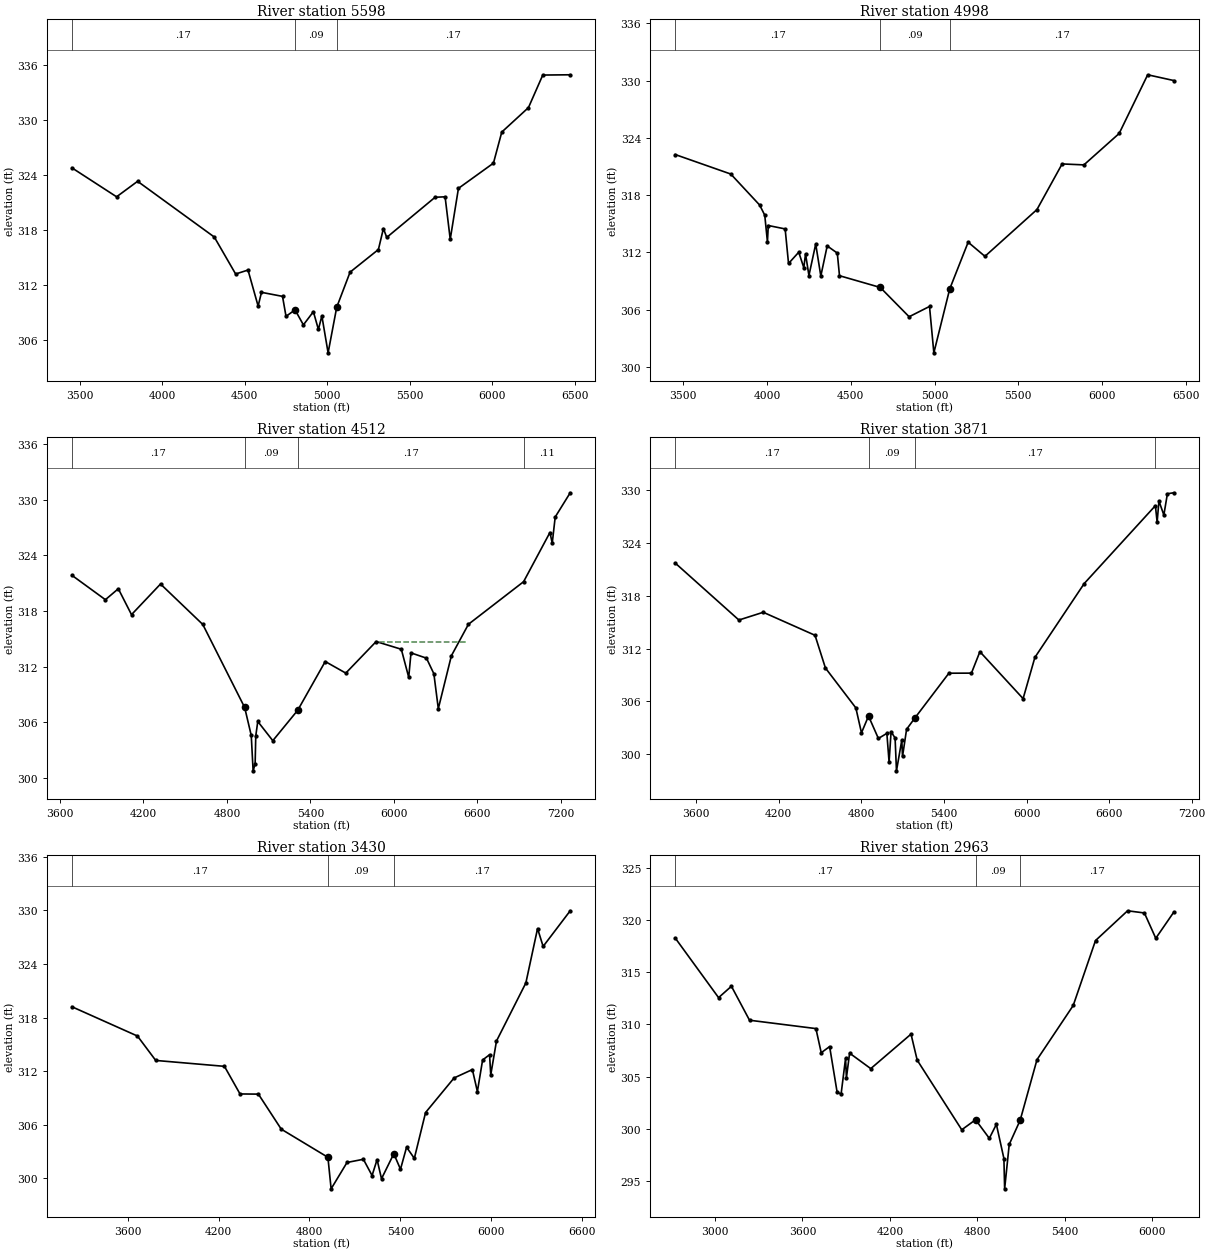
Type RM Length L Ch R = 1 ,5598    ,600,600,600
BEGIN DESCRIPTION:
WFSJR 078 11.0
END DESCRIPTION:
XS GIS Cut Line= 3
       3736633.1     10264456.15      3735383.06      10264199.2
      3733657.36     10263952.67
#Sta/Elev= 30
  3452.9  324.81  3723.7  321.65    3851  323.34  4315.8  317.26    4445  313.23
    4520  313.66  4581.3  309.73  4601.7  311.23  4729.1  310.79  4750.3  308.61
    4805  309.32  4855.6  307.68  4916.2  309.12  4946.5  307.18  4967.5  308.66
  5005.3  304.63  5057.6  309.61  5138.4  313.43  5310.1   315.9  5340.4  318.19
  5360.6  317.22  5653.6   321.6  5714.2  321.65  5745.3  317.02    5795  322.57
  6007.1  325.32  6057.6  328.71  6219.3  331.38    6306  334.93  6472.3  334.96
#Mann= 3 , 0 , 0
  3452.9     .17       0    4805     .09       0  5057.6     .17       0
Bank Sta=4805,5057.6
XS Rating Curve= 0 ,0
Exp/Cntr=0.3,0.1

Type RM Length L Ch R = 1 ,4998    ,486,486,486
BEGIN DESCRIPTION:
WFSJR 078 10.0
END DESCRIPTION:
XS GIS Cut Line= 3
      3736834.46     10264008.23      3735308.27     10263749.29
       3733883.1     10263661.01
#Sta/Elev= 30
    3452  322.24  3783.3   320.2  3955.7  316.95  3986.1  315.89  4002.1   313.1
  4007.2  314.81  4107.9  314.45  4128.1  310.83    4189  312.01  4219.4  310.39
  4229.6  311.84  4249.9  309.57  4290.4  312.87  4320.9  309.52    4359  312.67
  4419.3  311.92  4432.4  309.55  4675.9  308.32  4848.3  305.25    4970  306.33
  4995.9  301.47  5090.6  308.16  5200.8  313.06    5301  311.58  5611.6  316.48
  5761.9  321.26  5892.1  321.16  6102.5  324.45  6272.9   330.6  6427.9     330
#Mann= 3 , 0 , 0
    3452     .17       0  4675.9     .09       0  5090.6     .17       0
Bank Sta=4675.9,5090.6
XS Rating Curve= 0 ,0
Exp/Cntr=0.3,0.1

Type RM Length L Ch R = 1 ,4512    ,641,641,641
BEGIN DESCRIPTION:
WFSJR 078 9.0
END DESCRIPTION:
XS GIS Cut Line= 3
      3736858.73     10263851.97      3735598.52     10263479.14
      3733466.42     10262706.16
#Sta/Elev= 30
  3685.8  321.84  3926.6  319.21  4019.5  320.39  4114.3   317.6  4322.9   320.9
  4626.8  316.54  4927.7   307.6  4975.1  304.58  4988.5  300.77    5003  301.52
  5007.5  304.53    5022  306.09    5130  304.02  5309.2   307.3  5506.9  312.55
  5654.7   311.3  5872.9   314.7  6053.8  313.87    6107  310.85  6123.4  313.48
  6234.6  312.91  6287.8  311.23  6319.7  307.47  6413.7  313.17  6536.2  316.56
  6932.8  321.15  7122.1  326.45  7138.7  325.31    7160  328.12  7267.9  330.73
#Mann= 4 ,-1 , 0
  3685.8     .17       0  4927.7     .09       0  5309.2     .17       0
  6932.8     .11       0
#XS Ineff= 1 ,-1
  5894.4    6530  314.62
Permanent Ineff=
       F
Bank Sta=4927.7,5309.2
XS Rating Curve= 0 ,0
Exp/Cntr=0.3,0.1

Type RM Length L Ch R = 1 ,3871    ,441,441,441
BEGIN DESCRIPTION:
WFSJR 078 8.0
END DESCRIPTION:
XS GIS Cut Line= 3
      3736872.62     10263806.82      3736063.72     10263122.57
      3733563.59     10262570.72
#Sta/Elev= 30
    3449  321.68  3910.9  315.23  4087.7  316.11  4463.8   313.5  4539.4  309.79
  4760.3  305.27  4801.2  302.44  4852.4  304.34  4924.1   301.8  4985.6  302.38
  5001.8  299.12  5016.3  302.57  5045.4  301.85  5055.5  298.13  5094.2  301.62
  5099.4  299.76  5128.9  302.84  5186.7  304.07  5436.2   309.2    5600  309.21
  5661.5  311.64  5975.3  306.32  6060.8  310.99  6419.3  319.37  6936.3   328.2
  6948.9  326.34    6962  328.73  6997.7  327.14  7023.5  329.55  7068.8  329.66
#Mann= 4 ,-1 , 0
    3449     .17       0  4852.4     .09       0  5186.7     .17       0
  6936.3     .11       0
Bank Sta=4852.4,5186.7
XS Rating Curve= 0 ,0
Exp/Cntr=0.3,0.1

Type RM Length L Ch R = 1 ,3430    ,467,467,467
BEGIN DESCRIPTION:
WFSJR 078 7.0
END DESCRIPTION:
XS GIS Cut Line= 3
      3736917.78     10263772.12      3736237.22     10262994.34
       3734192.5     10262039.67
#Sta/Elev= 30
  3231.4  319.22  3664.4  315.94  3784.9  313.21  4238.6  312.55  4341.4  309.46
  4462.8  309.44  4613.6  305.52  4921.7  302.37  4942.9  298.84  5047.8  301.79
  5155.8  302.15  5213.3  300.33  5246.4  302.11  5275.6  299.97  5356.8  302.77
  5400.9  301.03  5441.1   303.5  5492.3  302.25  5566.5  307.38  5754.8  311.25
  5875.5  312.19  5908.6  309.73  5943.1  313.26  5988.9  313.85  5996.9   311.6
  6034.6  315.38  6228.6  321.88  6305.9  327.97  6342.7  325.97  6521.5  329.96
#Mann= 3 , 0 , 0
  3231.4     .17       0  4921.7     .09       0  5356.8     .17       0
Bank Sta=4921.7,5356.8
XS Rating Curve= 0 ,0
Exp/Cntr=0.3,0.1

Type RM Length L Ch R = 1 ,2963    ,469,469,469
BEGIN DESCRIPTION:
WFSJR 078 6.0
END DESCRIPTION:
XS GIS Cut Line= 3
      3737587.94     10263522.13      3735598.33      10262261.7
      3734603.28      10261885.9
#Sta/Elev= 30
  2727.9  318.24  3024.7  312.55  3112.8  313.64    3237  310.39  3692.5  309.59
  3728.9  307.28  3786.6  307.87  3838.3  303.48  3865.4  303.34  3895.9  306.74
  3901.8  304.88  3923.6  307.24  4068.8  305.76    4345  309.06  4387.4  306.57
  4693.1  299.91  4787.8  300.87  4882.3  299.09  4930.6  300.43  4982.3  297.16
  4987.3  294.26  5018.8  298.51    5094  300.83  5209.4  306.62  5457.8   311.8
  5610.7  318.01  5830.8  320.86  5946.2  320.65  6024.3  318.23  6146.8  320.71
#Mann= 3 , 0 , 0
  2727.9     .17       0  4787.8     .09       0    5094     .17       0
Bank Sta=4787.8,5094
XS Rating Curve= 0 ,0
Exp/Cntr=0.3,0.1

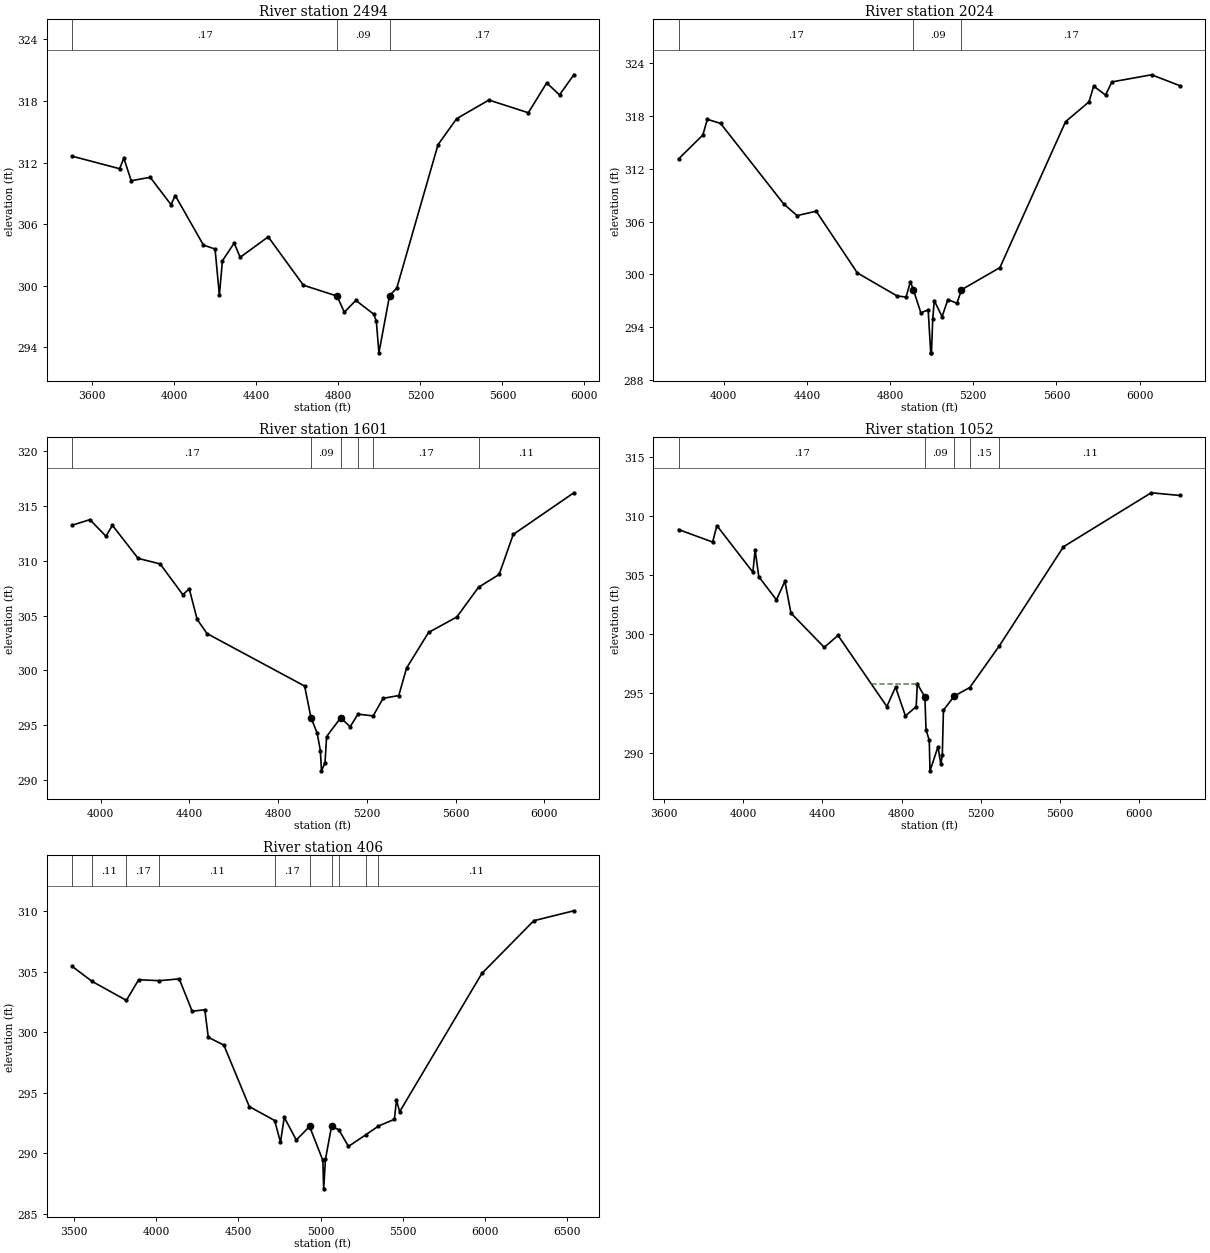
Type RM Length L Ch R = 1 ,2494    ,470,470,470
BEGIN DESCRIPTION:
WFSJR 078 5.0
END DESCRIPTION:
XS GIS Cut Line= 4
      3737098.36      10263001.3      3736334.45     10262473.51
      3735813.61     10261786.01      3735202.71      10261546.5
#Sta/Elev= 30
  3501.4  312.63    3733  311.41    3754  312.43  3789.9  310.24  3882.5  310.57
  3983.9  307.91  4004.8  308.79    4142  303.97  4198.8  303.58  4219.8  299.09
  4234.6  302.44  4292.1  304.16  4321.2  302.78  4458.1  304.77  4629.4  300.06
  4793.7     299  4829.1  297.43  4885.3  298.58  4972.4  297.24  4985.1  296.57
  4997.9  293.47  5049.6  299.03  5085.3   299.8  5286.1  313.75  5376.8  316.28
  5534.2   318.1  5726.7  316.86  5816.2  319.77  5878.6   318.6  5948.6  320.56
#Mann= 3 , 0 , 0
  3501.4     .17       0  4793.7     .09       0  5049.6     .17       0
#XS Ineff= 1 ,-1
    4090  4458.1  304.77
Permanent Ineff=
       F
Bank Sta=4793.7,5049.6
XS Rating Curve= 0 ,0
Exp/Cntr=0.3,0.1

Type RM Length L Ch R = 1 ,2024    ,423,423,423
BEGIN DESCRIPTION:
WFSJR 078 4.0
END DESCRIPTION:
XS GIS Cut Line= 3
      3737199.03     10262845.03      3736391.68     10261933.05
      3735342.15     10261359.34
#Sta/Elev= 30
    3782  313.11  3898.9  315.83  3920.6  317.61  3984.2  317.15  4288.6  307.99
  4352.2  306.68  4444.2  307.18  4642.4  300.17    4834  297.55  4876.6  297.44
  4897.5  299.17  4911.8  298.26  4947.8  295.64  4982.9  295.98  4995.3   291.1
  4998.8   291.1    5005  294.97  5012.3  297.03  5049.9  295.21  5077.8  297.15
  5121.4  296.72  5143.2  298.26  5328.2  300.78  5644.1  317.35  5756.5  319.59
  5779.3  321.38  5836.3  320.37  5867.1  321.86  6057.8  322.67  6196.1  321.41
#Mann= 3 , 0 , 0
    3782     .17       0  4911.8     .09       0  5143.2     .17       0
Bank Sta=4911.8,5143.2
XS Rating Curve= 0 ,0
Exp/Cntr=0.3,0.1

Type RM Length L Ch R = 1 ,1601    ,549,549,549
BEGIN DESCRIPTION:
WFSJR 078 3.0
END DESCRIPTION:
XS GIS Cut Line= 3
      3737306.64     10262723.47      3736735.16     10261847.48
      3735887.79     10260974.81
#Sta/Elev= 30
  3870.9  313.24  3951.2  313.75  4023.6  312.24  4052.9  313.23  4168.5  310.22
    4268  309.71  4370.6   306.9  4399.1  307.45  4434.9  304.65  4479.3  303.36
  4919.5  298.57  4947.8   295.7    4976  294.28  4990.2  292.69  4995.4  290.84
  5011.3  291.58  5018.5  293.97    5082  295.68  5124.5  294.86    5160  296.01
  5228.2  295.85  5273.1  297.45  5343.9  297.71  5379.1  300.22  5478.1  303.46
  5605.5  304.87  5703.3  307.58  5796.3  308.75  5859.9   312.4  6133.2   316.2
#Mann= 6 ,-1 , 0
  3870.9     .17       0  4947.8     .09       0    5082     .17       0
    5160     .15       0  5228.2     .17       0  5703.3     .11       0
Bank Sta=4947.8,5082
XS Rating Curve= 0 ,0
Exp/Cntr=0.3,0.1

Type RM Length L Ch R = 1 ,1052    ,646,646,646
BEGIN DESCRIPTION:
WFSJR 078 2.0
END DESCRIPTION:
XS GIS Cut Line= 4
      3737431.68     10262671.45      3737056.43     10261714.26
      3736761.53     10261157.53      3736051.25     10260641.28
#Sta/Elev= 30
  3672.8  308.87  3845.1  307.81  3866.6   309.2  4048.5  305.26  4059.9  307.15
  4078.3  304.88  4167.7  302.92  4210.3  304.49    4241   301.8  4409.2   298.9
  4478.8  299.91  4725.7  293.89  4769.7  295.54  4819.4   293.1    4874  293.88
  4879.7  295.81    4918   294.7  4923.7  291.93    4940  291.03  4943.8  288.45
    4984  290.48  4998.8  289.01    5006  289.79  5011.7  293.58  5066.4  294.78
  5144.8   295.5  5292.4  298.98  5618.1  307.41  6061.7  311.98    6209  311.75
#Mann= 5 ,-1 , 0
  3672.8     .17       0    4918     .09       0  5066.4     .17       0
  5144.8     .15       0  5292.4     .11       0
#XS Ineff= 1 ,-1
    4650  4879.7  295.81
Permanent Ineff=
       F
Bank Sta=4918,5066.4
XS Rating Curve= 0 ,0
Exp/Cntr=0.3,0.1

Type RM Length L Ch R = 1 ,406     ,0,0,0
BEGIN DESCRIPTION:
WFSJR 078 1.0
END DESCRIPTION:
XS GIS Cut Line= 4
      3738070.56      10262612.4      3737719.86     10261716.56
      3737306.67      10260987.4       3736141.2     10260533.16
#Sta/Elev= 30
  3489.2  305.44    3610   304.2  3819.5  302.62  3893.9  304.33    4020  304.25
  4140.8   304.4  4219.5  301.72  4296.1  301.85  4317.5  299.57  4412.2  298.92
  4566.8  293.84  4720.9  292.69  4756.4  290.89  4779.4  292.95  4852.5  291.08
  4933.3   292.2  5014.1  289.39  5018.9  287.04  5029.9  289.48  5066.7   292.2
  5110.7  291.93  5169.9  290.55  5276.3  291.52  5352.1  292.23  5449.1  292.79
  5461.7   294.4  5480.8  293.41  5980.9  304.85  6296.9  309.21  6540.2  310.03
#Mann= 10 ,-1 , 0
  3489.2     .17       0    3610     .11       0  3819.5     .17       0
    4020     .11       0  4720.9     .17       0  4933.3     .09       0
  5066.7     .17       0  5110.7     .11       0  5276.3     .17       0
  5352.1     .11       0
Bank Sta=4933.3,5066.7
XS Rating Curve= 0 ,0
Exp/Cntr=0.3,0.1

Chan Stop Cuts=-1
Use User Specified Reach Order=0
Composite Channel Slope=5