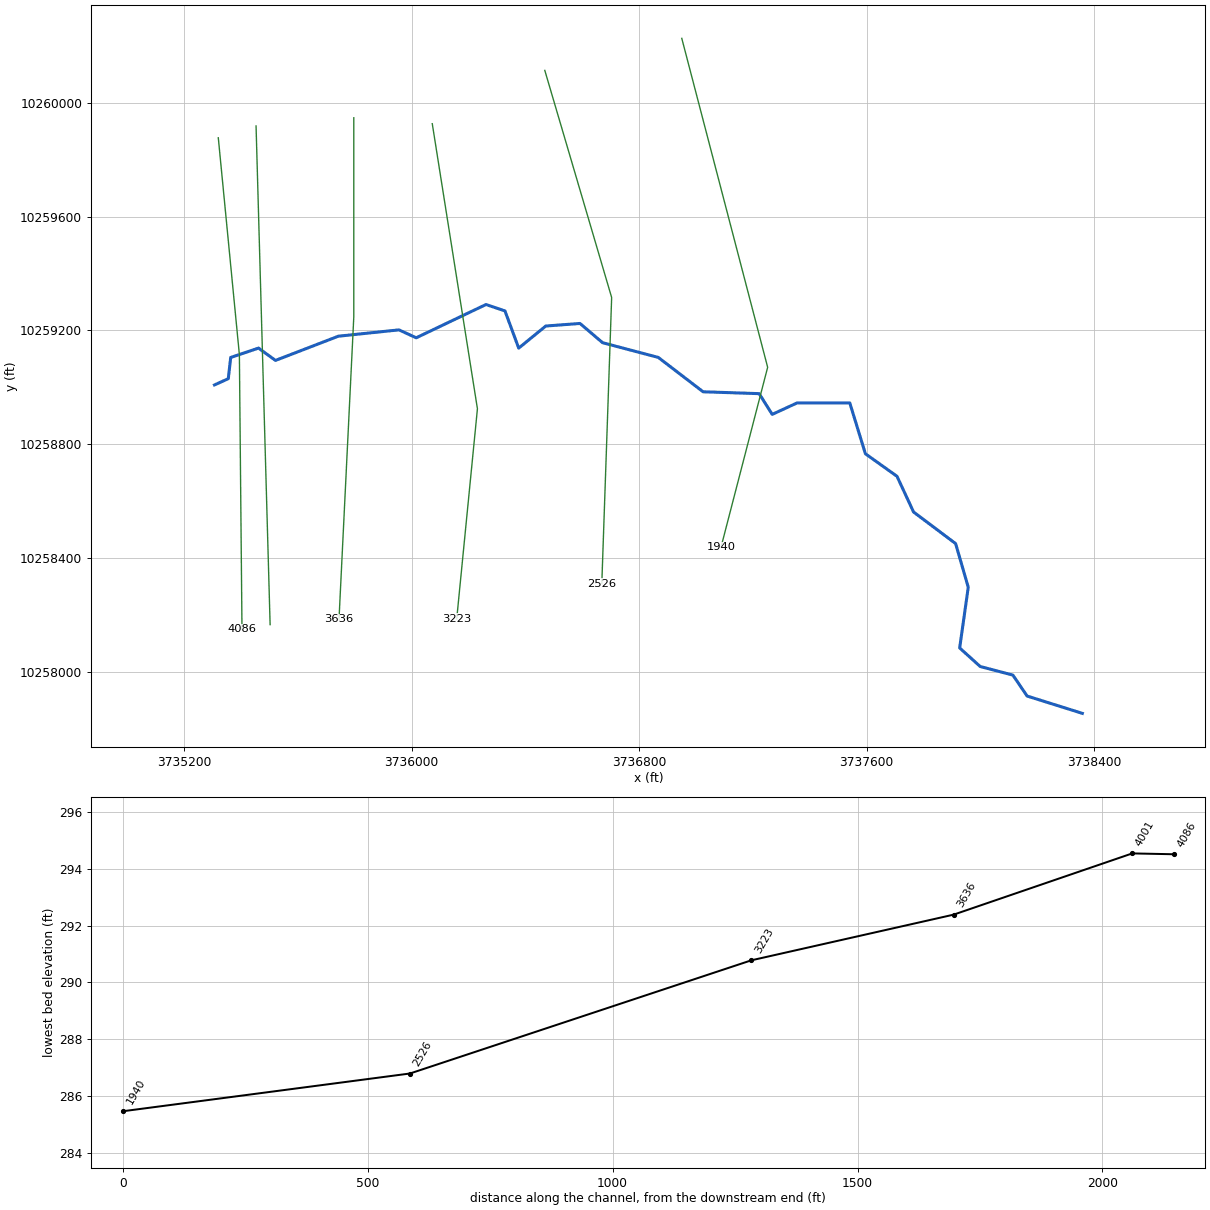
--- WFSJR 079.prj (project) ---

Proj Title=WFSJR 079 Base Level Engineering
Current Plan=p01
Default Exp/Contr=0.3,0.1
English Units
Geom File=g01
Flow File=f01
Plan File=p01
Y Axis Title=Elevation
X Axis Title(PF)=Main Channel Distance
X Axis Title(XS)=Station
BEGIN DESCRIPTION:
WFSJR 079
END DESCRIPTION:
DSS Export Rating Curves= 0
DSS Export Rating Curve Sorted= 0
DSS Export Volume Flow Curves= 0
DXF OffsetX= 0
DXF OffsetY= 0
DXF ScaleX= 1
DXF ScaleY= 10

--- WFSJR 079.p01 (plan) ---

Plan Title=Multiple Run
Program Version=4.10
Short Identifier=Multiple
Geom File=g01
Flow File=f01
Subcritical Flow
K Sum by GR= 0
Std Step Tol= 0.01
Critical Tol= 0.01
Num of Std Step Trials= 20
Max Error Tol= 0.3
Flow Tol Ratio= 0.001
Split Flow NTrial= 30
Split Flow Tol= 0.02
Split Flow Ratio= 0.02
Log Output Level= 0
Friction Slope Method= 1
Unsteady Friction Slope Method= 2
Unsteady Bridges Friction Slope Method= 1
Parabolic Critical Depth
Global Vel Dist= 1 , 1 , 1
Global Log Level= 0
CheckData=True
Encroach Param=-1 ,0,0, 0
BEGIN DESCRIPTION:
Multiple Run
END DESCRIPTION:
Computation Interval=1HOUR
Output Interval=1HOUR
Run HTab= 0
Run UNet= 0
Run PostProcess= 0
Run WQNet= 0
UNET Theta= 1
UNET Theta Warmup= 1
UNET ZTol= 0.02
UNET ZSATol= 0.05
UNET MxIter= 20
UNET MaxInSteps= 0
UNET DtIC= 0
UNET DtMin= 0
UNET MaxCRTS= 20
UNET WFStab= 2
UNET SFStab= 1
UNET WFX= 1
UNET SFX= 1
UNET DSS MLevel= 4
UNET DZMax Abort= 100
UNET Convert EG Bridges= 0
UNET Use Existing IB Tables=-1
UNET Froude Reduction=False
UNET Froude Limit= 1
UNET Froude Power= 10
UNET Time Slicing=0,0, 5
UNET Junction Losses=0
Instantaneous Interval=1HOUR
Write IC File= 0
Write IC File at Sim End=0
Echo Input=False
Echo Parameters=False
Echo Output=False
Write Detailed= 0
WQ AD Non Conservative
WQ ULTIMATE=-1
WQ Max Comp Step=1HOUR
WQ Output Interval=15MIN
WQ Output Selected Increments= 0
WQ Output face flow=0
WQ Output face velocity=0
WQ Output face area=0
WQ Output face dispersion=0
WQ Output cell volume=0
WQ Output cell surface area=0
WQ Output cell continuity=0
WQ Output cumulative cell continuity=0
WQ Output face conc=0
WQ Output face dconc_dx=0
WQ Output face courant=0
WQ Output face peclet=0
WQ Output face adv mass=0
WQ Output face disp mass=0
WQ Output cell mass=0
WQ Output cell source sink temp=0
WQ Output cell source sink nsm=0
WQ Output MaxMinRange=-1
WQ Daily Max Min Mean=-1
WQ Daily Range=0
WQ Daily Time=0
WQ Create Restart=0
WQ Fixed Restart=0
WQ System Summary=0
WQ Use Fixed Temperature=0
Sorting and Armoring Iterations= 10
XS Update Threshold= 0.02
Hydraulics Update Threshold= 0.02
Energy Slope Method= 1
Volume Change Method= 0
XS Weighting Method= 0
Number of US Weighted Cross Sections= 1
Number of DS Weighted Cross Sections= 1
Upstream XS Weight=0.25
Main XS Weight=0.5
Downstream XS Weight=0.25
Number of DS XS's Weighted with US Boundary= 1
Upstream Boundary Weight= 1
Weight of XSs Associated with US Boundary= 0
Number of US XS's Weighted with DS Boundary= 1
Downstream Boundary Weight= 0.5
Weight of XSs Associated with DS Boundary= 0.5
Sediment Output Level= 4
Mass or Volume Output= 0
Output Increment Type= 1
Profile and TS Output Increment= 10
XS Output Flag= 0
XS Output Increment= 10
Disregard all LS=0
Disregard all Conn=0
Disregard all Breaches=0
Disregard all Pumps=0

--- WFSJR 079.f01 (steady flow) ---

Flow Title=Multiple
Program Version=4.10
Number of Profiles= 7
Profile Names=10-year,25-year,50-year,1pct_min,100-year,1pct_plu,500-year
River Rch & RM=WFSJR 079,Reach-1         ,4086
     193     240     306     128     387    1169     643
River Rch & RM=WFSJR 079,Reach-1         ,3223
     331     426     557     239     723    2183    1257
Boundary for River Rch & Prof#=WFSJR 079,Reach-1         , 1
Up Type= 0
Dn Type= 3
Dn Slope=0.006
Boundary for River Rch & Prof#=WFSJR 079,Reach-1         , 2
Up Type= 0
Dn Type= 3
Dn Slope=0.006
Boundary for River Rch & Prof#=WFSJR 079,Reach-1         , 3
Up Type= 0
Dn Type= 3
Dn Slope=0.006
Boundary for River Rch & Prof#=WFSJR 079,Reach-1         , 4
Up Type= 0
Dn Type= 3
Dn Slope=0.006
Boundary for River Rch & Prof#=WFSJR 079,Reach-1         , 5
Up Type= 0
Dn Type= 3
Dn Slope=0.006
Boundary for River Rch & Prof#=WFSJR 079,Reach-1         , 6
Up Type= 0
Dn Type= 3
Dn Slope=0.006
Boundary for River Rch & Prof#=WFSJR 079,Reach-1         , 7
Up Type= 0
Dn Type= 3
Dn Slope=0.006
DSS Import GetInterval= 0
DSS Import GetPeak= 0
DSS Import FillOption= 0

--- WFSJR 079.g01 (geometry) ---

Geom Title=Existing Conditions
Program Version=4.10

River Reach=WFSJR 079       ,Reach-1
Reach XY= 30
      3735306.34     10259008.31      3735354.96     10259030.35
      3735363.38      10259104.9      3735461.27     10259137.96
       3735520.9     10259094.53      3735742.05     10259179.76
      3735955.24     10259201.98        3736016.      10259174.2
      3736261.49     10259291.22      3736328.16     10259268.65
      3736376.42     10259137.75      3736471.56     10259215.52
      3736592.05     10259224.55      3736671.56     10259156.84
      3736867.39     10259105.11      3737025.03     10258984.27
      3737222.25     10258977.68      3737268.09     10258904.76
      3737355.59     10258945.04        3737541.     10258945.04
      3737595.87     10258766.22      3737706.98     10258687.05
      3737765.31     10258561.36      3737913.23     10258450.25
      3737957.67     10258296.77      3737927.46     10258083.23
      3737999.69     10258017.95      3738114.62     10257987.75
      3738164.62     10257914.13      3738359.01     10257853.09

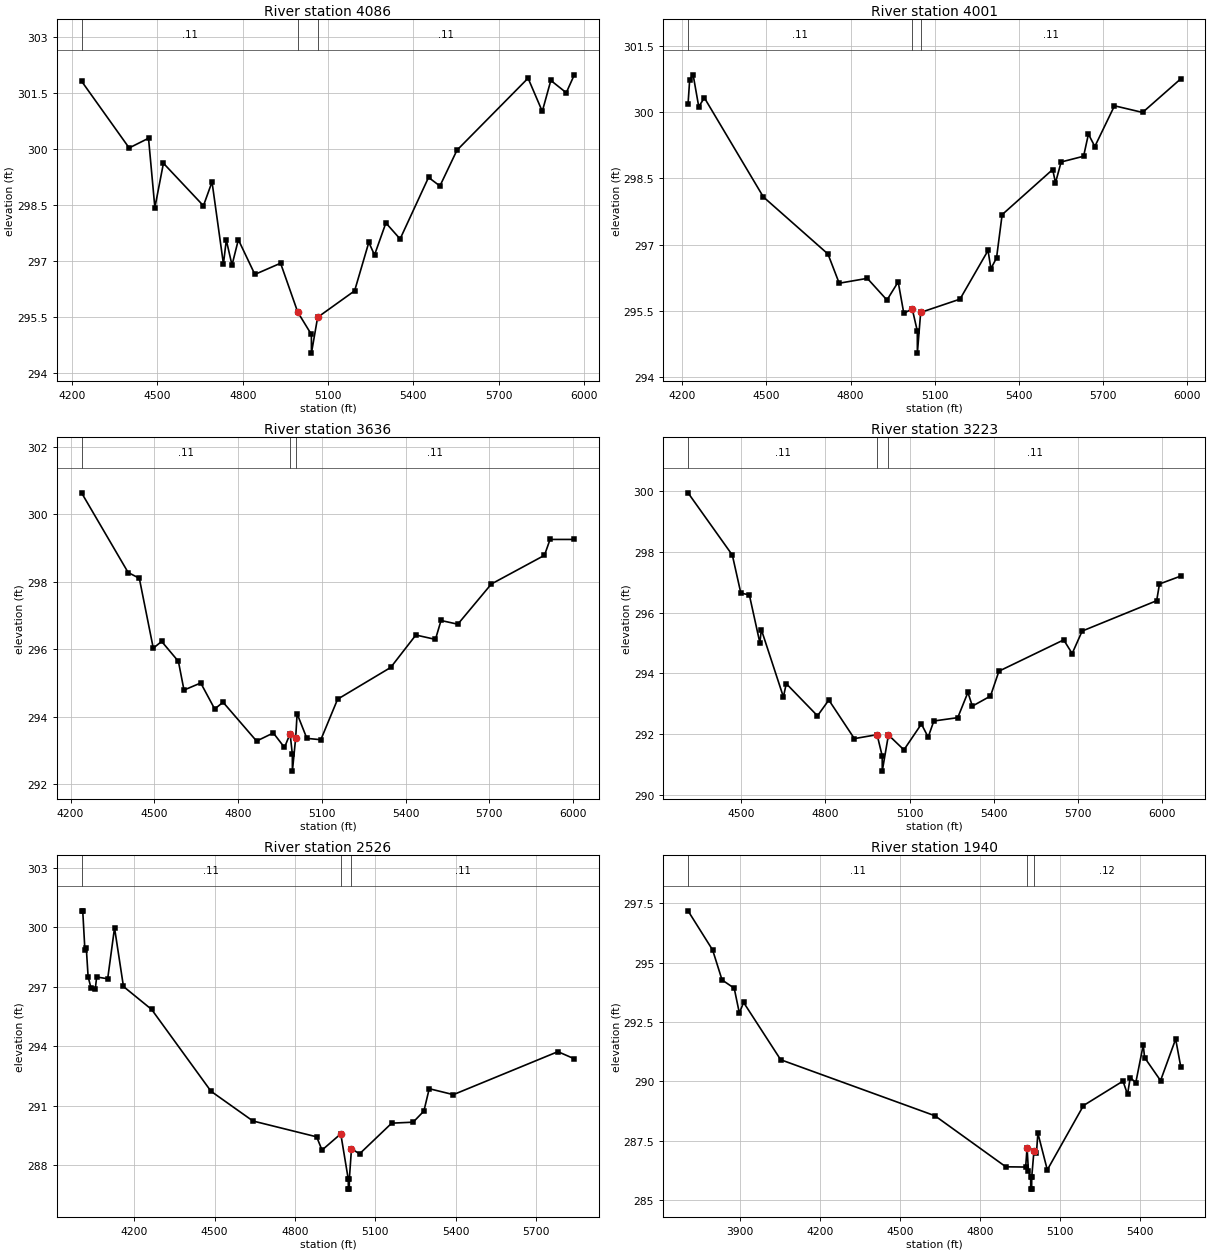
Type RM Length L Ch R = 1 ,4086    ,85,85,85
BEGIN DESCRIPTION:
WFSJR 079 4.0
END DESCRIPTION:
XS GIS Cut Line= 3
      3735319.79     10259877.67      3735393.96     10259114.57
      3735403.13     10258148.51
#Sta/Elev= 30
  4233.3  301.81  4400.7  300.02  4468.8  300.28  4491.1  298.42  4521.2  299.61
  4661.9  298.47  4692.1  299.11  4732.2  296.91  4742.3  297.55  4762.4  296.88
  4784.7  297.56  4842.8  296.63  4933.2  296.93  4993.5  295.62  5041.5  295.02
  5041.7  294.52  5063.5  295.48  5193.5  296.19  5243.5  297.49  5263.5  297.15
  5303.5  298.01  5353.5  297.58  5453.5  299.23  5493.5     299  5553.5  299.96
  5803.5  301.89  5853.5     301  5883.5  301.83  5937.8   301.5  5966.1  301.98
#Mann= 3 , 0 , 0
  4233.3     .11       0  4993.5     .07       0  5063.5     .11       0
Bank Sta=4993.5,5063.5
XS Rating Curve= 0 ,0
Exp/Cntr=0.3,0.1

Type RM Length L Ch R = 1 ,4001    ,365,365,365
BEGIN DESCRIPTION:
WFSJR 079 3.0
END DESCRIPTION:
XS GIS Cut Line= 2
      3735452.61      10259919.3      3735502.06      10258165.1
#Sta/Elev= 30
  4221.3  300.17  4227.2  300.73  4239.5  300.84  4259.5  300.12  4279.6  300.32
  4489.6  298.08  4719.7  296.79  4759.7  296.13  4859.8  296.24  4929.8  295.75
  4969.8  296.16  4989.8  295.45  5019.8  295.55  5037.9  295.05  5038.1  294.55
  5049.9  295.47  5189.9  295.77  5289.8  296.87    5300  296.46    5320   296.7
    5340  297.68    5520   298.7    5530   298.4  5550.1  298.87  5630.1     299
  5647.3   299.5  5670.1  299.22  5740.1  300.14  5840.2  299.99  5976.2  300.75
#Mann= 3 , 0 , 0
  4221.3     .11       0  5019.8     .07       0  5049.9     .11       0
Bank Sta=5019.8,5049.9
XS Rating Curve= 0 ,0
Exp/Cntr=0.3,0.1

Type RM Length L Ch R = 1 ,3636    ,413,413,413
BEGIN DESCRIPTION:
WFSJR 079 2.0
END DESCRIPTION:
XS GIS Cut Line= 3
      3735796.36     10259947.98      3735796.36     10259247.45
      3735744.37     10258184.25
#Sta/Elev= 30
  4239.4  300.63  4406.3  298.27  4446.3   298.1  4496.3  296.03  4526.3  296.23
  4586.3  295.64  4606.3  294.79  4666.3     295  4716.3  294.23  4746.3  294.43
  4866.3  293.28  4926.3  293.52  4966.3  293.09  4986.4   293.5  4994.4  292.89
  4994.6  292.39  5006.4  293.38  5011.5  294.09  5046.4  293.36  5096.5  293.32
  5156.6  294.52  5346.8  295.46  5436.9  296.42    5507  296.29    5527  296.85
  5587.1  296.74  5707.2  297.93  5897.5  298.78  5917.5  299.25  6004.4  299.25
#Mann= 3 , 0 , 0
  4239.4     .11       0  4986.4     .07       0  5006.4     .11       0
Bank Sta=4986.4,5006.4
XS Rating Curve= 0 ,0
Exp/Cntr=0.3,0.1

Type RM Length L Ch R = 1 ,3223    ,697,697,697
BEGIN DESCRIPTION:
Mapping XS 50c3663b
END DESCRIPTION:
XS GIS Cut Line= 3
      3736072.39     10259927.18      3736231.25     10258924.53
      3736158.39     10258185.47
#Sta/Elev= 30
  4309.8  299.94  4467.9  297.89  4498.2  296.64  4528.6  296.58  4566.2     295
  4571.3  295.44  4650.1  293.22  4660.2  293.66  4771.6   292.6  4812.1  293.12
  4903.2  291.85  4984.2  291.98  5002.5  291.28  5002.7  290.78  5024.7  291.97
    5080  291.48  5142.3  292.33  5166.5   291.9  5186.7  292.43    5272  292.54
  5308.2  293.37  5324.2  292.92  5388.7  293.25  5418.9  294.07    5650   295.1
  5680.1  294.65  5715.8  295.39  5981.6  296.39  5991.6  296.94  6067.6   297.2
#Mann= 3 , 0 , 0
  4309.8     .11       0  4984.2     .07       0  5024.7     .11       0
Bank Sta=4984.2,5024.7
XS Rating Curve= 0 ,0
Exp/Cntr=0.3,0.1

Type RM Length L Ch R = 1 ,2526    ,586,586,586
BEGIN DESCRIPTION:
Mapping XS 170b1a61
END DESCRIPTION:
XS GIS Cut Line= 3
      3736468.24     10260114.62      3736703.37     10259315.94
      3736668.75      10258309.9
#Sta/Elev= 30
  4003.4  300.84  4007.8  300.84    4016  298.84  4021.2  298.94  4027.9  297.51
  4038.4  296.96  4054.6  296.89  4059.8   297.5  4100.9  297.41  4126.5  299.98
  4159.8  297.02    4265  295.86  4486.6  291.73    4643  290.23  4880.9  289.43
  4900.9  288.76  4970.9  289.58  4998.9  287.29  4999.2  286.79  5002.7  286.79
  5002.9  287.29  5010.9  288.83    5041  288.57    5161  290.12  5241.1  290.17
  5281.1  290.73  5301.1  291.86  5391.2  291.56  5781.4  293.73  5842.6  293.37
#Mann= 3 , 0 , 0
  4003.4     .11       0  4970.9     .07       0  5010.9     .11       0
Bank Sta=4970.9,5010.9
XS Rating Curve= 0 ,0
Exp/Cntr=0.3,0.1

Type RM Length L Ch R = 1 ,1940    ,0,0,0
BEGIN DESCRIPTION:
WFSJR 079 1.0
END DESCRIPTION:
XS GIS Cut Line= 3
      3736950.01     10260227.46      3737252.09     10259070.37
      3737088.02     10258437.56
#Sta/Elev= 30
  3703.9  297.18  3796.3  295.53  3831.6  294.27  3877.3  293.92  3896.5  292.88
  3912.6  293.32  4051.6  290.91  4630.6  288.55  4896.8   286.4  4971.3  286.39
  4976.5  287.21  4981.7  286.22    4990  285.96  4990.3  285.46  4993.8  285.46
    4994  285.96  5002.3  287.06  5011.9     287  5017.1  287.82  5052.5  286.27
  5188.3  288.98  5336.6  290.01  5353.6  289.45  5363.9  290.16  5384.6  289.94
  5412.6  291.53  5417.7     291  5477.6  290.03  5534.3  291.78  5553.5  290.61
#Mann= 3 , 0 , 0
  3703.9     .11       0  4976.5     .06       0  5002.3     .12       0
Bank Sta=4976.5,5002.3
XS Rating Curve= 0 ,0
Exp/Cntr=0.3,0.1

Chan Stop Cuts=-1
Use User Specified Reach Order=0
Composite Channel Slope=5