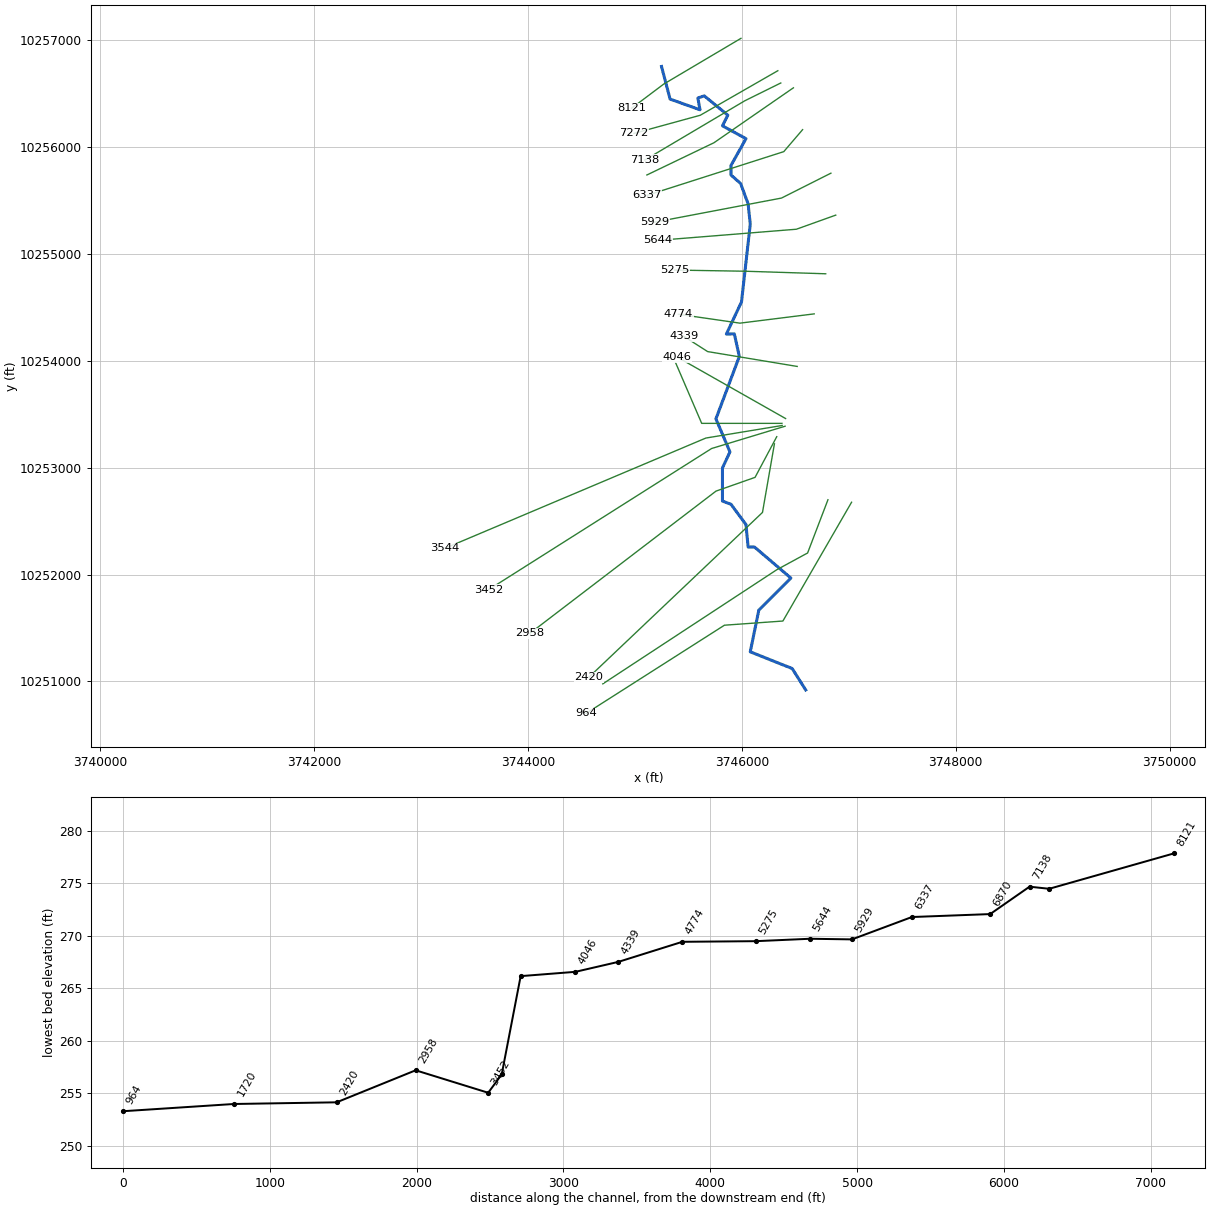
--- WFSJR 080.prj (project) ---

Proj Title=WFSJR 080 Base Level Engineering
Current Plan=p01
Default Exp/Contr=0.3,0.1
English Units
Geom File=g01
Flow File=f01
Plan File=p01
Y Axis Title=Elevation
X Axis Title(PF)=Main Channel Distance
X Axis Title(XS)=Station
BEGIN DESCRIPTION:
WFSJR 080
END DESCRIPTION:
DSS Export Rating Curves= 0
DSS Export Rating Curve Sorted= 0
DSS Export Volume Flow Curves= 0
DXF OffsetX= 0
DXF OffsetY= 0
DXF ScaleX= 1
DXF ScaleY= 10

--- WFSJR 080.p01 (plan) ---

Plan Title=Multiple Run
Program Version=4.10
Short Identifier=Multiple
Geom File=g01
Flow File=f01
Subcritical Flow
K Sum by GR= 0
Std Step Tol= 0.01
Critical Tol= 0.01
Num of Std Step Trials= 20
Max Error Tol= 0.3
Flow Tol Ratio= 0.001
Split Flow NTrial= 30
Split Flow Tol= 0.02
Split Flow Ratio= 0.02
Log Output Level= 0
Friction Slope Method= 1
Unsteady Friction Slope Method= 2
Unsteady Bridges Friction Slope Method= 1
Parabolic Critical Depth
Global Vel Dist= 1 , 1 , 1
Global Log Level= 0
CheckData=True
Encroach Param=-1 ,0,0, 0
BEGIN DESCRIPTION:
Multiple Run
END DESCRIPTION:
Computation Interval=1HOUR
Output Interval=1HOUR
Run HTab= 0
Run UNet= 0
Run PostProcess= 0
Run WQNet= 0
UNET Theta= 1
UNET Theta Warmup= 1
UNET ZTol= 0.02
UNET ZSATol= 0.05
UNET MxIter= 20
UNET MaxInSteps= 0
UNET DtIC= 0
UNET DtMin= 0
UNET MaxCRTS= 20
UNET WFStab= 2
UNET SFStab= 1
UNET WFX= 1
UNET SFX= 1
UNET DSS MLevel= 4
UNET DZMax Abort= 100
UNET Convert EG Bridges= 0
UNET Use Existing IB Tables=-1
UNET Froude Reduction=False
UNET Froude Limit= 1
UNET Froude Power= 10
UNET Time Slicing=0,0, 5
UNET Junction Losses=0
Instantaneous Interval=1HOUR
Write IC File= 0
Write IC File at Sim End=0
Echo Input=False
Echo Parameters=False
Echo Output=False
Write Detailed= 0
WQ AD Non Conservative
WQ ULTIMATE=-1
WQ Max Comp Step=1HOUR
WQ Output Interval=15MIN
WQ Output Selected Increments= 0
WQ Output face flow=0
WQ Output face velocity=0
WQ Output face area=0
WQ Output face dispersion=0
WQ Output cell volume=0
WQ Output cell surface area=0
WQ Output cell continuity=0
WQ Output cumulative cell continuity=0
WQ Output face conc=0
WQ Output face dconc_dx=0
WQ Output face courant=0
WQ Output face peclet=0
WQ Output face adv mass=0
WQ Output face disp mass=0
WQ Output cell mass=0
WQ Output cell source sink temp=0
WQ Output cell source sink nsm=0
WQ Output MaxMinRange=-1
WQ Daily Max Min Mean=-1
WQ Daily Range=0
WQ Daily Time=0
WQ Create Restart=0
WQ Fixed Restart=0
WQ System Summary=0
WQ Use Fixed Temperature=0
Sorting and Armoring Iterations= 10
XS Update Threshold= 0.02
Hydraulics Update Threshold= 0.02
Energy Slope Method= 1
Volume Change Method= 0
XS Weighting Method= 0
Number of US Weighted Cross Sections= 1
Number of DS Weighted Cross Sections= 1
Upstream XS Weight=0.25
Main XS Weight=0.5
Downstream XS Weight=0.25
Number of DS XS's Weighted with US Boundary= 1
Upstream Boundary Weight= 1
Weight of XSs Associated with US Boundary= 0
Number of US XS's Weighted with DS Boundary= 1
Downstream Boundary Weight= 0.5
Weight of XSs Associated with DS Boundary= 0.5
Sediment Output Level= 4
Mass or Volume Output= 0
Output Increment Type= 1
Profile and TS Output Increment= 10
XS Output Flag= 0
XS Output Increment= 10
Disregard all LS=0
Disregard all Conn=0
Disregard all Breaches=0
Disregard all Pumps=0

--- WFSJR 080.f01 (steady flow) ---

Flow Title=Multiple
Program Version=4.10
Number of Profiles= 7
Profile Names=10-year,25-year,50-year,1pct_min,100-year,1pct_plu,500-year
River Rch & RM=WFSJR 080,Reach-1         ,8121
     373     486     638     277     836    2525    1477
River Rch & RM=WFSJR 080,Reach-1         ,7272
     602     805    1078     474    1431    4322    2616
River Rch & RM=WFSJR 080,Reach-1         ,3544
    2685    3842    5384    2467    7450   22499   14771
Boundary for River Rch & Prof#=WFSJR 080,Reach-1         , 1
Up Type= 0
Dn Type= 3
Dn Slope=0.003
Boundary for River Rch & Prof#=WFSJR 080,Reach-1         , 2
Up Type= 0
Dn Type= 3
Dn Slope=0.003
Boundary for River Rch & Prof#=WFSJR 080,Reach-1         , 3
Up Type= 0
Dn Type= 3
Dn Slope=0.003
Boundary for River Rch & Prof#=WFSJR 080,Reach-1         , 4
Up Type= 0
Dn Type= 3
Dn Slope=0.003
Boundary for River Rch & Prof#=WFSJR 080,Reach-1         , 5
Up Type= 0
Dn Type= 3
Dn Slope=0.003
Boundary for River Rch & Prof#=WFSJR 080,Reach-1         , 6
Up Type= 0
Dn Type= 3
Dn Slope=0.003
Boundary for River Rch & Prof#=WFSJR 080,Reach-1         , 7
Up Type= 0
Dn Type= 3
Dn Slope=0.003
DSS Import GetInterval= 0
DSS Import GetPeak= 0
DSS Import FillOption= 0

--- WFSJR 080.g01 (geometry) ---

Geom Title=Existing Conditions
Program Version=4.10

River Reach=WFSJR 080       ,Reach-1
Reach XY= 30
      3745248.23     10256751.84      3745328.23     10256446.84
      3745608.23     10256346.84      3745588.23     10256456.84
      3745648.23     10256476.84      3745868.23     10256296.84
      3745818.23     10256196.84      3746038.23     10256076.84
      3745898.23     10255826.84      3745898.23     10255736.84
      3745988.23     10255656.84      3746058.23     10255466.84
      3746078.23     10255276.84      3745996.26      10254549.7
      3745854.87     10254248.84      3745929.29     10254250.97
      3745976.06     10254039.41      3745757.09     10253455.83
      3745888.23     10253146.84      3745818.23     10252996.84
      3745818.23     10252686.84      3745898.23     10252656.84
      3746038.23     10252466.84      3746058.23     10252256.84
      3746118.23     10252256.84      3746458.23     10251966.84
      3746158.23     10251666.84      3746078.23     10251276.84
      3746470.53     10251120.58      3746596.89     10250919.82

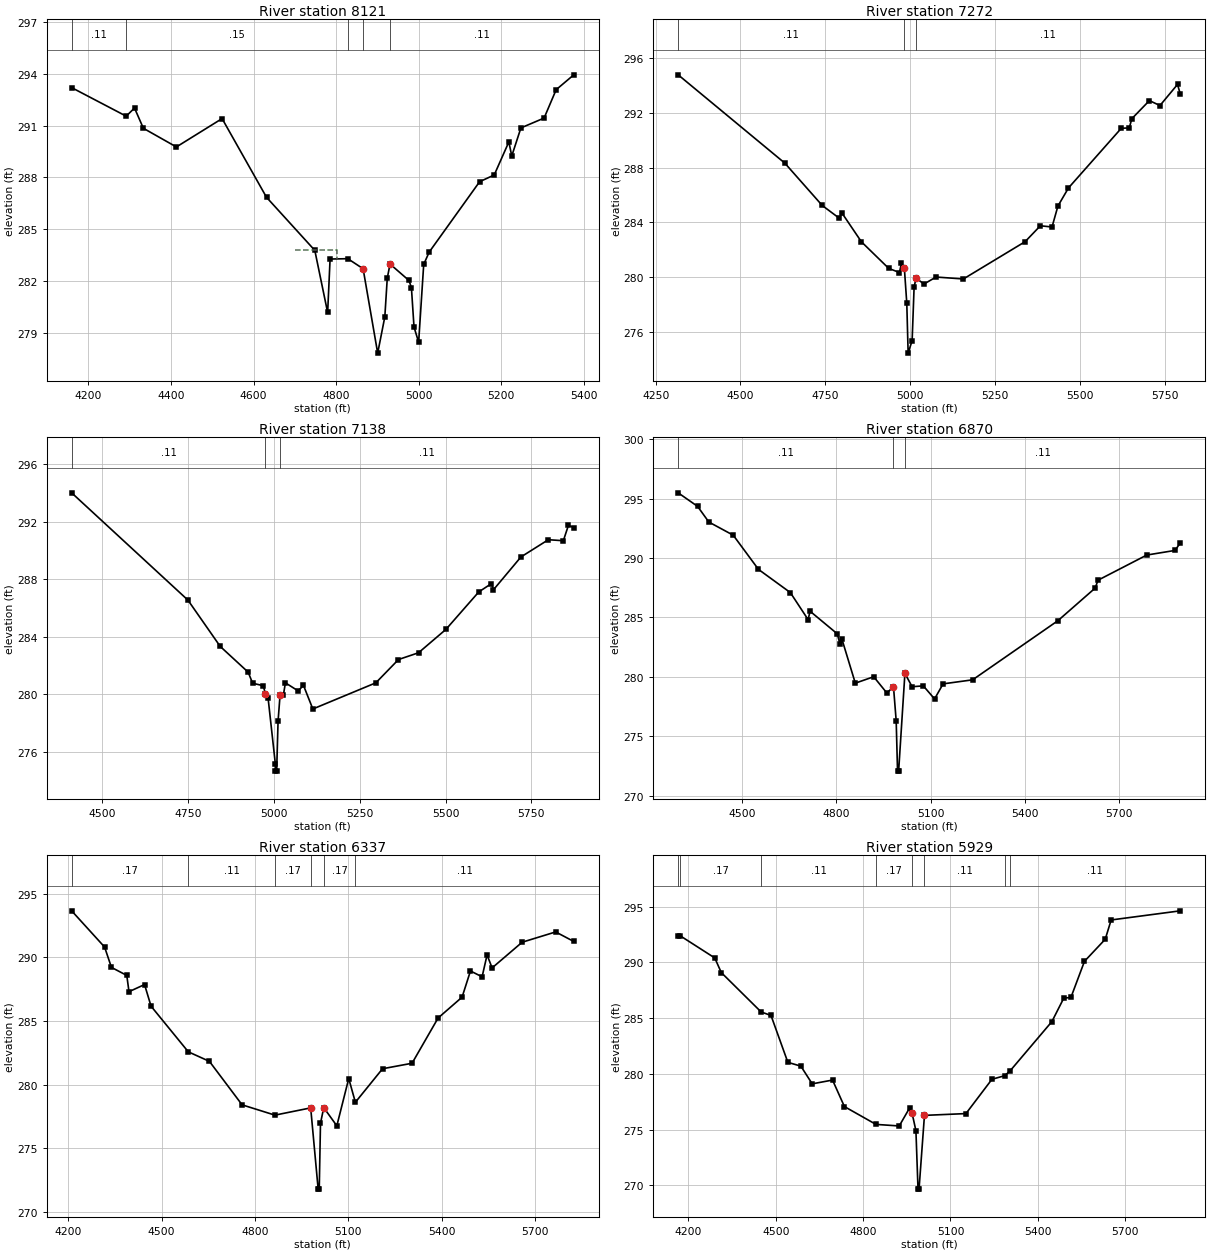
Type RM Length L Ch R = 1 ,8121    ,849,849,849
BEGIN DESCRIPTION:
WFSJR 080 10.0
END DESCRIPTION:
XS GIS Cut Line= 3
       3745991.4     10257015.18      3745268.23     10256586.84
      3744967.83     10256361.05
#Sta/Elev= 30
  4159.5  293.19  4291.6  291.54  4311.8  292.01  4333.2  290.84  4413.2  289.76
  4523.9   291.4  4631.5  286.85  4748.5  283.78  4779.6  280.19  4785.5  283.28
  4828.4   283.3  4865.5  282.72  4900.8  277.84  4918.1  279.94    4924  282.17
  4930.7  282.99  4976.6  282.04  4982.5  281.63  4988.8  279.35    5000  278.47
  5012.3  282.97  5025.5  283.68  5147.7  287.75  5183.1  288.14  5218.5  290.05
  5225.6  289.24  5247.7  290.86  5303.9  291.43  5333.1  293.07  5375.8  293.93
#Mann= 5 ,-1 , 0
  4159.5     .11       0  4291.6     .15       0  4828.4     .11       0
  4865.5     .06       0  4930.7     .11       0
#XS Ineff= 1 ,-1
    4700  4801.2  283.83
Permanent Ineff=
       F
Bank Sta=4865.5,4930.7
XS Rating Curve= 0 ,0
Exp/Cntr=0.3,0.1

Type RM Length L Ch R = 1 ,7272    ,134,134,134
BEGIN DESCRIPTION:
WFSJR 080 9.0
END DESCRIPTION:
XS GIS Cut Line= 3
      3746336.05     10256712.24      3745610.31     10256295.56
      3744989.98     10256125.74
#Sta/Elev= 30
  4316.4  294.77  4630.7  288.33    4741  285.24  4791.8   284.3  4798.6  284.71
  4856.5  282.59    4937  280.65  4968.6  280.35  4974.4  281.03  4983.1  280.66
  4990.2  278.11  4994.2  274.47    5006  275.39  5011.8  279.31  5017.7  279.94
  5040.8  279.51  5076.5  280.02  5157.1  279.88    5339   282.6  5383.9  283.76
  5418.3  283.67  5435.7   285.2  5466.8  286.52  5622.4  290.87    5646   290.9
  5653.5  291.57  5705.3  292.89  5736.4  292.53  5788.2  294.07  5796.4  293.36
#Mann= 3 , 0 , 0
  4316.4     .11       0  4983.1     .06       0  5017.7     .11       0
Bank Sta=4983.1,5017.7
XS Rating Curve= 0 ,0
Exp/Cntr=0.3,0.1

Type RM Length L Ch R = 1 ,7138    ,268,268,268
BEGIN DESCRIPTION:
WFSJR 080 8.0
END DESCRIPTION:
XS GIS Cut Line= 3
      3746363.83     10256597.66      3746026.98     10256430.97
       3745091.7     10255876.73
#Sta/Elev= 30
  4410.4  294.02  4749.2  286.56  4843.3  283.34  4924.7  281.55  4937.7  280.78
  4968.9  280.61  4974.7  280.04  4982.8  279.74  5003.9  275.17  5004.2  274.67
  5007.7  274.67  5011.8  278.14  5017.7  279.98  5027.4  279.97  5033.2  280.81
  5070.2  280.25  5085.9  280.63  5113.1  278.99  5296.7  280.81  5362.7  282.43
  5421.1   282.9  5501.1  284.53  5596.6  287.13  5633.6  287.71  5639.4  287.28
  5719.4  289.56  5799.3  290.76    5843  290.69  5857.8  291.76  5873.4   291.6
#Mann= 3 , 0 , 0
  4410.4     .11       0  4974.7     .06       0  5017.7     .11       0
Bank Sta=4974.7,5017.7
XS Rating Curve= 0 ,0
Exp/Cntr=0.3,0.1

Type RM Length L Ch R = 1 ,6870    ,533,533,533
BEGIN DESCRIPTION:
WFSJR 080 7.0
END DESCRIPTION:
XS GIS Cut Line= 3
      3746481.87     10256552.52      3745738.79     10256038.61
      3745111.56     10255737.13
#Sta/Elev= 30
  4296.1   295.5  4357.9  294.36  4393.8  293.04  4471.5  291.93  4551.9  289.05
  4653.3   287.1    4710  284.82  4716.1  285.53  4802.6  283.63  4811.4  282.78
  4817.5  283.19  4860.3  279.47  4918.9  280.01  4960.8  278.64  4981.9  279.17
  4990.5   276.3  4994.8  272.06  4998.3  272.06  5018.3  280.29  5041.2  279.17
    5077  279.24  5112.8  278.14  5139.9  279.41    5234  279.75  5505.6  284.73
  5624.4  287.48  5633.3  288.14  5788.7  290.26  5878.9  290.65  5895.5  291.29
#Mann= 3 , 0 , 0
  4296.1     .11       0  4981.9     .06       0  5018.3     .11       0
Bank Sta=4981.9,5018.3
XS Rating Curve= 0 ,0
Exp/Cntr=0.3,0.1

Type RM Length L Ch R = 1 ,6337    ,408,408,408
BEGIN DESCRIPTION:
WFSJR 080 6.0
END DESCRIPTION:
XS GIS Cut Line= 3
      3746567.84     10256161.06      3746391.56     10255955.28
      3745112.43     10255546.23
#Sta/Elev= 30
  4211.1  293.67    4317  290.82    4339  289.22  4388.3  288.59  4395.4  287.31
  4445.4  287.87  4466.3  286.17    4586  282.58  4653.9  281.83  4758.9  278.41
  4864.5   277.6  4979.4  278.17  5003.4  271.78  5006.9  271.78  5010.9  276.96
  5021.4  278.19  5063.4  276.76  5101.7  280.48    5123  278.61  5210.4  281.25
  5305.2  281.68  5388.9  285.24    5466  286.88  5492.9  288.94  5530.3  288.48
  5546.3   290.2  5562.5  289.18    5659   291.2  5766.8  292.01    5825  291.26
#Mann= 6 ,-1 , 0
  4211.1     .17       0    4586     .11       0  4864.5     .17       0
  4979.4     .09       0  5021.4     .17       0    5123     .11       0
#XS Ineff= 1 ,-1
  5101.7    5200  280.48
Permanent Ineff=
       F
Bank Sta=4979.4,5021.4
XS Rating Curve= 0 ,0
Exp/Cntr=0.3,0.1

Type RM Length L Ch R = 1 ,5929    ,285,285,285
BEGIN DESCRIPTION:
WFSJR 080 5.0
END DESCRIPTION:
XS GIS Cut Line= 3
      3746832.55     10255753.89      3746370.73     10255521.25
      3745184.57     10255295.81
#Sta/Elev= 30
  4164.8  292.37  4172.3  292.38  4290.5   290.4  4312.8  289.09  4449.8  285.55
  4483.6  285.24  4541.5  281.03  4586.1  280.69  4625.1   279.1    4695  279.44
  4735.7  277.06  4844.1  275.46    4924  275.32  4959.7  276.94  4968.3  276.45
  4981.3  274.89  4988.5  269.65    4992  269.65  5010.6  276.27  5153.1  276.43
  5242.4  279.51  5285.9  279.83  5303.6  280.23  5448.3  284.69    5489  286.79
  5513.7  286.86  5560.2   290.1  5631.5  292.08  5651.8  293.81  5889.3  294.63
#Mann= 8 ,-1 , 0
  4164.8     .11       0  4172.3     .17       0  4449.8     .11       0
  4844.1     .17       0  4968.3     .07       0  5010.6     .11       0
  5285.9     .17       0  5303.6     .11       0
Bank Sta=4968.3,5010.6
XS Rating Curve= 0 ,0
Exp/Cntr=0.3,0.1

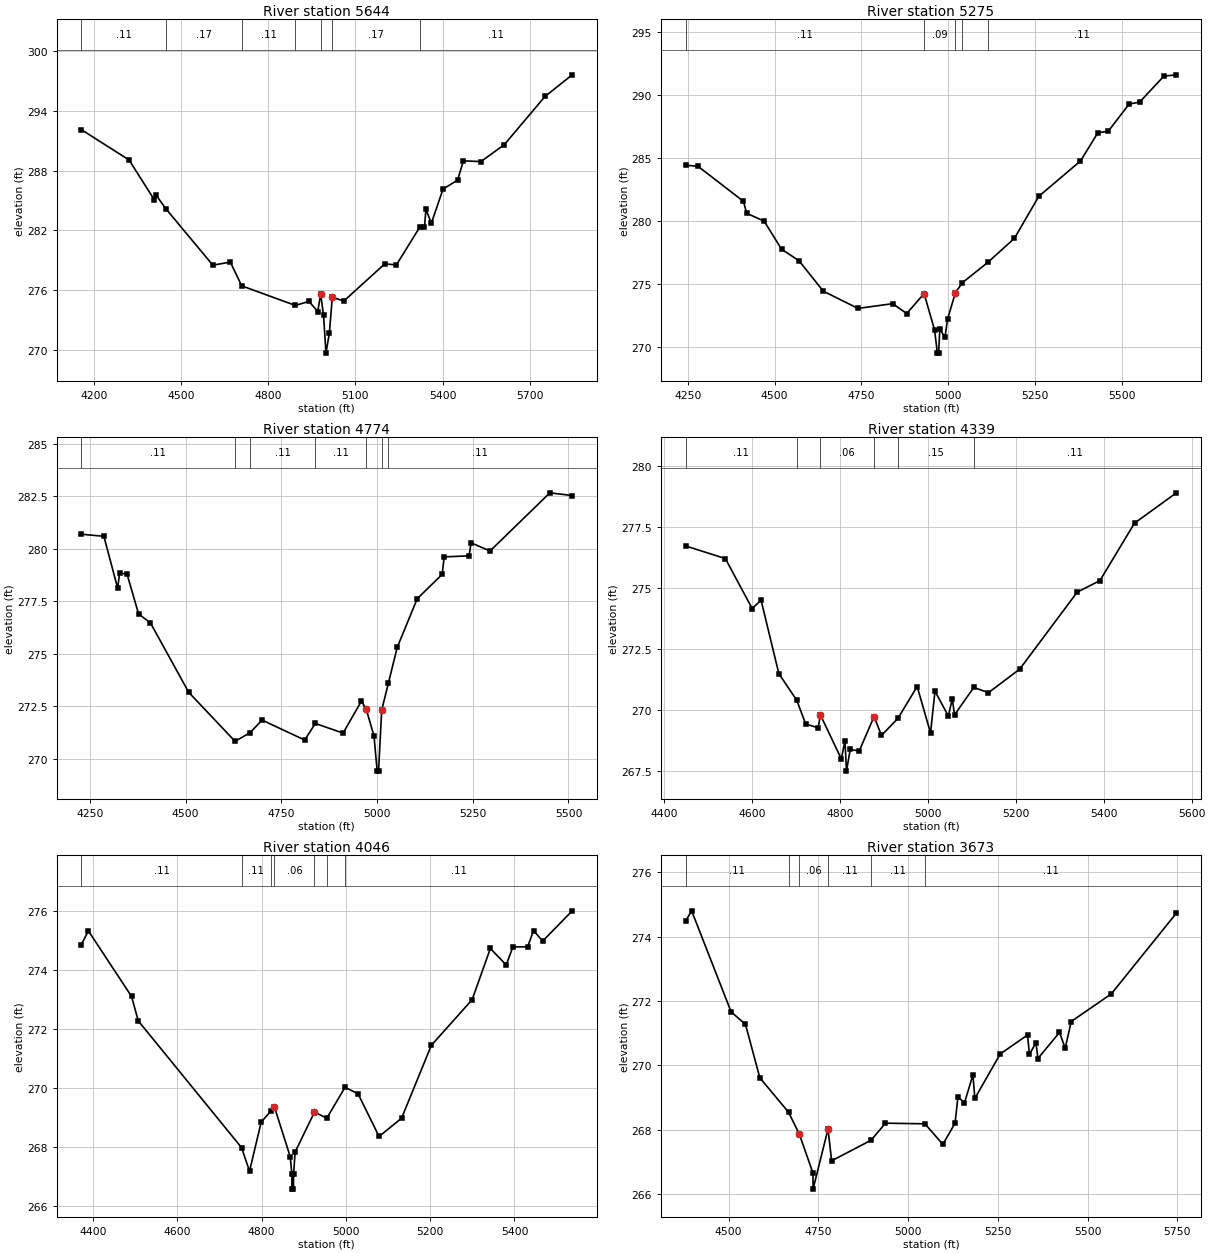
Type RM Length L Ch R = 1 ,5644    ,369,369,369
BEGIN DESCRIPTION:
Mapping XS dca4ede9
END DESCRIPTION:
XS GIS Cut Line= 3
      3746877.64     10255361.51      3746509.62     10255229.58
      3745214.45     10255125.41
#Sta/Elev= 30
  4156.2   292.1  4320.6  289.06  4407.5  285.07  4412.8  285.57  4447.6  284.16
  4609.1  278.52  4669.3  278.83  4708.4  276.45    4893  274.49  4940.2  274.89
  4970.3  273.88  4980.3  275.62  4990.3  273.49  4998.6  269.71  5010.4  271.73
  5020.4  275.29  5060.6  274.94    5201  278.65  5241.2  278.55  5322.3  282.36
  5337.9  282.36  5342.9  284.11  5361.5  282.72  5401.7  286.14  5451.8  287.04
  5471.9  288.97  5532.1   288.9  5612.3  290.58  5752.8  295.42  5846.5  297.59
#Mann= 7 ,-1 , 0
  4156.2     .11       0  4447.6     .17       0  4708.4     .11       0
    4893     .17       0  4980.3     .09       0  5020.4     .17       0
  5322.3     .11       0
Bank Sta=4980.3,5020.4
XS Rating Curve= 0 ,0
Exp/Cntr=0.3,0.1

Type RM Length L Ch R = 1 ,5275    ,501,501,501
BEGIN DESCRIPTION:
WFSJR 080 4.0
END DESCRIPTION:
XS GIS Cut Line= 3
      3746783.95     10254812.92      3746028.23     10254836.84
      3745371.82     10254847.62
#Sta/Elev= 30
  4243.9  284.41    4280  284.31  4410.1  281.54  4420.1  280.58  4470.1  279.96
  4520.1  277.73  4570.2  276.82  4640.2   274.4  4740.2  273.03  4840.3  273.41
  4880.3  272.62  4930.3  274.21  4960.4  271.33  4968.6  269.48  4972.1  269.48
  4975.5  271.38  4990.4  270.74  4997.7  272.17  5020.4  274.27  5040.4  275.07
  5113.9  276.69  5190.4   278.6  5260.4  281.93  5380.4  284.74  5430.4  286.98
  5460.4   287.1  5520.4  289.26  5550.5  289.41  5620.5  291.48  5656.5  291.58
#Mann= 5 ,-1 , 0
  4243.9     .11       0  4930.3     .09       0  5020.4     .11       0
  5040.4     .17       0  5113.9     .11       0
Bank Sta=4930.3,5020.4
XS Rating Curve= 0 ,0
Exp/Cntr=0.3,0.1

Type RM Length L Ch R = 1 ,4774    ,435,435,435
BEGIN DESCRIPTION:
WFSJR 080 3.0
END DESCRIPTION:
XS GIS Cut Line= 3
      3746676.32     10254437.92      3745981.84     10254351.11
      3745405.42     10254434.45
#Sta/Elev= 30
  4227.4   280.7  4286.3   280.6  4322.3  278.13  4327.3  278.85  4346.8   278.8
    4377   276.9  4407.9  276.48    4508  273.17    4629  270.84  4668.3  271.25
  4699.5  271.85    4811   270.9  4838.6  271.69  4911.2  271.23  4959.3  272.76
  4971.7  272.36  4991.9   271.1  5000.3  269.42  5003.8  269.42  5012.1  272.33
  5029.6  273.61  5052.6  275.31  5104.9  277.63  5170.2  278.79  5175.2  279.62
  5240.5  279.67  5245.5  280.29  5295.1   279.9  5451.4  282.67  5509.7  282.54
#Mann= 7 ,-1 , 0
  4227.4     .11       0    4629     .11       0  4668.3     .11       0
  4838.6     .11       0  4971.7     .06       0  5012.1     .11       0
  5029.6     .11       0
Bank Sta=4971.7,5012.1
XS Rating Curve= 0 ,0
Exp/Cntr=0.3,0.1

Type RM Length L Ch R = 1 ,4339    ,293,293,293
BEGIN DESCRIPTION:
Mapping XS f7e033f6
END DESCRIPTION:
XS GIS Cut Line= 3
      3746517.11     10253946.28      3745679.44     10254085.16
      3745454.92      10254228.9
#Sta/Elev= 30
  4449.7  276.72  4540.2   276.2    4601  274.16  4621.3   274.5  4661.8  271.49
  4702.4  270.41  4722.6  269.44  4751.1  269.28  4756.1  269.81  4803.7  268.01
    4812  268.75  4815.4  267.51    4824   268.4  4844.3  268.33  4878.1  269.74
    4895  268.97  4932.5  269.67  4976.1  270.97  5006.5  269.07  5016.6  270.78
    5047  269.76  5055.9  270.47    5061  269.81  5104.7  270.93  5138.2  270.72
  5209.2  271.68  5339.9  274.83  5391.5   275.3  5470.1  277.65  5565.4  278.89
#Mann= 6 ,-1 , 0
  4449.7     .11       0  4702.4     .11       0  4756.1     .06       0
  4878.1     .11       0  4932.5     .15       0  5104.7     .11       0
#XS Ineff= 1 ,-1
  4976.1    5190  270.97
Permanent Ineff=
       F
Bank Sta=4756.1,4878.1
XS Rating Curve= 0 ,0
Exp/Cntr=0.3,0.1

Type RM Length L Ch R = 1 ,4046    ,373,373,373
BEGIN DESCRIPTION:
Mapping XS 900a8400
END DESCRIPTION:
XS GIS Cut Line= 2
      3746408.93     10253458.75      3745396.05     10254032.92
#Sta/Elev= 30
  4372.6  274.87  4389.3  275.34  4491.7  273.11  4507.6  272.28  4752.7  267.97
  4771.6  267.17  4799.2  268.84  4822.1  269.21  4830.7  269.35  4868.1  267.66
    4872  267.06  4872.2  266.56  4875.7  266.56    4876  267.06  4879.7  267.82
  4925.6  269.18  4954.8  268.97  4998.1  270.02    5029   269.8  5078.8  268.35
  5132.2  268.97  5202.9  271.45  5299.6     273  5342.8  274.74  5380.4  274.18
  5396.2  274.79  5431.4   274.8  5445.3  275.35  5466.9  274.99  5536.9  276.02
#Mann= 7 ,-1 , 0
  4372.6     .11       0  4752.7     .11       0  4822.1     .15       0
  4830.7     .06       0  4925.6     .15       0  4954.8     .11       0
  4998.1     .11       0
#XS Ineff= 1 ,-1
  4998.1    5180  270.02
Permanent Ineff=
       F
Bank Sta=4830.7,4925.6
XS Rating Curve= 0 ,0
Exp/Cntr=0.3,0.1

Type RM Length L Ch R = 1 ,3673    ,129,129,129
BEGIN DESCRIPTION:
Mapping XS 4c3170ee
END DESCRIPTION:
XS GIS Cut Line= 3
      3746374.78     10253413.76      3745623.96     10253413.76
      3745380.24     10253980.34
#Sta/Elev= 30
  4380.1  274.48    4397   274.8    4507  271.66    4547  271.27    4587  269.61
    4667  268.54    4697  267.86    4735  266.65  4735.3  266.15    4777  268.02
    4787  267.03    4897  267.67    4937   268.2    5047  268.18    5097  267.54
  5130.9   268.2    5139  269.02  5157.1  268.83  5180.7   269.7  5186.1  268.97
  5256.7  270.35  5332.8  270.94  5338.2  270.34  5356.3   270.7  5361.8  270.21
  5421.9  271.02  5437.8  270.53  5454.6  271.36  5566.4  272.22  5747.7  274.73
#Mann= 6 ,-1 , 0
  4380.1     .11       0    4667     .11       0    4697     .06       0
    4777     .11       0    4897     .11       0    5047     .11       0
Bank Sta=4697,4777
XS Rating Curve= 0 ,0
Exp/Cntr=0.3,0.1

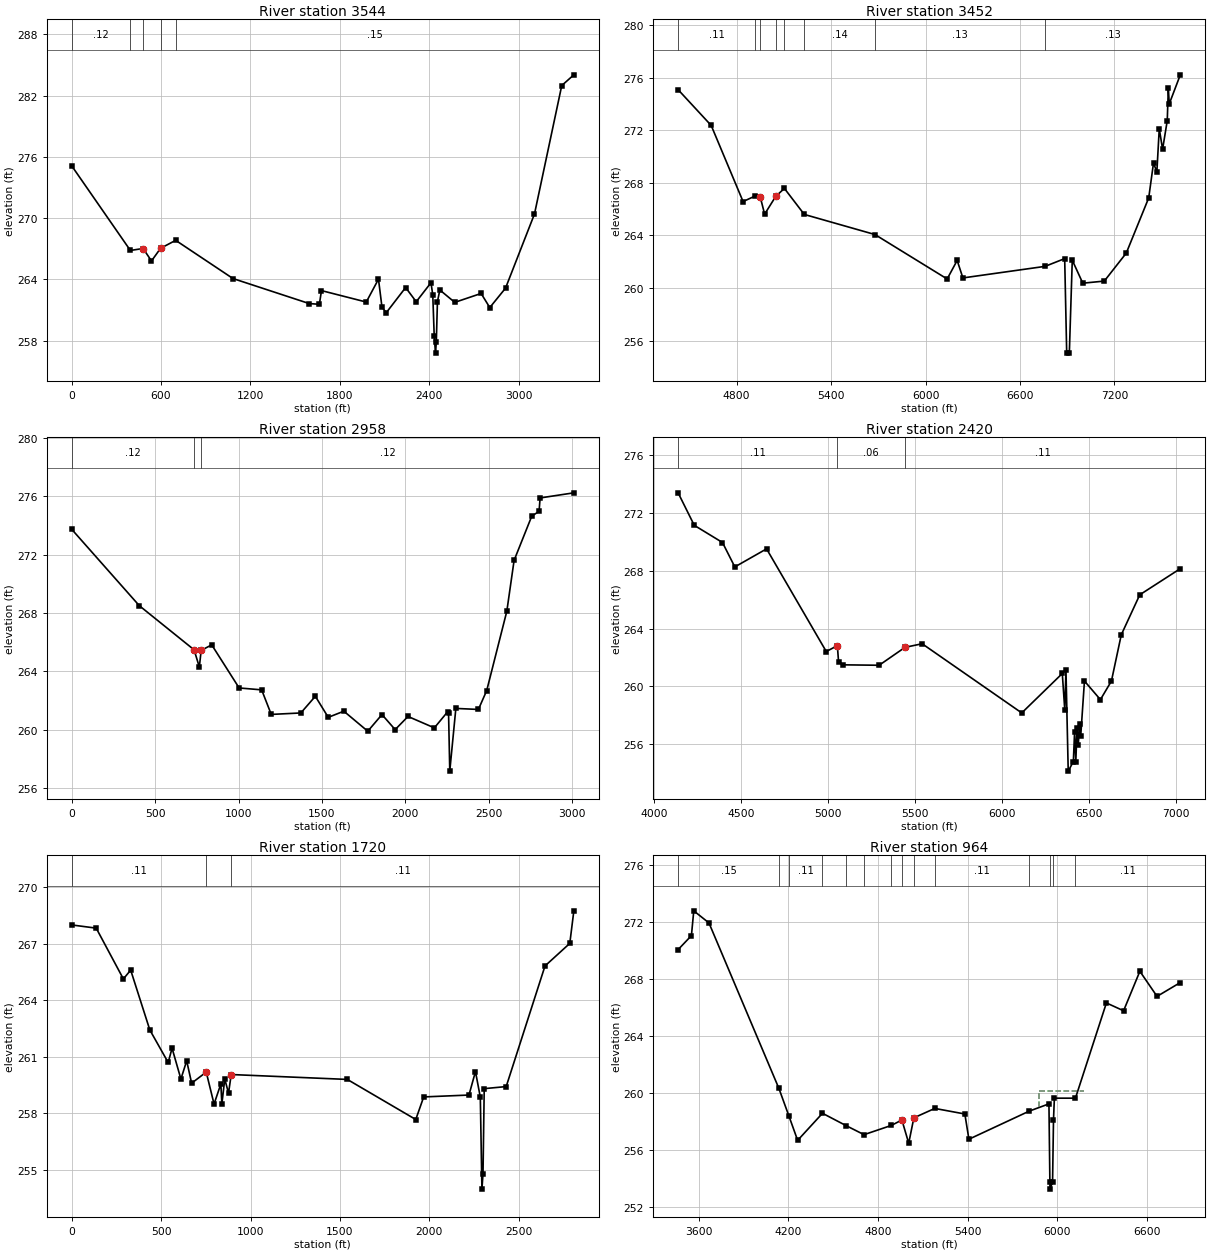
Type RM Length L Ch R = 1 ,3544    ,92,92,92
XS GIS Cut Line= 3
      3746376.75     10253393.87      3745663.15     10253276.44
      3743224.16     10252245.74
#Sta/Elev= 30
       0  275.13   394.1  266.84   479.7  267.03   535.8  265.81   596.8  267.05
   698.2  267.83  1082.8  264.09  1594.8  261.64  1662.6  261.57  1676.8  262.91
  1977.4  261.79  2059.4  264.03  2083.1  261.26  2112.3  260.76  2241.6  263.21
  2312.7  261.82  2411.7  263.68  2423.8  262.49  2433.4  258.48  2442.1  256.79
  2447.5  257.87  2455.1  261.83  2471.2  262.97  2571.4  261.76  2748.2  262.63
  2806.5  261.25  2912.1  263.15  3106.5  270.41  3289.4  282.98  3370.6  284.03
#Mann= 5 ,-1 , 0
       0     .12       0   394.1     .12       0   479.7     .06       0
   596.8     .12       0   698.2     .15       0
Bank Sta=479.7,596.8
XS Rating Curve= 0 ,0
Exp/Cntr=0.3,0.1

Type RM Length L Ch R = 1 ,3452    ,494,494,494
BEGIN DESCRIPTION:
Mapping XS 4efb428c
END DESCRIPTION:
XS GIS Cut Line= 3
        3746404.     10253387.01      3745716.72     10253178.58
       3743627.8     10251855.83
#Sta/Elev= 30
    4428  275.08  4638.1  272.36  4840.7  266.57    4917  266.99  4949.9  266.92
  4977.6  265.61  5048.6  266.97  5103.2  267.57  5229.6  265.59  5678.8  264.06
  6137.4  260.68  6200.9  262.09  6237.4  260.76  6759.5  261.64  6884.1  262.23
  6896.9  255.04  6913.6  255.04  6932.3  262.11  6999.1  260.36  7135.8  260.52
  7275.4  262.65    7418  266.85  7448.5  269.51  7469.7  268.81    7485  272.12
  7506.1  270.54  7535.8  272.73  7542.6  275.19  7548.5     274  7618.7  276.21
#Mann= 8 ,-1 , 0
    4428     .11       0    4917     .13       0  4949.9     .07       0
  5048.6     .13       0  5103.2     .15       0  5229.6     .14       0
  5678.8     .13       0  6759.5     .13       0
Bank Sta=4949.9,5048.6
XS Rating Curve= 0 ,0
Exp/Cntr=0.3,0.1

Type RM Length L Ch R = 1 ,2958    ,538,538,538
XS GIS Cut Line= 4
        3746326.      10253289.2      3746123.02     10252908.61
      3745757.77     10252780.04      3744017.07     10251449.67
#Sta/Elev= 30
       0  273.73   405.3   268.5   733.7  265.48   765.2   264.3   776.1  265.44
   839.4  265.82  1003.6  262.87  1138.7  262.74    1196  261.06  1373.5  261.16
  1460.3   262.3  1537.7  260.86  1631.1  261.28  1774.5  259.91  1859.7  261.05
  1938.6  260.02  2015.6  260.92  2173.5  260.14  2252.4  261.23  2258.7  261.13
  2265.9  257.18  2302.3  261.47  2437.4   261.4  2487.2  262.69  2607.8  268.12
  2651.4   271.6  2757.4  274.63    2801  274.95  2807.3  275.87  3009.4  276.22
#Mann= 3 , 0 , 0
       0     .12       0   733.7     .07       0   776.1     .12       0
Bank Sta=733.7,776.1
XS Rating Curve= 0 ,0
Exp/Cntr=0.3,0.1

Type RM Length L Ch R = 1 ,2420    ,700,700,700
BEGIN DESCRIPTION:
WFSJR 080 2.0
END DESCRIPTION:
XS GIS Cut Line= 3
       3746304.3     10253222.56      3746192.53     10252580.42
      3744569.26     10251039.61
#Sta/Elev= 30
  4137.5   273.4  4230.4  271.15  4392.8  269.96  4463.8  268.27  4646.5  269.52
  4990.1  262.41  5053.9  262.82  5060.8  261.69  5089.2  261.49  5294.2  261.46
  5443.1   262.7  5541.8  262.95    6115  258.16  6348.3  260.89  6362.5  258.38
  6369.4  261.12  6382.4  254.13  6411.9  254.79  6419.1  256.85    6426  254.76
  6433.3  257.15  6440.2  255.92  6447.4  257.41  6454.3  256.56  6475.8  260.37
  6567.6  259.08  6631.1  260.37  6687.7  263.57  6794.1  266.34  7027.4  268.15
#Mann= 3 , 0 , 0
  4137.5     .11       0  5053.9     .06       0  5443.1     .11       0
Bank Sta=5053.9,5443.1
XS Rating Curve= 0 ,0
Exp/Cntr=0.3,0.1

Type RM Length L Ch R = 1 ,1720    ,756,756,756
XS GIS Cut Line= 4
      3746804.92     10252699.28      3746614.62     10252201.34
      3746326.63     10252044.77      3744698.96      10250977.1
#Sta/Elev= 30
       0  268.01   137.3  267.84   289.2  265.14     330  265.61     437  262.43
   539.6   260.7   561.4  261.46   610.8  259.82   643.1  260.79   670.7   259.6
   752.4  260.19   796.1  258.49   834.1  259.56   839.8   258.5     856  259.82
     877  259.07   892.1  260.06  1541.1   259.8  1923.8  257.67  1968.1  258.87
  2221.3  258.97  2257.5  260.22  2284.6  258.86  2293.7  253.97  2299.7  254.79
  2306.5  259.31  2429.3  259.42  2646.3  265.83  2784.9  267.03  2807.5  268.76
#Mann= 3 , 0 , 0
       0     .11       0   752.4     .06       0   892.1     .11       0
Bank Sta=752.4,892.1
XS Rating Curve= 0 ,0
Exp/Cntr=0.3,0.1

Type RM Length L Ch R = 1 ,964     ,0,0,0
BEGIN DESCRIPTION:
WFSJR 080 1.0
END DESCRIPTION:
XS GIS Cut Line= 4
      3747025.89     10252675.94      3746383.51      10251564.8
      3745836.63     10251525.73       3744543.2     10250701.07
#Sta/Elev= 30
  3460.3  270.08  3549.4  271.06  3565.2   272.8  3667.1  271.95  4135.9  260.34
  4202.5  258.42  4261.4   256.7  4427.9   258.6  4588.7  257.72  4706.4   257.1
  4889.8  257.75    4960  258.13  5005.8   256.5  5040.2  258.28  5180.5  258.94
    5382  258.55  5409.2  256.78  5813.2  258.75  5945.6  259.26  5951.9  253.78
  5952.4  253.28  5969.9  253.78  5976.1  258.14    5982  259.66  6123.2  259.66
  6330.7  266.34  6445.8  265.79    6555  268.56  6670.1   266.8    6826  267.77
#Mann= 14 ,-1 , 0
  3460.3     .15       0  4135.9     .11       0  4202.5     .11       0
  4427.9     .11       0  4588.7     .12       0  4706.4     .12       0
  4889.8     .12       0    4960     .06       0  5040.2     .12       0
  5180.5     .11       0  5813.2     .11       0  5951.9     .11       0
  5969.9     .15       0  6123.2     .11       0
#XS Ineff= 1 ,-1
  5882.1    6180  260.13
Permanent Ineff=
       F
Bank Sta=4960,5040.2
XS Rating Curve= 0 ,0
Exp/Cntr=0.3,0.1

Chan Stop Cuts=-1
Use User Specified Reach Order=0
Composite Channel Slope=5