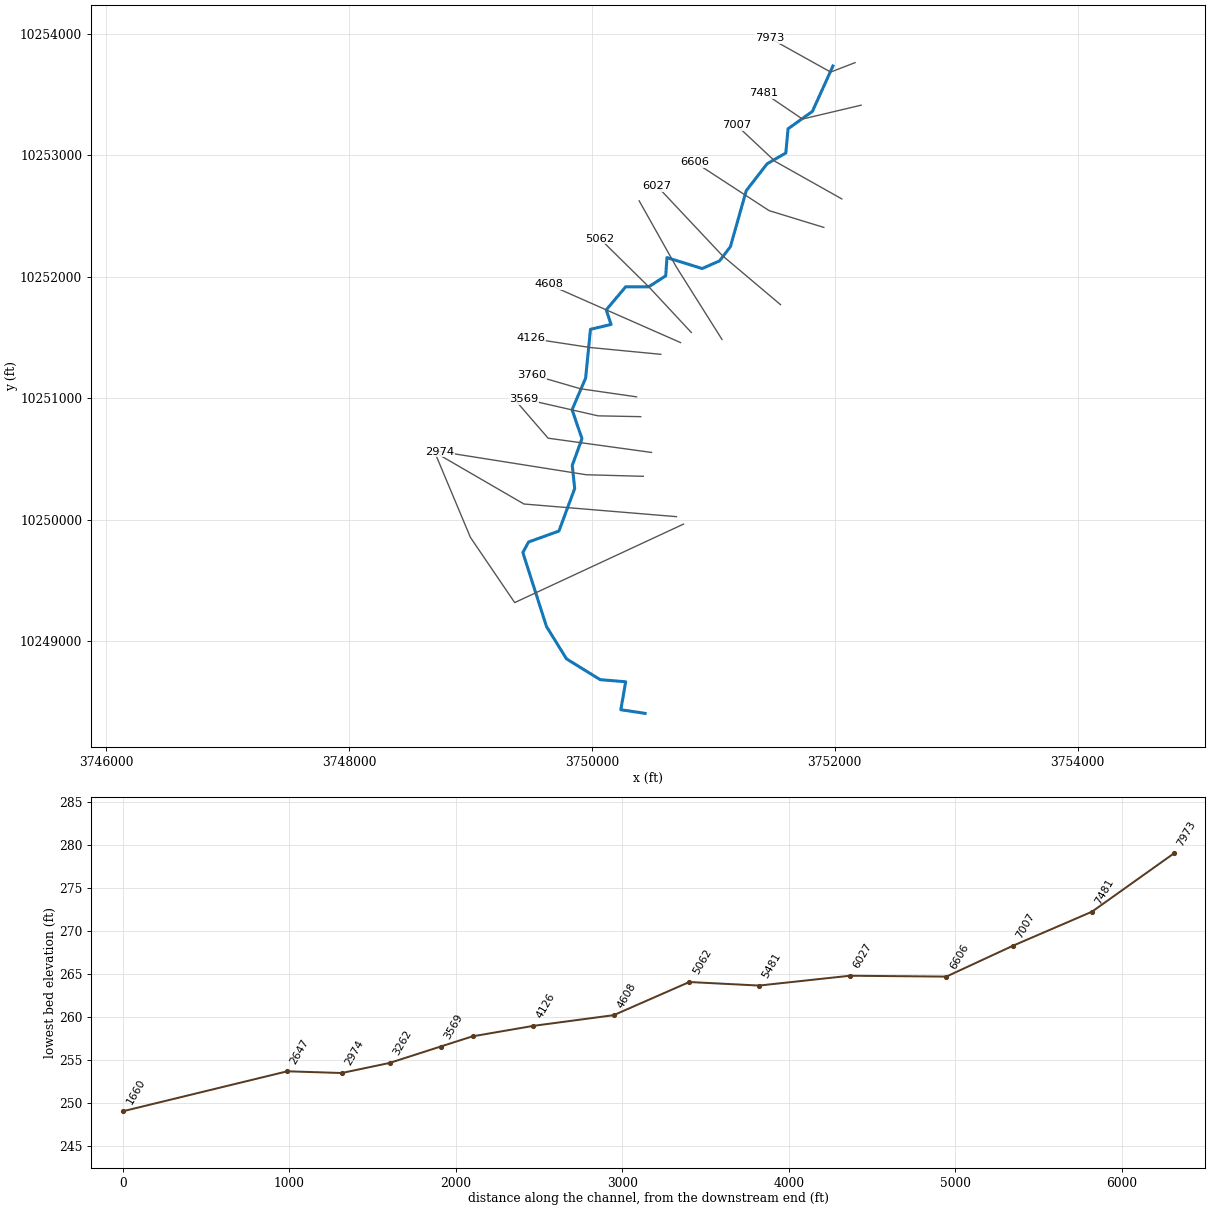
--- WFSJR 082.prj (project) ---

Proj Title=WFSJR 082 Base Level Engineering
Current Plan=p01
Default Exp/Contr=0.3,0.1
English Units
Geom File=g01
Flow File=f01
Plan File=p01
Y Axis Title=Elevation
X Axis Title(PF)=Main Channel Distance
X Axis Title(XS)=Station
BEGIN DESCRIPTION:
WFSJR 082
END DESCRIPTION:
DSS Export Rating Curves= 0
DSS Export Rating Curve Sorted= 0
DSS Export Volume Flow Curves= 0
DXF OffsetX= 0
DXF OffsetY= 0
DXF ScaleX= 1
DXF ScaleY= 10

--- WFSJR 082.p01 (plan) ---

Plan Title=Multiple Run
Program Version=4.10
Short Identifier=Multiple
Geom File=g01
Flow File=f01
Subcritical Flow
K Sum by GR= 0
Std Step Tol= 0.01
Critical Tol= 0.01
Num of Std Step Trials= 20
Max Error Tol= 0.3
Flow Tol Ratio= 0.001
Split Flow NTrial= 30
Split Flow Tol= 0.02
Split Flow Ratio= 0.02
Log Output Level= 0
Friction Slope Method= 1
Unsteady Friction Slope Method= 2
Unsteady Bridges Friction Slope Method= 1
Parabolic Critical Depth
Global Vel Dist= 1 , 1 , 1
Global Log Level= 0
CheckData=True
Encroach Param=-1 ,0,0, 0
BEGIN DESCRIPTION:
Multiple Run
END DESCRIPTION:
Computation Interval=1HOUR
Output Interval=1HOUR
Run HTab= 0
Run UNet= 0
Run PostProcess= 0
Run WQNet= 0
UNET Theta= 1
UNET Theta Warmup= 1
UNET ZTol= 0.02
UNET ZSATol= 0.05
UNET MxIter= 20
UNET MaxInSteps= 0
UNET DtIC= 0
UNET DtMin= 0
UNET MaxCRTS= 20
UNET WFStab= 2
UNET SFStab= 1
UNET WFX= 1
UNET SFX= 1
UNET DSS MLevel= 4
UNET DZMax Abort= 100
UNET Convert EG Bridges= 0
UNET Use Existing IB Tables=-1
UNET Froude Reduction=False
UNET Froude Limit= 1
UNET Froude Power= 10
UNET Time Slicing=0,0, 5
UNET Junction Losses=0
Instantaneous Interval=1HOUR
Write IC File= 0
Write IC File at Sim End=0
Echo Input=False
Echo Parameters=False
Echo Output=False
Write Detailed= 0
WQ AD Non Conservative
WQ ULTIMATE=-1
WQ Max Comp Step=1HOUR
WQ Output Interval=15MIN
WQ Output Selected Increments= 0
WQ Output face flow=0
WQ Output face velocity=0
WQ Output face area=0
WQ Output face dispersion=0
WQ Output cell volume=0
WQ Output cell surface area=0
WQ Output cell continuity=0
WQ Output cumulative cell continuity=0
WQ Output face conc=0
WQ Output face dconc_dx=0
WQ Output face courant=0
WQ Output face peclet=0
WQ Output face adv mass=0
WQ Output face disp mass=0
WQ Output cell mass=0
WQ Output cell source sink temp=0
WQ Output cell source sink nsm=0
WQ Output MaxMinRange=-1
WQ Daily Max Min Mean=-1
WQ Daily Range=0
WQ Daily Time=0
WQ Create Restart=0
WQ Fixed Restart=0
WQ System Summary=0
WQ Use Fixed Temperature=0
Sorting and Armoring Iterations= 10
XS Update Threshold= 0.02
Hydraulics Update Threshold= 0.02
Energy Slope Method= 1
Volume Change Method= 0
XS Weighting Method= 0
Number of US Weighted Cross Sections= 1
Number of DS Weighted Cross Sections= 1
Upstream XS Weight=0.25
Main XS Weight=0.5
Downstream XS Weight=0.25
Number of DS XS's Weighted with US Boundary= 1
Upstream Boundary Weight= 1
Weight of XSs Associated with US Boundary= 0
Number of US XS's Weighted with DS Boundary= 1
Downstream Boundary Weight= 0.5
Weight of XSs Associated with DS Boundary= 0.5
Sediment Output Level= 4
Mass or Volume Output= 0
Output Increment Type= 1
Profile and TS Output Increment= 10
XS Output Flag= 0
XS Output Increment= 10
Disregard all LS=0
Disregard all Conn=0
Disregard all Breaches=0
Disregard all Pumps=0

--- WFSJR 082.f01 (steady flow) ---

Flow Title=Multiple
Program Version=4.10
Number of Profiles= 7
Profile Names=10-year,25-year,50-year,1pct_min,100-year,1pct_plu,500-year
River Rch & RM=WFSJR 082,Reach-1         ,7973
     477     638     856     378    1141    3446    2098
River Rch & RM=WFSJR 082,Reach-1         ,6606
     623     839    1129     499    1508    4554    2783
Boundary for River Rch & Prof#=WFSJR 082,Reach-1         , 1
Up Type= 0
Dn Type= 3
Dn Slope=0.0055
Boundary for River Rch & Prof#=WFSJR 082,Reach-1         , 2
Up Type= 0
Dn Type= 3
Dn Slope=0.0055
Boundary for River Rch & Prof#=WFSJR 082,Reach-1         , 3
Up Type= 0
Dn Type= 3
Dn Slope=0.0055
Boundary for River Rch & Prof#=WFSJR 082,Reach-1         , 4
Up Type= 0
Dn Type= 3
Dn Slope=0.0055
Boundary for River Rch & Prof#=WFSJR 082,Reach-1         , 5
Up Type= 0
Dn Type= 3
Dn Slope=0.0055
Boundary for River Rch & Prof#=WFSJR 082,Reach-1         , 6
Up Type= 0
Dn Type= 3
Dn Slope=0.0055
Boundary for River Rch & Prof#=WFSJR 082,Reach-1         , 7
Up Type= 0
Dn Type= 3
Dn Slope=0.0055
DSS Import GetInterval= 0
DSS Import GetPeak= 0
DSS Import FillOption= 0

--- WFSJR 082.g01 (geometry) ---

Geom Title=Existing Conditions
Program Version=4.10

River Reach=WFSJR 082       ,Reach-1
Reach XY= 30
      3751985.56      10253733.6      3751816.36     10253359.99
      3751615.67     10253216.79      3751597.33     10253017.51
      3751443.19     10252928.98      3751271.42     10252707.48
      3751140.56     10252246.13      3751051.22     10252129.84
      3750908.23     10252066.84      3750618.23     10252156.84
      3750608.23     10252006.84      3750468.23     10251916.84
      3750278.23     10251916.84      3750118.23     10251726.84
      3750158.23     10251606.84      3749988.23     10251566.84
      3749948.23     10251165.57      3749836.82     10250904.97
      3749918.23     10250666.84      3749838.23     10250446.84
      3749858.23     10250256.84      3749728.23     10249906.84
      3749478.23     10249816.84      3749431.37     10249729.98
      3749625.75     10249121.74      3749790.85      10248855.2
      3750068.47       10248684.      3750278.23     10248666.84
      3750238.23     10248436.84      3750438.23     10248406.84

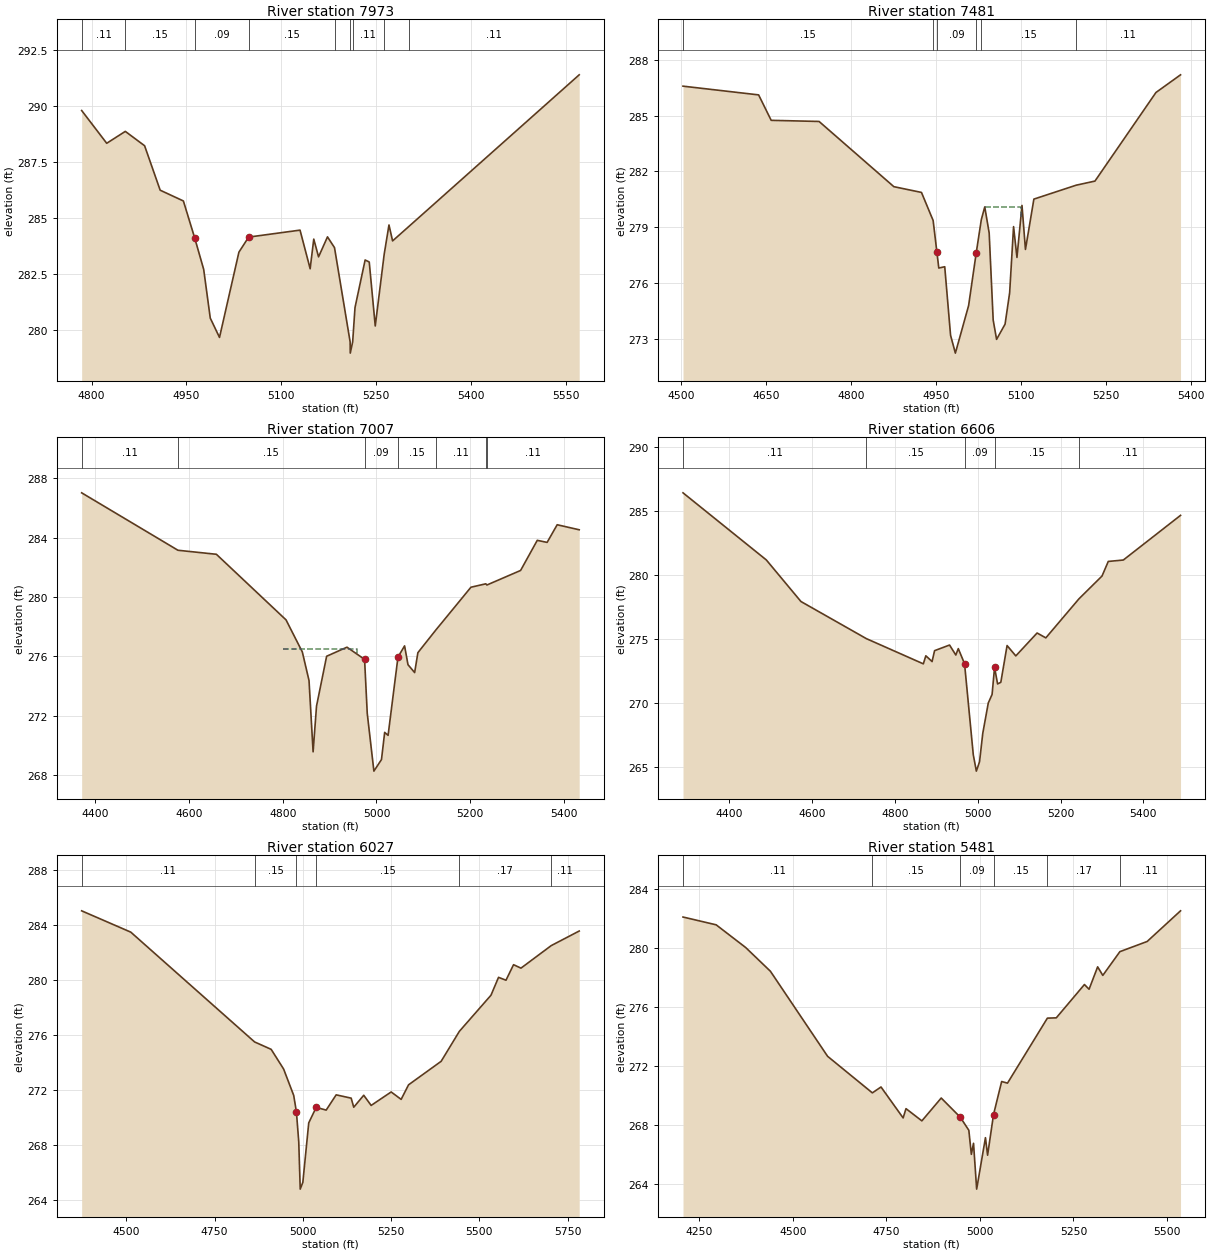
Type RM Length L Ch R = 1 ,7973    ,492,492,492
BEGIN DESCRIPTION:
WFSJR 082 16.0
END DESCRIPTION:
XS GIS Cut Line= 3
      3752167.86     10253761.07      3751966.62     10253683.43
      3751467.88     10253961.05
#Sta/Elev= 30
  4784.3   289.8  4823.9  288.34  4853.3  288.87  4883.8  288.23  4908.4  286.25
  4945.1  285.77    4963  284.12  4977.2  282.72  4987.6  280.55  5002.2  279.69
  5032.9  283.49  5048.3  284.16  5129.5  284.47  5145.5  282.75  5151.2  284.07
  5158.8  283.28  5172.9  284.17    5184  283.69  5208.7  279.49  5208.9  278.99
  5212.7  279.49  5216.4  281.02  5232.4  283.14  5238.9  283.05  5248.4   280.2
  5262.5  283.39  5270.1   284.7  5275.8  283.99  5302.2  284.65  5570.8  291.39
#Mann= 9 ,-1 , 0
  4784.3     .11       0  4853.3     .15       0    4963     .09       0
  5048.3     .15       0    5184     .11       0  5208.7     .12       0
  5212.7     .11       0  5262.5     .17       0  5302.2     .11       0
#XS Ineff= 1 ,-1
  5129.5    5320  284.47
Permanent Ineff=
       T
Bank Sta=4963,5048.3
XS Rating Curve= 0 ,0
Exp/Cntr=0.3,0.1

Type RM Length L Ch R = 1 ,7481    ,474,474,474
BEGIN DESCRIPTION:
WFSJR 082 15.0
END DESCRIPTION:
XS GIS Cut Line= 3
      3752217.88     10253411.08      3751734.18     10253296.86
      3751417.88     10253511.05
#Sta/Elev= 30
    4503  286.59  4636.6  286.12  4658.8  284.75  4743.4  284.69  4875.5  281.18
  4924.3  280.87  4944.9  279.36  4951.6 277.645  4954.9   276.8  4965.4  276.87
  4975.7  273.18  4984.2  272.22  5007.6  274.78  5021.1  277.63    5030   279.4
  5036.1  280.09  5043.9  278.69    5051     274    5057  272.96    5072  273.78
  5080.1  275.47    5087  279.03    5093  277.37  5101.9  280.17    5108   277.8
  5122.9  280.51  5197.7  281.26  5230.8  281.48  5338.6  286.25    5382   287.2
#Mann= 6 ,-1 , 0
    4503     .15       0  4944.9     .12       0  4951.6     .09       0
  5021.1     .15       0    5030     .15       0  5197.7     .11       0
#XS Ineff= 1 ,-1
  5036.1    5100  280.09
Permanent Ineff=
       F
Bank Sta=4951.6,5021.1
XS Rating Curve= 0 ,0
Exp/Cntr=0.3,0.1

Type RM Length L Ch R = 1 ,7007    ,401,401,401
BEGIN DESCRIPTION:
WFSJR 082 14.0
END DESCRIPTION:
XS GIS Cut Line= 3
      3752058.58     10252639.73      3751509.85     10252948.03
      3751193.98      10253243.9
#Sta/Elev= 30
  4370.6  287.02  4576.2  283.15  4658.2  282.88  4806.9  278.46  4841.7   276.3
    4856  274.37  4864.7  269.57    4872  272.65  4893.6  276.01    4937  276.62
  4974.6   275.8  4980.3  272.16  4994.5  268.27  5010.7  269.05  5017.5  270.88
  5024.8  270.68  5045.9  275.95    5060  276.71  5067.3  275.44  5081.5  274.91
  5088.4  276.25  5126.3  277.76  5201.7  280.66  5233.4  280.89  5235.8  280.81
  5307.7  281.79  5343.3  283.82  5364.3  283.68  5385.8  284.87  5432.8  284.53
#Mann= 7 ,-1 , 0
  4370.6     .11       0  4576.2     .15       0  4974.6     .09       0
  5045.9     .15       0  5126.3     .11       0  5233.4     .15       0
  5235.8     .11       0
#XS Ineff= 2 ,-1
    4800  4958.7  276.52    5060    5110  276.71
Permanent Ineff=
       F       F
Bank Sta=4974.6,5045.9
XS Rating Curve= 0 ,0
Exp/Cntr=0.3,0.1

Type RM Length L Ch R = 1 ,6606    ,579,579,579
BEGIN DESCRIPTION:
WFSJR 082 13.0
END DESCRIPTION:
XS GIS Cut Line= 3
      3751910.13     10252405.37      3751459.59      10252543.4
      3750847.58     10252941.86
#Sta/Elev= 30
  4288.1  286.42  4489.2  281.18  4572.9  277.93  4730.9  275.03  4868.5  273.06
  4874.5  273.69  4889.6  273.24  4895.6  274.09  4931.8  274.53  4946.9  273.75
  4952.9  274.25    4968  273.07  4989.1  265.96  4996.5  264.68  5004.2  265.41
    5012  267.63  5025.3     270  5034.5  270.67  5040.5  272.78  5047.8  271.49
  5055.6  271.62  5070.7  274.49  5091.8  273.68  5143.2  275.47  5164.3  275.09
  5244.3  278.14    5300  279.92  5315.1  281.06  5351.4  281.17  5489.6  284.66
#Mann= 5 ,-1 , 0
  4288.1     .11       0  4730.9     .15       0    4968     .09       0
  5040.5     .15       0  5244.3     .11       0
Bank Sta=4968,5040.5
XS Rating Curve= 0 ,0
Exp/Cntr=0.3,0.1

Type RM Length L Ch R = 1 ,6027    ,546,546,546
BEGIN DESCRIPTION:
WFSJR 082 12.0
END DESCRIPTION:
XS GIS Cut Line= 3
      3751553.34     10251769.96      3751074.25     10252173.82
      3750537.69     10252743.94
#Sta/Elev= 30
  4373.4  285.03  4512.5  283.48  4863.3  275.49  4910.3  274.95  4945.5  273.52
  4974.1   271.6  4981.8   270.4  4988.4  268.22  4992.6  264.78    5000  265.28
  5016.7   269.6  5037.8  270.73  5066.1  270.53  5094.4  271.64  5136.9   271.4
  5144.2  270.74  5172.5  271.61  5193.5  270.87  5250.2  271.85  5278.5  271.31
  5299.5  272.37  5391.8  274.08  5443.4  276.26    5533  278.89  5554.4  280.19
  5575.5  279.98  5596.9  281.11    5618  280.86  5703.7   282.5  5782.9  283.56
#Mann= 6 ,-1 , 0
  4373.4     .11       0  4863.3     .15       0  4981.8     .09       0
  5037.8     .15       0  5443.4     .17       0  5703.7     .11       0
Bank Sta=4981.8,5037.8
XS Rating Curve= 0 ,0
Exp/Cntr=0.3,0.1

Type RM Length L Ch R = 1 ,5481    ,419,419,419
BEGIN DESCRIPTION:
WFSJR 082 11.0
END DESCRIPTION:
XS GIS Cut Line= 3
      3751071.57      10251483.5      3750693.96     10252082.46
      3750389.29      10252624.1
#Sta/Elev= 30
  4206.6   282.1  4295.2  281.57  4374.1  280.03  4440.2  278.42    4593  272.65
  4712.6  270.17  4735.7  270.57  4794.8  268.47  4802.5   269.1  4844.9  268.27
  4896.6  269.82  4947.5  268.52  4970.4  267.63  4977.1     266  4982.9  266.75
  4991.3  263.64  5014.8  267.13  5020.5  265.94  5036.4   268.7  5058.1  270.94
  5073.7  270.83  5180.3  275.24  5204.1  275.26  5279.3  277.52  5291.7   277.2
  5314.6  278.72  5328.4  278.14    5374  279.75  5446.9  280.44  5536.1  282.52
#Mann= 6 ,-1 , 0
  4206.6     .11       0  4712.6     .15       0  4947.5     .09       0
  5036.4     .15       0  5180.3     .17       0    5374     .11       0
Bank Sta=4947.5,5036.4
XS Rating Curve= 0 ,0
Exp/Cntr=0.3,0.1

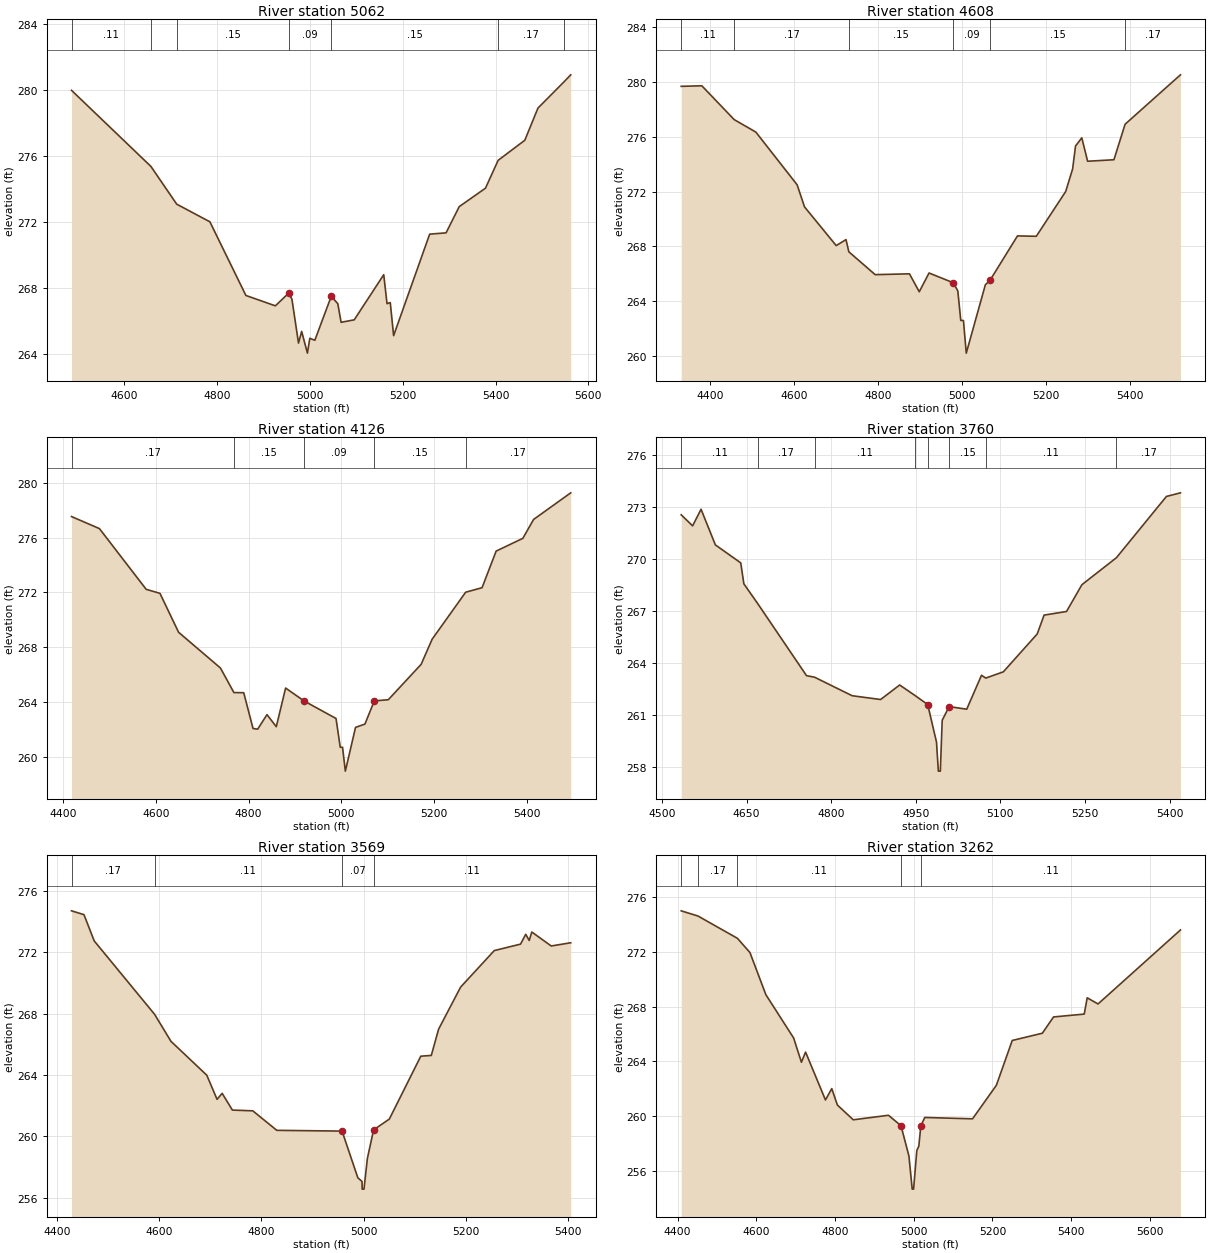
Type RM Length L Ch R = 1 ,5062    ,454,454,454
BEGIN DESCRIPTION:
WFSJR 082 10.0
END DESCRIPTION:
XS GIS Cut Line= 3
      3750818.95     10251540.81      3750468.23     10251916.84
      3750067.84     10252311.08
#Sta/Elev= 30
  4485.8     280    4657  275.38  4712.6  273.09  4784.1  272.02  4861.7  267.55
  4925.2  266.92  4953.6  267.68  4960.9  267.33  4975.1  264.66  4981.9  265.37
  4994.3  264.05  4999.5  264.95  5010.3  264.83  5045.7   267.5  5059.8  267.05
  5066.9  265.92  5095.2  266.07  5158.8  268.81  5165.9  267.05  5172.9  267.12
  5180.1  265.11  5257.8  271.27  5293.2  271.35  5321.5  272.94  5378.1  274.06
  5405.4  275.75  5462.9  276.97  5491.2  278.92  5547.9  280.53  5561.9  280.94
#Mann= 7 ,-1 , 0
  4485.8     .11       0    4657     .17       0  4712.6     .15       0
  4953.6     .09       0  5045.7     .15       0  5405.4     .17       0
  5547.9     .11       0
Bank Sta=4953.6,5045.7
XS Rating Curve= 0 ,0
Exp/Cntr=0.3,0.1

Type RM Length L Ch R = 1 ,4608    ,482,482,482
BEGIN DESCRIPTION:
WFSJR 082 9.0
END DESCRIPTION:
XS GIS Cut Line= 3
      3750730.39     10251457.48      3750118.23     10251726.84
      3749642.98     10251936.15
#Sta/Elev= 30
  4331.2  279.68  4380.3  279.72  4457.3  277.25  4508.8  276.34  4607.1  272.49
  4624.6  270.88  4700.1  268.05  4723.4  268.49  4730.1   267.6  4792.8  265.93
  4874.4  265.99  4897.7  264.68    4921  266.05  4978.6  265.34  4989.5  264.74
  4996.5  262.59  5002.9  262.58  5009.6   260.2    5055  265.19    5066  265.51
  5131.5  268.76  5176.2  268.73  5246.2     272  5262.7  273.65  5269.6  275.32
  5284.5  275.92  5298.4  274.21    5361  274.32  5387.5  276.91  5519.3  280.52
#Mann= 6 ,-1 , 0
  4331.2     .11       0  4457.3     .17       0  4730.1     .15       0
  4978.6     .09       0    5066     .15       0  5387.5     .17       0
Bank Sta=4978.6,5066
XS Rating Curve= 0 ,0
Exp/Cntr=0.3,0.1

Type RM Length L Ch R = 1 ,4126    ,366,366,366
BEGIN DESCRIPTION:
WFSJR 082 8.0
END DESCRIPTION:
XS GIS Cut Line= 3
      3750567.85     10251361.07      3749988.23     10251416.84
      3749498.66     10251491.31
#Sta/Elev= 30
  4417.7  277.53    4478  276.65  4578.9  272.22  4608.6  271.93  4648.8  269.09
  4739.2  266.48  4768.2  264.69  4789.4  264.68  4809.5  262.07  4819.5  262.02
  4839.6  263.08  4859.7   262.2  4879.8  265.02    4920  264.07  4988.6   262.8
  4997.7   260.7  5002.7   260.7  5008.7  258.96  5030.7  262.15    5051  262.39
  5071.2  264.08  5101.5  264.17  5172.3  266.75    5196  268.58  5268.4  272.01
  5303.8  272.34  5334.2  275.01  5391.8  275.94  5415.1  277.32  5495.2  279.26
#Mann= 5 ,-1 , 0
  4417.7     .17       0  4768.2     .15       0    4920     .09       0
  5071.2     .15       0  5268.4     .17       0
Bank Sta=4920,5071.2
XS Rating Curve= 0 ,0
Exp/Cntr=0.3,0.1

Type RM Length L Ch R = 1 ,3760    ,191,191,191
BEGIN DESCRIPTION:
WFSJR 082 7.0
END DESCRIPTION:
XS GIS Cut Line= 3
      3750367.81     10251011.08      3749906.57     10251077.51
       3749503.9     10251194.43
#Sta/Elev= 30
    4534  272.56  4554.2  271.92  4569.2  272.88  4594.6  270.82  4639.6  269.78
  4645.1  268.57  4670.2   267.4  4756.2  263.26  4770.5  263.17  4837.1   262.1
  4887.6  261.88  4921.4  262.72  4948.2  262.12  4971.1  261.59  4986.7  259.42
    4990  257.74  4993.5  257.74  4996.8  260.68  5009.1  261.47  5040.3  261.32
  5066.5  263.28  5074.1  263.12  5105.2  263.48  5165.3  265.67  5177.5  266.76
  5217.3  266.97  5244.6  268.52  5305.8  270.08  5394.4  273.62  5419.3  273.83
#Mann= 8 ,-1 , 0
    4534     .11       0  4670.2     .17       0  4770.5     .11       0
  4948.2     .15       0  4971.1     .09       0  5009.1     .15       0
  5074.1     .11       0  5305.8     .17       0
Bank Sta=4971.1,5009.1
XS Rating Curve= 0 ,0
Exp/Cntr=0.3,0.1

Type RM Length L Ch R = 1 ,3569    ,307,307,307
BEGIN DESCRIPTION:
WFSJR 082 6.0
END DESCRIPTION:
XS GIS Cut Line= 3
      3750402.25     10250848.09      3750050.65     10250854.88
      3749442.07     10250993.76
#Sta/Elev= 30
  4428.9  274.69  4453.3  274.44  4473.3  272.73  4591.3  267.95  4623.3  266.19
  4693.4  263.98  4713.4  262.41  4723.4   262.8  4743.4  261.71  4783.3  261.66
  4830.2  260.39  4957.8  260.34  4988.6   257.3  4996.8  257.06  4997.1  256.56
  5000.6  256.56  5007.3  258.56  5019.4  260.42  5050.1  261.12  5111.7  265.22
  5132.2  265.27  5146.5  266.98  5189.5  269.72  5255.3   272.1  5306.6  272.52
  5316.8  273.16  5323.6  272.76  5328.7  273.31  5366.6   272.4  5404.8  272.61
#Mann= 4 ,-1 , 0
  4428.9     .17       0  4591.3     .11       0  4957.8     .07       0
  5019.4     .11       0
Bank Sta=4957.8,5019.4
XS Rating Curve= 0 ,0
Exp/Cntr=0.3,0.1

Type RM Length L Ch R = 1 ,3262    ,288,288,288
BEGIN DESCRIPTION:
WFSJR 082 5.0
END DESCRIPTION:
XS GIS Cut Line= 3
      3750490.81     10250553.82      3749639.28       10250671.
      3749371.97     10250979.83
#Sta/Elev= 30
  4409.4     275    4452  274.62  4552.2  272.99    4584  271.95  4624.4  268.87
    4695   265.7  4714.7  263.93  4725.3  264.67  4775.8  261.17  4791.8     262
  4806.1   260.8  4846.4  259.72  4935.8  260.05  4967.6  259.29  4987.8  257.07
  4996.1  254.65  4999.6  254.65  5007.8  257.47  5012.9  257.79    5018  259.28
  5028.1  259.89  5149.3  259.79  5209.8  262.24  5250.2  265.52  5326.6  266.05
  5355.1  267.24    5433  267.45  5440.6  268.64  5468.1  268.19  5677.4   273.6
#Mann= 5 ,-1 , 0
  4409.4     .11       0    4452     .17       0  4552.2     .11       0
  4967.6     .06       0    5018     .11       0
Bank Sta=4967.6,5018
XS Rating Curve= 0 ,0
Exp/Cntr=0.3,0.1

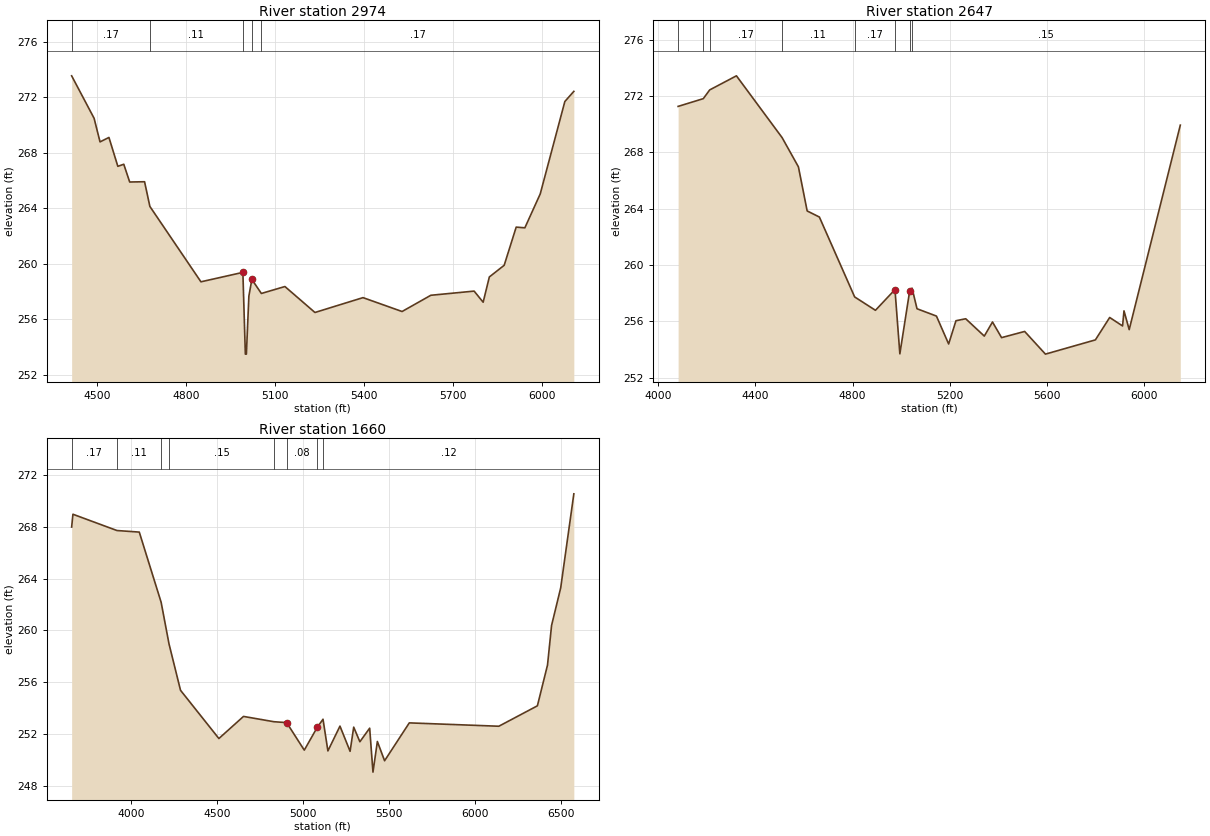
Type RM Length L Ch R = 1 ,2974    ,327,327,327
BEGIN DESCRIPTION:
WFSJR 082 4.0
END DESCRIPTION:
XS GIS Cut Line= 3
      3750423.53     10250357.29      3749952.56     10250370.31
      3748745.93     10250561.29
#Sta/Elev= 30
  4413.1  273.53  4488.8  270.47  4508.8  268.77  4538.8  269.09  4568.8  267.01
  4588.8  267.16  4608.8  265.88  4658.9   265.9  4676.8  264.12  4848.9  258.69
  4990.3  259.37  4998.6  253.48  5002.1  253.48  5010.5  257.66  5020.6  258.86
  5052.6  257.85    5132  258.35  5233.2  256.48  5395.2  257.55  5526.9  256.55
  5623.9  257.72  5769.8  258.02  5800.2  257.22  5821.1  259.04  5871.1  259.88
  5911.6  262.63  5940.8  262.58  5992.6  265.02  6075.6  271.68  6105.9  272.41
#Mann= 5 ,-1 , 0
  4413.1     .17       0  4676.8     .11       0  4990.3     .06       0
  5020.6     .11       0  5052.6     .17       0
Bank Sta=4990.3,5020.6
XS Rating Curve= 0 ,0
Exp/Cntr=0.3,0.1

Type RM Length L Ch R = 1 ,2647    ,987,987,987
BEGIN DESCRIPTION:
WFSJR 082 3.0
END DESCRIPTION:
XS GIS Cut Line= 3
      3750696.92     10250025.26      3749440.41     10250129.42
      3748743.82     10250533.05
#Sta/Elev= 30
  4082.4  271.26    4186  271.81  4212.3  272.43  4322.3  273.43  4510.4  269.04
  4577.3  266.97  4613.3  263.84  4663.5  263.41  4808.6  257.74  4894.2  256.79
  4974.5  258.26  4994.6   253.7  5034.7  258.13  5044.8  258.36  5065.2   256.9
  5145.1  256.38  5195.3   254.4  5225.4  256.05  5265.5  256.19    5342  254.96
  5375.7  255.96    5413  254.85    5508  255.29  5593.5  253.68    5799  254.69
  5857.8  256.28  5910.8  255.68  5916.6  256.75  5938.1  255.42  6148.3  269.93
#Mann= 8 ,-1 , 0
  4082.4     .17       0    4186     .11       0  4212.3     .17       0
  4510.4     .11       0  4808.6     .17       0  4974.5     .09       0
  5034.7     .15       0  5044.8     .15       0
Bank Sta=4974.5,5034.7
XS Rating Curve= 0 ,0
Exp/Cntr=0.3,0.1

Type RM Length L Ch R = 1 ,1660    ,0,0,0
BEGIN DESCRIPTION:
WFSJR 082 2.0
END DESCRIPTION:
XS GIS Cut Line= 4
      3750754.67     10249964.07      3749364.02     10249318.23
      3748999.43     10249854.68      3748713.17      10250536.5
#Sta/Elev= 30
  3654.6     268  3662.1  268.99  3918.3  267.73    4048  267.61  4175.2  262.18
    4221  258.96    4288  255.37  4511.1  251.64  4654.4  253.35  4830.9  252.94
  4905.3  252.87  5007.9  250.74  5084.4  252.53  5116.9  253.13  5145.3  250.68
  5215.5   252.6  5274.4  250.65  5295.4  252.52  5331.3  251.39  5388.3  252.44
  5407.5  249.04  5433.1  251.41  5475.1  249.92  5618.8  252.85  6139.7  252.59
    6364  254.17  6422.8  257.32  6446.5  260.39  6499.5  263.29    6576  270.57
#Mann= 8 ,-1 , 0
  3654.6     .17       0  3918.3     .11       0  4175.2     .17       0
    4221     .15       0  4830.9     .15       0  4905.3     .08       0
  5084.4     .15       0  5116.9     .12       0
Bank Sta=4905.3,5084.4
XS Rating Curve= 0 ,0
Exp/Cntr=0.3,0.1

Chan Stop Cuts=-1
Use User Specified Reach Order=0
Composite Channel Slope=5