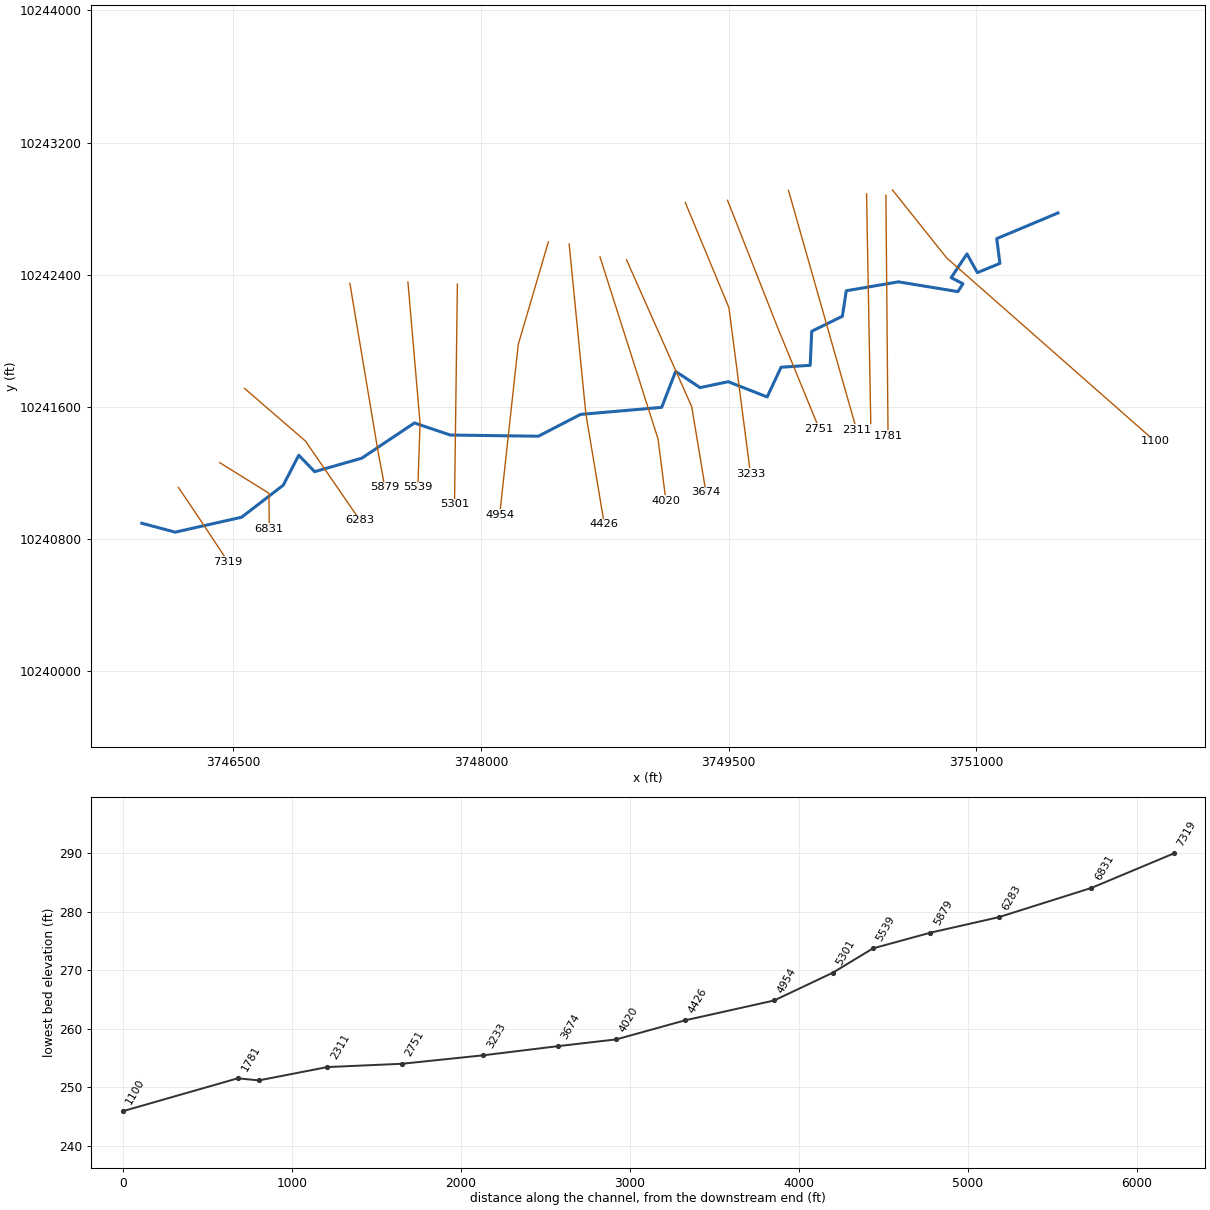
--- WFSJR 084.prj (project) ---

Proj Title=WFSJR 084 Base Level Engineering
Current Plan=p01
Default Exp/Contr=0.3,0.1
English Units
Geom File=g01
Flow File=f01
Plan File=p01
Y Axis Title=Elevation
X Axis Title(PF)=Main Channel Distance
X Axis Title(XS)=Station
BEGIN DESCRIPTION:
WFSJR 084
END DESCRIPTION:
DSS Export Rating Curves= 0
DSS Export Rating Curve Sorted= 0
DSS Export Volume Flow Curves= 0
DXF OffsetX= 0
DXF OffsetY= 0
DXF ScaleX= 1
DXF ScaleY= 10

--- WFSJR 084.p01 (plan) ---

Plan Title=Multiple Run
Program Version=4.10
Short Identifier=Multiple
Geom File=g01
Flow File=f01
Subcritical Flow
K Sum by GR= 0
Std Step Tol= 0.01
Critical Tol= 0.01
Num of Std Step Trials= 20
Max Error Tol= 0.3
Flow Tol Ratio= 0.001
Split Flow NTrial= 30
Split Flow Tol= 0.02
Split Flow Ratio= 0.02
Log Output Level= 0
Friction Slope Method= 1
Unsteady Friction Slope Method= 2
Unsteady Bridges Friction Slope Method= 1
Parabolic Critical Depth
Global Vel Dist= 1 , 1 , 1
Global Log Level= 0
CheckData=True
Encroach Param=-1 ,0,0, 0
BEGIN DESCRIPTION:
Multiple Run
END DESCRIPTION:
Computation Interval=1HOUR
Output Interval=1HOUR
Run HTab= 0
Run UNet= 0
Run PostProcess= 0
Run WQNet= 0
UNET Theta= 1
UNET Theta Warmup= 1
UNET ZTol= 0.02
UNET ZSATol= 0.05
UNET MxIter= 20
UNET MaxInSteps= 0
UNET DtIC= 0
UNET DtMin= 0
UNET MaxCRTS= 20
UNET WFStab= 2
UNET SFStab= 1
UNET WFX= 1
UNET SFX= 1
UNET DSS MLevel= 4
UNET DZMax Abort= 100
UNET Convert EG Bridges= 0
UNET Use Existing IB Tables=-1
UNET Froude Reduction=False
UNET Froude Limit= 1
UNET Froude Power= 10
UNET Time Slicing=0,0, 5
UNET Junction Losses=0
Instantaneous Interval=1HOUR
Write IC File= 0
Write IC File at Sim End=0
Echo Input=False
Echo Parameters=False
Echo Output=False
Write Detailed= 0
WQ AD Non Conservative
WQ ULTIMATE=-1
WQ Max Comp Step=1HOUR
WQ Output Interval=15MIN
WQ Output Selected Increments= 0
WQ Output face flow=0
WQ Output face velocity=0
WQ Output face area=0
WQ Output face dispersion=0
WQ Output cell volume=0
WQ Output cell surface area=0
WQ Output cell continuity=0
WQ Output cumulative cell continuity=0
WQ Output face conc=0
WQ Output face dconc_dx=0
WQ Output face courant=0
WQ Output face peclet=0
WQ Output face adv mass=0
WQ Output face disp mass=0
WQ Output cell mass=0
WQ Output cell source sink temp=0
WQ Output cell source sink nsm=0
WQ Output MaxMinRange=-1
WQ Daily Max Min Mean=-1
WQ Daily Range=0
WQ Daily Time=0
WQ Create Restart=0
WQ Fixed Restart=0
WQ System Summary=0
WQ Use Fixed Temperature=0
Sorting and Armoring Iterations= 10
XS Update Threshold= 0.02
Hydraulics Update Threshold= 0.02
Energy Slope Method= 1
Volume Change Method= 0
XS Weighting Method= 0
Number of US Weighted Cross Sections= 1
Number of DS Weighted Cross Sections= 1
Upstream XS Weight=0.25
Main XS Weight=0.5
Downstream XS Weight=0.25
Number of DS XS's Weighted with US Boundary= 1
Upstream Boundary Weight= 1
Weight of XSs Associated with US Boundary= 0
Number of US XS's Weighted with DS Boundary= 1
Downstream Boundary Weight= 0.5
Weight of XSs Associated with DS Boundary= 0.5
Sediment Output Level= 4
Mass or Volume Output= 0
Output Increment Type= 1
Profile and TS Output Increment= 10
XS Output Flag= 0
XS Output Increment= 10
Disregard all LS=0
Disregard all Conn=0
Disregard all Breaches=0
Disregard all Pumps=0

--- WFSJR 084.f01 (steady flow) ---

Flow Title=Multiple
Program Version=4.10
Number of Profiles= 7
Profile Names=10-year,25-year,50-year,1pct_min,100-year,1pct_plu,500-year
River Rch & RM=WFSJR 084,Reach-1         ,7319
     288     373     491     214     645    1948    1142
River Rch & RM=WFSJR 084,Reach-1         ,5879
     537     721     969     429    1296    3914    2396
Boundary for River Rch & Prof#=WFSJR 084,Reach-1         , 1
Up Type= 0
Dn Type= 3
Dn Slope=0.005
Boundary for River Rch & Prof#=WFSJR 084,Reach-1         , 2
Up Type= 0
Dn Type= 3
Dn Slope=0.005
Boundary for River Rch & Prof#=WFSJR 084,Reach-1         , 3
Up Type= 0
Dn Type= 3
Dn Slope=0.005
Boundary for River Rch & Prof#=WFSJR 084,Reach-1         , 4
Up Type= 0
Dn Type= 3
Dn Slope=0.005
Boundary for River Rch & Prof#=WFSJR 084,Reach-1         , 5
Up Type= 0
Dn Type= 3
Dn Slope=0.005
Boundary for River Rch & Prof#=WFSJR 084,Reach-1         , 6
Up Type= 0
Dn Type= 3
Dn Slope=0.005
Boundary for River Rch & Prof#=WFSJR 084,Reach-1         , 7
Up Type= 0
Dn Type= 3
Dn Slope=0.005
DSS Import GetInterval= 0
DSS Import GetPeak= 0
DSS Import FillOption= 0

--- WFSJR 084.g01 (geometry) ---

Geom Title=Existing Conditions
Program Version=4.10

River Reach=WFSJR 084       ,Reach-1
Reach XY= 30
      3745945.93     10240894.05      3746148.19     10240840.23
       3746550.1     10240930.51      3746802.53     10241124.43
      3746896.54     10241305.95      3746992.37     10241206.73
      3747278.31     10241288.24      3747597.06     10241501.52
       3747814.5     10241428.34      3748347.84     10241421.31
      3748603.31     10241553.34      3749094.71     10241596.05
      3749179.09     10241813.76      3749327.53     10241715.58
       3749498.1     10241751.52      3749733.52     10241659.07
      3749817.89     10241839.02      3749994.19     10241850.74
      3750003.57     10242056.99      3750189.24     10242147.87
      3750212.68      10242302.3      3750528.83     10242356.21
      3750888.98     10242297.09      3750919.19     10242345.01
       3750848.1     10242381.47      3750943.67     10242525.48
      3751006.95     10242411.94      3751143.15     10242467.92
      3751124.14     10242617.92      3751495.31      10242773.7

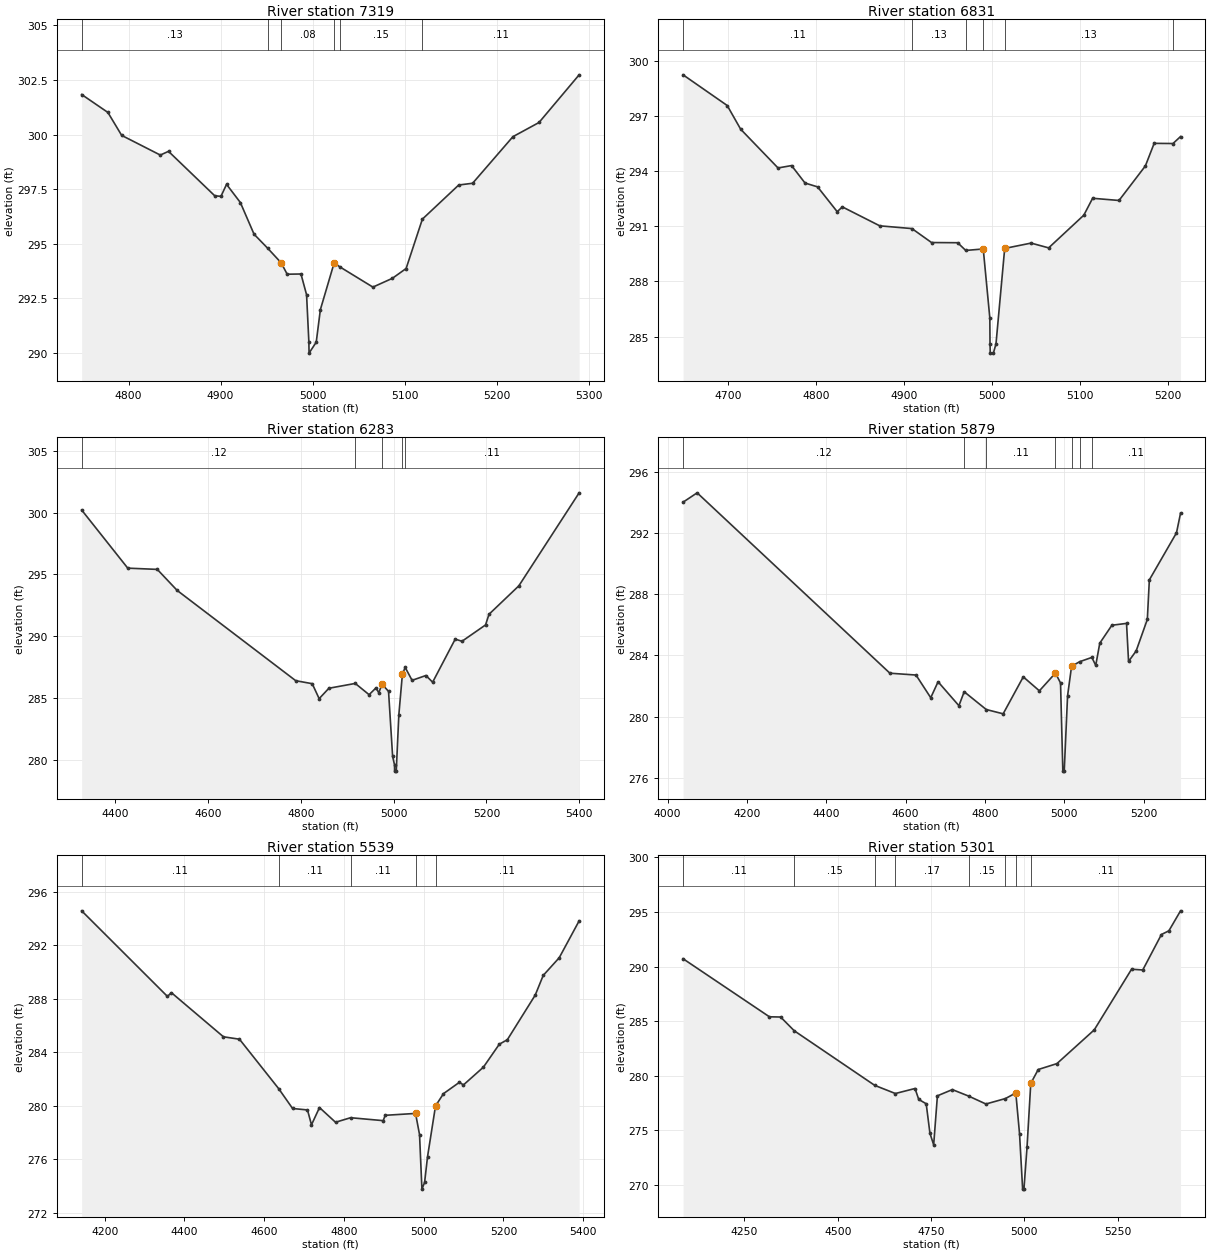
Type RM Length L Ch R = 1 ,7319    ,488,488,488
BEGIN DESCRIPTION:
WFSJR 084 13.0
END DESCRIPTION:
XS GIS Cut Line= 3
      3746167.87     10241111.04      3746307.91     10240902.73
      3746467.85     10240661.07
#Sta/Elev= 30
    4749  301.83  4777.5  301.01  4792.5  299.96  4834.5  299.06  4843.4  299.23
  4893.6   297.2  4900.4  297.17  4906.5  297.72  4921.5  296.89  4936.4  295.44
  4951.4  294.79  4965.9  294.13  4972.4  293.61  4987.4  293.62  4993.5  292.67
    4996   290.5  4996.2     290    5004   290.5  5008.5  291.99  5023.5  294.13
  5029.5  293.95  5065.6  293.02  5086.7  293.42  5101.7  293.87  5119.4  296.13
  5158.9  297.69    5174  297.77  5217.8   299.9  5246.2  300.55  5289.8  302.73
#Mann= 6 ,-1 , 0
    4749     .13       0  4951.4     .13       0  4965.9     .08       0
  5023.5     .13       0  5029.5     .15       0  5119.4     .11       0
Bank Sta=4965.9,5023.5
XS Rating Curve= 0 ,0
Exp/Cntr=0.3,0.1

Type RM Length L Ch R = 1 ,6831    ,548,548,548
BEGIN DESCRIPTION:
WFSJR 084 12.0
END DESCRIPTION:
XS GIS Cut Line= 3
      3746417.86     10241261.06      3746716.07     10241075.74
      3746717.85     10240861.04
#Sta/Elev= 30
  4648.9  299.25  4699.1  297.58  4714.4  296.29  4756.9  294.18  4772.3  294.31
  4787.6  293.36  4801.9  293.15  4824.2   291.8  4830.1  292.06  4872.6  291.03
  4909.2  290.88  4931.5  290.12  4961.2  290.11  4970.4  289.69  4990.3  289.77
  4997.8  286.01    4998   284.6  4998.3   284.1  5001.8   284.1  5004.8   284.6
  5014.7   289.8  5044.7  290.09  5064.7  289.83  5104.7  291.61  5114.7  292.53
  5144.7  292.41  5174.7  294.29  5184.7  295.52  5206.1  295.51  5214.7  295.89
#Mann= 6 ,-1 , 0
  4648.9     .11       0  4909.2     .13       0  4970.4     .13       0
  4990.3     .08       0  5014.7     .13       0  5206.1     .11       0
Bank Sta=4990.3,5014.7
XS Rating Curve= 0 ,0
Exp/Cntr=0.3,0.1

Type RM Length L Ch R = 1 ,6283    ,404,404,404
BEGIN DESCRIPTION:
WFSJR 084 11.0
END DESCRIPTION:
XS GIS Cut Line= 3
      3746567.82      10241711.1      3746937.13     10241391.82
      3747267.85     10240911.08
#Sta/Elev= 30
  4328.1  300.21  4427.4  295.51    4491  295.41  4533.8  293.71  4789.3  286.41
  4824.8  286.17  4839.7  284.96  4860.7   285.8  4917.5  286.19  4947.3  285.28
  4962.2  285.83  4968.2  285.43    4975  286.13  4989.2  285.55    4998  280.29
  5002.1   279.6  5002.3   279.1  5005.8   279.1  5011.4  283.66    5019  286.92
    5025  287.49  5039.9  286.44  5069.7  286.83  5084.2  286.29  5132.8  289.77
  5147.5   289.6  5198.2  290.92  5205.6  291.78  5269.9  294.08  5399.8   301.6
#Mann= 5 ,-1 , 0
  4328.1     .12       0  4917.5     .12       0    4975     .06       0
    5019     .12       0    5025     .11       0
Bank Sta=4975,5019
XS Rating Curve= 0 ,0
Exp/Cntr=0.3,0.1

Type RM Length L Ch R = 1 ,5879    ,340,340,340
BEGIN DESCRIPTION:
WFSJR 084 10.0
END DESCRIPTION:
XS GIS Cut Line= 3
      3747206.23     10242346.64       3747375.5     10241335.39
      3747417.85     10241111.07
#Sta/Elev= 30
  4039.2     294  4074.7  294.61  4560.4  282.84  4626.2  282.72  4663.3  281.24
  4681.8  282.28  4734.3  280.72  4747.6  281.63  4803.2  280.47  4845.8  280.19
  4896.5   282.6  4937.1  281.69  4977.6  282.85  4990.4   282.2  4996.2  276.45
  4999.7  276.45  5008.1  281.36  5018.2  283.29  5038.5  283.59  5069.3  283.87
  5079.1  283.35  5089.3   284.8  5119.8  285.97  5156.7  286.09  5161.8  283.61
  5180.9  284.29  5209.1  286.35  5214.2  288.93  5282.6     292  5292.8  293.28
#Mann= 7 ,-1 , 0
  4039.2     .12       0  4747.6     .12       0  4803.2     .11       0
  4977.6     .08       0  5018.2     .12       0  5038.5     .11       0
  5069.3     .11       0
#XS Ineff= 2 ,-1
                          5156.7    5225  286.09
Permanent Ineff=
       F       F
Bank Sta=4977.6,5018.2
XS Rating Curve= 0 ,0
Exp/Cntr=0.3,0.1

Type RM Length L Ch R = 1 ,5539    ,238,238,238
BEGIN DESCRIPTION:
WFSJR 084 9.0
END DESCRIPTION:
XS GIS Cut Line= 3
      3747557.79     10242355.39      3747631.17     10241500.74
      3747617.85     10241111.06
#Sta/Elev= 30
  4142.2  294.58  4357.3  288.18  4367.3  288.46  4497.8  285.16    4538  284.98
  4636.4  281.28  4671.2   279.8  4708.6  279.69  4718.6  278.58  4738.7  279.87
  4778.9  278.77  4816.7  279.11  4898.5  278.89  4903.5  279.29  4979.6  279.43
  4989.6  277.85  4995.6  273.77  5002.3  274.27  5009.7   276.2  5029.7  279.99
  5049.7  280.91  5089.7  281.76  5099.7  281.56  5149.8  282.89  5189.8  284.61
  5209.8  284.94  5279.8  288.28  5299.8  289.75  5339.9  291.07  5389.9  293.83
#Mann= 5 ,-1 , 0
  4142.2     .11       0  4636.4     .11       0  4816.7     .11       0
  4979.6     .06       0  5029.7     .11       0
Bank Sta=4979.6,5029.7
XS Rating Curve= 0 ,0
Exp/Cntr=0.3,0.1

Type RM Length L Ch R = 1 ,5301    ,347,347,347
BEGIN DESCRIPTION:
WFSJR 084 8.0
END DESCRIPTION:
XS GIS Cut Line= 2
      3747857.27     10242342.34      3747839.91     10241009.86
#Sta/Elev= 30
  4085.8  290.72  4317.1   285.4  4347.1  285.38  4383.6  284.12  4599.1  279.12
  4654.5  278.37  4707.1  278.83  4717.1  277.83  4737.1  277.43  4747.1  274.73
  4757.1  273.67  4767.1  278.16  4807.1  278.73  4851.1  278.13  4897.1  277.41
  4949.4  277.91  4977.1  278.42  4987.1  274.69  4995.4  269.61  4998.9  269.61
  5007.2  273.46  5017.2   279.3  5037.2  280.57  5087.2  281.11  5187.2   284.2
  5287.2  289.76  5317.2  289.69  5367.2  292.94  5387.2  293.28  5418.4  295.11
#Mann= 8 ,-1 , 0
  4085.8     .11       0  4383.6     .15       0  4599.1     .11       0
  4654.5     .17       0  4851.1     .15       0  4949.4     .11       0
  4977.1     .07       0  5017.2     .11       0
#XS Ineff= 1 ,-1
    4550  4977.1  278.42
Permanent Ineff=
       F
Bank Sta=4977.1,5017.2
XS Rating Curve= 0 ,0
Exp/Cntr=0.3,0.1

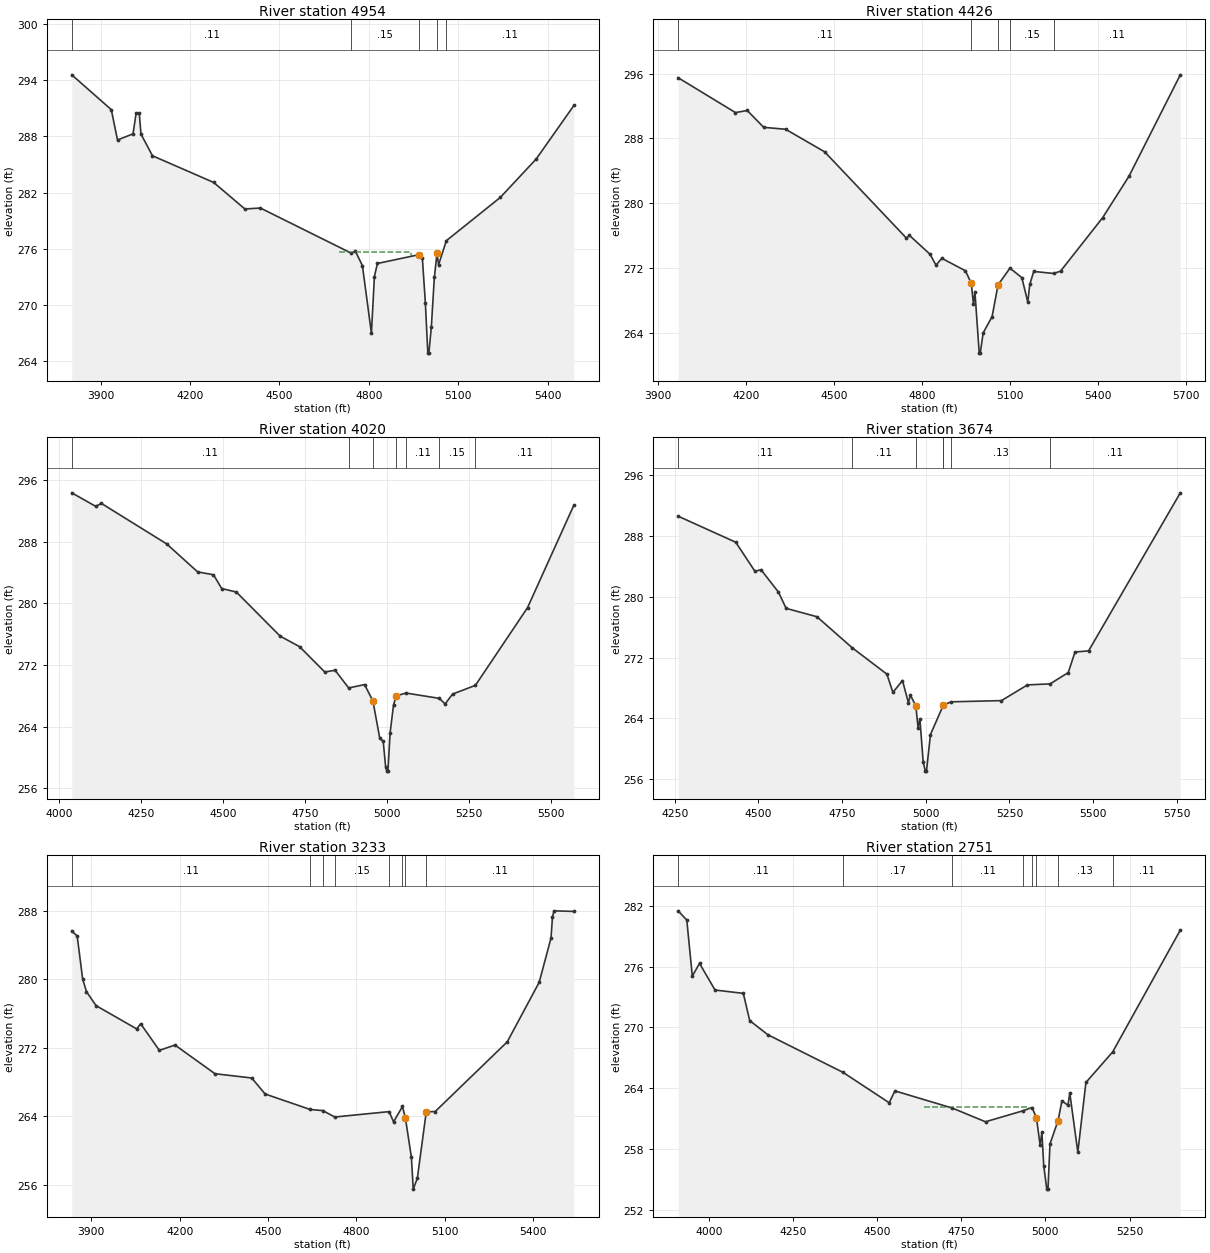
Type RM Length L Ch R = 1 ,4954    ,528,528,528
BEGIN DESCRIPTION:
Mapping XS cbff2aa5
END DESCRIPTION:
XS GIS Cut Line= 3
      3748408.48     10242598.38      3748226.19     10241977.75
      3748113.42     10240945.44
#Sta/Elev= 30
  3802.9  294.57  3935.6  290.85  3956.4  287.61  4008.5  288.27    4019   290.5
  4029.4  290.46  4035.2  288.24  4073.8  285.93  4279.2  283.08  4383.8  280.25
  4435.9  280.35  4740.5  275.54    4755  275.73  4778.4   274.2  4808.6  266.98
  4818.6  273.04  4828.7  274.43  4969.5  275.38  4979.6     275  4989.6  270.26
  4997.9  264.86  5001.4  264.86  5009.7  267.65  5019.8  272.94  5028.9  275.56
  5033.9  274.28    5060  276.86  5241.1  281.48  5361.8  285.59  5488.2   291.3
#Mann= 5 ,-1 , 0
  3802.9     .11       0  4740.5     .15       0  4969.5     .09       0
  5028.9     .15       0    5060     .11       0
#XS Ineff= 1 ,-1
    4700  4942.6  275.69
Permanent Ineff=
       F
Bank Sta=4969.5,5028.9
XS Rating Curve= 0 ,0
Exp/Cntr=0.3,0.1

Type RM Length L Ch R = 1 ,4426    ,406,406,406
BEGIN DESCRIPTION:
WFSJR 084 7.0
END DESCRIPTION:
XS GIS Cut Line= 3
      3748534.35     10242585.44      3748635.08     10241559.07
      3748747.02     10240888.35
#Sta/Elev= 30
  3968.7  295.51    4164   291.2  4204.2  291.46    4260  289.38  4334.8  289.14
  4467.9  286.35  4746.8  275.67  4756.8  276.02  4827.2  273.68  4847.3  272.34
  4867.4  273.18  4947.7  271.64  4967.8  270.08    4975   267.5  4980.1  269.01
  4994.7  261.46  4998.2  261.46  5008.1  263.96  5038.5  265.97  5058.8  269.89
  5099.4  271.97  5139.9  270.79  5160.2  267.78    5167  269.95  5180.5  271.56
  5248.2  271.31  5271.7  271.59  5415.2   278.2  5504.9  283.32    5680  295.87
#Mann= 5 ,-1 , 0
  3968.7     .11       0  4967.8     .06       0  5058.8     .11       0
  5099.4     .15       0  5248.2     .11       0
#XS Ineff= 1 ,-1
  5099.4    5300  271.97
Permanent Ineff=
       F
Bank Sta=4967.8,5058.8
XS Rating Curve= 0 ,0
Exp/Cntr=0.3,0.1

Type RM Length L Ch R = 1 ,4020    ,346,346,346
BEGIN DESCRIPTION:
WFSJR 084 6.0
END DESCRIPTION:
XS GIS Cut Line= 3
      3748720.99     10242507.24      3749072.55     10241404.84
      3749120.29     10241031.57
#Sta/Elev= 30
  4037.6  294.32  4110.9  292.56    4128  292.95  4327.5  287.69  4421.9  284.06
  4470.4  283.69  4495.4   281.9    4540  281.45  4674.1  275.72  4733.2  274.36
  4810.3  271.07  4841.8   271.3  4883.1     269  4931.7  269.44  4957.2  267.32
  4978.2  262.46  4988.7  262.08  4996.1  258.74  4999.6  258.21  5003.1  258.21
  5009.7  263.17  5020.2   266.8  5028.3  267.98  5058.3  268.34    5160  267.65
  5177.7  266.93  5200.3   268.2  5270.2  269.34  5429.4  279.42    5571  292.73
#Mann= 7 ,-1 , 0
  4037.6     .11       0  4883.1     .15       0  4957.2     .09       0
  5028.3     .15       0  5058.3     .11       0    5160     .15       0
  5270.2     .11       0
Bank Sta=4957.2,5028.3
XS Rating Curve= 0 ,0
Exp/Cntr=0.3,0.1

Type RM Length L Ch R = 1 ,3674    ,441,441,441
BEGIN DESCRIPTION:
WFSJR 084 5.0
END DESCRIPTION:
XS GIS Cut Line= 3
      3748881.57     10242489.92      3749276.54     10241600.15
       3749363.1     10241080.81
#Sta/Elev= 30
  4260.4  290.63  4432.4   287.2  4489.9  283.36  4507.7  283.59  4559.7  280.65
  4582.9  278.49  4674.9  277.39    4780  273.31    4884  269.82  4901.8  267.42
  4930.5  268.98  4948.3  266.04  4953.8   267.1  4970.3  265.64  4977.1  262.78
  4982.5  263.93  4992.2   258.3  4998.6  257.05  5002.1  257.05  5014.1  261.87
  5052.3  265.73  5052.4  265.74  5075.6  266.18  5226.1  266.34  5303.9  268.41
  5371.3  268.54  5425.6  270.03  5445.9  272.74  5486.4  272.89  5760.4  293.71
#Mann= 7 ,-1 , 0
  4260.4     .11       0    4780     .11       0  4970.3     .07       0
  5052.3     .11       0  5052.4     .11       0  5075.6     .13       0
  5371.3     .11       0
Bank Sta=4970.3,5052.3
XS Rating Curve= 0 ,0
Exp/Cntr=0.3,0.1

Type RM Length L Ch R = 1 ,3233    ,482,482,482
BEGIN DESCRIPTION:
Mapping XS f9bf6982
END DESCRIPTION:
XS GIS Cut Line= 3
      3749237.49      10242837.1      3749502.23     10242199.11
      3749632.19     10241194.12
#Sta/Elev= 30
  3833.9  285.67  3852.3  285.07  3870.7  280.08  3883.7  278.58  3916.2  276.94
  4054.1  274.22  4067.8  274.82  4131.1  271.71  4184.3  272.33  4319.9  268.98
  4444.7  268.48    4490  266.61  4642.9   264.8  4685.8  264.67  4726.4  263.92
  4910.9  264.55    4926  263.35  4956.2  265.15  4966.3  263.77  4986.5  259.21
  4992.7  255.49  5006.7  256.76  5036.9  264.52  5067.2  264.56  5311.7   272.7
  5420.1  279.66  5460.3  284.84  5465.3   287.3  5470.5  288.02    5538  287.95
#Mann= 8 ,-1 , 0
  3833.9     .11       0  4642.9     .17       0  4685.8     .11       0
  4726.4     .15       0  4910.9     .11       0  4956.2     .11       0
  4966.3     .06       0  5036.9     .11       0
#XS Ineff= 1 ,-1
    4560  4956.2  265.15
Permanent Ineff=
       F
Bank Sta=4966.3,5036.9
XS Rating Curve= 0 ,0
Exp/Cntr=0.3,0.1

Type RM Length L Ch R = 1 ,2751    ,440,440,440
BEGIN DESCRIPTION:
WFSJR 084 4.0
END DESCRIPTION:
XS GIS Cut Line= 3
      3749493.57     10242850.11      3749795.41     10242083.41
      3750049.02     10241465.83
#Sta/Elev= 30
  3909.1  281.52  3934.7   280.6  3951.1  275.07  3972.5  276.33  4018.6   273.7
  4102.6  273.37  4121.6  270.68  4175.7  269.28  4398.7  265.57  4535.9  262.57
  4552.9  263.74  4723.6  262.04  4822.1  260.69  4933.8  261.78  4960.2   262.1
  4973.4  261.08  4984.2   258.4  4989.6  259.67    4995  256.32  5004.1  254.04
  5007.6  254.04  5013.6  258.51  5037.6  260.81  5049.1  262.76  5066.9  262.32
  5072.4  263.52  5096.3  257.69  5120.3  264.57  5199.6  267.58  5400.7  279.62
#Mann= 8 ,-1 , 0
  3909.1     .11       0  4398.7     .17       0  4723.6     .11       0
  4933.8     .15       0  4960.2     .13       0  4973.4     .09       0
  5037.6     .13       0  5199.6     .11       0
#XS Ineff= 2 ,-1
    4640  4951.8  262.14  5072.4    5120  263.52
Permanent Ineff=
       F       F
Bank Sta=4973.4,5037.6
XS Rating Curve= 0 ,0
Exp/Cntr=0.3,0.1

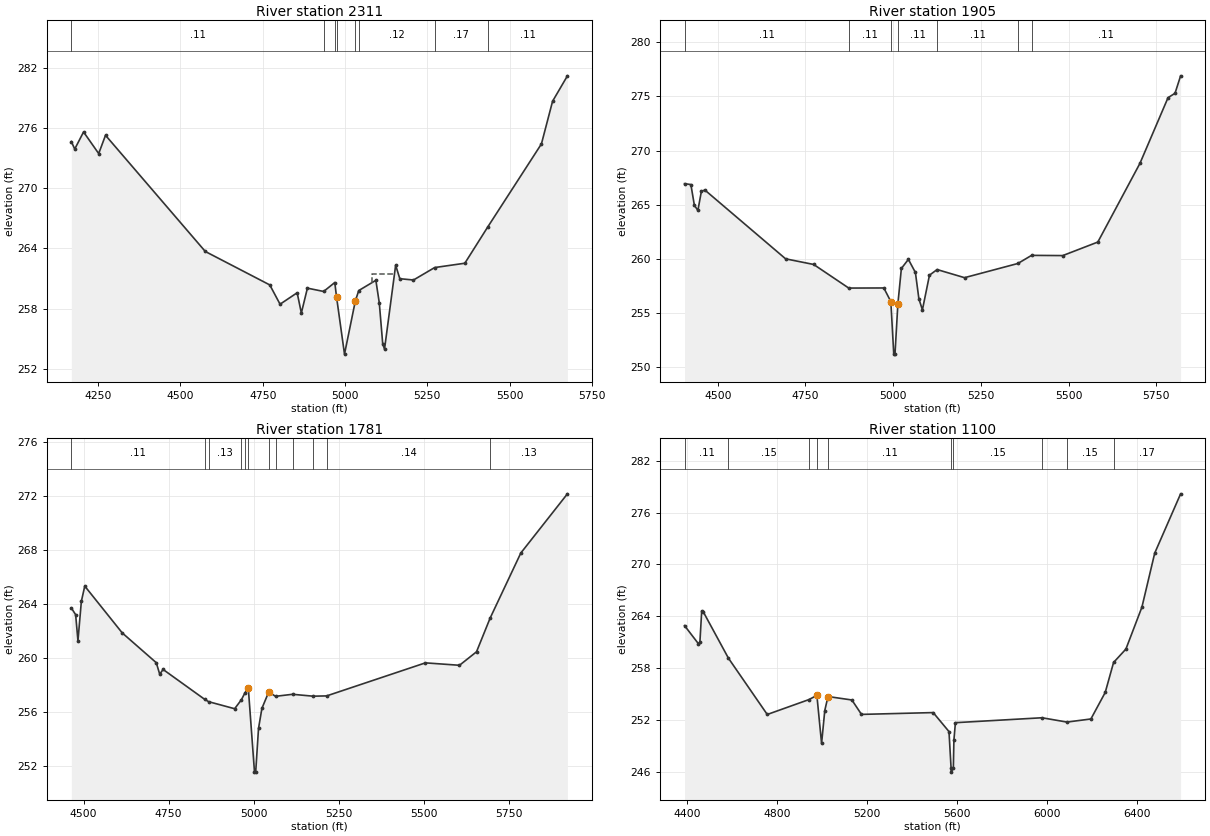
Type RM Length L Ch R = 1 ,2311    ,406,406,406
BEGIN DESCRIPTION:
Mapping XS 121516ee
END DESCRIPTION:
XS GIS Cut Line= 2
      3749862.47     10242910.95      3750274.81     10241461.25
#Sta/Elev= 30
  4168.4  274.64  4178.7   273.9  4205.5   275.6  4251.5  273.45  4272.2  275.27
  4575.4   263.7  4771.3  260.37  4802.5  258.45  4854.5  259.59  4867.2  257.57
  4885.6  260.05  4934.9  259.72  4968.8  260.61    4974   259.2  4998.3  253.48
  5031.2  258.77  5041.6  259.81  5093.6  260.83    5104  258.58  5114.4  254.51
  5119.9  253.98  5153.7  262.33  5166.4  260.99  5207.9  260.86  5272.2   262.1
  5363.9  262.53  5433.3  266.13  5596.6  274.41  5630.5  278.66  5675.6  281.19
#Mann= 8 ,-1 , 0
  4168.4     .11       0  4934.9     .12       0  4968.8     .12       0
    4974     .08       0  5031.2     .12       0  5041.6     .12       0
  5272.2     .17       0  5433.3     .11       0
#XS Ineff= 3 ,-1
    4680  4968.8  260.61  5080.8  5150.4  261.42  5153.7    5360  262.33
Permanent Ineff=
       F       F       F
Bank Sta=4974,5031.2
XS Rating Curve= 0 ,0
Exp/Cntr=0.3,0.1

Type RM Length L Ch R = 1 ,1905    ,124,124,124
BEGIN DESCRIPTION:
WFSJR 084 3.0
END DESCRIPTION:
XS GIS Cut Line= 2
      3750335.57      10242889.2      3750361.59     10241475.14
#Sta/Elev= 30
  4405.2  266.94  4423.3  266.86  4433.3  264.94  4443.3  264.47  4453.3  266.24
  4463.3  266.35  4693.4     260  4773.4  259.48  4873.4   257.3  4973.4  257.31
  4993.4  256.05  5001.7   251.2  5005.2   251.2  5013.4  255.82  5023.4  259.11
  5043.4  259.95  5063.4  258.74  5073.4   256.3  5083.4  255.29  5103.5  258.49
  5125.3  259.01  5203.5  258.26  5355.5  259.57  5394.6  260.32  5483.5   260.3
  5583.5  261.55  5703.6  268.82  5783.6  274.88  5803.6  275.29  5819.5   276.9
#Mann= 7 ,-1 , 0
  4405.2     .11       0  4873.4     .11       0  4993.4     .06       0
  5013.4     .11       0  5125.3     .11       0  5355.5     .17       0
  5394.6     .11       0
#XS Ineff= 1 ,-1
  5043.4    5480  259.95
Permanent Ineff=
       F
Bank Sta=4993.4,5013.4
XS Rating Curve= 0 ,0
Exp/Cntr=0.3,0.1

Type RM Length L Ch R = 1 ,1781    ,681,681,681
BEGIN DESCRIPTION:
WFSJR 084 2.0
END DESCRIPTION:
XS GIS Cut Line= 2
      3750452.76      10242880.5      3750465.76     10241424.16
#Sta/Elev= 30
  4464.3  263.73  4476.9  263.23  4483.7   261.3  4493.7  264.22  4503.7  265.35
  4613.7  261.88  4713.7  259.67  4723.7  258.82  4733.7  259.17  4855.5  256.96
  4867.6  256.78  4943.7  256.26  4963.7  256.93  4973.8  257.43  4983.8   257.8
    5002  251.56  5005.5  251.56  5013.8   254.8  5023.8  256.29  5043.8   257.5
  5063.8  257.18  5113.8  257.33  5173.8  257.19  5213.8  257.21  5503.8  259.66
  5603.8  259.48  5653.8  260.48  5693.8  262.98  5783.8   267.8  5920.7  272.19
#Mann= 12 ,-1 , 0
  4464.3     .11       0  4855.5     .15       0  4867.6     .13       0
  4963.7     .12       0  4973.8     .12       0  4983.8     .06       0
  5043.8     .12       0  5063.8     .13       0  5113.8     .13       0
  5173.8     .13       0  5213.8     .14       0  5693.8     .13       0
Bank Sta=4983.8,5043.8
XS Rating Curve= 0 ,0
Exp/Cntr=0.3,0.1

Type RM Length L Ch R = 1 ,1100    ,0,0,0
BEGIN DESCRIPTION:
WFSJR 084 1.0
END DESCRIPTION:
XS GIS Cut Line= 3
      3750492.69     10242912.64      3750820.81     10242501.19
      3752081.26     10241391.79
#Sta/Elev= 30
    4388  262.91    4450   260.8  4456.4  261.01  4464.4  264.63  4470.8  264.53
  4583.3  259.13  4755.8  252.61  4940.4  254.33  4976.4  254.82  4997.3  249.25
  5011.5  253.07  5025.8  254.69    5132  254.29  5174.7  252.62  5493.5  252.83
  5563.7  250.63  5572.9  246.43  5573.4  245.93  5583.1  246.43  5585.5  249.61
  5592.2  251.66  5977.3  252.23  6088.1  251.73  6194.6  252.09  6258.2  255.16
  6295.4  258.64  6350.2  260.19  6421.4  265.05  6478.3  271.31  6593.4  278.18
#Mann= 10 ,-1 , 0
    4388     .11       0  4583.3     .15       0  4940.4     .11       0
  4976.4     .06       0  5025.8     .11       0  5572.9     .12       0
  5583.1     .15       0  5977.3     .17       0  6088.1     .15       0
  6295.4     .17       0
Bank Sta=4976.4,5025.8
XS Rating Curve= 0 ,0
Exp/Cntr=0.3,0.1

Chan Stop Cuts=-1
Use User Specified Reach Order=0
Composite Channel Slope=5