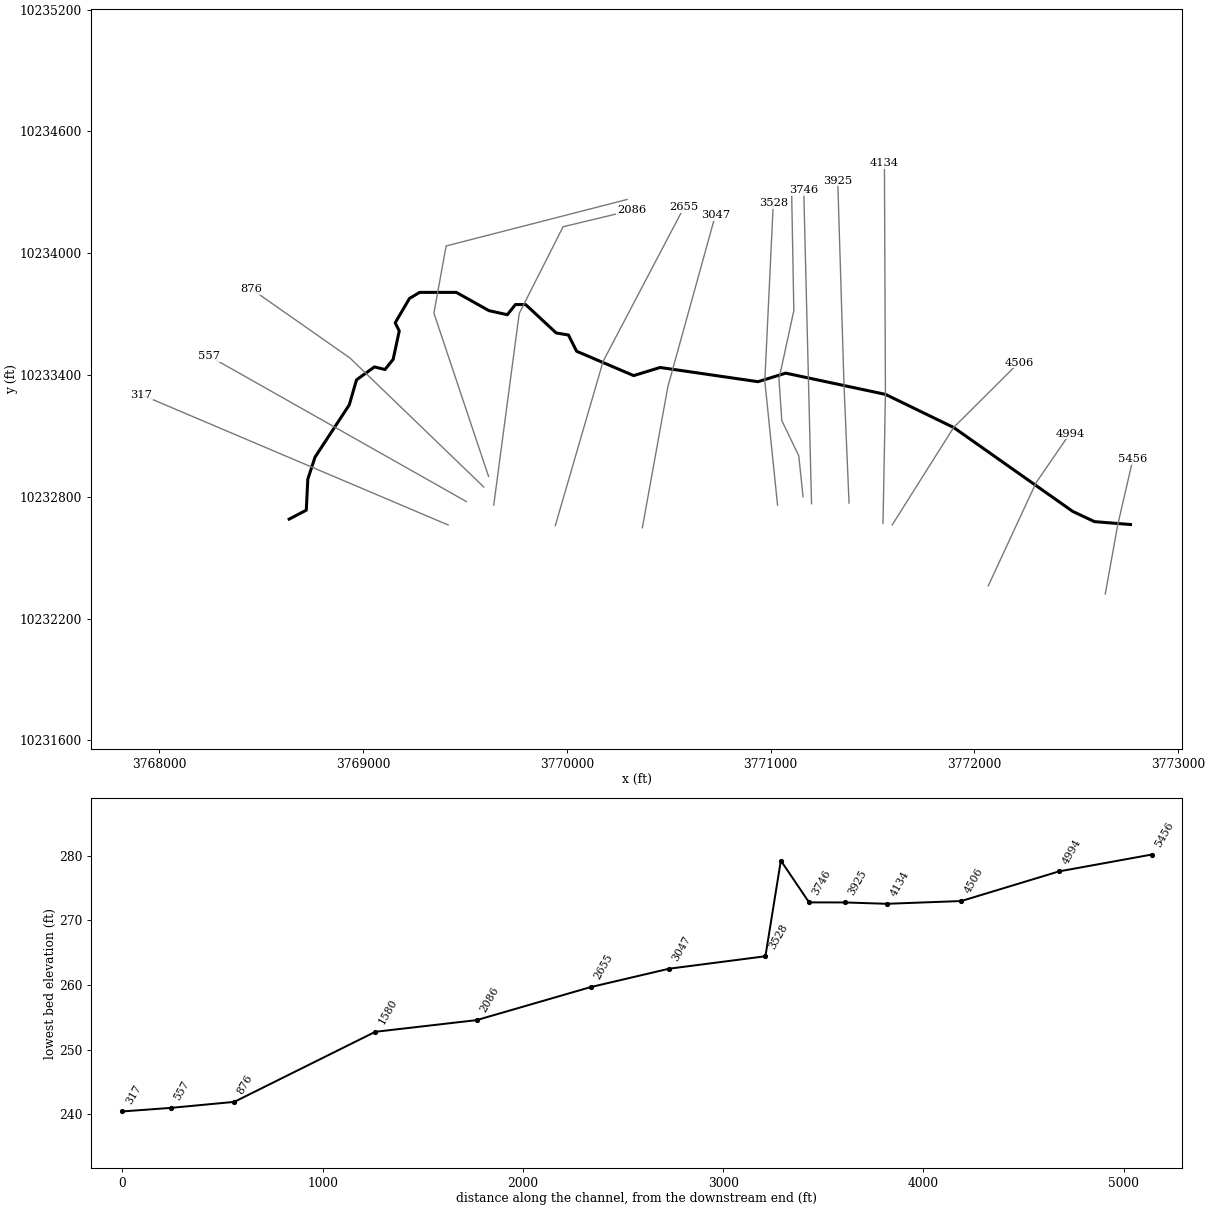
--- WFSJR 085.prj (project) ---

Proj Title=WFSJR 085 Base Level Engineering
Current Plan=p01
Default Exp/Contr=0.3,0.1
English Units
Geom File=g01
Flow File=f01
Plan File=p01
Y Axis Title=Elevation
X Axis Title(PF)=Main Channel Distance
X Axis Title(XS)=Station
BEGIN DESCRIPTION:
WFSJR 085
END DESCRIPTION:
DSS Export Rating Curves= 0
DSS Export Rating Curve Sorted= 0
DSS Export Volume Flow Curves= 0
DXF OffsetX= 0
DXF OffsetY= 0
DXF ScaleX= 1
DXF ScaleY= 10

--- WFSJR 085.p01 (plan) ---

Plan Title=Multiple Run
Program Version=4.10
Short Identifier=Multiple
Geom File=g01
Flow File=f01
Subcritical Flow
K Sum by GR= 0
Std Step Tol= 0.01
Critical Tol= 0.01
Num of Std Step Trials= 20
Max Error Tol= 0.3
Flow Tol Ratio= 0.001
Split Flow NTrial= 30
Split Flow Tol= 0.02
Split Flow Ratio= 0.02
Log Output Level= 0
Friction Slope Method= 1
Unsteady Friction Slope Method= 2
Unsteady Bridges Friction Slope Method= 1
Parabolic Critical Depth
Global Vel Dist= 1 , 1 , 1
Global Log Level= 0
CheckData=True
Encroach Param=-1 ,0,0, 0
BEGIN DESCRIPTION:
Multiple Run
END DESCRIPTION:
Computation Interval=1HOUR
Output Interval=1HOUR
Run HTab= 0
Run UNet= 0
Run PostProcess= 0
Run WQNet= 0
UNET Theta= 1
UNET Theta Warmup= 1
UNET ZTol= 0.02
UNET ZSATol= 0.05
UNET MxIter= 20
UNET MaxInSteps= 0
UNET DtIC= 0
UNET DtMin= 0
UNET MaxCRTS= 20
UNET WFStab= 2
UNET SFStab= 1
UNET WFX= 1
UNET SFX= 1
UNET DSS MLevel= 4
UNET DZMax Abort= 100
UNET Convert EG Bridges= 0
UNET Use Existing IB Tables=-1
UNET Froude Reduction=False
UNET Froude Limit= 1
UNET Froude Power= 10
UNET Time Slicing=0,0, 5
UNET Junction Losses=0
Instantaneous Interval=1HOUR
Write IC File= 0
Write IC File at Sim End=0
Echo Input=False
Echo Parameters=False
Echo Output=False
Write Detailed= 0
WQ AD Non Conservative
WQ ULTIMATE=-1
WQ Max Comp Step=1HOUR
WQ Output Interval=15MIN
WQ Output Selected Increments= 0
WQ Output face flow=0
WQ Output face velocity=0
WQ Output face area=0
WQ Output face dispersion=0
WQ Output cell volume=0
WQ Output cell surface area=0
WQ Output cell continuity=0
WQ Output cumulative cell continuity=0
WQ Output face conc=0
WQ Output face dconc_dx=0
WQ Output face courant=0
WQ Output face peclet=0
WQ Output face adv mass=0
WQ Output face disp mass=0
WQ Output cell mass=0
WQ Output cell source sink temp=0
WQ Output cell source sink nsm=0
WQ Output MaxMinRange=-1
WQ Daily Max Min Mean=-1
WQ Daily Range=0
WQ Daily Time=0
WQ Create Restart=0
WQ Fixed Restart=0
WQ System Summary=0
WQ Use Fixed Temperature=0
Sorting and Armoring Iterations= 10
XS Update Threshold= 0.02
Hydraulics Update Threshold= 0.02
Energy Slope Method= 1
Volume Change Method= 0
XS Weighting Method= 0
Number of US Weighted Cross Sections= 1
Number of DS Weighted Cross Sections= 1
Upstream XS Weight=0.25
Main XS Weight=0.5
Downstream XS Weight=0.25
Number of DS XS's Weighted with US Boundary= 1
Upstream Boundary Weight= 1
Weight of XSs Associated with US Boundary= 0
Number of US XS's Weighted with DS Boundary= 1
Downstream Boundary Weight= 0.5
Weight of XSs Associated with DS Boundary= 0.5
Sediment Output Level= 4
Mass or Volume Output= 0
Output Increment Type= 1
Profile and TS Output Increment= 10
XS Output Flag= 0
XS Output Increment= 10
Disregard all LS=0
Disregard all Conn=0
Disregard all Breaches=0
Disregard all Pumps=0

--- WFSJR 085.f01 (steady flow) ---

Flow Title=Multiple
Program Version=4.10
Number of Profiles= 7
Profile Names=10-year,25-year,50-year,1pct_min,100-year,1pct_plu,500-year
River Rch & RM=WFSJR 085,Reach-1         ,5456
     466     622     835     369    1114    3364    2050
River Rch & RM=WFSJR 085,Reach-1         ,3925
     763    1044    1423     637    1925    5813    3645
Boundary for River Rch & Prof#=WFSJR 085,Reach-1         , 1
Up Type= 0
Dn Type= 3
Dn Slope=0.005
Boundary for River Rch & Prof#=WFSJR 085,Reach-1         , 2
Up Type= 0
Dn Type= 3
Dn Slope=0.005
Boundary for River Rch & Prof#=WFSJR 085,Reach-1         , 3
Up Type= 0
Dn Type= 3
Dn Slope=0.005
Boundary for River Rch & Prof#=WFSJR 085,Reach-1         , 4
Up Type= 0
Dn Type= 3
Dn Slope=0.005
Boundary for River Rch & Prof#=WFSJR 085,Reach-1         , 5
Up Type= 0
Dn Type= 3
Dn Slope=0.005
Boundary for River Rch & Prof#=WFSJR 085,Reach-1         , 6
Up Type= 0
Dn Type= 3
Dn Slope=0.005
Boundary for River Rch & Prof#=WFSJR 085,Reach-1         , 7
Up Type= 0
Dn Type= 3
Dn Slope=0.005
DSS Import GetInterval= 0
DSS Import GetPeak= 0
DSS Import FillOption= 0

--- WFSJR 085.g01 (geometry) ---

Geom Title=Existing Conditions
Program Version=4.10

River Reach=WFSJR 085       ,Reach-1
Reach XY= 30
      3772765.55     10232663.17      3772588.65     10232677.45
      3772481.81     10232727.97      3771897.92     10233141.25
      3771563.33     10233304.41      3771074.14     10233408.98
      3770938.23     10233366.84      3770458.23     10233436.84
      3770328.23     10233396.84      3770048.23     10233516.84
      3770008.23     10233596.84      3769948.23     10233606.84
      3769798.23     10233746.84      3769748.23     10233746.84
      3769708.23     10233696.84      3769618.23     10233716.84
      3769458.23     10233806.84      3769278.23     10233806.84
      3769228.23     10233776.84      3769158.23     10233656.84
      3769178.23     10233616.84      3769148.23     10233476.84
      3769108.23     10233426.84       3769056.5     10233439.63
      3768968.49     10233375.96      3768933.03     10233252.78
      3768765.06     10232995.21      3768729.59     10232886.96
      3768722.13     10232733.92      3768638.15     10232689.83

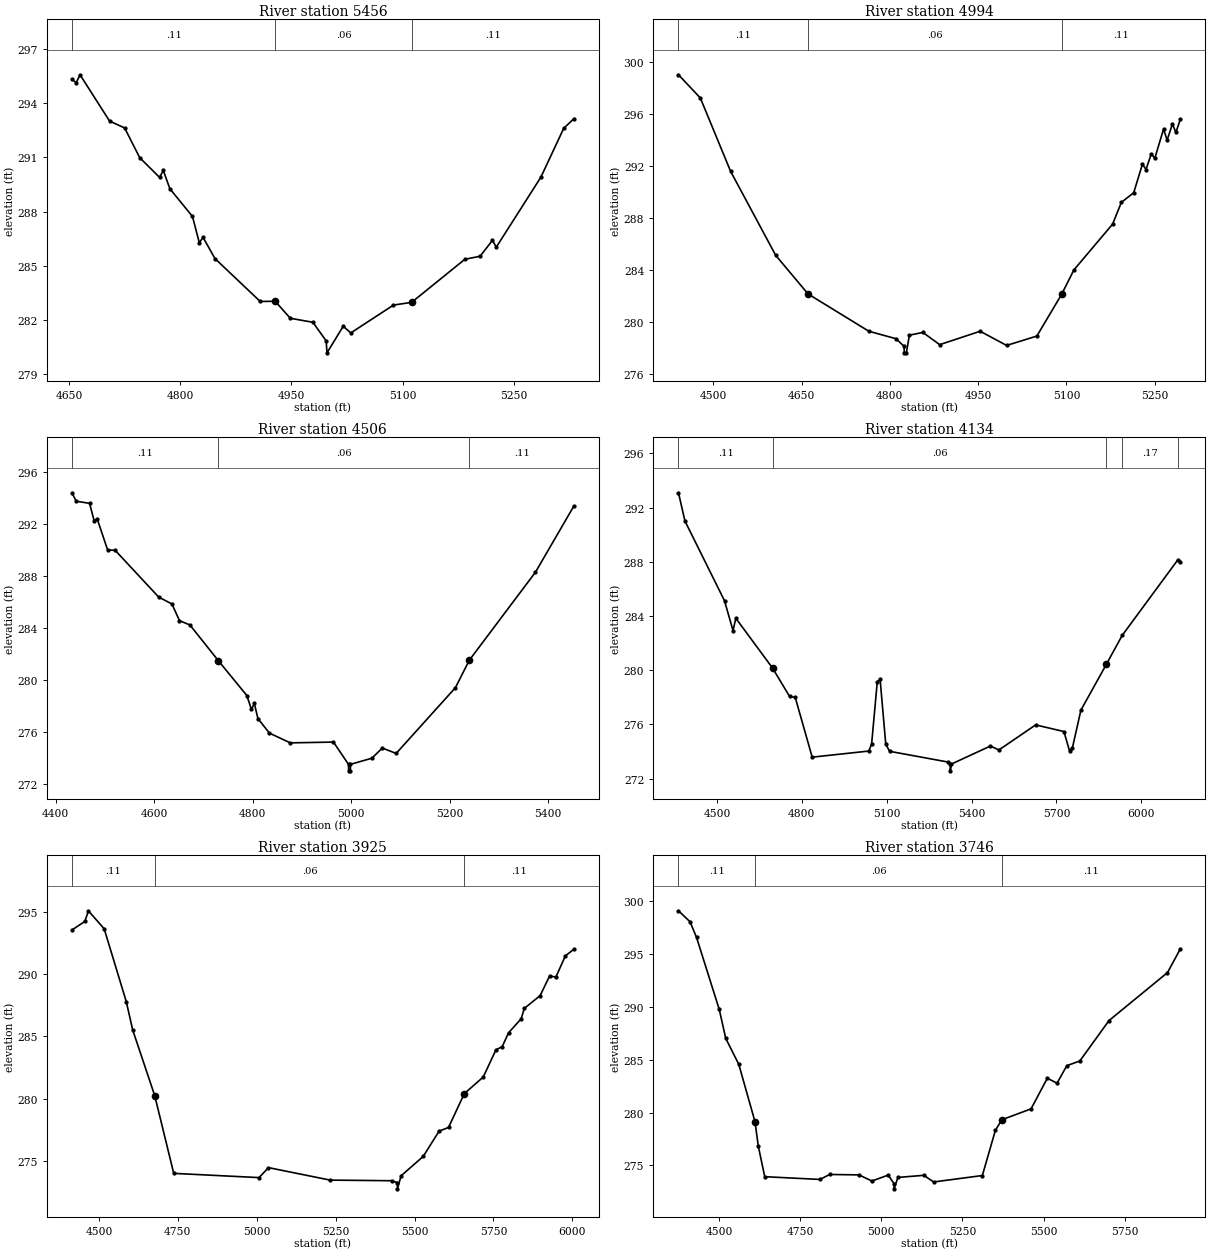
Type RM Length L Ch R = 1 ,5456    ,462,462,462
BEGIN DESCRIPTION:
WFSJR 085 9.0
END DESCRIPTION:
XS GIS Cut Line= 3
      3772641.71     10232321.08      3772702.94     10232661.72
      3772777.13     10232984.29
#Sta/Elev= 30
  4653.9  295.31  4659.7  295.12  4664.8  295.56  4704.7     293    4725  292.62
  4745.3  290.98  4772.1  289.89  4777.2  290.27    4786  289.26  4816.5  287.73
  4825.7  286.28  4830.8  286.57  4846.9   285.4  4907.9  283.03  4928.2  283.04
  4948.5   282.1    4979  281.88  4996.9  280.85    4998  280.19  5019.9  281.66
  5030.1  281.29  5087.7  282.83  5112.2  282.98    5184  285.36  5204.6  285.53
  5221.3  286.41  5226.4  286.03  5286.6   289.9  5317.4   292.6    5331  293.13
#Mann= 3 , 0 , 0
  4653.9     .11       0  4928.2     .06       0  5112.2     .11       0
Bank Sta=4928.2,5112.2
XS Rating Curve= 0 ,0
Exp/Cntr=0.3,0.1

Type RM Length L Ch R = 1 ,4994    ,488,488,488
BEGIN DESCRIPTION:
WFSJR 085 8.0
END DESCRIPTION:
XS GIS Cut Line= 3
      3772067.86      10232361.1      3772302.09     10232868.77
      3772467.86     10233111.09
#Sta/Elev= 30
  4440.9  298.98    4478   297.2  4529.5  291.55  4606.1  285.09  4661.1  282.12
  4764.4  279.25  4810.3  278.68  4824.3  278.09  4824.6  277.59  4828.1  277.59
  4833.3  278.95  4856.2  279.16  4884.7  278.22  4953.5  279.25  4998.5  278.16
  5049.8  278.88  5091.8  282.08  5112.8  283.97  5178.5  287.49  5193.4  289.16
  5214.4  289.91  5229.3  292.11  5235.3  291.69  5244.2   292.9  5250.2  292.55
  5265.1   294.8  5271.2  293.95  5280.1  295.19  5286.1  294.55  5293.6  295.54
#Mann= 3 , 0 , 0
  4440.9     .11       0  4661.1     .06       0  5091.8     .11       0
Bank Sta=4661.1,5091.8
XS Rating Curve= 0 ,0
Exp/Cntr=0.3,0.1

Type RM Length L Ch R = 1 ,4506    ,372,372,372
BEGIN DESCRIPTION:
WFSJR 085 7.0
END DESCRIPTION:
XS GIS Cut Line= 3
      3771596.56     10232661.32      3771897.92     10233141.25
      3772217.87     10233461.09
#Sta/Elev= 30
  4433.3  294.37    4442  293.72  4469.1  293.56  4478.5   292.2  4484.4  292.38
  4505.7  289.98    4521  289.95  4609.3  286.36  4636.4  285.82  4651.7  284.54
  4672.9  284.21  4730.7  281.46  4788.4  278.79  4797.8  277.72  4803.7  278.18
  4810.9  277.02  4834.3   275.9  4876.7  275.15  4964.4  275.21  4994.9   273.5
  4995.2     273  4998.7     273  4998.9   273.5  5042.3  273.97  5063.5  274.75
  5091.7  274.34    5212  279.39  5240.2   281.5  5374.6  288.27  5452.4  293.34
#Mann= 3 , 0 , 0
  4433.3     .11       0  4730.7     .06       0  5240.2     .11       0
Bank Sta=4730.7,5240.2
XS Rating Curve= 0 ,0
Exp/Cntr=0.3,0.1

Type RM Length L Ch R = 1 ,4134    ,209,209,209
BEGIN DESCRIPTION:
WFSJR 085 6.0
END DESCRIPTION:
XS GIS Cut Line= 3
      3771551.43     10232668.32      3771563.33     10233304.41
      3771558.37     10234442.59
#Sta/Elev= 30
  4363.8  293.09  4386.6  291.01  4526.6  285.12  4556.6  282.92  4566.6  283.83
  4696.6  280.15  4756.6  278.06  4776.6  277.99  4836.6  273.58  5036.7  274.03
  5046.7  274.55  5066.7  279.14  5076.7  279.33  5096.7  274.54  5110.4  274.01
  5316.7  273.22  5324.7  273.07  5324.9  272.57  5328.7  273.07  5466.7   274.4
  5496.7  274.11  5626.7  275.96  5726.7  275.47  5746.7  274.02  5756.7  274.27
  5786.7  277.05  5876.7  280.43  5932.5  282.56    6129  288.13  6138.2  287.98
#Mann= 5 ,-1 , 0
  4363.8     .11       0  4696.6     .06       0  5876.7     .11       0
  5932.5     .17       0    6129     .11       0
Bank Sta=4696.6,5876.7
XS Rating Curve= 0 ,0
Exp/Cntr=0.3,0.1

Type RM Length L Ch R = 1 ,3925    ,179,179,179
BEGIN DESCRIPTION:
WFSJR 085 5.0
END DESCRIPTION:
XS GIS Cut Line= 3
      3771384.76       10232769.      3771359.97     10233353.78
      3771329.25     10234357.71
#Sta/Elev= 30
  4414.7  293.52  4455.7  294.21  4466.8  295.06  4516.9  293.61  4586.9  287.77
  4606.9  285.53    4677  280.24  4737.1  274.02  5007.3  273.68  5037.3  274.48
  5232.5  273.48  5427.5  273.43  5445.5  273.28  5445.8  272.78  5457.5  273.83
  5527.5  275.38  5577.6   277.4  5607.6   277.7  5657.6  280.41  5717.6  281.74
  5757.6  283.91  5777.7  284.18  5797.7  285.28  5837.7  286.41  5847.7  287.24
  5897.7  288.26  5927.7  289.83  5947.7  289.75  5977.8  291.45  6004.4  291.97
#Mann= 3 , 0 , 0
  4414.7     .11       0    4677     .06       0  5657.6     .11       0
Bank Sta=4677,5657.6
XS Rating Curve= 0 ,0
Exp/Cntr=0.3,0.1

Type RM Length L Ch R = 1 ,3746    ,141,141,141
BEGIN DESCRIPTION:
Mapping XS 12338007
END DESCRIPTION:
XS GIS Cut Line= 2
      3771200.73     10232765.47      3771162.54      10234310.6
#Sta/Elev= 30
  4375.5  299.11  4411.1  298.07  4431.1  296.59  4501.1  289.77  4521.1  287.03
  4561.2  284.58  4611.2  279.14  4621.2  276.85  4641.2  273.94  4811.2  273.68
  4841.2  274.15  4931.3  274.11  4971.3  273.53  5021.3  274.09  5039.3  273.29
  5039.6  272.79  5051.3  273.87  5131.3  274.07  5161.3  273.44  5311.4  274.05
  5351.4  278.32  5371.4  279.33  5461.4  280.36  5511.5  283.26  5541.5  282.79
  5571.5  284.45  5611.5  284.89  5701.5  288.72  5881.6  293.26  5921.1   295.5
#Mann= 3 , 0 , 0
  4375.5     .11       0  4611.2     .06       0  5371.4     .11       0
Bank Sta=4611.2,5371.4
XS Rating Curve= 0 ,0
Exp/Cntr=0.3,0.1

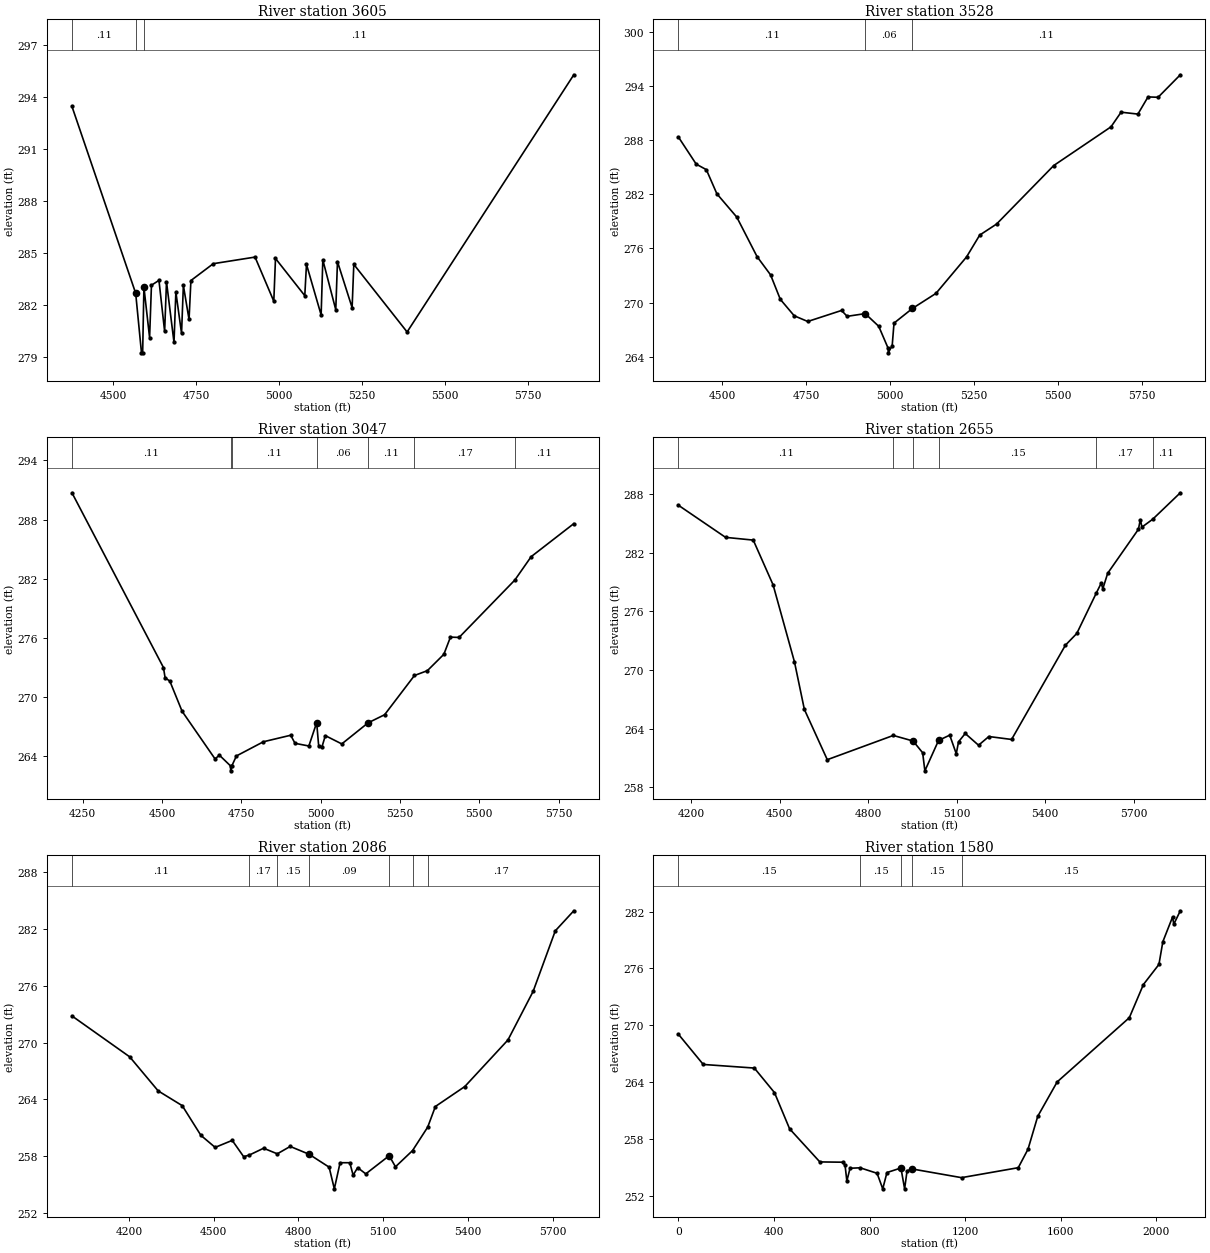
Type RM Length L Ch R = 1 ,3605    ,77,77,77
BEGIN DESCRIPTION:
Mapping XS aceed75f
END DESCRIPTION:
XS GIS Cut Line= 6
      3771159.07     10232800.19      3771138.23     10233001.61
       3771054.9     10233175.22      3771041.01     10233380.08
      3771113.93     10233716.88      3771103.51     10234282.89
#Sta/Elev= 30
    4376  293.44  4567.9  282.69  4585.4  279.26  4588.9  279.26  4592.7  283.04
  4609.8  280.14  4615.4  283.15    4638  283.43  4655.1  280.49  4660.7  283.35
  4683.3  279.86  4688.9  282.76    4706  280.38  4711.5  283.14  4728.6  281.18
  4734.2  283.42  4801.6  284.39  4927.3  284.77  4983.8  282.23  4988.9  284.69
  5077.1  282.55  5082.2  284.35  5126.3  281.44  5131.4  284.61  5170.4  281.74
  5175.5  284.51  5219.6  281.86  5224.7  284.35  5385.2  280.46  5887.1  295.26
#Mann= 3 ,-1 , 0
    4376     .11       0  4567.9     .06       0  4592.7     .11       0
#XS Ineff= 1 ,-1
  4801.6    5550  284.39
Permanent Ineff=
       F
Bank Sta=4567.9,4592.7
XS Rating Curve= 0 ,0
Exp/Cntr=0.3,0.1

Type RM Length L Ch R = 1 ,3528    ,481,481,481
BEGIN DESCRIPTION:
WFSJR 085 4.0
END DESCRIPTION:
XS GIS Cut Line= 3
      3771034.06     10232758.56      3770971.56     10233369.66
      3771013.18     10234247.08
#Sta/Elev= 30
  4370.3  288.32  4423.1  285.33  4453.2  284.72  4484.5  282.05  4543.7  279.47
    4604   275.1  4644.2  273.08  4673.2  270.37  4714.6  268.55  4754.8  267.92
  4855.3  269.14    4872  268.49  4925.7  268.79  4965.9  267.39    4994  264.95
  4994.3  264.45    5006  265.25  5011.4  267.74  5066.1  269.36  5136.2  271.03
  5227.1  275.06  5266.3  277.48  5316.4   278.7  5486.6  285.18  5656.8  289.46
  5686.8  291.08  5736.8  290.87  5766.9  292.77  5796.9  292.73    5863  295.22
#Mann= 3 ,-1 , 0
  4370.3     .11       0  4925.7     .06       0  5066.1     .11       0
Bank Sta=4925.7,5066.1
XS Rating Curve= 0 ,0
Exp/Cntr=0.3,0.1

Type RM Length L Ch R = 1 ,3047    ,392,392,392
BEGIN DESCRIPTION:
WFSJR 085 3.0
END DESCRIPTION:
XS GIS Cut Line= 3
      3770370.86      10232647.4      3770495.87     10233341.88
      3770728.51     10234185.66
#Sta/Elev= 30
  4216.6  290.72  4504.8     273    4510  271.97  4525.1  271.61  4563.6  268.56
  4667.4  263.73    4681  264.11  4716.2  263.02  4716.5  262.52  4720.2  263.02
  4734.7  264.03  4819.8  265.47  4905.7  266.13  4919.3  265.31  4962.9  265.04
  4987.5  267.41    4994  264.99  5004.4  264.97  5014.8  266.09  5066.6  265.25
  5149.6  267.39  5201.5  268.21  5295.6  272.19  5336.3  272.68  5388.2  274.34
  5408.9  276.08  5436.2  276.05  5611.8  281.87  5663.2  284.24  5797.5  287.59
#Mann= 7 ,-1 , 0
  4216.6     .11       0  4716.2     .11       0  4720.2     .11       0
  4987.5     .06       0  5149.6     .11       0  5295.6     .17       0
  5611.8     .11       0
Bank Sta=4987.5,5149.6
XS Rating Curve= 0 ,0
Exp/Cntr=0.3,0.1

Type RM Length L Ch R = 1 ,2655    ,569,569,569
BEGIN DESCRIPTION:
WFSJR 085 2.0
END DESCRIPTION:
XS GIS Cut Line= 3
      3769943.78     10232657.83      3770178.23     10233466.84
      3770575.42      10234226.7
#Sta/Elev= 30
  4157.7  286.83  4317.2  283.55    4411  283.27  4478.2  278.69  4550.5  270.82
  4584.1  265.95  4661.7  260.81  4885.3  263.29  4952.3  262.72  4984.7  261.52
  4992.2  259.67  5038.6  262.78  5076.4  263.32  5098.5  261.42  5106.3  262.64
  5128.9  263.49    5174  262.29  5208.9  263.18  5285.9  262.88  5468.2  272.52
  5506.7  273.72  5573.4  277.89  5589.4  278.86    5595   278.3  5611.4  279.88
  5715.6  284.38  5721.8  285.36  5727.5   284.6  5763.7   285.4  5857.4  288.11
#Mann= 6 ,-1 , 0
  4157.7     .11       0  4885.3     .15       0  4952.3     .09       0
  5038.6     .15       0  5573.4     .17       0  5763.7     .11       0
Bank Sta=4952.3,5038.6
XS Rating Curve= 0 ,0
Exp/Cntr=0.3,0.1

Type RM Length L Ch R = 1 ,2086    ,506,506,506
BEGIN DESCRIPTION:
WFSJR 085 1.0
END DESCRIPTION:
XS GIS Cut Line= 4
       3769641.7     10232758.54       3769766.7       10233703.
      3769981.98     10234130.08      3770317.88     10234211.08
#Sta/Elev= 30
  3998.2  272.83  4202.5  268.51  4303.4  264.91  4388.6  263.35  4454.7  260.21
  4505.1  258.94  4565.6  259.68    4606  257.96  4625.4  258.12  4676.6  258.85
  4725.1  258.26  4770.8  259.04    4838  258.21  4908.6  256.85    4927  254.56
  4947.4  257.32  4981.8  257.32  4993.5  256.01  5009.7   256.8  5038.3  256.14
  5121.2  258.06  5143.5  256.89  5203.8   258.6  5257.5  261.08  5284.7  263.26
  5388.9  265.37  5541.6  270.29  5630.7  275.42  5709.2  281.82  5774.7  283.94
#Mann= 7 ,-1 , 0
  3998.2     .11       0  4625.4     .17       0  4725.1     .15       0
    4838     .09       0  5121.2     .15       0  5203.8     .17       0
  5257.5     .17       0
Bank Sta=4838,5121.2
XS Rating Curve= 0 ,0
Exp/Cntr=0.3,0.1

Type RM Length L Ch R = 1 ,1580    ,704,704,704
XS GIS Cut Line= 4
      3769616.37     10232899.97      3769348.15     10233704.66
      3769408.04     10234035.38      3770296.06     10234264.55
#Sta/Elev= 30
       0  269.05   103.7  265.87   317.4  265.49   401.7   262.9     465  259.08
   591.5  255.59   686.3  255.56   696.9  255.26   704.5  253.58   717.9  254.92
   760.1  254.97     831  254.39   854.7  252.75   872.3  254.47   930.8  254.95
   946.2  252.75   956.4  254.64   976.7  254.85  1184.3  253.93  1421.7  254.98
  1462.5  256.93  1503.2   260.4  1584.5  264.03  1886.4   270.8  1945.3   274.3
  2010.3  276.42  2026.7  278.82  2067.3  281.42  2072.5  280.67  2099.8  282.08
#Mann= 5 ,-1 , 0
       0     .15       0   760.1     .15       0   930.8     .09       0
   976.7     .15       0  1184.3     .15       0
Bank Sta=930.8,976.7
XS Rating Curve= 0 ,0
Exp/Cntr=0.3,0.1

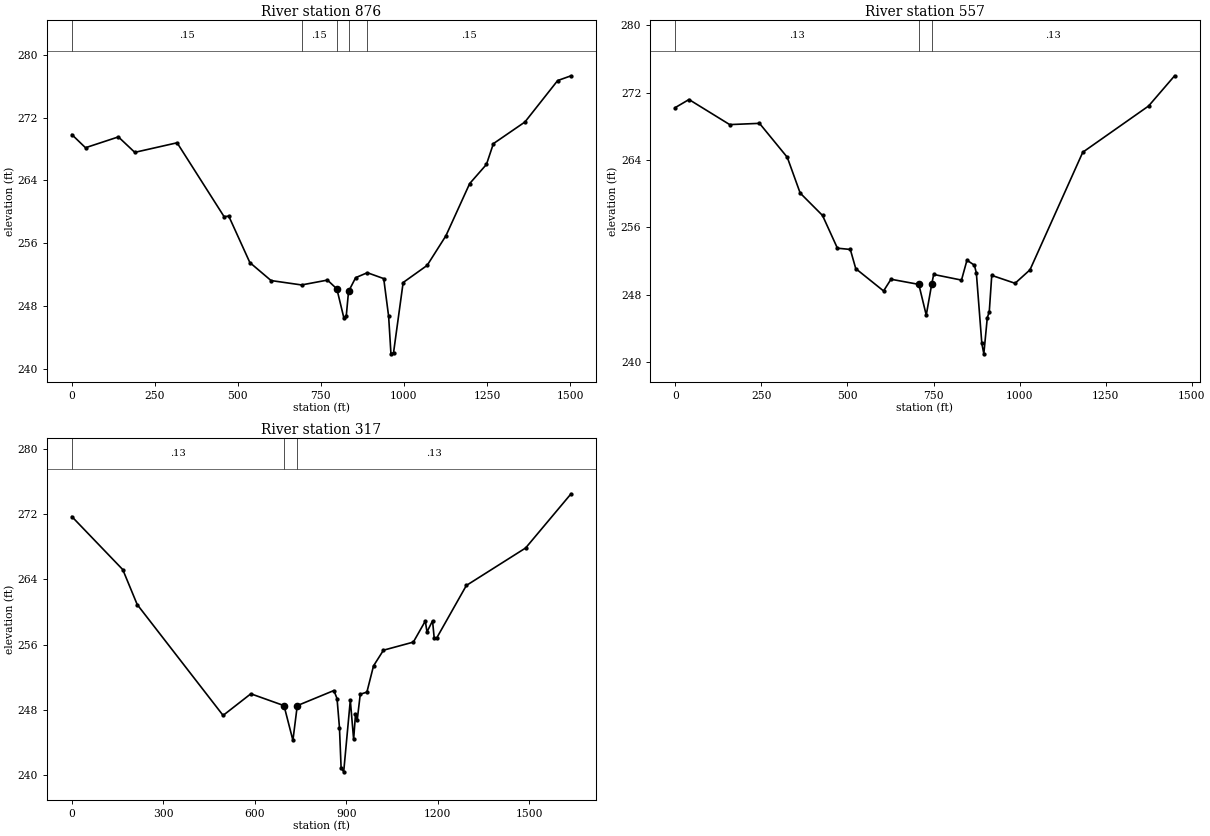
Type RM Length L Ch R = 1 ,876     ,318,318,318
XS GIS Cut Line= 3
      3769592.94     10232847.88      3768936.69      10233483.3
       3768454.2      10233822.5
#Sta/Elev= 30
       0  269.85    41.2  268.17   140.2  269.55   189.6  267.58     317   268.8
   458.4  259.39   472.6  259.45   536.1  253.53   599.9  251.24   691.8  250.68
   769.7   251.3     798  250.18   819.1  246.48   826.3  246.72   833.2  249.85
   854.6  251.61   889.8  252.24   939.1  251.49   953.9  246.68   960.9   241.9
   968.7  242.05   997.6  250.99  1069.8  253.17  1126.4  256.95  1197.9   263.6
  1248.4  266.04  1269.3  268.69  1364.3  271.45  1462.8  276.73  1503.2  277.34
#Mann= 5 ,-1 , 0
       0     .15       0   691.8     .15       0     798     .09       0
   833.2     .15       0   889.8     .15       0
Bank Sta=798,833.2
XS Rating Curve= 0 ,0
Exp/Cntr=0.3,0.1

Type RM Length L Ch R = 1 ,557     ,241,241,241
XS GIS Cut Line= 2
      3769507.24      10232776.5      3768245.87     10233492.64
#Sta/Elev= 30
       0  270.23    39.6  271.18   157.9   268.2   244.4  268.35   325.1  264.32
   362.6  260.07   427.5  257.41   470.8  253.52   508.3  253.37   524.1  251.09
   604.9  248.44   626.5  249.83   707.3  249.22   728.9  245.57   744.8  249.25
   750.5   250.4   831.3  249.73   847.2  252.09   868.8   251.5   874.5  250.57
   890.4   242.2   896.2  240.97   906.3  245.27     912  245.96   919.2  250.29
     987  249.35  1030.3  250.95  1183.7  264.92  1374.9  270.41  1450.5     274
#Mann= 3 , 0 , 0
       0     .13       0   707.3     .08       0   744.8     .13       0
#XS Ineff= 1 ,-1
   847.2    1060  252.09
Permanent Ineff=
       F
Bank Sta=707.3,744.8
XS Rating Curve= 0 ,0
Exp/Cntr=0.3,0.1

Type RM Length L Ch R = 1 ,317     ,0,0,0
XS GIS Cut Line= 2
      3769417.85     10232661.07       3767911.3     10233303.26
#Sta/Elev= 30
       0  271.69   167.1  265.19   214.4  260.91     496  247.33     587  249.98
   695.7  248.53   724.9  244.28   739.2  248.53   859.3  250.38   869.6  249.39
   877.5  245.85   882.9  240.94   891.4  240.42   913.1  249.19     924   244.4
   930.1  247.46   935.6  246.72   945.7  249.92   967.5  250.19   989.2   253.4
  1021.8  255.32  1119.7  256.31    1159  258.89  1164.5  257.56  1182.7  258.91
  1188.1  256.84  1195.8  256.78  1293.6  263.25  1487.9  267.84  1636.9  274.48
#Mann= 3 , 0 , 0
       0     .13       0   695.7     .08       0   739.2     .13       0
Bank Sta=695.7,739.2
XS Rating Curve= 0 ,0
Exp/Cntr=0.3,0.1

Chan Stop Cuts=-1
Use User Specified Reach Order=0
Composite Channel Slope=5