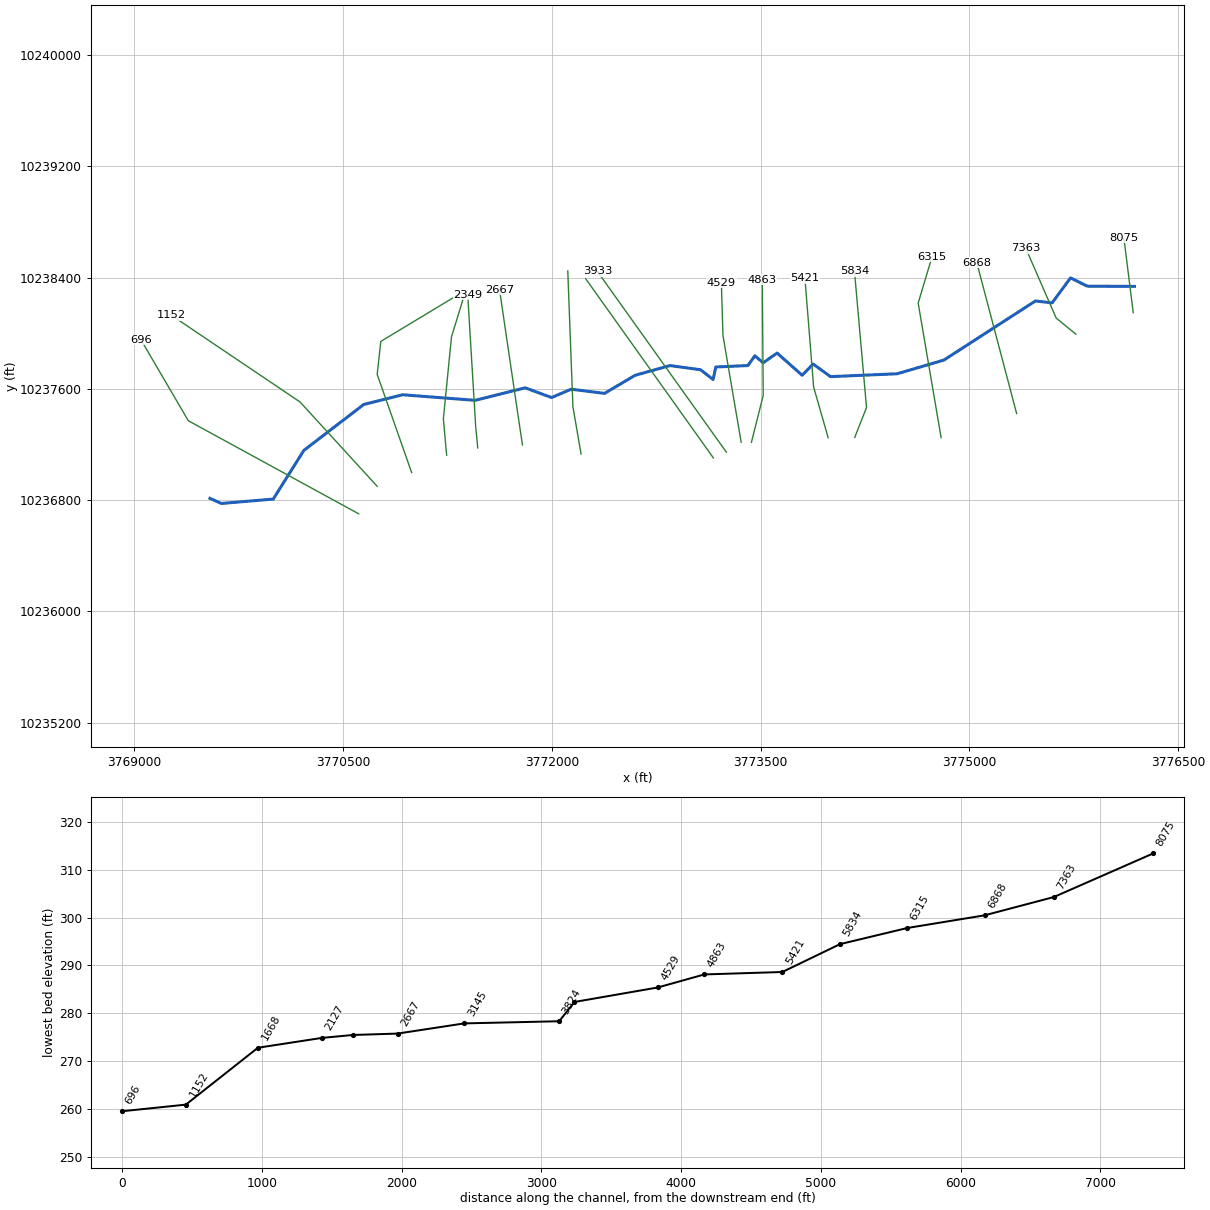
--- WFSJR 086.prj (project) ---

Proj Title=WFSJR 086 Base Level Engineering
Current Plan=p01
Default Exp/Contr=0.3,0.1
English Units
Geom File=g01
Flow File=f01
Plan File=p01
Y Axis Title=Elevation
X Axis Title(PF)=Main Channel Distance
X Axis Title(XS)=Station
BEGIN DESCRIPTION:
WFSJR 086
END DESCRIPTION:
DSS Export Rating Curves= 0
DSS Export Rating Curve Sorted= 0
DSS Export Volume Flow Curves= 0
DXF OffsetX= 0
DXF OffsetY= 0
DXF ScaleX= 1
DXF ScaleY= 10

--- WFSJR 086.p01 (plan) ---

Plan Title=Multiple Run
Program Version=4.10
Short Identifier=Multiple
Geom File=g01
Flow File=f01
Subcritical Flow
K Sum by GR= 0
Std Step Tol= 0.01
Critical Tol= 0.01
Num of Std Step Trials= 20
Max Error Tol= 0.3
Flow Tol Ratio= 0.001
Split Flow NTrial= 30
Split Flow Tol= 0.02
Split Flow Ratio= 0.02
Log Output Level= 0
Friction Slope Method= 1
Unsteady Friction Slope Method= 2
Unsteady Bridges Friction Slope Method= 1
Parabolic Critical Depth
Global Vel Dist= 1 , 1 , 1
Global Log Level= 0
CheckData=True
Encroach Param=-1 ,0,0, 0
BEGIN DESCRIPTION:
Multiple Run
END DESCRIPTION:
Computation Interval=1HOUR
Output Interval=1HOUR
Run HTab= 0
Run UNet= 0
Run PostProcess= 0
Run WQNet= 0
UNET Theta= 1
UNET Theta Warmup= 1
UNET ZTol= 0.02
UNET ZSATol= 0.05
UNET MxIter= 20
UNET MaxInSteps= 0
UNET DtIC= 0
UNET DtMin= 0
UNET MaxCRTS= 20
UNET WFStab= 2
UNET SFStab= 1
UNET WFX= 1
UNET SFX= 1
UNET DSS MLevel= 4
UNET DZMax Abort= 100
UNET Convert EG Bridges= 0
UNET Use Existing IB Tables=-1
UNET Froude Reduction=False
UNET Froude Limit= 1
UNET Froude Power= 10
UNET Time Slicing=0,0, 5
UNET Junction Losses=0
Instantaneous Interval=1HOUR
Write IC File= 0
Write IC File at Sim End=0
Echo Input=False
Echo Parameters=False
Echo Output=False
Write Detailed= 0
WQ AD Non Conservative
WQ ULTIMATE=-1
WQ Max Comp Step=1HOUR
WQ Output Interval=15MIN
WQ Output Selected Increments= 0
WQ Output face flow=0
WQ Output face velocity=0
WQ Output face area=0
WQ Output face dispersion=0
WQ Output cell volume=0
WQ Output cell surface area=0
WQ Output cell continuity=0
WQ Output cumulative cell continuity=0
WQ Output face conc=0
WQ Output face dconc_dx=0
WQ Output face courant=0
WQ Output face peclet=0
WQ Output face adv mass=0
WQ Output face disp mass=0
WQ Output cell mass=0
WQ Output cell source sink temp=0
WQ Output cell source sink nsm=0
WQ Output MaxMinRange=-1
WQ Daily Max Min Mean=-1
WQ Daily Range=0
WQ Daily Time=0
WQ Create Restart=0
WQ Fixed Restart=0
WQ System Summary=0
WQ Use Fixed Temperature=0
Sorting and Armoring Iterations= 10
XS Update Threshold= 0.02
Hydraulics Update Threshold= 0.02
Energy Slope Method= 1
Volume Change Method= 0
XS Weighting Method= 0
Number of US Weighted Cross Sections= 1
Number of DS Weighted Cross Sections= 1
Upstream XS Weight=0.25
Main XS Weight=0.5
Downstream XS Weight=0.25
Number of DS XS's Weighted with US Boundary= 1
Upstream Boundary Weight= 1
Weight of XSs Associated with US Boundary= 0
Number of US XS's Weighted with DS Boundary= 1
Downstream Boundary Weight= 0.5
Weight of XSs Associated with DS Boundary= 0.5
Sediment Output Level= 4
Mass or Volume Output= 0
Output Increment Type= 1
Profile and TS Output Increment= 10
XS Output Flag= 0
XS Output Increment= 10
Disregard all LS=0
Disregard all Conn=0
Disregard all Breaches=0
Disregard all Pumps=0

--- WFSJR 086.f01 (steady flow) ---

Flow Title=Multiple
Program Version=4.10
Number of Profiles= 7
Profile Names=10-year,25-year,50-year,1pct_min,100-year,1pct_plu,500-year
River Rch & RM=WFSJR 086,Reach-1         ,8075
     507     681     917     406    1227    3705    2276
River Rch & RM=WFSJR 086,Reach-1         ,5421
     776    1072    1470     663    2003    6049    3848
Boundary for River Rch & Prof#=WFSJR 086,Reach-1         , 1
Up Type= 0
Dn Type= 3
Dn Slope=0.002
Boundary for River Rch & Prof#=WFSJR 086,Reach-1         , 2
Up Type= 0
Dn Type= 3
Dn Slope=0.002
Boundary for River Rch & Prof#=WFSJR 086,Reach-1         , 3
Up Type= 0
Dn Type= 3
Dn Slope=0.002
Boundary for River Rch & Prof#=WFSJR 086,Reach-1         , 4
Up Type= 0
Dn Type= 3
Dn Slope=0.002
Boundary for River Rch & Prof#=WFSJR 086,Reach-1         , 5
Up Type= 0
Dn Type= 3
Dn Slope=0.002
Boundary for River Rch & Prof#=WFSJR 086,Reach-1         , 6
Up Type= 0
Dn Type= 3
Dn Slope=0.002
Boundary for River Rch & Prof#=WFSJR 086,Reach-1         , 7
Up Type= 0
Dn Type= 3
Dn Slope=0.002
DSS Import GetInterval= 0
DSS Import GetPeak= 0
DSS Import FillOption= 0

--- WFSJR 086.g01 (geometry) ---

Geom Title=Existing Conditions
Program Version=4.10

River Reach=WFSJR 086       ,Reach-1
Reach XY= 30
      3776185.73     10238336.22      3775847.22     10238337.64
      3775726.58     10238397.26      3775593.87     10238217.71
      3775473.94     10238231.19      3774816.72     10237806.41
      3774480.61      10237707.8      3774002.14     10237687.31
      3773876.79     10237777.94      3773798.23     10237696.84
      3773618.23     10237856.84      3773518.23     10237786.84
      3773458.23     10237836.84      3773408.23     10237766.84
      3773178.23     10237756.84      3773158.23     10237666.84
      3773068.23     10237736.84      3772848.23     10237766.84
      3772598.23     10237696.84      3772378.23     10237566.84
      3772138.23     10237596.84      3771998.23     10237536.84
      3771808.23     10237606.84      3771448.23     10237516.84
      3770928.23     10237556.84      3770648.23     10237486.84
      3770218.23     10237156.84      3769998.23     10236806.84
       3769625.2     10236775.43      3769543.55     10236812.17

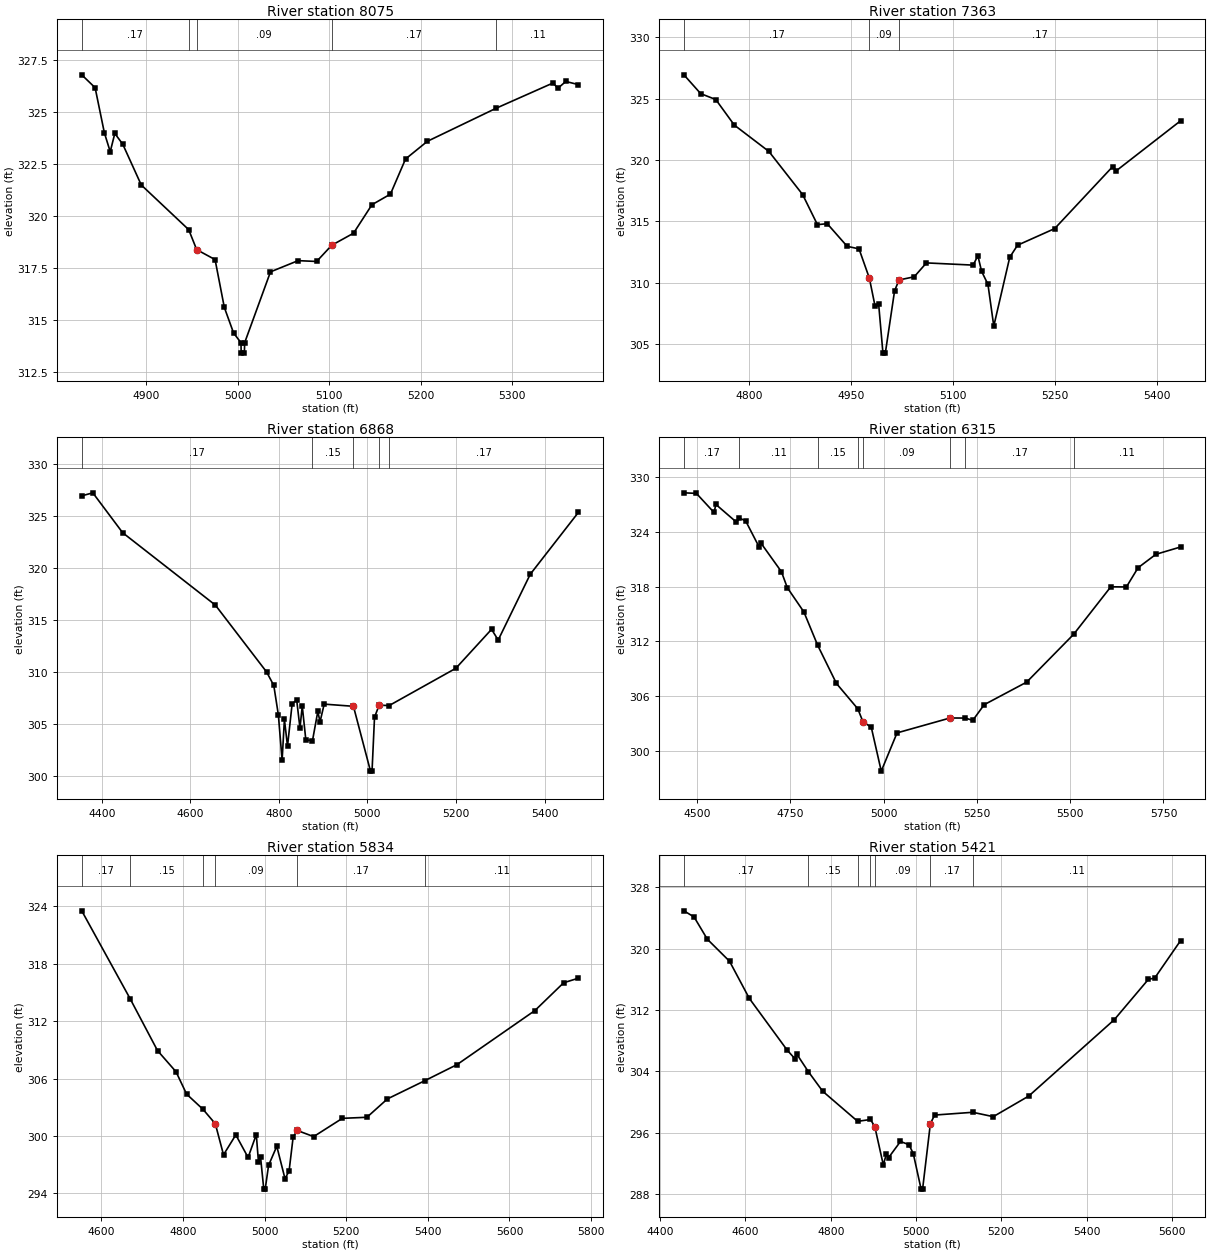
Type RM Length L Ch R = 1 ,8075    ,712,712,712
BEGIN DESCRIPTION:
WFSJR 086 14.0
END DESCRIPTION:
XS GIS Cut Line= 2
      3776176.88     10238146.57       3776109.6     10238684.78
#Sta/Elev= 30
  4829.7  326.81  4844.3  326.19  4854.4  324.02  4860.8  323.11  4865.8  323.99
  4874.5  323.47  4894.7  321.51  4946.5  319.36  4955.2   318.4  4975.3  317.92
  4985.4  315.62  4995.5  314.39  5003.6  313.92  5003.8  313.42  5007.3  313.42
  5007.6  313.92  5035.8  317.33    5066  317.87  5086.2  317.83  5102.7  318.61
  5126.5  319.19  5146.6  320.56  5166.8  321.07  5183.3  322.76  5207.1  323.61
  5282.6  325.21  5344.5  326.42  5349.6  326.16  5358.3  326.49  5372.1  326.34
#Mann= 5 ,-1 , 0
  4829.7     .17       0  4946.5     .12       0  4955.2     .09       0
  5102.7     .17       0  5282.6     .11       0
Bank Sta=4955.2,5102.7
XS Rating Curve= 0 ,0
Exp/Cntr=0.3,0.1

Type RM Length L Ch R = 1 ,7363    ,495,495,495
BEGIN DESCRIPTION:
WFSJR 086 13.0
END DESCRIPTION:
XS GIS Cut Line= 3
      3775764.51     10237992.52      3775623.45     10238108.08
      3775404.32     10238610.96
#Sta/Elev= 30
  4704.5  326.93  4729.2   325.4  4751.4  324.92  4778.7  322.84  4829.5   320.7
  4879.2  317.19    4901  314.74  4915.4  314.82  4944.7  312.98  4962.2  312.77
  4977.4  310.39  4985.7  308.14  4991.1  308.26  4997.4  304.29  5000.9  304.29
  5014.5  309.35    5021  310.24  5043.4   310.5  5061.4  311.63  5130.1  311.45
  5137.1  312.21  5142.6  310.94  5151.9  309.89  5160.5  306.49    5184  312.09
  5195.5  313.07  5250.1  314.42  5335.4  319.46  5340.9  319.13  5435.4  323.19
#Mann= 3 , 0 , 0
  4704.5     .17       0  4977.4     .09       0    5021     .17       0
#XS Ineff= 1 ,-1
  5137.1    5190  312.21
Permanent Ineff=
       F
Bank Sta=4977.4,5021
XS Rating Curve= 0 ,0
Exp/Cntr=0.3,0.1

Type RM Length L Ch R = 1 ,6868    ,553,553,553
BEGIN DESCRIPTION:
WFSJR 086 12.0
END DESCRIPTION:
XS GIS Cut Line= 2
      3775339.21     10237421.74      3775052.89     10238506.28
#Sta/Elev= 30
  4354.9  326.97  4379.9  327.26  4447.3  323.42  4656.7  316.45  4772.3  310.02
  4788.6  308.72  4798.9   305.9  4807.4  301.52  4812.6  305.45  4819.6  302.87
    4830  306.93  4840.3  307.33  4847.7  304.62  4852.9  306.72    4861  303.47
    4876   303.4    4888  306.21  4893.1  305.22  4902.4  306.92  4968.5  306.71
    5007  300.47  5010.5  300.47  5016.1  305.65  5026.5  306.82  5049.1  306.78
  5199.8  310.37  5280.4  314.12  5295.4  313.09  5367.8  319.42  5476.6  325.38
#Mann= 5 ,-1 , 0
  4354.9     .17       0    4876     .15       0  4968.5     .09       0
  5026.5     .15       0  5049.1     .17       0
Bank Sta=4968.5,5026.5
XS Rating Curve= 0 ,0
Exp/Cntr=0.3,0.1

Type RM Length L Ch R = 1 ,6315    ,481,481,481
BEGIN DESCRIPTION:
WFSJR 086 11.0
END DESCRIPTION:
XS GIS Cut Line= 3
      3774796.67     10237248.14      3774631.74     10238216.02
      3774731.56      10238550.2
#Sta/Elev= 30
  4465.2  328.24  4498.6  328.18  4545.9  326.09  4550.9  326.97    4606  325.03
  4614.1  325.47  4630.5  325.18  4666.2  322.36  4671.3  322.76  4726.4  319.62
  4742.1  317.88  4786.6  315.22  4823.5  311.58  4873.9   307.4  4930.9  304.64
  4944.9  303.22  4967.2  302.61  4993.9  297.82  5036.2     302  5178.3  303.63
  5218.8  303.62  5239.1  303.37  5269.6  305.08  5383.5  307.55  5509.2  312.77
  5608.9  317.97  5650.6  317.95  5681.9  320.05  5729.7  321.52  5795.8  322.32
#Mann= 8 ,-1 , 0
  4465.2     .17       0  4614.1     .11       0  4823.5     .15       0
  4930.9     .17       0  4944.9     .09       0  5178.3     .17       0
  5218.8     .17       0  5509.2     .11       0
Bank Sta=4944.9,5178.3
XS Rating Curve= 0 ,0
Exp/Cntr=0.3,0.1

Type RM Length L Ch R = 1 ,5834    ,413,413,413
BEGIN DESCRIPTION:
WFSJR 086 10.0
END DESCRIPTION:
XS GIS Cut Line= 3
      3774176.01     10237250.31      3774260.64     10237465.15
      3774173.94     10238447.12
#Sta/Elev= 30
  4552.2  323.54  4670.5  314.37  4737.8  308.93  4783.1  306.72  4809.1  304.38
  4849.3  302.79  4879.4  301.28  4899.5  298.04  4929.6  300.12  4959.7  297.76
  4979.8  300.16  4985.1  297.29  4990.1  297.84  4998.1  294.45  5001.6  294.45
  5009.9  296.94    5030  298.93  5050.1  295.54  5060.1  296.34  5070.1  299.91
  5080.2  300.58  5120.3  299.94  5190.6  301.85  5250.8  301.96    5301  303.88
  5391.9  305.77  5471.7  307.47  5662.4  313.12  5732.7  316.02  5768.9   316.5
#Mann= 6 ,-1 , 0
  4552.2     .17       0  4670.5     .15       0  4849.3     .17       0
  4879.4     .09       0  5080.2     .17       0  5391.9     .11       0
Bank Sta=4879.4,5080.2
XS Rating Curve= 0 ,0
Exp/Cntr=0.3,0.1

Type RM Length L Ch R = 1 ,5421    ,558,558,558
BEGIN DESCRIPTION:
WFSJR 086 9.0
END DESCRIPTION:
XS GIS Cut Line= 3
      3773985.03     10237248.17      3773880.72     10237612.29
      3773817.94     10238396.11
#Sta/Elev= 30
  4455.6  324.95  4479.4  324.15  4510.6  321.24  4562.6  318.37  4609.1  313.51
  4697.9  306.76  4715.6  305.67  4720.8  306.21  4747.3  303.97  4781.1   301.4
  4863.2  297.47  4893.3  297.71  4903.4  296.77  4923.4  291.77  4930.7  293.26
  4935.7  292.73  4963.6  294.84  4983.6  294.42  4993.7  293.25    5012  288.62
  5015.5  288.62  5033.8  297.18  5043.8  298.29  5133.2  298.65  5181.3  298.08
  5264.5  300.77  5465.2  310.74  5545.4  316.02  5559.8  316.16  5620.7  321.06
#Mann= 7 ,-1 , 0
  4455.6     .17       0  4747.3     .15       0  4863.2     .17       0
  4893.3     .12       0  4903.4     .09       0  5033.8     .17       0
  5133.2     .11       0
Bank Sta=4903.4,5033.8
XS Rating Curve= 0 ,0
Exp/Cntr=0.3,0.1

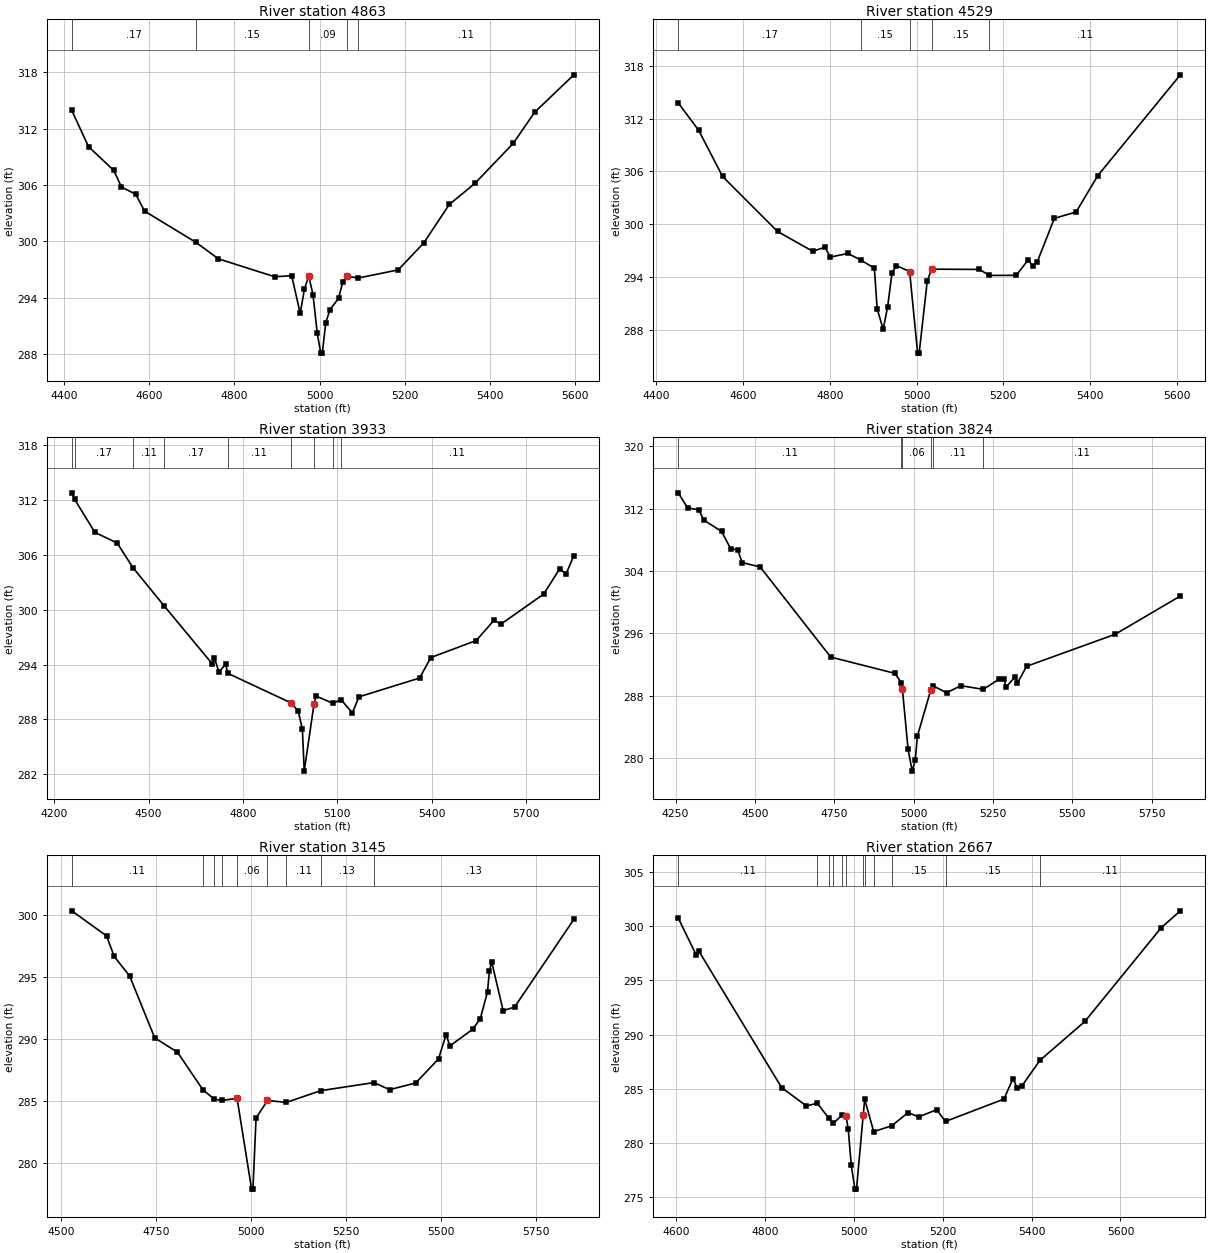
Type RM Length L Ch R = 1 ,4863    ,334,334,334
BEGIN DESCRIPTION:
WFSJR 086 8.0
END DESCRIPTION:
XS GIS Cut Line= 3
      3773433.81     10237215.54      3773518.46     10237551.95
      3773511.95     10238383.13
#Sta/Elev= 30
  4418.2  313.94  4457.6  310.08  4516.7  307.56  4534.7  305.79  4568.3  305.02
  4588.9  303.23  4709.5   299.9  4762.1  298.15  4894.2  296.24  4934.2  296.35
  4954.2  292.35  4964.2  294.92  4974.2  296.33  4984.2  294.33  4994.2  290.23
  5002.5  288.11    5006  288.11  5014.2  291.36  5024.2  292.74  5044.2  293.94
  5054.2  295.71  5064.2   296.3  5089.9   296.1  5184.2  296.97  5244.2  299.84
  5304.2  303.94  5364.2  306.18  5454.2  310.44  5504.2  313.74  5596.3  317.73
#Mann= 5 ,-1 , 0
  4418.2     .17       0  4709.5     .15       0  4974.2     .09       0
  5064.2     .15       0  5089.9     .11       0
Bank Sta=4974.2,5064.2
XS Rating Curve= 0 ,0
Exp/Cntr=0.3,0.1

Type RM Length L Ch R = 1 ,4529    ,596,596,596
BEGIN DESCRIPTION:
WFSJR 086 7.0
END DESCRIPTION:
XS GIS Cut Line= 3
      3773360.04     10237215.54      3773229.26     10237983.27
      3773217.85     10238361.11
#Sta/Elev= 30
  4450.9  313.78  4497.9  310.68  4553.1  305.43  4679.7  299.19  4760.8  296.94
  4788.8   297.4  4801.4  296.29    4842  296.69  4871.4  295.94  4902.8  295.03
  4909.2  290.42  4923.1  288.09  4933.3  290.63  4943.4  294.46  4953.6  295.32
    4984  294.64  5002.5  285.38    5006  285.38  5024.6  293.55  5034.7  294.91
    5145  294.88  5167.7   294.2  5229.7  294.21  5257.5  295.98  5267.5  295.24
  5277.5  295.67  5317.5  300.68  5367.6   301.4  5417.6  305.53  5607.7  316.97
#Mann= 5 ,-1 , 0
  4450.9     .17       0  4871.4     .15       0    4984     .09       0
  5034.7     .15       0  5167.7     .11       0
Bank Sta=4984,5034.7
XS Rating Curve= 0 ,0
Exp/Cntr=0.3,0.1

Type RM Length L Ch R = 1 ,3933    ,109,109,109
BEGIN DESCRIPTION:
WFSJR 086 6.0
END DESCRIPTION:
XS GIS Cut Line= 2
      3773253.72     10237143.94      3772327.06     10238443.87
#Sta/Elev= 30
  4255.5  312.78  4264.3  312.08  4328.9  308.46  4400.1  307.28  4449.7  304.61
  4549.9  300.39  4702.6  294.06  4708.7  294.76  4723.5  293.17  4744.4  294.05
  4751.9  293.04  4952.1  289.82  4975.5  288.93  4988.8  286.93  4994.6  282.35
  5025.7  289.68    5032  290.56  5086.4  289.76  5111.5  290.18  5147.6  288.71
  5168.5  290.47  5361.5  292.53  5397.1  294.77  5541.5  296.63  5598.7  298.87
  5619.6  298.41  5756.1  301.71  5806.5  304.45  5827.4  303.93  5851.9  305.91
#Mann= 9 ,-1 , 0
  4255.5     .11       0  4264.3     .17       0  4449.7     .11       0
  4549.9     .17       0  4751.9     .11       0  4952.1     .06       0
  5025.7     .11       0  5086.4     .15       0  5111.5     .11       0
Bank Sta=4952.1,5025.7
XS Rating Curve= 0 ,0
Exp/Cntr=0.3,0.1

Type RM Length L Ch R = 1 ,3824    ,679,679,679
BEGIN DESCRIPTION:
WFSJR 086 5.0
END DESCRIPTION:
XS GIS Cut Line= 2
      3773160.37     10237102.76      3772242.64     10238391.49
#Sta/Elev= 30
  4258.4  314.05  4287.8  312.12  4323.5  311.87  4338.2  310.56  4394.8   309.1
  4424.3  306.82  4445.2  306.77  4459.9   305.1  4516.5  304.53    4739  292.96
  4940.7  290.88  4961.6  289.68  4964.6 288.926  4982.5  281.19  4995.5  278.32
  5005.2  279.71    5012  282.81  5054.3  288.76  5062.4  289.25  5104.2  288.38
  5148.5  289.29  5219.8  288.82  5270.2  290.15  5284.9  290.19  5291.1  289.09
  5320.6  290.46  5326.7   289.6  5356.2  291.78  5635.3  295.89  5840.5   300.8
#Mann= 6 ,-1 , 0
  4258.4     .11       0  4961.6     .11       0  4964.6     .06       0
  5054.3     .11       0  5062.4     .11       0  5219.8     .11       0
Bank Sta=4964.6,5054.3
XS Rating Curve= 0 ,0
Exp/Cntr=0.3,0.1

Type RM Length L Ch R = 1 ,3145    ,478,478,478
BEGIN DESCRIPTION:
WFSJR 086 4.0
END DESCRIPTION:
XS GIS Cut Line= 3
      3772209.87     10237130.94      3772151.27     10237471.66
      3772114.42     10238447.14
#Sta/Elev= 30
    4529  300.31  4620.5  298.29  4640.8  296.63  4681.3  295.06  4747.3  290.07
  4807.3  288.91  4874.7  285.86  4904.2  285.13  4924.2  285.02  4964.2  285.19
  5002.5  277.87    5006  277.87  5014.2   283.6  5044.3  285.02  5093.5  284.86
  5184.4  285.81  5324.5  286.46    5366  285.89  5434.5  286.43  5494.6  288.37
  5514.6  290.33  5524.6  289.42  5584.6  290.76  5604.7  291.62  5623.6  293.78
  5628.6  295.47  5634.7  296.18  5664.7  292.27  5694.7  292.54  5850.9  299.62
#Mann= 9 ,-1 , 0
    4529     .11       0  4874.7     .11       0  4904.2     .11       0
  4924.2     .11       0  4964.2     .06       0  5044.3     .11       0
  5093.5     .11       0  5184.4     .13       0  5324.5     .13       0
Bank Sta=4964.2,5044.3
XS Rating Curve= 0 ,0
Exp/Cntr=0.3,0.1

Type RM Length L Ch R = 1 ,2667    ,318,318,318
BEGIN DESCRIPTION:
WFSJR 086 3.0
END DESCRIPTION:
XS GIS Cut Line= 3
      3771788.86     10237196.03      3771754.44     10237426.08
      3771623.93     10238313.63
#Sta/Elev= 30
  4604.9  300.75  4645.4  297.35  4650.5  297.75  4837.5  285.11  4893.1  283.42
  4917.8  283.66  4943.6  282.29  4953.7  281.81  4973.9  282.58  4982.5   282.5
  4987.5  281.25  4994.2  277.94  5002.5  275.74    5006  275.74    5021  282.54
  5024.5  284.02  5044.7  281.05  5085.1  281.58    5122   282.8  5145.8  282.41
  5186.2  283.06  5206.4  281.99  5337.8  284.05    5358  285.93  5368.1  285.04
  5378.3  285.27  5418.7  287.62  5519.8  291.21  5691.6  299.86  5734.6  301.42
#Mann= 12 ,-1 , 0
  4604.9     .11       0  4917.8     .11       0  4943.6     .11       0
  4953.7     .11       0  4973.9     .11       0  4982.5     .06       0
    5021     .11       0  5024.5     .11       0  5044.7     .15       0
  5085.1     .15       0  5206.4     .15       0  5418.7     .11       0
#XS Ineff= 1 ,-1
  5024.5    5350  284.02
Permanent Ineff=
       F
Bank Sta=4982.5,5021
XS Rating Curve= 0 ,0
Exp/Cntr=0.3,0.1

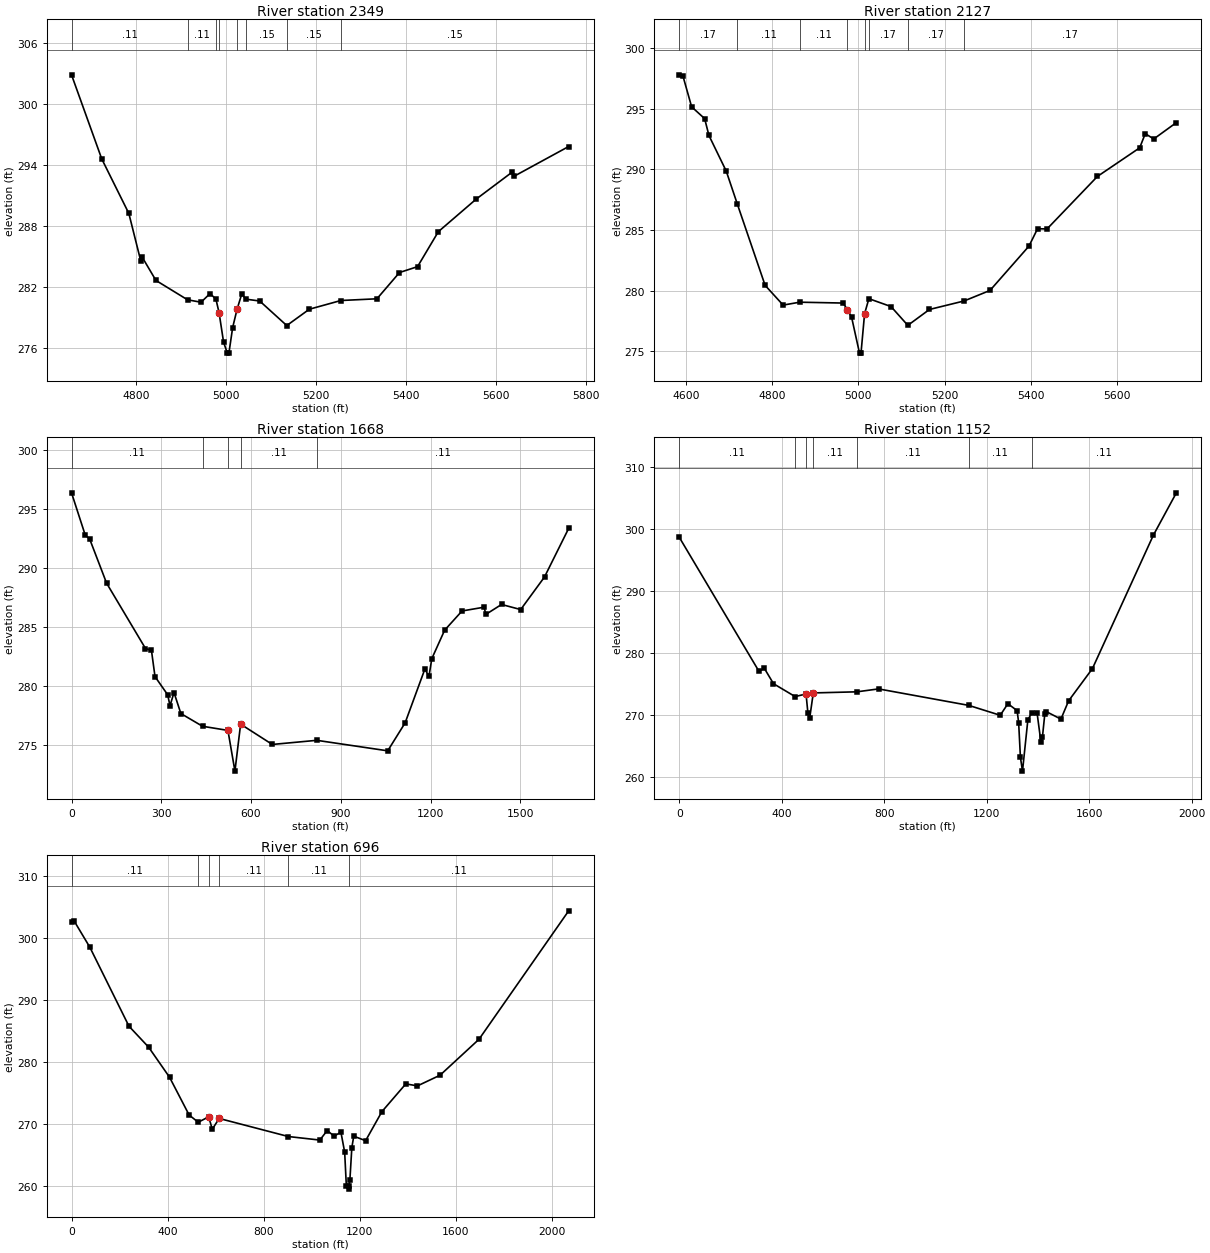
Type RM Length L Ch R = 1 ,2349    ,222,222,222
BEGIN DESCRIPTION:
WFSJR 086 2.0
END DESCRIPTION:
XS GIS Cut Line= 3
      3771467.68     10237174.31      3771452.48     10237332.77
      3771395.45     10238276.16
#Sta/Elev= 30
  4656.4   302.9  4723.5  294.61  4783.7  289.23  4810.3  284.52  4813.7  284.89
  4843.9  282.62  4914.1  280.71  4944.1  280.47  4964.2  281.33  4977.2  280.77
  4984.2  279.42  4994.2  276.52  5002.5  275.45    5006  275.45  5014.3  277.97
  5024.3  279.81  5034.3  281.25  5044.3  280.77  5074.4  280.59  5134.5  278.17
  5184.6  279.78  5254.7  280.64  5334.8  280.81  5384.9   283.4    5425  283.98
  5471.2  287.43  5555.2  290.64  5634.2  293.27  5639.2  292.89  5760.7  295.83
#Mann= 8 ,-1 , 0
  4656.4     .11       0  4914.1     .11       0  4977.2     .11       0
  4984.2     .06       0  5024.3     .11       0  5044.3     .15       0
  5134.5     .15       0  5254.7     .15       0
#XS Ineff= 1 ,-1
  5034.3    5350  281.25
Permanent Ineff=
       T
Bank Sta=4984.2,5024.3
XS Rating Curve= 0 ,0
Exp/Cntr=0.3,0.1

Type RM Length L Ch R = 1 ,2127    ,459,459,459
BEGIN DESCRIPTION:
WFSJR 086 1.0
END DESCRIPTION:
XS GIS Cut Line= 4
      3771244.15     10237122.24      3771220.67     10237383.74
      3771278.87     10237972.96      3771367.12     10238260.07
#Sta/Elev= 30
  4583.6  297.79  4592.5  297.67  4612.5  295.15  4642.7  294.18  4652.7  292.79
  4692.9  289.85  4718.7  287.13  4783.2  280.43  4825.1   278.8  4863.4  279.04
  4964.1  278.97  4974.6  278.43  4984.1  277.81  5002.5  274.84    5006  274.84
  5014.3  278.09  5024.3  279.33  5075.7  278.68  5114.8  277.13    5165  278.44
  5245.4  279.14  5305.7  280.01  5396.1  283.66  5416.2   285.1  5438.2  285.08
  5555.2  289.41  5653.4  291.77  5666.4  292.94  5686.1   292.5  5738.6  293.85
#Mann= 8 ,-1 , 0
  4583.6     .17       0  4718.7     .11       0  4863.4     .11       0
  4974.6     .06       0  5014.3     .11       0  5024.3     .17       0
  5114.8     .17       0  5245.4     .17       0
Bank Sta=4974.6,5014.3
XS Rating Curve= 0 ,0
Exp/Cntr=0.3,0.1

Type RM Length L Ch R = 1 ,1668    ,516,516,516
XS GIS Cut Line= 4
      3770992.52     10236997.83      3770745.12     10237703.55
      3770771.17     10237940.53      3771349.29     10238289.49
#Sta/Elev= 30
       0  296.36    45.8  292.78    60.6  292.45   117.3   288.7   247.2  283.17
   267.1  283.01     279  280.79   321.3  279.25   329.1  278.32   342.5  279.44
   365.4  277.66   437.9  276.58   522.7  276.23   546.1  272.78   565.1  276.76
     671  275.04   819.7  275.39  1056.7   274.5  1114.9  276.87  1180.9  281.43
  1194.5  280.81  1204.1  282.31  1246.9  284.72  1305.1  286.35  1378.8  286.67
  1384.7  286.06  1437.1   286.9  1501.1  286.47  1580.7  289.23  1661.5  293.35
#Mann= 5 ,-1 , 0
       0     .11       0   437.9     .11       0   522.7     .06       0
   565.1     .11       0   819.7     .11       0
Bank Sta=522.7,565.1
XS Rating Curve= 0 ,0
Exp/Cntr=0.3,0.1

Type RM Length L Ch R = 1 ,1152    ,456,456,456
XS GIS Cut Line= 3
      3770745.12     10236898.87      3770190.28      10237505.5
      3769263.35     10238130.64
#Sta/Elev= 30
       0  298.67   311.2  277.01   332.2  277.49     368     275   452.4  272.92
     495  273.34   502.4  270.22   509.2  269.43   523.3  273.51   693.6  273.69
     778  274.16  1129.9   271.5  1252.8   269.9  1282.7  271.77  1318.7  270.65
  1324.7  268.72  1331.6  263.12  1339.7  260.88  1360.7  269.18  1375.7  270.24
  1396.7  270.24  1411.7  265.56  1417.7  266.47  1426.6  270.03  1432.7  270.49
  1489.7  269.28  1519.6  272.23  1612.6  277.44  1850.3  298.98  1940.1  305.83
#Mann= 7 ,-1 , 0
       0     .11       0   452.4     .11       0     495     .06       0
   523.3     .11       0   693.6     .11       0  1129.9     .11       0
  1375.7     .11       0
Bank Sta=495,523.3
XS Rating Curve= 0 ,0
Exp/Cntr=0.3,0.1

Type RM Length L Ch R = 1 ,696     ,0,0,0
XS GIS Cut Line= 3
      3770612.31     10236700.95      3769388.35     10237370.22
      3769047.21     10237953.55
#Sta/Elev= 30
       0   302.6    10.7   302.8    76.2  298.56   239.3   285.8   320.9  282.43
   408.2  277.57   489.8  271.47   527.7   270.3   571.3  271.17   586.3  269.17
     615  270.91   903.4  267.99  1034.3  267.42    1065  268.96    1094  268.05
    1122  268.71  1137.7  265.48  1144.8  259.95  1153.8   259.5  1155.5 259.947
  1159.5     261  1167.6  266.22  1175.6  268.05  1224.9  267.32    1293  272.02
  1392.4  276.49    1441  276.17    1535  277.89  1697.2  283.69  2070.8  304.43
#Mann= 6 ,-1 , 0
       0     .11       0   527.7     .11       0   571.3     .06       0
     615     .11       0   903.4     .11       0  1155.5     .11       0
Bank Sta=571.3,615
XS Rating Curve= 0 ,0
Exp/Cntr=0.3,0.1

Chan Stop Cuts=-1
Use User Specified Reach Order=0
Composite Channel Slope=5