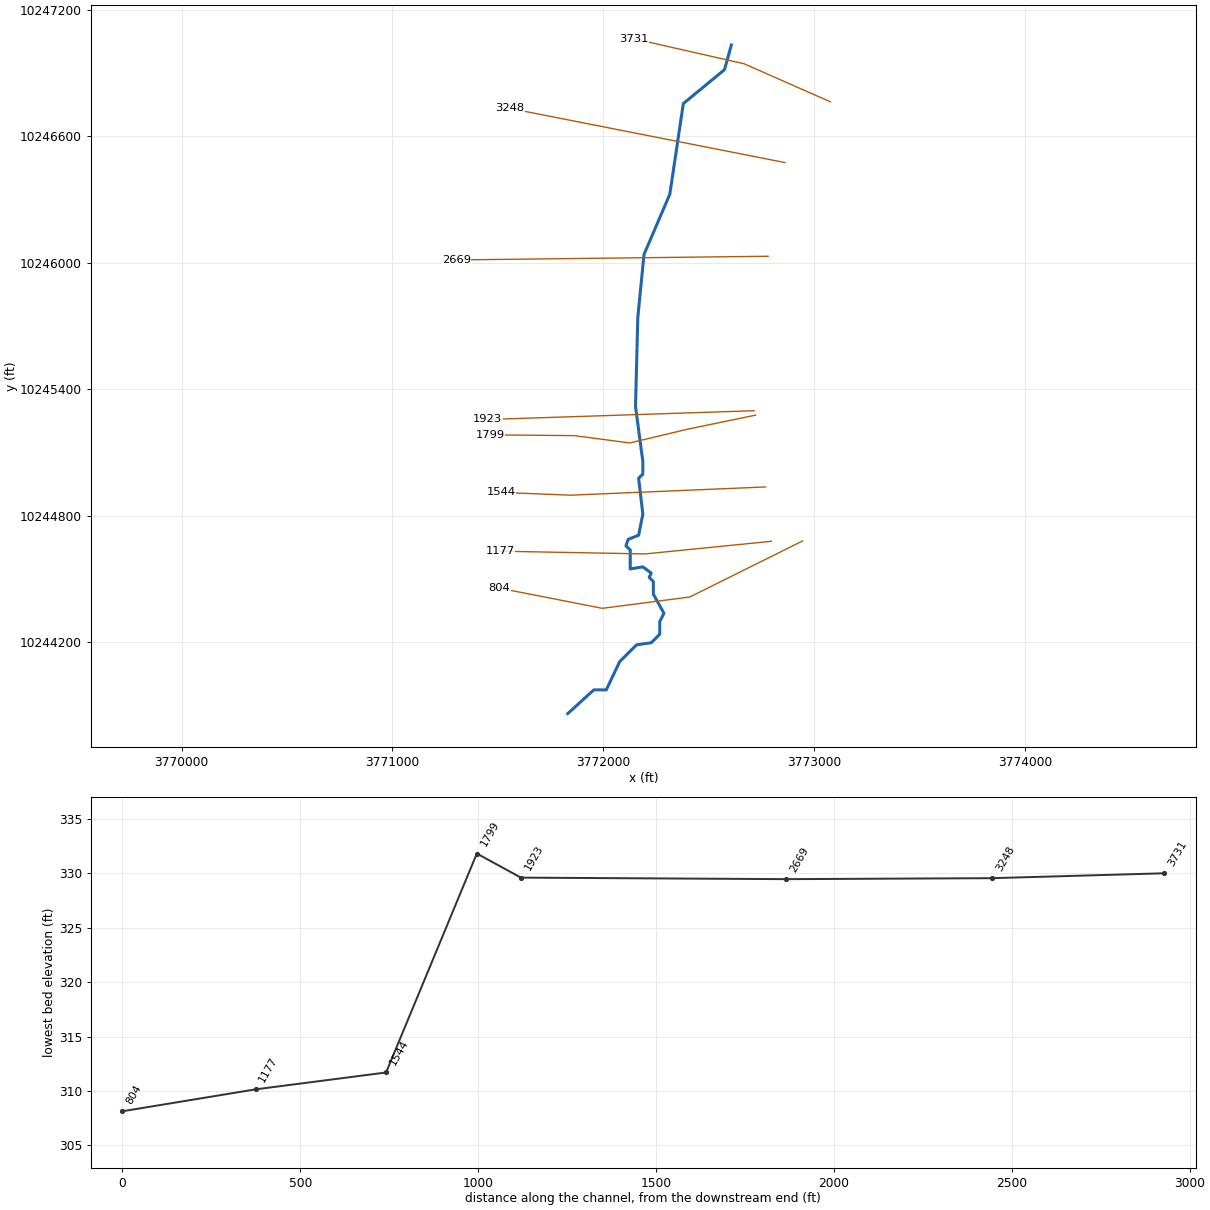
--- WFSJR 087.prj (project) ---

Proj Title=WFSJR 087 Base Level Engineering
Current Plan=p01
Default Exp/Contr=0.3,0.1
English Units
Geom File=g01
Flow File=f01
Plan File=p01
Y Axis Title=Elevation
X Axis Title(PF)=Main Channel Distance
X Axis Title(XS)=Station
BEGIN DESCRIPTION:
WFSJR 087
END DESCRIPTION:
DSS Export Rating Curves= 0
DSS Export Rating Curve Sorted= 0
DSS Export Volume Flow Curves= 0
DXF OffsetX= 0
DXF OffsetY= 0
DXF ScaleX= 1
DXF ScaleY= 10

--- WFSJR 087.p01 (plan) ---

Plan Title=Multiple Run
Program Version=4.10
Short Identifier=Multiple
Geom File=g01
Flow File=f01
Subcritical Flow
K Sum by GR= 0
Std Step Tol= 0.01
Critical Tol= 0.01
Num of Std Step Trials= 20
Max Error Tol= 0.3
Flow Tol Ratio= 0.001
Split Flow NTrial= 30
Split Flow Tol= 0.02
Split Flow Ratio= 0.02
Log Output Level= 0
Friction Slope Method= 1
Unsteady Friction Slope Method= 2
Unsteady Bridges Friction Slope Method= 1
Parabolic Critical Depth
Global Vel Dist= 1 , 1 , 1
Global Log Level= 0
CheckData=True
Encroach Param=-1 ,0,0, 0
BEGIN DESCRIPTION:
Multiple Run
END DESCRIPTION:
Computation Interval=1HOUR
Output Interval=1HOUR
Run HTab= 0
Run UNet= 0
Run PostProcess= 0
Run WQNet= 0
UNET Theta= 1
UNET Theta Warmup= 1
UNET ZTol= 0.02
UNET ZSATol= 0.05
UNET MxIter= 20
UNET MaxInSteps= 0
UNET DtIC= 0
UNET DtMin= 0
UNET MaxCRTS= 20
UNET WFStab= 2
UNET SFStab= 1
UNET WFX= 1
UNET SFX= 1
UNET DSS MLevel= 4
UNET DZMax Abort= 100
UNET Convert EG Bridges= 0
UNET Use Existing IB Tables=-1
UNET Froude Reduction=False
UNET Froude Limit= 1
UNET Froude Power= 10
UNET Time Slicing=0,0, 5
UNET Junction Losses=0
Instantaneous Interval=1HOUR
Write IC File= 0
Write IC File at Sim End=0
Echo Input=False
Echo Parameters=False
Echo Output=False
Write Detailed= 0
WQ AD Non Conservative
WQ ULTIMATE=-1
WQ Max Comp Step=1HOUR
WQ Output Interval=15MIN
WQ Output Selected Increments= 0
WQ Output face flow=0
WQ Output face velocity=0
WQ Output face area=0
WQ Output face dispersion=0
WQ Output cell volume=0
WQ Output cell surface area=0
WQ Output cell continuity=0
WQ Output cumulative cell continuity=0
WQ Output face conc=0
WQ Output face dconc_dx=0
WQ Output face courant=0
WQ Output face peclet=0
WQ Output face adv mass=0
WQ Output face disp mass=0
WQ Output cell mass=0
WQ Output cell source sink temp=0
WQ Output cell source sink nsm=0
WQ Output MaxMinRange=-1
WQ Daily Max Min Mean=-1
WQ Daily Range=0
WQ Daily Time=0
WQ Create Restart=0
WQ Fixed Restart=0
WQ System Summary=0
WQ Use Fixed Temperature=0
Sorting and Armoring Iterations= 10
XS Update Threshold= 0.02
Hydraulics Update Threshold= 0.02
Energy Slope Method= 1
Volume Change Method= 0
XS Weighting Method= 0
Number of US Weighted Cross Sections= 1
Number of DS Weighted Cross Sections= 1
Upstream XS Weight=0.25
Main XS Weight=0.5
Downstream XS Weight=0.25
Number of DS XS's Weighted with US Boundary= 1
Upstream Boundary Weight= 1
Weight of XSs Associated with US Boundary= 0
Number of US XS's Weighted with DS Boundary= 1
Downstream Boundary Weight= 0.5
Weight of XSs Associated with DS Boundary= 0.5
Sediment Output Level= 4
Mass or Volume Output= 0
Output Increment Type= 1
Profile and TS Output Increment= 10
XS Output Flag= 0
XS Output Increment= 10
Disregard all LS=0
Disregard all Conn=0
Disregard all Breaches=0
Disregard all Pumps=0

--- WFSJR 087.f01 (steady flow) ---

Flow Title=Multiple
Program Version=4.10
Number of Profiles= 7
Profile Names=10-year,25-year,50-year,1pct_min,100-year,1pct_plu,500-year
River Rch & RM=WFSJR 087,Reach-1         ,3731
     391     517     689     303     915    2763    1667
River Rch & RM=WFSJR 087,Reach-1         ,3248
     495     661     886     391    1182    3570    2169
River Rch & RM=WFSJR 087,Reach-1         ,1544
     538     723     973     432    1304    3938    2417
Boundary for River Rch & Prof#=WFSJR 087,Reach-1         , 1
Up Type= 0
Dn Type= 3
Dn Slope=0.006
Boundary for River Rch & Prof#=WFSJR 087,Reach-1         , 2
Up Type= 0
Dn Type= 3
Dn Slope=0.006
Boundary for River Rch & Prof#=WFSJR 087,Reach-1         , 3
Up Type= 0
Dn Type= 3
Dn Slope=0.006
Boundary for River Rch & Prof#=WFSJR 087,Reach-1         , 4
Up Type= 0
Dn Type= 3
Dn Slope=0.006
Boundary for River Rch & Prof#=WFSJR 087,Reach-1         , 5
Up Type= 0
Dn Type= 3
Dn Slope=0.006
Boundary for River Rch & Prof#=WFSJR 087,Reach-1         , 6
Up Type= 0
Dn Type= 3
Dn Slope=0.006
Boundary for River Rch & Prof#=WFSJR 087,Reach-1         , 7
Up Type= 0
Dn Type= 3
Dn Slope=0.006
DSS Import GetInterval= 0
DSS Import GetPeak= 0
DSS Import FillOption= 0

--- WFSJR 087.g01 (geometry) ---

Geom Title=Existing Conditions
Program Version=4.10

River Reach=WFSJR 087       ,Reach-1
Reach XY= 30
      3772608.14     10247032.02      3772575.59     10246914.83
      3772380.28     10246754.24      3772316.26     10246324.55
      3772193.65     10246038.09      3772164.35      10245739.7
       3772153.5     10245316.52      3772188.23     10245056.84
      3772188.23     10244996.84      3772168.23     10244976.84
      3772188.23     10244806.84      3772168.23     10244706.84
      3772118.23     10244686.84      3772108.23     10244656.84
      3772128.23     10244636.84      3772128.23     10244546.84
      3772188.23     10244556.84      3772228.23     10244526.84
      3772218.23     10244506.84      3772238.23     10244486.84
      3772238.23     10244426.84      3772288.23     10244336.84
      3772268.23     10244296.84      3772268.23     10244236.84
      3772228.23     10244196.84      3772158.23     10244186.84
      3772078.47     10244107.48      3772014.56     10243973.02
      3771955.91     10243973.39      3771832.12     10243860.89

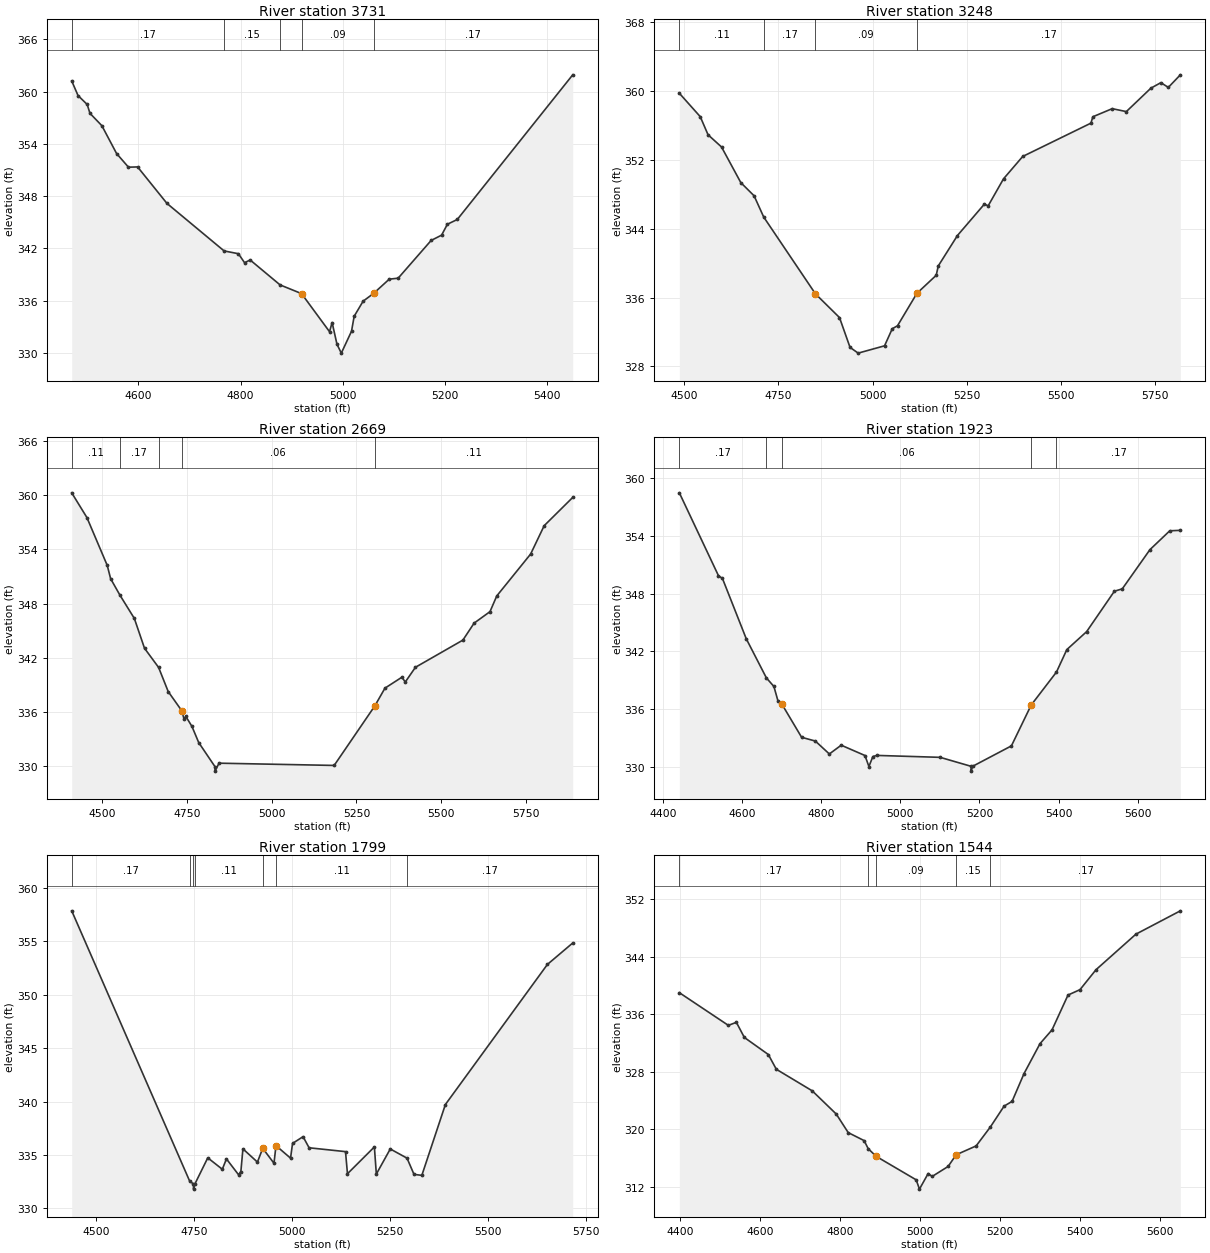
Type RM Length L Ch R = 1 ,3731    ,483,483,483
BEGIN DESCRIPTION:
WFSJR 087 2.0
END DESCRIPTION:
XS GIS Cut Line= 3
      3773077.83     10246762.63      3772668.11     10246943.19
      3772147.26     10247061.25
#Sta/Elev= 30
  4469.2  361.23  4481.6  359.55  4499.5  358.53    4505  357.51  4528.3  356.09
  4557.1   352.9  4580.4  351.33  4598.3  351.36  4655.9  347.17  4767.8  341.72
  4795.8   341.4  4807.9  340.37  4818.9  340.68  4877.5  337.82  4919.6  336.82
  4974.4  332.45  4979.5   333.5    4989  331.01  4997.5  329.99  5017.5   332.5
  5022.7  334.22  5040.2  335.95  5060.7  336.84  5091.5  338.48  5108.9  338.59
  5173.5  342.92    5194  343.53  5205.4  344.78  5224.8  345.33    5451  361.93
#Mann= 5 ,-1 , 0
  4469.2     .17       0  4767.8     .15       0  4877.5     .17       0
  4919.6     .09       0  5060.7     .17       0
Bank Sta=4919.6,5060.7
XS Rating Curve= 0 ,0
Exp/Cntr=0.3,0.1

Type RM Length L Ch R = 1 ,3248    ,579,579,579
BEGIN DESCRIPTION:
Mapping XS 1356b7ad
END DESCRIPTION:
XS GIS Cut Line= 2
      3772862.59     10246474.43      3771557.04     10246731.37
#Sta/Elev= 30
    4487  359.72  4542.5     357  4563.2   354.9    4599  353.48  4650.3  349.34
  4685.5  347.81  4711.1  345.34  4848.5  336.42  4912.3  333.67  4940.3  330.21
  4961.9  329.54    5032  330.39  5052.4  332.37  5066.4  332.72  5117.8  336.48
  5169.2  338.58  5174.7  339.67  5225.6   343.2    5297  346.84  5307.2  346.65
  5347.9  349.78  5398.9  352.38  5580.1  356.25  5585.2  356.99  5636.6  357.93
  5674.1  357.59  5739.3  360.31  5765.8  360.95  5785.6   360.4  5817.6  361.86
#Mann= 4 ,-1 , 0
    4487     .11       0  4711.1     .17       0  4848.5     .09       0
  5117.8     .17       0
Bank Sta=4848.5,5117.8
XS Rating Curve= 0 ,0
Exp/Cntr=0.3,0.1

Type RM Length L Ch R = 1 ,2669    ,746,746,746
BEGIN DESCRIPTION:
Mapping XS 7002ecc5
END DESCRIPTION:
XS GIS Cut Line= 2
      3772782.73     10246029.99      3771303.53     10246012.63
#Sta/Elev= 30
  4409.4  360.27  4454.3  357.53  4514.3  352.23  4524.3  350.76  4552.2  348.91
  4594.3  346.36  4624.3  343.06    4666  340.93  4694.3  338.26  4734.3  336.14
  4741.4  335.17  4746.4   335.5  4764.3  334.41  4784.3  332.62  4832.3  329.95
  4832.6  329.45  4844.3  330.33  5184.3  330.08  5304.3  336.67  5334.3  338.64
  5384.3  339.85  5394.3  339.32  5424.3  340.95  5564.4  343.96  5597.5  345.84
  5644.4  347.11  5664.4  348.85  5764.4  353.49  5804.4  356.63  5888.7  359.76
#Mann= 5 ,-1 , 0
  4409.4     .11       0  4552.2     .17       0    4666     .11       0
  4734.3     .06       0  5304.3     .11       0
Bank Sta=4734.3,5304.3
XS Rating Curve= 0 ,0
Exp/Cntr=0.3,0.1

Type RM Length L Ch R = 1 ,1923    ,124,124,124
BEGIN DESCRIPTION:
Mapping XS 73bd6c46
END DESCRIPTION:
XS GIS Cut Line= 2
      3772716.71     10245297.35       3771451.1     10245255.74
#Sta/Elev= 30
  4441.5  358.46  4540.4  349.86  4550.4  349.58  4610.5  343.33  4661.5  339.26
  4680.5  338.37  4690.5  336.91  4700.5  336.55  4750.5   333.1  4785.2  332.71
  4820.6  331.37  4850.6  332.28  4910.6  331.21  4920.6  330.07  4930.6   331.1
  4940.6  331.22  5100.7  331.02  5178.8  330.09    5179  329.59  5182.8  330.09
  5280.8  332.21  5330.8  336.45  5394.7  339.87  5420.9   342.2  5470.9  344.06
    5541  348.25    5561   348.5    5631  352.57    5681  354.52  5707.8  354.57
#Mann= 5 ,-1 , 0
  4441.5     .17       0  4661.5     .11       0  4700.5     .06       0
  5330.8     .11       0  5394.7     .17       0
Bank Sta=4700.5,5330.8
XS Rating Curve= 0 ,0
Exp/Cntr=0.3,0.1

Type RM Length L Ch R = 1 ,1799    ,255,255,255
BEGIN DESCRIPTION:
Mapping XS e6fd928d
END DESCRIPTION:
XS GIS Cut Line= 5
      3772723.64     10245276.51      3772404.22     10245210.55
      3772126.44     10245144.58      3771862.55      10245179.3
      3771463.29     10245182.77
#Sta/Elev= 30
  4438.2  357.85  4739.1  332.53  4748.4   332.3  4748.7   331.8  4752.4   332.3
    4785  334.73  4822.1  333.66  4832.6  334.63  4863.4  333.15  4869.4  333.45
  4874.6  335.57  4911.6  334.33  4925.1  335.62  4953.8  334.22  4958.9  335.87
    4996   334.7  5001.1  336.08  5027.9  336.71  5043.3  335.67  5136.1  335.31
  5141.1  333.24  5209.7  335.75  5214.7  333.21  5250.2  335.56  5292.9   334.7
  5310.7  333.18  5330.7  333.09  5390.7  339.72  5650.7  352.83  5715.3  354.84
#Mann= 7 ,-1 , 0
  4438.2     .17       0  4739.1     .11       0  4748.4     .11       0
  4752.4     .11       0  4925.1     .06       0  4958.9     .11       0
  5292.9     .17       0
#XS Ineff= 2 ,-1
    4680  4874.6  335.57  5027.9    5380  336.71
Permanent Ineff=
       T       T
Bank Sta=4925.1,4958.9
XS Rating Curve= 0 ,0
Exp/Cntr=0.3,0.1

Type RM Length L Ch R = 1 ,1544    ,367,367,367
BEGIN DESCRIPTION:
Mapping XS 3bf82ff3
END DESCRIPTION:
XS GIS Cut Line= 3
      3772770.49     10244935.81      3771846.06     10244896.75
      3771516.67     10244909.77
#Sta/Elev= 30
  4397.2  338.99  4519.9  334.45    4540  334.87    4560  332.77    4620   330.4
  4640.1  328.35  4730.1  325.35  4790.2  322.13  4820.2  319.55    4860  318.44
  4870.3  317.31  4890.3  316.25  4990.4  312.99  4998.6   311.7  5020.4  313.87
  5030.4  313.46  5070.4  314.85  5090.5  316.47  5140.5   317.7  5176.3  320.34
  5210.6  323.23  5230.6  323.89  5260.6  327.76  5300.6  331.91  5330.7  333.83
  5370.7  338.66  5400.7  339.41  5440.8  342.18  5540.8  347.12  5652.1  350.36
#Mann= 5 ,-1 , 0
  4397.2     .17       0  4870.3     .15       0  4890.3     .09       0
  5090.5     .15       0  5176.3     .17       0
Bank Sta=4890.3,5090.5
XS Rating Curve= 0 ,0
Exp/Cntr=0.3,0.1

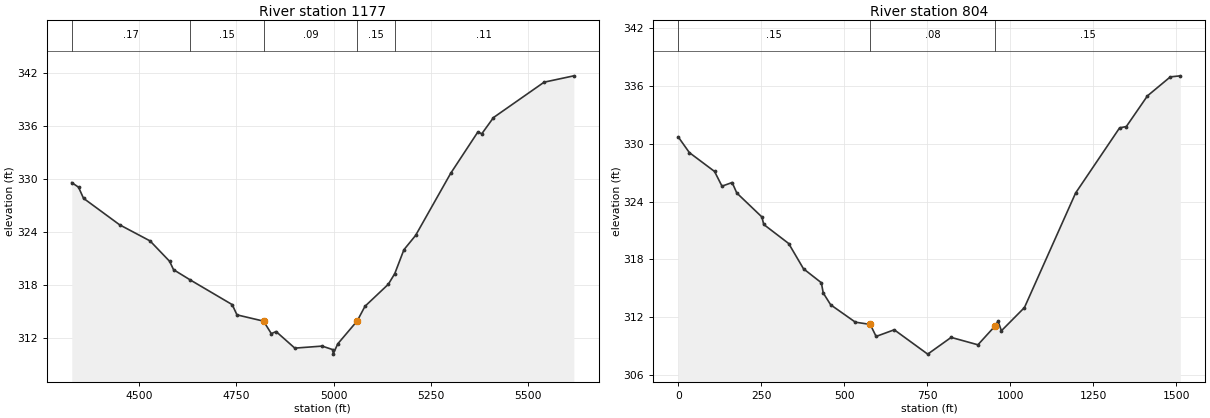
Type RM Length L Ch R = 1 ,1177    ,374,374,374
BEGIN DESCRIPTION:
WFSJR 087 1.0
END DESCRIPTION:
XS GIS Cut Line= 3
      3772797.93       10244678.      3772198.93      10244618.1
      3771511.44      10244631.1
#Sta/Elev= 30
  4327.3  329.59  4344.6  329.07  4357.5  327.81  4450.1  324.81  4528.4  322.98
  4578.6  320.67  4588.7  319.72  4631.2  318.57  4739.4  315.76  4751.6   314.6
  4819.8  313.89  4839.9  312.47  4852.1  312.71  4900.2  310.83  4970.4  311.06
  4998.4  310.65  4998.6  310.15  5010.4  311.31  5060.4  313.91  5080.4  315.57
  5140.4  318.07    5157  319.28  5180.4  321.98  5210.4   323.6  5300.4  330.63
  5370.4  335.33  5380.4  335.12  5410.5  336.96  5540.5  340.97  5616.9  341.69
#Mann= 5 ,-1 , 0
  4327.3     .17       0  4631.2     .15       0  4819.8     .09       0
  5060.4     .15       0    5157     .11       0
Bank Sta=4819.8,5060.4
XS Rating Curve= 0 ,0
Exp/Cntr=0.3,0.1

Type RM Length L Ch R = 1 ,804     ,0,0,0
XS GIS Cut Line= 4
      3772945.85     10244679.52      3772411.13     10244413.89
       3771996.2     10244360.07      3771508.35     10244455.56
#Sta/Elev= 30
       0  330.72    33.5  329.09   109.4  327.13   131.8   325.6   162.4  325.98
   176.4  324.89     252   322.4   257.6  321.62   332.7  319.64   377.4  317.01
   431.2  315.56   436.8   314.5   459.2  313.27   533.7  311.46   578.4  311.23
   596.1  309.98   650.8  310.67   751.6  308.14   822.2  309.88   902.9  309.11
   953.3  311.02   963.4  311.56   973.7  310.57    1043  312.98  1197.2  324.89
  1329.7  331.66    1350   331.8  1413.7  334.99  1482.5  336.96  1512.6  337.07
#Mann= 3 , 0 , 0
       0     .15       0   578.4     .08       0   953.3     .15       0
Bank Sta=578.4,953.3
XS Rating Curve= 0 ,0
Exp/Cntr=0.3,0.1
Stream Node=WFSJR 087       ,Reach-1         , 0 , 0 ,Upstream end
Stream Node=WFSJR 087       ,Reach-1         , 0 , 1 ,Downstream end

Chan Stop Cuts=-1
Use User Specified Reach Order=0
Composite Channel Slope=5