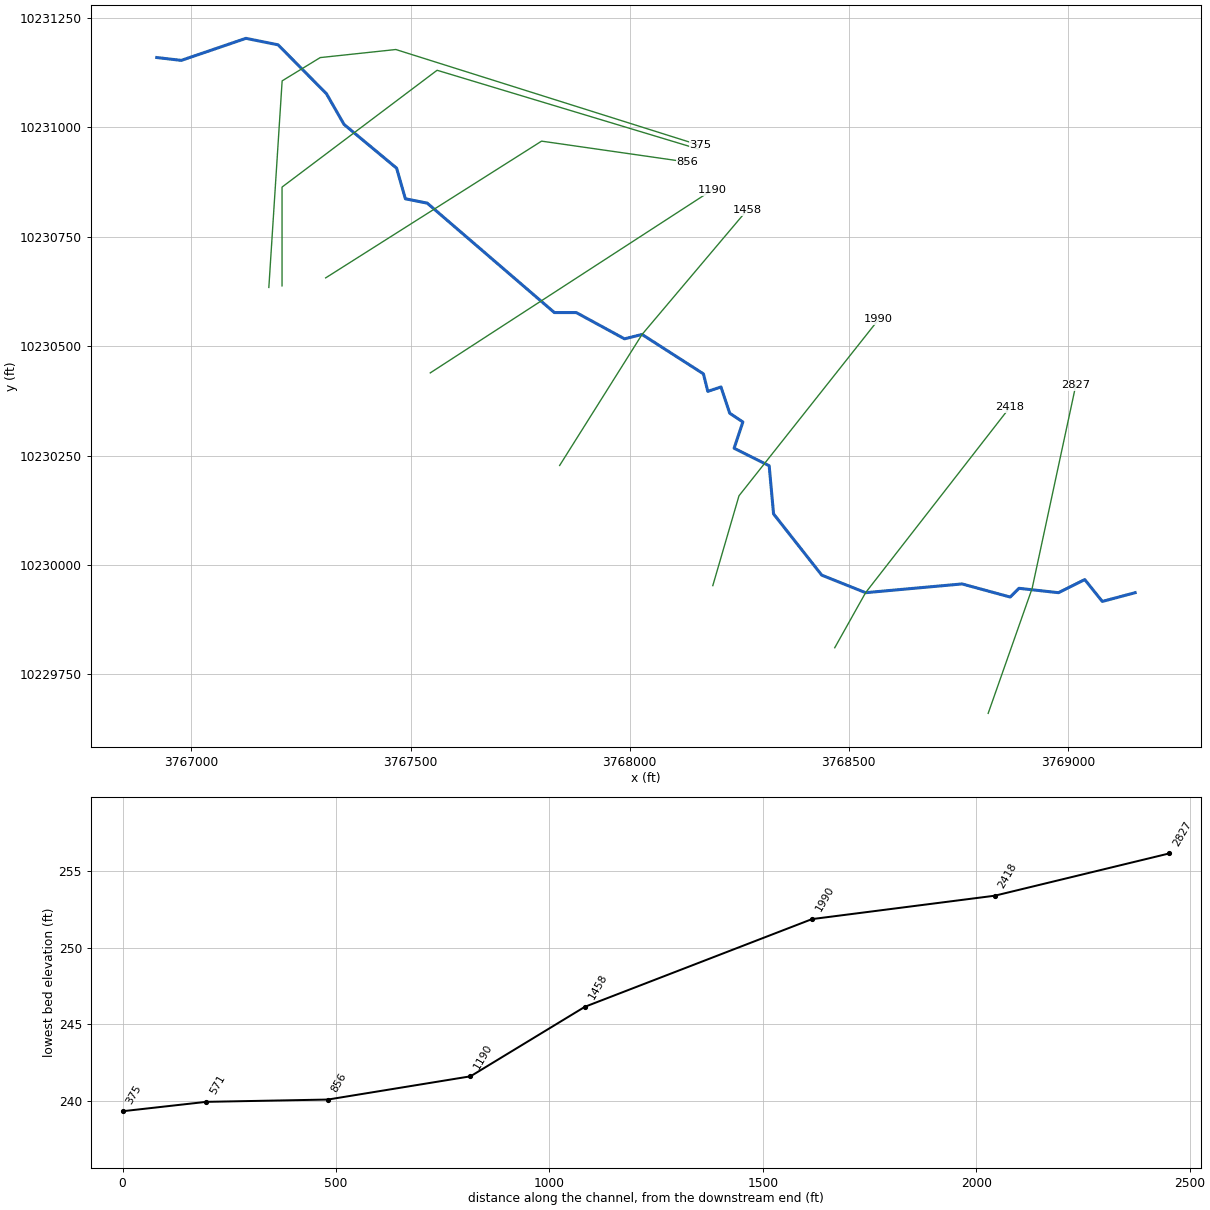
--- WFSJR 089.prj (project) ---

Proj Title=WFSJR 089 Base Level Engineering
Current Plan=p01
Default Exp/Contr=0.3,0.1
English Units
Geom File=g01
Flow File=f01
Plan File=p01
Y Axis Title=Elevation
X Axis Title(PF)=Main Channel Distance
X Axis Title(XS)=Station
BEGIN DESCRIPTION:
WFSJR 089
END DESCRIPTION:
DSS Export Rating Curves= 0
DSS Export Rating Curve Sorted= 0
DSS Export Volume Flow Curves= 0
DXF OffsetX= 0
DXF OffsetY= 0
DXF ScaleX= 1
DXF ScaleY= 10

--- WFSJR 089.p01 (plan) ---

Plan Title=Multiple Run
Program Version=4.10
Short Identifier=Multiple
Geom File=g01
Flow File=f01
Subcritical Flow
K Sum by GR= 0
Std Step Tol= 0.01
Critical Tol= 0.01
Num of Std Step Trials= 20
Max Error Tol= 0.3
Flow Tol Ratio= 0.001
Split Flow NTrial= 30
Split Flow Tol= 0.02
Split Flow Ratio= 0.02
Log Output Level= 0
Friction Slope Method= 1
Unsteady Friction Slope Method= 2
Unsteady Bridges Friction Slope Method= 1
Parabolic Critical Depth
Global Vel Dist= 1 , 1 , 1
Global Log Level= 0
CheckData=True
Encroach Param=-1 ,0,0, 0
BEGIN DESCRIPTION:
Multiple Run
END DESCRIPTION:
Computation Interval=1HOUR
Output Interval=1HOUR
Run HTab= 0
Run UNet= 0
Run PostProcess= 0
Run WQNet= 0
UNET Theta= 1
UNET Theta Warmup= 1
UNET ZTol= 0.02
UNET ZSATol= 0.05
UNET MxIter= 20
UNET MaxInSteps= 0
UNET DtIC= 0
UNET DtMin= 0
UNET MaxCRTS= 20
UNET WFStab= 2
UNET SFStab= 1
UNET WFX= 1
UNET SFX= 1
UNET DSS MLevel= 4
UNET DZMax Abort= 100
UNET Convert EG Bridges= 0
UNET Use Existing IB Tables=-1
UNET Froude Reduction=False
UNET Froude Limit= 1
UNET Froude Power= 10
UNET Time Slicing=0,0, 5
UNET Junction Losses=0
Instantaneous Interval=1HOUR
Write IC File= 0
Write IC File at Sim End=0
Echo Input=False
Echo Parameters=False
Echo Output=False
Write Detailed= 0
WQ AD Non Conservative
WQ ULTIMATE=-1
WQ Max Comp Step=1HOUR
WQ Output Interval=15MIN
WQ Output Selected Increments= 0
WQ Output face flow=0
WQ Output face velocity=0
WQ Output face area=0
WQ Output face dispersion=0
WQ Output cell volume=0
WQ Output cell surface area=0
WQ Output cell continuity=0
WQ Output cumulative cell continuity=0
WQ Output face conc=0
WQ Output face dconc_dx=0
WQ Output face courant=0
WQ Output face peclet=0
WQ Output face adv mass=0
WQ Output face disp mass=0
WQ Output cell mass=0
WQ Output cell source sink temp=0
WQ Output cell source sink nsm=0
WQ Output MaxMinRange=-1
WQ Daily Max Min Mean=-1
WQ Daily Range=0
WQ Daily Time=0
WQ Create Restart=0
WQ Fixed Restart=0
WQ System Summary=0
WQ Use Fixed Temperature=0
Sorting and Armoring Iterations= 10
XS Update Threshold= 0.02
Hydraulics Update Threshold= 0.02
Energy Slope Method= 1
Volume Change Method= 0
XS Weighting Method= 0
Number of US Weighted Cross Sections= 1
Number of DS Weighted Cross Sections= 1
Upstream XS Weight=0.25
Main XS Weight=0.5
Downstream XS Weight=0.25
Number of DS XS's Weighted with US Boundary= 1
Upstream Boundary Weight= 1
Weight of XSs Associated with US Boundary= 0
Number of US XS's Weighted with DS Boundary= 1
Downstream Boundary Weight= 0.5
Weight of XSs Associated with DS Boundary= 0.5
Sediment Output Level= 4
Mass or Volume Output= 0
Output Increment Type= 1
Profile and TS Output Increment= 10
XS Output Flag= 0
XS Output Increment= 10
Disregard all LS=0
Disregard all Conn=0
Disregard all Breaches=0
Disregard all Pumps=0

--- WFSJR 089.f01 (steady flow) ---

Flow Title=Multiple
Program Version=4.10
Number of Profiles= 7
Profile Names=10-year,25-year,50-year,1pct_min,100-year,1pct_plu,500-year
River Rch & RM=WFSJR 089,Reach-1         ,2827
     584     789    1066     475    1434    4331    2675
Boundary for River Rch & Prof#=WFSJR 089,Reach-1         , 1
Up Type= 0
Dn Type= 3
Dn Slope=0.006
Boundary for River Rch & Prof#=WFSJR 089,Reach-1         , 2
Up Type= 0
Dn Type= 3
Dn Slope=0.006
Boundary for River Rch & Prof#=WFSJR 089,Reach-1         , 3
Up Type= 0
Dn Type= 3
Dn Slope=0.006
Boundary for River Rch & Prof#=WFSJR 089,Reach-1         , 4
Up Type= 0
Dn Type= 3
Dn Slope=0.006
Boundary for River Rch & Prof#=WFSJR 089,Reach-1         , 5
Up Type= 0
Dn Type= 3
Dn Slope=0.006
Boundary for River Rch & Prof#=WFSJR 089,Reach-1         , 6
Up Type= 0
Dn Type= 3
Dn Slope=0.006
Boundary for River Rch & Prof#=WFSJR 089,Reach-1         , 7
Up Type= 0
Dn Type= 3
Dn Slope=0.006
DSS Import GetInterval= 0
DSS Import GetPeak= 0
DSS Import FillOption= 0

--- WFSJR 089.g01 (geometry) ---

Geom Title=Existing Conditions
Program Version=4.10

River Reach=WFSJR 089       ,Reach-1
Reach XY= 30
      3769153.23     10229936.84      3769078.23     10229916.84
      3769038.23     10229966.84      3768978.23     10229936.84
      3768888.23     10229946.84      3768868.23     10229926.84
      3768758.23     10229956.84      3768538.23     10229936.84
      3768438.23     10229976.84      3768328.23     10230116.84
      3768318.23     10230226.84      3768238.23     10230266.84
      3768258.23     10230326.84      3768228.23     10230346.84
      3768208.23     10230406.84      3768178.23     10230396.84
      3768168.23     10230436.84      3768028.23     10230526.84
      3767988.23     10230516.84      3767878.23     10230576.84
      3767828.23     10230576.84      3767538.23     10230826.84
      3767488.23     10230836.84      3767468.23     10230906.84
      3767348.23     10231006.84      3767308.23     10231076.84
      3767197.78     10231188.67      3767124.49     10231203.47
      3766977.04     10231153.08      3766921.02     10231159.62

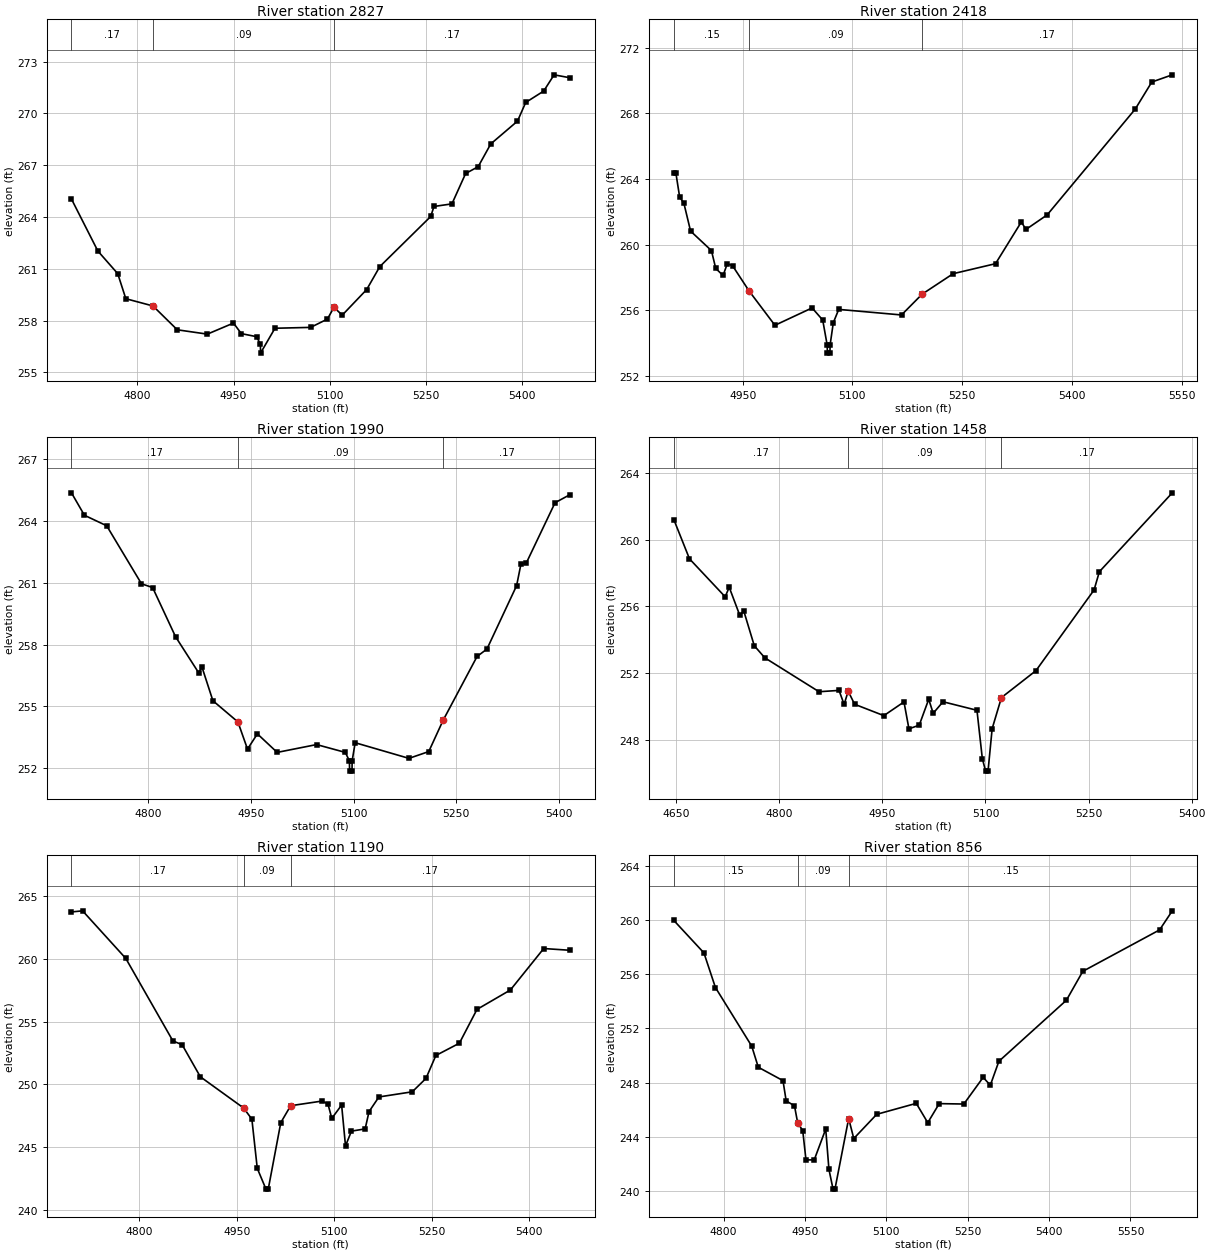
Type RM Length L Ch R = 1 ,2827    ,409,409,409
BEGIN DESCRIPTION:
WFSJR 089 5.0
END DESCRIPTION:
XS GIS Cut Line= 3
      3768817.85     10229661.06      3768918.23     10229946.84
      3769017.85     10230411.08
#Sta/Elev= 30
  4697.1  265.04  4738.3  262.03  4769.3  260.72  4781.9  259.27  4824.3  258.85
  4862.2  257.47  4909.1  257.22  4949.9  257.86  4962.1  257.25  4986.2  257.07
  4991.9  256.62  4992.1  256.12  5014.6  257.56  5070.2  257.61  5096.4  258.09
  5106.6  258.77  5119.6  258.32  5157.7   259.8  5178.2  261.13  5257.6  264.03
  5262.7  264.61  5290.7  264.76  5312.1  266.52  5331.6  266.91  5351.3  268.23
    5393  269.55  5405.8  270.63  5433.9  271.29  5450.1  272.23  5474.8  272.06
#Mann= 3 , 0 , 0
  4697.1     .17       0  4824.3     .09       0  5106.6     .17       0
Bank Sta=4824.3,5106.6
XS Rating Curve= 0 ,0
Exp/Cntr=0.3,0.1

Type RM Length L Ch R = 1 ,2418    ,428,428,428
BEGIN DESCRIPTION:
WFSJR 089 4.0
END DESCRIPTION:
XS GIS Cut Line= 3
      3768467.86     10229811.09      3768538.23     10229936.84
      3768867.83     10230361.05
#Sta/Elev= 30
  4855.9  264.37  4858.7  264.37  4863.9  262.89  4869.6  262.53  4878.8  260.82
  4907.3  259.63  4913.2  258.54  4923.2  258.11    4929  258.83  4936.1  258.71
    4959  257.15  4994.1  255.07  5044.9  256.13  5059.4  255.39  5065.5  253.87
  5065.8  253.37  5069.3  253.37  5069.5  253.87  5073.9  255.23  5081.3  256.04
  5167.1   255.7  5195.3  256.97  5237.7  258.22  5295.6  258.83  5330.9  261.38
  5337.2  260.92  5366.2  261.81  5486.6  268.27  5509.2  269.92  5537.2  270.36
#Mann= 3 , 0 , 0
  4855.9     .15       0    4959     .09       0  5195.3     .17       0
Bank Sta=4959,5195.3
XS Rating Curve= 0 ,0
Exp/Cntr=0.3,0.1

Type RM Length L Ch R = 1 ,1990    ,532,532,532
BEGIN DESCRIPTION:
WFSJR 089 3.0
END DESCRIPTION:
XS GIS Cut Line= 3
      3768189.62     10229952.92      3768249.38     10230158.24
      3768567.88     10230561.11
#Sta/Elev= 30
  4688.3  265.37  4707.2  264.28  4739.7  263.77  4790.5  260.95  4806.7  260.77
  4840.2  258.38  4873.7  256.64  4878.9  256.89  4894.7  255.27  4931.2  254.24
  4945.2  252.92  4959.6  253.66  4988.5  252.76    5046  253.14  5087.9  252.76
  5093.9  252.35  5094.2  251.85  5097.7  251.85  5097.9  252.35  5102.3  253.23
  5180.8  252.47  5209.7   252.8  5230.5  254.31  5280.2  257.42  5294.6  257.78
  5337.9  260.86  5344.3  261.92  5351.9  261.95    5394  264.89  5415.7  265.28
#Mann= 3 , 0 , 0
  4688.3     .17       0  4931.2     .09       0  5230.5     .17       0
Bank Sta=4931.2,5230.5
XS Rating Curve= 0 ,0
Exp/Cntr=0.3,0.1

Type RM Length L Ch R = 1 ,1458    ,268,268,268
BEGIN DESCRIPTION:
WFSJR 089 2.0
END DESCRIPTION:
XS GIS Cut Line= 3
      3767840.22     10230227.49      3768028.23     10230526.84
      3768267.88      10230811.1
#Sta/Elev= 30
  4646.5   261.2  4669.3  258.85  4721.2  256.58  4727.1  257.15  4742.4  255.48
  4748.3  255.73  4763.6  253.65  4778.9  252.93  4857.8   250.9  4886.9  250.98
  4894.3  250.14  4900.2  250.93  4909.6  250.15  4952.1  249.47  4981.4  250.29
  4988.6  248.68  5003.6   248.9  5017.4  250.45  5023.9  249.61  5038.2   250.3
  5087.6  249.79  5095.4   246.9  5100.2  246.15  5103.7  246.15  5109.7  248.69
  5123.2  250.55  5173.4  252.16    5258  256.99  5265.7  258.08  5371.8   262.8
#Mann= 3 ,-1 , 0
  4646.5     .17       0  4900.2     .09       0  5123.2     .17       0
Bank Sta=4900.2,5123.2
XS Rating Curve= 0 ,0
Exp/Cntr=0.3,0.1

Type RM Length L Ch R = 1 ,1190    ,334,334,334
BEGIN DESCRIPTION:
Mapping XS bb0f9c30
END DESCRIPTION:
XS GIS Cut Line= 2
      3767545.06     10230439.05       3768188.2     10230856.98
#Sta/Elev= 30
  4695.7  263.76  4712.8  263.85  4779.3  260.05  4851.8  253.46    4866  253.16
    4894   250.6  4960.5  248.11  4973.3  247.22  4981.6  243.29    4995  241.63
  4998.5  241.63  5017.8  246.94    5033  248.29  5081.1  248.66  5090.3  248.44
  5096.3  247.28  5111.4  248.34  5117.4  245.08  5126.5  246.26  5147.6  246.44
  5153.6  247.82  5168.8  248.99  5220.1   249.4  5241.2  250.47  5256.4   252.3
  5292.6  253.28  5319.7  255.98  5371.1  257.53  5422.4  260.84  5462.7   260.7
#Mann= 3 ,-1 , 0
  4695.7     .17       0  4960.5     .09       0    5033     .17       0
#XS Ineff= 1 ,-1
  5081.1    5175  248.66
Permanent Ineff=
       F
Bank Sta=4960.5,5033
XS Rating Curve= 0 ,0
Exp/Cntr=0.3,0.1

Type RM Length L Ch R = 1 ,856     ,285,285,285
BEGIN DESCRIPTION:
WFSJR 089 1.0
END DESCRIPTION:
XS GIS Cut Line= 3
       3767306.4      10230656.1        3767799.     10230968.58
      3768131.03     10230920.84
#Sta/Elev= 30
  4708.3  259.98  4763.8  257.58    4785  255.02  4851.9  250.69    4864  249.13
  4909.5  248.14  4915.4  246.64  4930.7  246.28  4936.6  245.02  4945.9  244.45
  4951.9  242.28  4967.1  242.28  4988.3  244.56  4994.2  241.58  5001.8  240.12
  5005.3  240.12  5030.6  245.34    5040  243.86  5082.3  245.65  5155.2  246.46
  5176.4  245.03  5197.5  246.44  5242.9  246.41  5278.5  248.38  5291.7   247.8
  5307.5  249.57  5431.9  254.08  5462.2  256.22  5603.7  259.28  5627.1  260.69
#Mann= 3 , 0 , 0
  4708.3     .15       0  4936.6     .09       0  5030.6     .15       0
#XS Ineff= 1 ,-1
  5155.2    5260  246.46
Permanent Ineff=
       F
Bank Sta=4936.6,5030.6
XS Rating Curve= 0 ,0
Exp/Cntr=0.3,0.1

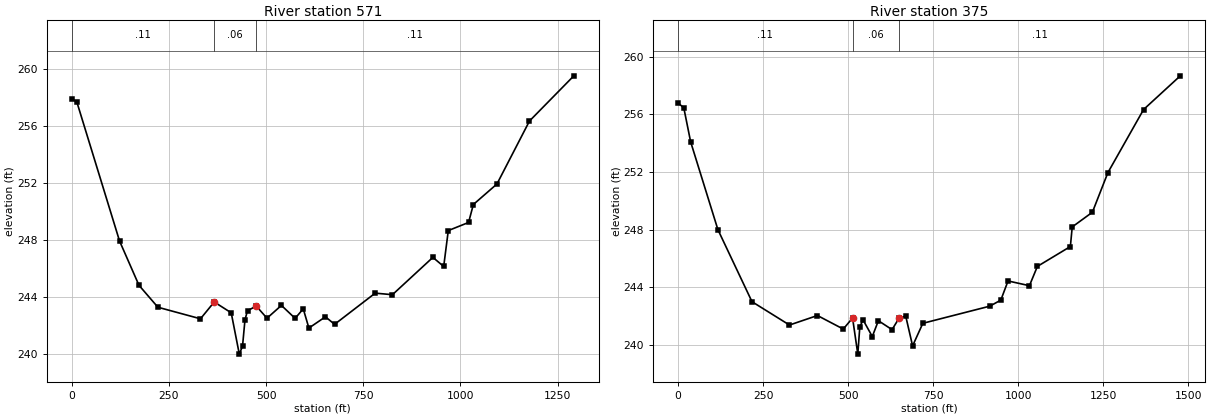
Type RM Length L Ch R = 1 ,571     ,196,196,196
XS GIS Cut Line= 4
      3767206.86     10230637.89      3767206.86     10230863.59
       3767560.6     10231130.52        3768157.     10230950.36
#Sta/Elev= 30
       0  257.89    13.2  257.68   123.2  247.91   173.2   244.8   221.9  243.26
   331.4  242.45   366.8  243.63   410.5  242.87   431.3  239.97   439.6  240.53
   445.9  242.38   452.4  243.02     475  243.34   502.5  242.49   539.6  243.39
   574.9  242.48   595.8  243.15   610.3   241.8   652.9  242.59   676.4  242.06
   780.9  244.25   825.2  244.14   929.3  246.76   957.1  246.12   968.9  248.64
  1021.1  249.21  1033.4  250.47  1094.1  251.91  1177.8  256.33  1291.9   259.5
#Mann= 3 , 0 , 0
       0     .11       0   366.8     .06       0     475     .11       0
Bank Sta=366.8,475
XS Rating Curve= 0 ,0
Exp/Cntr=0.3,0.1

Type RM Length L Ch R = 1 ,375     ,0,0,0
XS GIS Cut Line= 5
      3767176.73      10230634.3      3767207.11      10231106.3
      3767293.92     10231159.47      3767466.44     10231177.92
      3768160.89     10230958.73
#Sta/Elev= 30
       0   256.8    16.8  256.45    36.8   254.1     117     248   217.2     243
   327.4  241.38   409.6  242.04   485.6   241.1   512.9  241.87   528.3  239.36
   534.2  241.25   543.7  241.74   570.9  240.58   588.8  241.68     629  241.06
   649.1  241.84   669.2     242   689.4  239.93   719.5   241.5   916.4  242.69
   948.8  243.11     970  244.44  1032.9  244.11  1056.3  245.45  1153.3  246.83
  1158.7  248.19    1218  249.21  1263.6  251.96  1368.5  256.34  1476.5  258.68
#Mann= 3 , 0 , 0
       0     .11       0   512.9     .06       0   649.1     .11       0
Bank Sta=512.9,649.1
XS Rating Curve= 0 ,0
Exp/Cntr=0.3,0.1

Chan Stop Cuts=-1
Use User Specified Reach Order=0
Composite Channel Slope=5