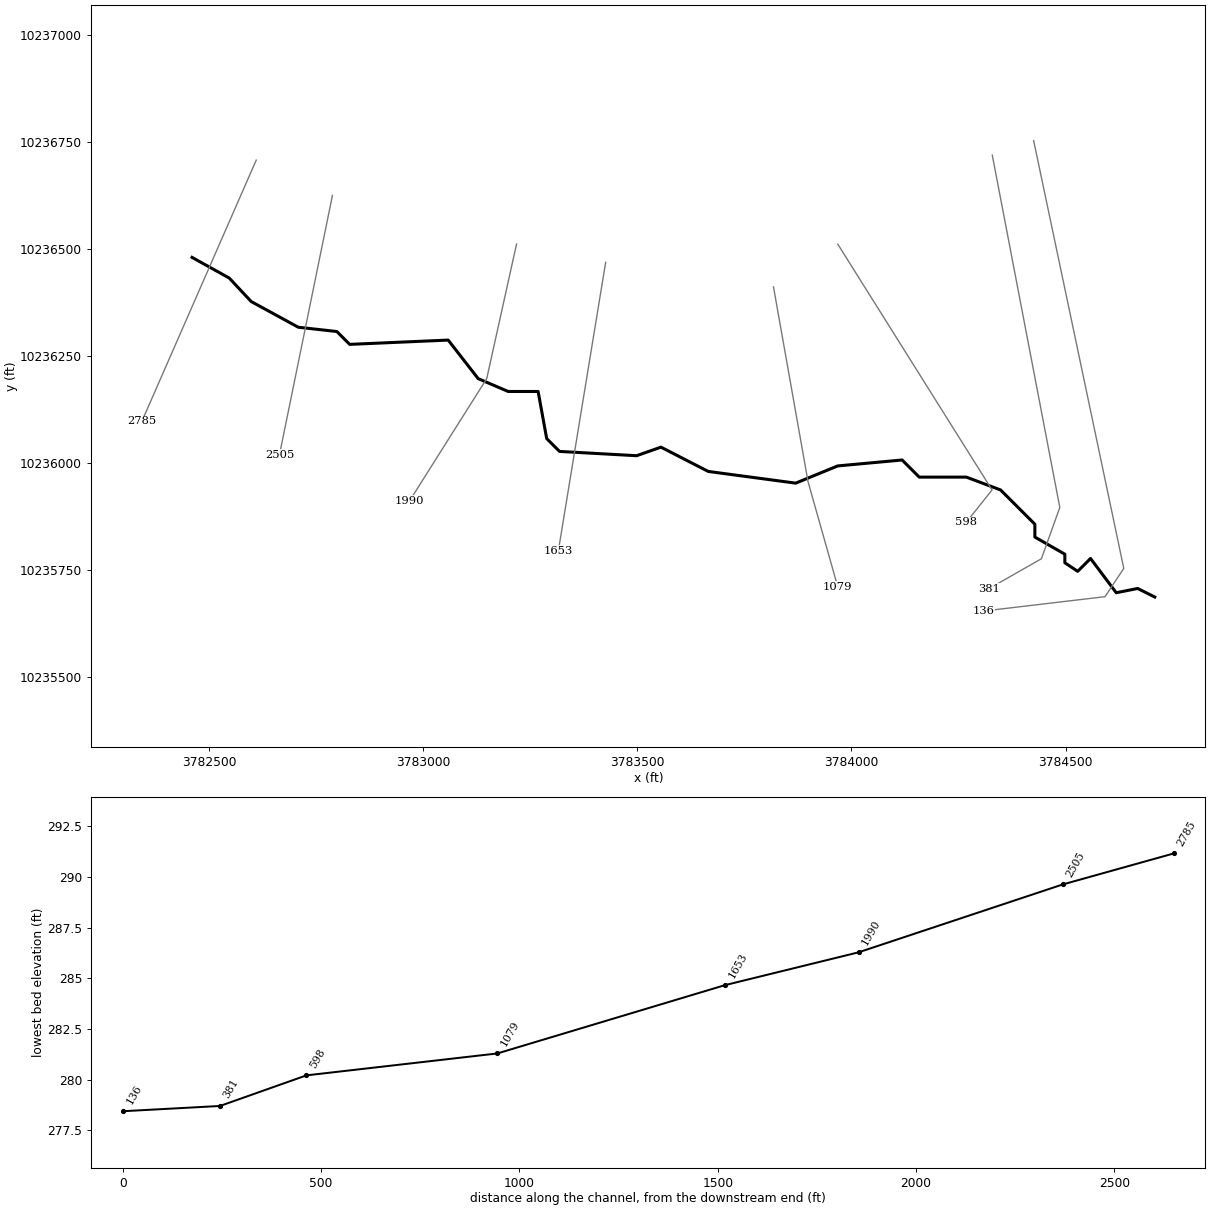
--- WFSJR 090.prj (project) ---

Proj Title=WFSJR 090 Base Level Engineering
Current Plan=p01
Default Exp/Contr=0.3,0.1
English Units
Geom File=g01
Flow File=f01
Plan File=p01
Y Axis Title=Elevation
X Axis Title(PF)=Main Channel Distance
X Axis Title(XS)=Station
BEGIN DESCRIPTION:
WFSJR 090
END DESCRIPTION:
DSS Export Rating Curves= 0
DSS Export Rating Curve Sorted= 0
DSS Export Volume Flow Curves= 0
DXF OffsetX= 0
DXF OffsetY= 0
DXF ScaleX= 1
DXF ScaleY= 10

--- WFSJR 090.p01 (plan) ---

Plan Title=Multiple Run
Program Version=4.10
Short Identifier=Multiple
Geom File=g01
Flow File=f01
Subcritical Flow
K Sum by GR= 0
Std Step Tol= 0.01
Critical Tol= 0.01
Num of Std Step Trials= 20
Max Error Tol= 0.3
Flow Tol Ratio= 0.001
Split Flow NTrial= 30
Split Flow Tol= 0.02
Split Flow Ratio= 0.02
Log Output Level= 0
Friction Slope Method= 1
Unsteady Friction Slope Method= 2
Unsteady Bridges Friction Slope Method= 1
Parabolic Critical Depth
Global Vel Dist= 1 , 1 , 1
Global Log Level= 0
CheckData=True
Encroach Param=-1 ,0,0, 0
BEGIN DESCRIPTION:
Multiple Run
END DESCRIPTION:
Computation Interval=1HOUR
Output Interval=1HOUR
Run HTab= 0
Run UNet= 0
Run PostProcess= 0
Run WQNet= 0
UNET Theta= 1
UNET Theta Warmup= 1
UNET ZTol= 0.02
UNET ZSATol= 0.05
UNET MxIter= 20
UNET MaxInSteps= 0
UNET DtIC= 0
UNET DtMin= 0
UNET MaxCRTS= 20
UNET WFStab= 2
UNET SFStab= 1
UNET WFX= 1
UNET SFX= 1
UNET DSS MLevel= 4
UNET DZMax Abort= 100
UNET Convert EG Bridges= 0
UNET Use Existing IB Tables=-1
UNET Froude Reduction=False
UNET Froude Limit= 1
UNET Froude Power= 10
UNET Time Slicing=0,0, 5
UNET Junction Losses=0
Instantaneous Interval=1HOUR
Write IC File= 0
Write IC File at Sim End=0
Echo Input=False
Echo Parameters=False
Echo Output=False
Write Detailed= 0
WQ AD Non Conservative
WQ ULTIMATE=-1
WQ Max Comp Step=1HOUR
WQ Output Interval=15MIN
WQ Output Selected Increments= 0
WQ Output face flow=0
WQ Output face velocity=0
WQ Output face area=0
WQ Output face dispersion=0
WQ Output cell volume=0
WQ Output cell surface area=0
WQ Output cell continuity=0
WQ Output cumulative cell continuity=0
WQ Output face conc=0
WQ Output face dconc_dx=0
WQ Output face courant=0
WQ Output face peclet=0
WQ Output face adv mass=0
WQ Output face disp mass=0
WQ Output cell mass=0
WQ Output cell source sink temp=0
WQ Output cell source sink nsm=0
WQ Output MaxMinRange=-1
WQ Daily Max Min Mean=-1
WQ Daily Range=0
WQ Daily Time=0
WQ Create Restart=0
WQ Fixed Restart=0
WQ System Summary=0
WQ Use Fixed Temperature=0
Sorting and Armoring Iterations= 10
XS Update Threshold= 0.02
Hydraulics Update Threshold= 0.02
Energy Slope Method= 1
Volume Change Method= 0
XS Weighting Method= 0
Number of US Weighted Cross Sections= 1
Number of DS Weighted Cross Sections= 1
Upstream XS Weight=0.25
Main XS Weight=0.5
Downstream XS Weight=0.25
Number of DS XS's Weighted with US Boundary= 1
Upstream Boundary Weight= 1
Weight of XSs Associated with US Boundary= 0
Number of US XS's Weighted with DS Boundary= 1
Downstream Boundary Weight= 0.5
Weight of XSs Associated with DS Boundary= 0.5
Sediment Output Level= 4
Mass or Volume Output= 0
Output Increment Type= 1
Profile and TS Output Increment= 10
XS Output Flag= 0
XS Output Increment= 10
Disregard all LS=0
Disregard all Conn=0
Disregard all Breaches=0
Disregard all Pumps=0

--- WFSJR 090.f01 (steady flow) ---

Flow Title=Multiple
Program Version=4.10
Number of Profiles= 7
Profile Names=10-year,25-year,50-year,1pct_min,100-year,1pct_plu,500-year
River Rch & RM=WFSJR 090,Reach-1         ,2785
     644     880    1198     538    1624    4904    3081
River Rch & RM=WFSJR 090,Reach-1         ,2505
     667     908    1231     550    1660    5013    3120
Boundary for River Rch & Prof#=WFSJR 090,Reach-1         , 1
Up Type= 0
Dn Type= 3
Dn Slope=0.005
Boundary for River Rch & Prof#=WFSJR 090,Reach-1         , 2
Up Type= 0
Dn Type= 3
Dn Slope=0.005
Boundary for River Rch & Prof#=WFSJR 090,Reach-1         , 3
Up Type= 0
Dn Type= 3
Dn Slope=0.005
Boundary for River Rch & Prof#=WFSJR 090,Reach-1         , 4
Up Type= 0
Dn Type= 3
Dn Slope=0.005
Boundary for River Rch & Prof#=WFSJR 090,Reach-1         , 5
Up Type= 0
Dn Type= 3
Dn Slope=0.005
Boundary for River Rch & Prof#=WFSJR 090,Reach-1         , 6
Up Type= 0
Dn Type= 3
Dn Slope=0.005
Boundary for River Rch & Prof#=WFSJR 090,Reach-1         , 7
Up Type= 0
Dn Type= 3
Dn Slope=0.005
DSS Import GetInterval= 0
DSS Import GetPeak= 0
DSS Import FillOption= 0

--- WFSJR 090.g01 (geometry) ---

Geom Title=Existing Conditions
Program Version=4.10

River Reach=WFSJR 090       ,Reach-1
Reach XY= 30
      3782460.12     10236479.94      3782546.91     10236431.73
      3782598.23     10236376.84      3782708.23     10236316.84
      3782798.23     10236306.84      3782828.23     10236276.84
      3783058.23     10236286.84      3783128.23     10236196.84
      3783198.23     10236166.84      3783268.23     10236166.84
      3783288.23     10236056.84      3783318.23     10236026.84
      3783498.23     10236016.84      3783555.06     10236036.84
      3783665.53      10235980.1      3783869.65     10235952.77
      3783967.69     10235992.96      3784118.23     10236006.84
      3784158.23     10235966.84      3784268.23     10235966.84
      3784348.23     10235936.84      3784428.23     10235856.84
      3784428.23     10235826.84      3784498.23     10235786.84
      3784498.23     10235766.84      3784528.23     10235746.84
      3784558.23     10235776.84      3784618.23     10235696.84
      3784668.23     10235706.84      3784708.23     10235686.84

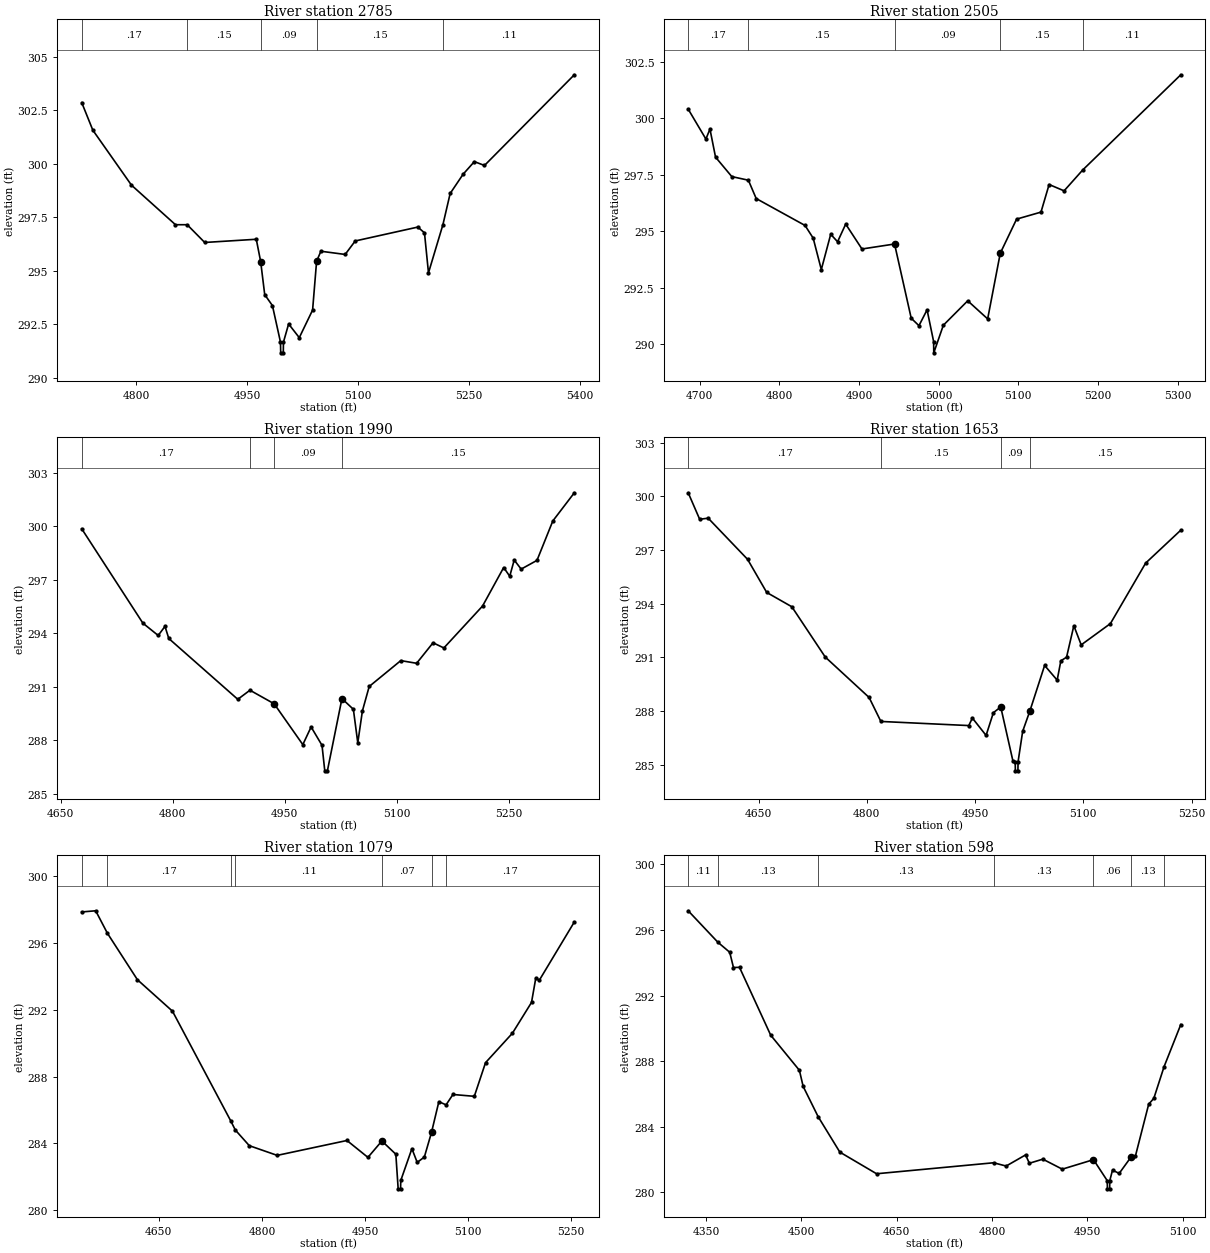
Type RM Length L Ch R = 1 ,2785    ,280,280,280
BEGIN DESCRIPTION:
WFSJR 090 5.0
END DESCRIPTION:
XS GIS Cut Line= 2
        3782610.     10236707.16      3782343.06     10236097.33
#Sta/Elev= 30
  4726.3  302.86  4741.3  301.57  4793.5     299    4853  297.15  4868.8  297.15
  4892.5  296.32  4962.2  296.47  4968.1  295.43  4973.6  293.88    4984  293.37
  4994.9  291.66  4995.2  291.16  4998.7  291.16  4998.9  291.66  5005.9  292.51
  5020.3  291.87  5038.3  293.16  5043.7  295.44  5049.5  295.91  5082.3  295.76
  5095.9  296.39  5180.5  297.04  5189.5  296.77  5194.9   294.9  5214.4  297.15
  5224.2  298.61  5241.7  299.51  5256.9   300.1  5270.6  299.92    5392  304.16
#Mann= 5 ,-1 , 0
  4726.3     .17       0  4868.8     .15       0  4968.1     .09       0
  5043.7     .15       0  5214.4     .11       0
Bank Sta=4968.1,5043.7
XS Rating Curve= 0 ,0
Exp/Cntr=0.3,0.1

Type RM Length L Ch R = 1 ,2505    ,515,515,515
BEGIN DESCRIPTION:
Mapping XS 2348e658
END DESCRIPTION:
XS GIS Cut Line= 2
      3782787.94     10236624.69      3782664.24     10236019.19
#Sta/Elev= 30
  4685.8   300.4    4708  299.08  4713.1  299.52  4720.1  298.28  4740.5  297.42
  4761.3  297.26  4771.1  296.45  4832.4  295.26  4842.6   294.7  4852.8  293.31
  4864.6  294.87  4873.2  294.54  4883.4  295.32  4903.8  294.22  4944.7  294.44
  4965.6  291.16  4975.3  290.83  4985.5  291.53  4993.7  290.13  4993.9  289.63
  5005.9  290.85  5036.5  291.93  5061.5  291.13  5077.3  294.03  5097.8  295.54
  5128.4  295.85  5138.6  297.07  5157.4  296.79  5180.7  297.71  5303.8  301.92
#Mann= 5 ,-1 , 0
  4685.8     .17       0  4761.3     .15       0  4944.7     .09       0
  5077.3     .15       0  5180.7     .11       0
Bank Sta=4944.7,5077.3
XS Rating Curve= 0 ,0
Exp/Cntr=0.3,0.1

Type RM Length L Ch R = 1 ,1990    ,337,337,337
BEGIN DESCRIPTION:
WFSJR 090 4.0
END DESCRIPTION:
XS GIS Cut Line= 3
      3783217.84     10236511.03      3783148.23     10236196.84
      3782967.87      10235911.1
#Sta/Elev= 30
  4678.2  299.85  4760.1  294.56  4780.6  293.87  4789.7  294.38  4794.8   293.7
  4887.2  290.29  4903.5   290.8  4935.9  290.04  4974.3  287.75  4985.4  288.74
    5000  287.71  5003.7  286.28  5007.2  286.28  5026.7  290.33    5042  289.73
  5047.9  287.85  5054.1  289.64  5063.2  291.01  5105.5  292.46  5126.7  292.31
  5148.7  293.46  5163.2  293.17    5215  295.52  5243.3  297.68  5251.4  297.19
  5257.4   298.1  5266.7  297.59  5287.9  298.08  5309.1  300.29  5337.9  301.87
#Mann= 4 ,-1 , 0
  4678.2     .17       0  4903.5     .15       0  4935.9     .09       0
  5026.7     .15       0
Bank Sta=4935.9,5026.7
XS Rating Curve= 0 ,0
Exp/Cntr=0.3,0.1

Type RM Length L Ch R = 1 ,1653    ,574,574,574
BEGIN DESCRIPTION:
WFSJR 090 3.0
END DESCRIPTION:
XS GIS Cut Line= 2
      3783425.97     10236468.45       3783315.5     10235794.84
#Sta/Elev= 30
  4552.5   300.2  4568.4  298.72  4580.2  298.78  4634.8  296.48  4661.3  294.63
  4696.1  293.83  4742.4  291.02  4803.2  288.76  4819.5  287.42  4941.3  287.19
  4946.3  287.61  4965.3  286.64  4975.4  287.91  4985.6  288.23  5002.6  285.19
  5005.6  285.16  5005.9  284.66  5009.4  284.66  5009.6  285.16    5016  286.87
  5026.1  288.02  5046.4  290.55  5063.8  289.73  5068.9  290.81  5076.8  291.01
  5086.9  292.77  5097.1   291.7  5137.6  292.89  5186.4  296.27  5235.1  298.11
#Mann= 4 ,-1 , 0
  4552.5     .17       0  4819.5     .15       0  4985.6     .09       0
  5026.1     .15       0
Bank Sta=4985.6,5026.1
XS Rating Curve= 0 ,0
Exp/Cntr=0.3,0.1

Type RM Length L Ch R = 1 ,1079    ,481,481,481
BEGIN DESCRIPTION:
WFSJR 090 2.0
END DESCRIPTION:
XS GIS Cut Line= 3
      3783817.85     10236411.08      3783898.58     10235955.99
      3783967.84      10235711.1
#Sta/Elev= 30
  4537.8  297.84  4558.1  297.91  4575.1  296.57  4618.8  293.79  4669.8  291.91
  4754.5  285.36  4761.2  284.81  4781.6  283.87  4822.2  283.29  4923.7  284.18
  4954.2  283.17  4974.5  284.15  4994.8  283.36  4998.2  281.29  5001.7  281.29
    5002  281.79  5018.2  283.69  5025.9  282.87  5036.3  283.19  5046.7  284.66
  5057.4   286.5  5067.9  286.31  5077.9  286.93    5109  286.82  5125.3  288.83
  5164.4  290.59  5192.2  292.43  5198.4  293.88  5203.6  293.76  5254.5  297.24
#Mann= 7 ,-1 , 0
  4537.8     .11       0  4575.1     .17       0  4754.5     .11       0
  4761.2     .11       0  4974.5     .07       0  5046.7     .15       0
  5067.9     .17       0
Bank Sta=4974.5,5046.7
XS Rating Curve= 0 ,0
Exp/Cntr=0.3,0.1

Type RM Length L Ch R = 1 ,598     ,218,218,218
BEGIN DESCRIPTION:
WFSJR 090 1.0
END DESCRIPTION:
XS GIS Cut Line= 3
      3783967.88     10236511.03      3784328.23     10235936.84
      3784267.84     10235861.06
#Sta/Elev= 30
  4322.1  297.17  4368.8  295.25  4387.4  294.64  4393.3  293.71  4402.8  293.72
  4451.9  289.58    4497  287.44  4502.9  286.46  4526.5  284.61  4560.6  282.45
  4618.4  281.13  4802.5   281.8  4822.2   281.6  4852.8  282.28  4858.7  281.77
  4879.9  282.02  4910.5  281.41  4959.6  281.99  4981.2  280.71  4981.5  280.21
    4985  280.21  4985.2  280.71  4989.5  281.35    5000  281.15  5019.2  282.18
  5025.6  282.22  5046.4  285.37  5054.5  285.73  5070.7  287.67  5096.9  290.23
#Mann= 7 ,-1 , 0
  4322.1     .11       0  4368.8     .13       0  4526.5     .13       0
  4802.5     .13       0  4959.6     .06       0  5019.2     .13       0
  5070.7     .17       0
Bank Sta=4959.6,5019.2
XS Rating Curve= 0 ,0
Exp/Cntr=0.3,0.1

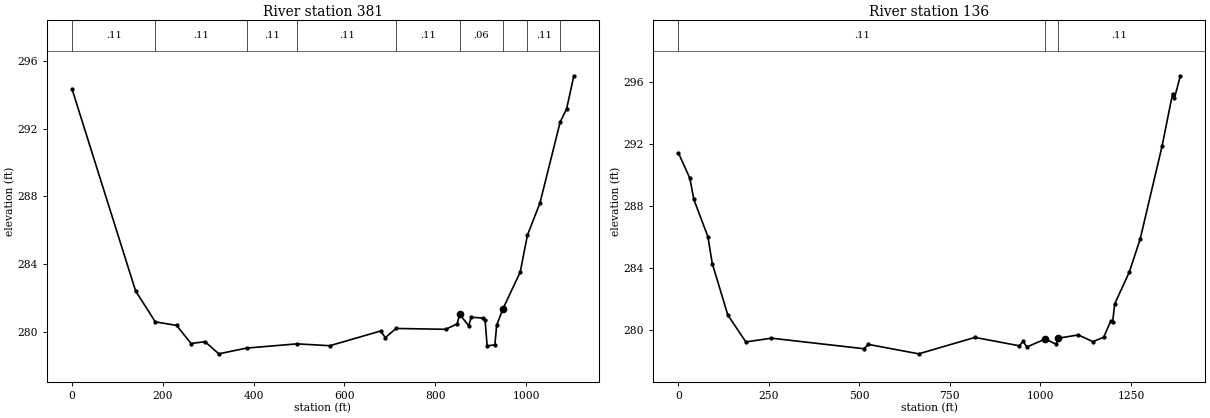
Type RM Length L Ch R = 1 ,381     ,245,245,245
XS GIS Cut Line= 4
      3784328.78      10236718.7      3784486.48     10235895.94
      3784443.44     10235776.17      3784320.24     10235705.97
#Sta/Elev= 30
       0  294.36   140.1  282.42   183.5  280.59   230.4  280.38   262.3  279.31
   292.9  279.42   323.4   278.7   384.5  279.04   495.6  279.29   567.8  279.18
   679.8  280.05     690  279.66   713.8   280.2   822.9  280.15   848.3  280.47
   853.7  281.03   873.8  280.36   879.1  280.86   904.5  280.82   909.8  280.67
  914.24  279.17   931.3  279.23   935.2  280.39   949.2  281.37   987.1  283.53
  1002.9  285.71  1030.3  287.59    1075  292.39  1089.3  293.18  1105.2  295.13
#Mann= 9 ,-1 , 0
       0     .11       0   183.5     .11       0   384.5     .11       0
   495.6     .11       0   713.8     .11       0   853.7     .06       0
   949.2     .11       0  1002.9     .11       0    1075     .11       0
Bank Sta=853.7,949.2
XS Rating Curve= 0 ,0
Exp/Cntr=0.3,0.1

Type RM Length L Ch R = 1 ,136     ,0,0,0
XS GIS Cut Line= 4
      3784425.38     10236752.61      3784635.88     10235753.62
      3784592.04     10235687.65      3784307.78     10235654.01
#Sta/Elev= 30
       0  291.41    31.7  289.77    42.4  288.42    81.5     286    93.5  284.27
   136.4  280.95   186.2  279.21   257.1  279.45   512.5  278.77   524.6  279.05
   663.7  278.44   819.1   279.5   941.8  278.96     952  279.25   962.5  278.88
  1013.3   279.4  1043.2  279.06  1049.2  279.45  1104.8  279.66  1144.6  279.23
  1174.8  279.51  1194.3  280.57  1199.3  280.47  1205.1  281.66  1245.3  283.71
  1275.5  285.85    1336  291.85    1365  295.24    1370  294.93  1386.4  296.39
#Mann= 3 , 0 , 0
       0     .11       0  1013.3     .06       0  1049.2     .11       0
Bank Sta=1013.3,1049.2
XS Rating Curve= 0 ,0
Exp/Cntr=0.3,0.1

Chan Stop Cuts=-1
Use User Specified Reach Order=0
Composite Channel Slope=5