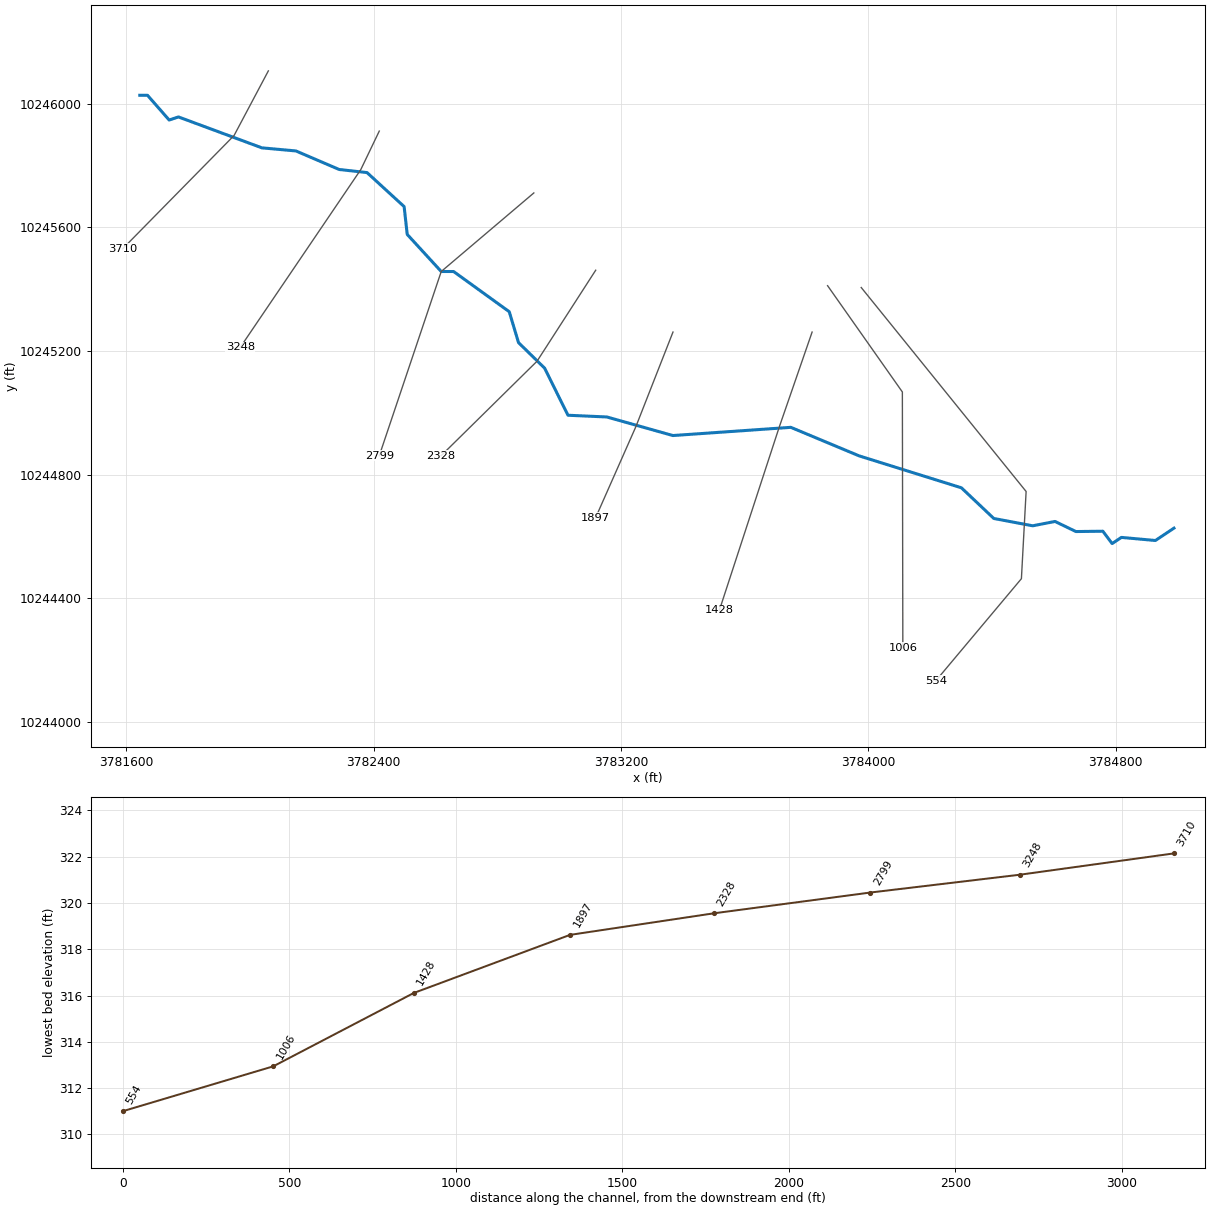
--- WFSJR 092.prj (project) ---

Proj Title=WFSJR 092 Base Level Engineering
Current Plan=p01
Default Exp/Contr=0.3,0.1
English Units
Geom File=g01
Flow File=f01
Plan File=p01
Y Axis Title=Elevation
X Axis Title(PF)=Main Channel Distance
X Axis Title(XS)=Station
BEGIN DESCRIPTION:
WFSJR 092
END DESCRIPTION:
DSS Export Rating Curves= 0
DSS Export Rating Curve Sorted= 0
DSS Export Volume Flow Curves= 0
DXF OffsetX= 0
DXF OffsetY= 0
DXF ScaleX= 1
DXF ScaleY= 10

--- WFSJR 092.p01 (plan) ---

Plan Title=Multiple Run
Program Version=4.10
Short Identifier=Multiple
Geom File=g01
Flow File=f01
Subcritical Flow
K Sum by GR= 0
Std Step Tol= 0.01
Critical Tol= 0.01
Num of Std Step Trials= 20
Max Error Tol= 0.3
Flow Tol Ratio= 0.001
Split Flow NTrial= 30
Split Flow Tol= 0.02
Split Flow Ratio= 0.02
Log Output Level= 0
Friction Slope Method= 1
Unsteady Friction Slope Method= 2
Unsteady Bridges Friction Slope Method= 1
Parabolic Critical Depth
Global Vel Dist= 1 , 1 , 1
Global Log Level= 0
CheckData=True
Encroach Param=-1 ,0,0, 0
BEGIN DESCRIPTION:
Multiple Run
END DESCRIPTION:
Computation Interval=1HOUR
Output Interval=1HOUR
Run HTab= 0
Run UNet= 0
Run PostProcess= 0
Run WQNet= 0
UNET Theta= 1
UNET Theta Warmup= 1
UNET ZTol= 0.02
UNET ZSATol= 0.05
UNET MxIter= 20
UNET MaxInSteps= 0
UNET DtIC= 0
UNET DtMin= 0
UNET MaxCRTS= 20
UNET WFStab= 2
UNET SFStab= 1
UNET WFX= 1
UNET SFX= 1
UNET DSS MLevel= 4
UNET DZMax Abort= 100
UNET Convert EG Bridges= 0
UNET Use Existing IB Tables=-1
UNET Froude Reduction=False
UNET Froude Limit= 1
UNET Froude Power= 10
UNET Time Slicing=0,0, 5
UNET Junction Losses=0
Instantaneous Interval=1HOUR
Write IC File= 0
Write IC File at Sim End=0
Echo Input=False
Echo Parameters=False
Echo Output=False
Write Detailed= 0
WQ AD Non Conservative
WQ ULTIMATE=-1
WQ Max Comp Step=1HOUR
WQ Output Interval=15MIN
WQ Output Selected Increments= 0
WQ Output face flow=0
WQ Output face velocity=0
WQ Output face area=0
WQ Output face dispersion=0
WQ Output cell volume=0
WQ Output cell surface area=0
WQ Output cell continuity=0
WQ Output cumulative cell continuity=0
WQ Output face conc=0
WQ Output face dconc_dx=0
WQ Output face courant=0
WQ Output face peclet=0
WQ Output face adv mass=0
WQ Output face disp mass=0
WQ Output cell mass=0
WQ Output cell source sink temp=0
WQ Output cell source sink nsm=0
WQ Output MaxMinRange=-1
WQ Daily Max Min Mean=-1
WQ Daily Range=0
WQ Daily Time=0
WQ Create Restart=0
WQ Fixed Restart=0
WQ System Summary=0
WQ Use Fixed Temperature=0
Sorting and Armoring Iterations= 10
XS Update Threshold= 0.02
Hydraulics Update Threshold= 0.02
Energy Slope Method= 1
Volume Change Method= 0
XS Weighting Method= 0
Number of US Weighted Cross Sections= 1
Number of DS Weighted Cross Sections= 1
Upstream XS Weight=0.25
Main XS Weight=0.5
Downstream XS Weight=0.25
Number of DS XS's Weighted with US Boundary= 1
Upstream Boundary Weight= 1
Weight of XSs Associated with US Boundary= 0
Number of US XS's Weighted with DS Boundary= 1
Downstream Boundary Weight= 0.5
Weight of XSs Associated with DS Boundary= 0.5
Sediment Output Level= 4
Mass or Volume Output= 0
Output Increment Type= 1
Profile and TS Output Increment= 10
XS Output Flag= 0
XS Output Increment= 10
Disregard all LS=0
Disregard all Conn=0
Disregard all Breaches=0
Disregard all Pumps=0

--- WFSJR 092.f01 (steady flow) ---

Flow Title=Multiple
Program Version=4.10
Number of Profiles= 7
Profile Names=10-year,25-year,50-year,1pct_min,100-year,1pct_plu,500-year
River Rch & RM=WFSJR 092,Reach-1         ,3710
     869    1202    1647     743    2245    6780    4305
Boundary for River Rch & Prof#=WFSJR 092,Reach-1         , 1
Up Type= 0
Dn Type= 3
Dn Slope=0.009
Boundary for River Rch & Prof#=WFSJR 092,Reach-1         , 2
Up Type= 0
Dn Type= 3
Dn Slope=0.009
Boundary for River Rch & Prof#=WFSJR 092,Reach-1         , 3
Up Type= 0
Dn Type= 3
Dn Slope=0.009
Boundary for River Rch & Prof#=WFSJR 092,Reach-1         , 4
Up Type= 0
Dn Type= 3
Dn Slope=0.009
Boundary for River Rch & Prof#=WFSJR 092,Reach-1         , 5
Up Type= 0
Dn Type= 3
Dn Slope=0.009
Boundary for River Rch & Prof#=WFSJR 092,Reach-1         , 6
Up Type= 0
Dn Type= 3
Dn Slope=0.009
Boundary for River Rch & Prof#=WFSJR 092,Reach-1         , 7
Up Type= 0
Dn Type= 3
Dn Slope=0.009
DSS Import GetInterval= 0
DSS Import GetPeak= 0
DSS Import FillOption= 0

--- WFSJR 092.g01 (geometry) ---

Geom Title=Existing Conditions
Program Version=4.10

River Reach=WFSJR 092       ,Reach-1
Reach XY= 30
      3781643.23     10246026.84      3781668.23     10246026.84
      3781738.23     10245946.84      3781768.23     10245956.84
      3782038.23     10245856.84      3782148.23     10245846.84
      3782288.23     10245786.84      3782378.23     10245776.84
      3782498.23     10245666.84      3782508.23     10245576.84
      3782618.23     10245456.84      3782658.23     10245456.84
      3782838.23     10245326.84      3782868.23     10245226.84
      3782952.71     10245144.23      3783028.14     10244991.97
      3783153.87     10244986.38      3783367.59     10244926.31
      3783748.95     10244952.85      3783969.66     10244860.66
      3784300.73     10244757.28       3784405.5      10244658.1
      3784531.22     10244634.36      3784603.53     10244648.44
      3784671.06     10244615.78      3784758.23     10244616.84
      3784788.23     10244576.84      3784818.23     10244596.84
      3784928.23     10244586.84      3784988.23     10244626.84

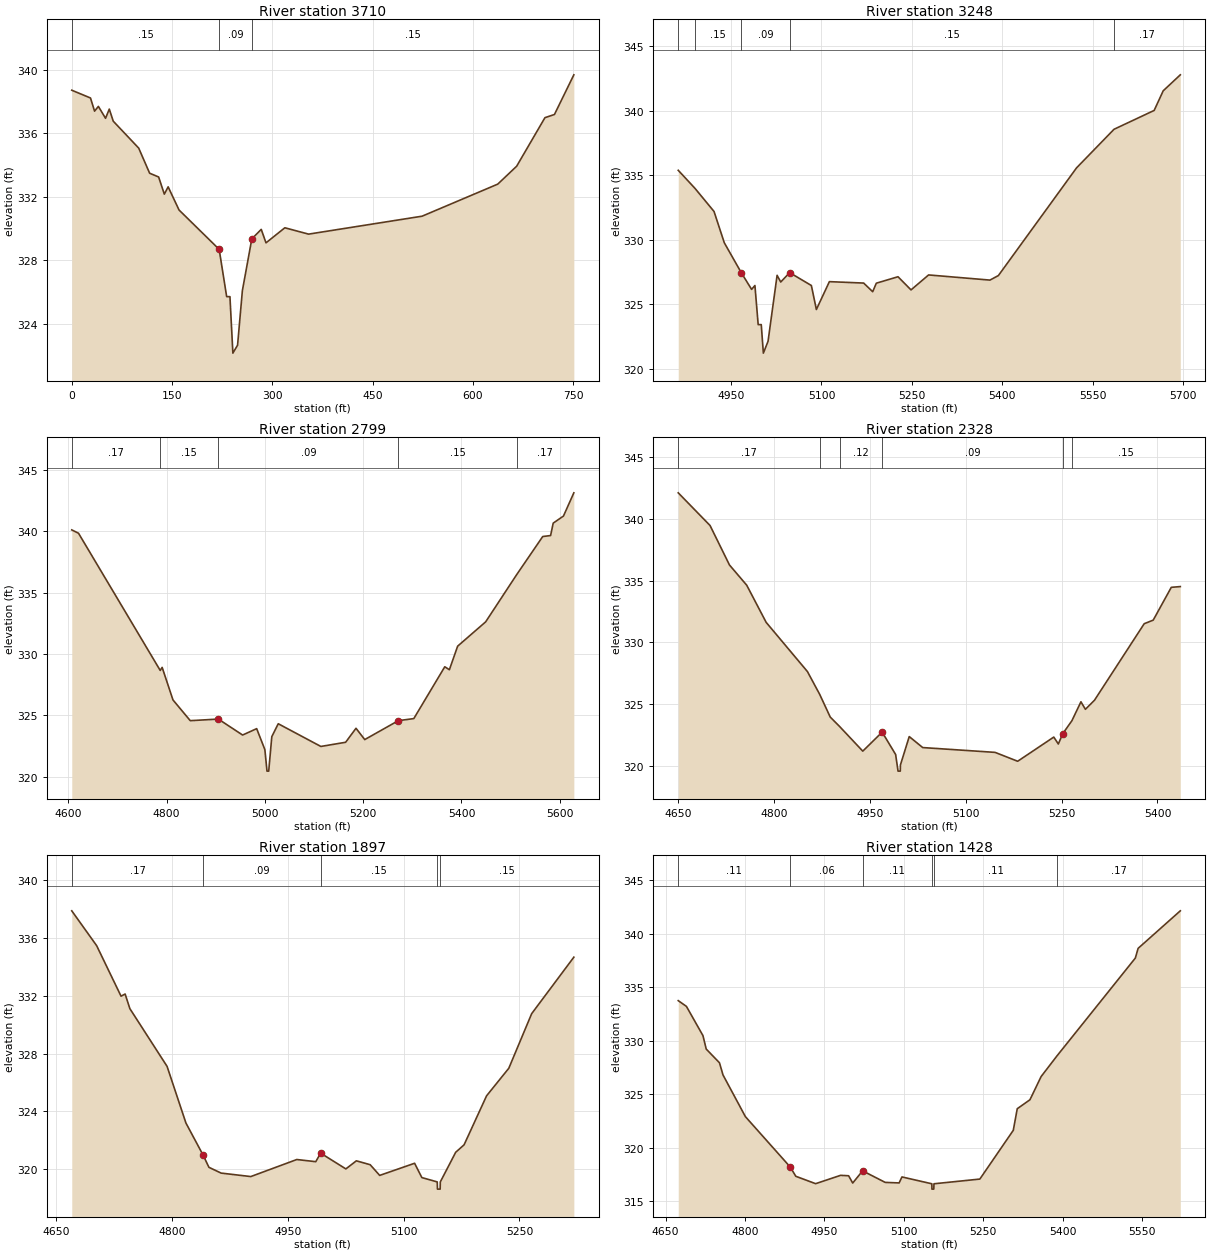
Type RM Length L Ch R = 1 ,3710    ,462,462,462
XS GIS Cut Line= 3
      3782059.07      10246105.8      3781948.23     10245896.84
      3781587.71     10245530.28
#Sta/Elev= 30
       0  338.71      28  338.22    34.1  337.39    39.8  337.69    50.5  336.94
    56.1  337.52      62  336.76   100.1  335.06   116.4  333.48   129.9  333.24
   138.4  332.16   144.1  332.62   160.4  331.16   220.4  328.68   231.6   325.7
   236.5   325.7   240.9  322.14   247.9  322.64   255.1  326.08   269.2  329.34
   283.3  329.94   290.4  329.09   318.6  330.04   354.1  329.64   523.8  330.77
   636.9  332.79   665.2  333.92   707.5  336.98   721.7  337.18   750.7  339.68
#Mann= 3 , 0 , 0
       0     .15       0   220.4     .09       0   269.2     .15       0
Bank Sta=220.4,269.2
XS Rating Curve= 0 ,0
Exp/Cntr=0.3,0.1

Type RM Length L Ch R = 1 ,3248    ,449,449,449
BEGIN DESCRIPTION:
WFSJR 092 6.0
END DESCRIPTION:
XS GIS Cut Line= 3
      3782417.85     10245911.08      3782358.23     10245786.84
      3781967.87      10245211.1
#Sta/Elev= 30
  4862.2  335.39    4890  333.99  4921.6   332.2  4938.7  329.77  4966.9  327.45
    4984  326.16  4989.5  326.46  4994.9  323.43    5000  323.43  5003.5  321.22
  5011.3  322.14  5026.3  327.25  5032.3  326.73  5047.2  327.46  5083.2  326.46
  5091.5   324.6  5113.1  326.76    5170  326.65    5185  325.98    5191  326.64
    5227  327.14  5248.6  326.12  5277.8  327.28  5379.6  326.88  5393.6  327.23
  5523.4  335.58  5585.6  338.57  5652.2  340.03  5667.2  341.55  5695.6  342.79
#Mann= 5 ,-1 , 0
  4862.2     .17       0    4890     .15       0  4966.9     .09       0
  5047.2     .15       0  5585.6     .17       0
Bank Sta=4966.9,5047.2
XS Rating Curve= 0 ,0
Exp/Cntr=0.3,0.1

Type RM Length L Ch R = 1 ,2799    ,471,471,471
BEGIN DESCRIPTION:
WFSJR 092 5.0
END DESCRIPTION:
XS GIS Cut Line= 3
      3782917.82     10245711.04      3782618.23     10245456.84
      3782417.84     10244861.04
#Sta/Elev= 30
  4607.1   340.1  4620.8  339.83  4787.1  328.65    4791   328.9    4813  326.25
  4848.2  324.56  4905.3  324.69  4954.7  323.39  4983.3  323.91    5000   322.2
  5004.3  320.45  5007.8  320.45  5014.1  323.26  5027.2  324.31  5113.9  322.46
  5164.3   322.8  5185.4  323.94  5203.2  323.02  5271.5  324.56    5303  324.73
    5366  328.95  5375.4  328.71  5392.2  330.63  5449.2  332.61  5512.2  336.45
  5565.3  339.56  5581.3  339.64  5586.6  340.65  5607.5  341.23  5628.6  343.12
#Mann= 5 ,-1 , 0
  4607.1     .17       0  4787.1     .15       0  4905.3     .09       0
  5271.5     .15       0  5512.2     .17       0
Bank Sta=4905.3,5271.5
XS Rating Curve= 0 ,0
Exp/Cntr=0.3,0.1

Type RM Length L Ch R = 1 ,2328    ,431,431,431
BEGIN DESCRIPTION:
WFSJR 092 4.0
END DESCRIPTION:
XS GIS Cut Line= 3
      3783117.83     10245461.04      3782928.23     10245166.84
      3782617.85     10244861.07
#Sta/Elev= 30
    4650  342.11  4699.8  339.46  4730.2  336.26  4757.2  334.62  4787.6  331.61
  4852.2  327.62  4871.4  325.77  4887.9  323.93  4902.5  323.17  4938.8  321.17
  4969.1  322.71  4990.2   320.9    4994  319.55  4997.5  319.55  4997.7  320.05
  5011.5  322.35  5032.6  321.46  5145.8  321.07  5181.2  320.35  5237.7  322.31
  5244.8  321.75  5251.9   322.6    5266  323.63  5280.2  325.17  5287.2  324.56
  5301.3  325.29  5379.2   331.5  5393.3  331.79  5421.6  334.45  5435.7  334.51
#Mann= 6 ,-1 , 0
    4650     .17       0  4871.4     .15       0  4902.5     .12       0
  4969.1     .09       0  5251.9     .12       0    5266     .15       0
Bank Sta=4969.1,5251.9
XS Rating Curve= 0 ,0
Exp/Cntr=0.3,0.1

Type RM Length L Ch R = 1 ,1897    ,469,469,469
BEGIN DESCRIPTION:
WFSJR 092 3.0
END DESCRIPTION:
XS GIS Cut Line= 3
      3783367.85     10245261.07      3783247.46     10244954.25
      3783117.87     10244661.12
#Sta/Elev= 30
  4670.4  337.89  4702.6  335.48  4734.2  331.98  4739.5  332.13  4745.6  331.12
  4793.8  327.12  4818.2   323.2  4840.7  320.95    4848  320.13  4863.8  319.73
  4902.2  319.49  4961.8  320.67  4986.3  320.52  4992.7  321.11  5025.3  320.02
  5038.9  320.58  5056.8  320.31  5069.1  319.57  5114.3  320.41  5123.7  319.42
  5143.6  319.12  5143.9  318.62  5147.4  318.62  5147.6  319.12  5167.5  321.17
  5178.4  321.69  5207.5  325.08  5236.3  326.99  5265.9  330.77  5320.5  334.68
#Mann= 5 ,-1 , 0
  4670.4     .17       0  4840.7     .09       0  4992.7     .15       0
  5143.6     .12       0  5147.6     .15       0
Bank Sta=4840.7,4992.7
XS Rating Curve= 0 ,0
Exp/Cntr=0.3,0.1

Type RM Length L Ch R = 1 ,1428    ,422,422,422
BEGIN DESCRIPTION:
WFSJR 092 2.0
END DESCRIPTION:
XS GIS Cut Line= 3
      3783817.84     10245261.04      3783711.23     10244952.85
      3783517.84     10244361.05
#Sta/Elev= 30
  4673.9  333.74  4689.4   333.2  4720.6  330.47  4726.8  329.21  4751.8  327.93
  4758.5  326.79  4800.8  322.89  4885.5  318.18  4896.1  317.31  4933.5  316.62
  4980.7   317.4  4995.8  317.36  5003.6  316.68  5022.3  317.82    5065  316.74
  5091.3  316.69  5096.6  317.25  5153.1  316.61  5153.3  316.11  5156.8  316.11
  5157.1  316.61  5243.8  317.05    5307  321.61  5314.5  323.63  5338.5  324.47
  5359.6  326.64  5389.7  328.58  5537.6  337.72  5542.9  338.63  5622.6  342.14
#Mann= 6 ,-1 , 0
  4673.9     .11       0  4885.5     .06       0  5022.3     .11       0
  5153.1     .11       0  5157.1     .11       0  5389.7     .17       0
Bank Sta=4885.5,5022.3
XS Rating Curve= 0 ,0
Exp/Cntr=0.3,0.1

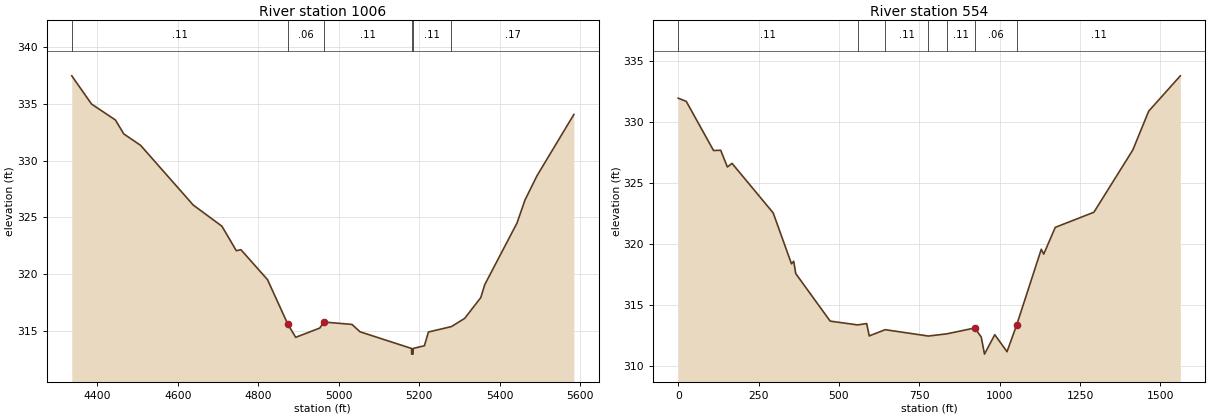
Type RM Length L Ch R = 1 ,1006    ,452,452,452
BEGIN DESCRIPTION:
WFSJR 092 1.0
END DESCRIPTION:
XS GIS Cut Line= 3
      3783867.88     10245411.04      3784109.77     10245067.22
       3784111.3     10244239.71
#Sta/Elev= 30
  4336.7  337.48  4385.9  334.99  4445.1  333.59    4466  332.36  4507.8  331.35
  4638.5  326.09  4709.9  324.22  4745.7  322.06  4757.1  322.15  4823.2  319.51
  4873.2  315.62  4893.2  314.42  4953.2  315.24  4963.2  315.77  5033.2  315.56
  5053.2  314.91  5181.2  313.44  5181.5  312.94    5185  312.94  5185.2  313.44
  5213.2  313.68  5223.2  314.89  5280.4  315.37  5313.2  316.09  5353.2  317.92
  5363.2  319.07  5443.2  324.49  5463.2  326.53  5493.2  328.68  5584.6  334.07
#Mann= 6 ,-1 , 0
  4336.7     .11       0  4873.2     .06       0  4963.2     .11       0
  5181.2     .11       0  5185.2     .11       0  5280.4     .17       0
Bank Sta=4873.2,4963.2
XS Rating Curve= 0 ,0
Exp/Cntr=0.3,0.1

Type RM Length L Ch R = 1 ,554     ,0,0,0
XS GIS Cut Line= 4
      3783976.75     10245405.07      3784510.04     10244745.35
       3784494.8     10244463.28      3784217.82     10244132.94
#Sta/Elev= 30
       0  331.94      25  331.68   109.8  327.66   132.1  327.68   152.9  326.31
   167.3  326.61   295.3  322.56   352.3  318.39   359.2   318.6   365.6  317.59
   472.7   313.7   558.1  313.39   586.3   313.5   594.2  312.49   643.8     313
   778.2  312.48   835.7  312.66   922.7  313.14   942.7  312.39   952.7     311
   984.7  312.59  1022.8   311.2  1052.9  313.39  1129.4  319.58    1137  319.18
  1172.8  321.37  1293.1  322.61  1414.1   327.7  1463.6  330.88  1561.9  333.77
#Mann= 7 ,-1 , 0
       0     .11       0   558.1     .11       0   643.8     .11       0
   778.2     .11       0   835.7     .11       0   922.7     .06       0
  1052.9     .11       0
Bank Sta=922.7,1052.9
XS Rating Curve= 0 ,0
Exp/Cntr=0.3,0.1

Chan Stop Cuts=-1
Use User Specified Reach Order=0
Composite Channel Slope=5