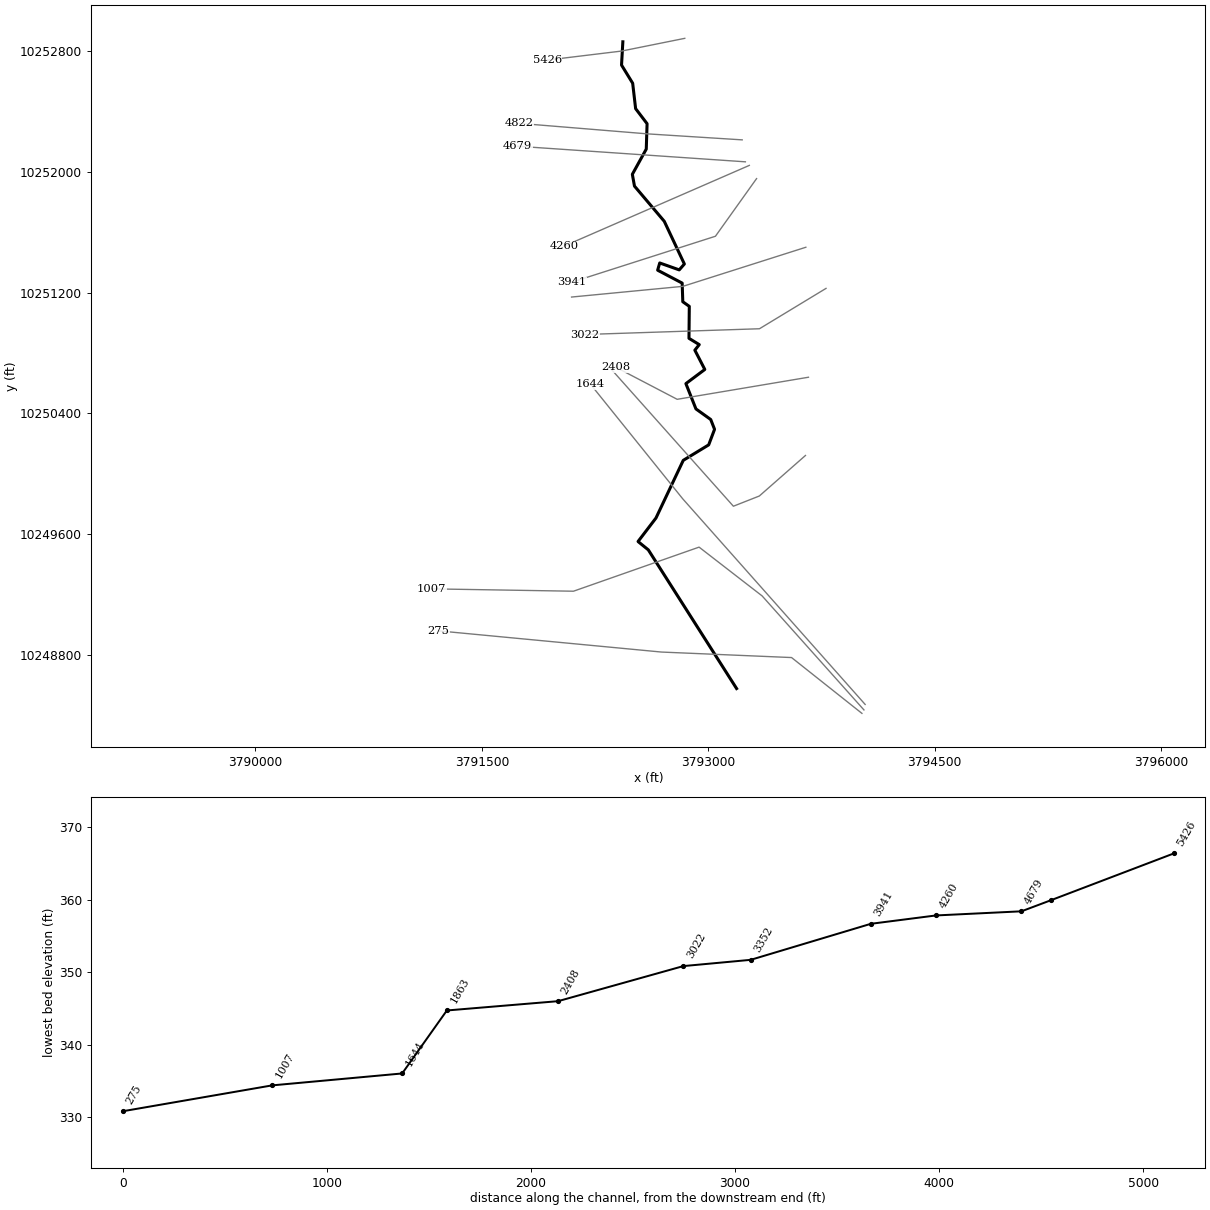
--- WFSJR 094.prj (project) ---

Proj Title=WFSJR 094 Base Level Engineering
Current Plan=p01
Default Exp/Contr=0.3,0.1
English Units
Geom File=g01
Flow File=f01
Plan File=p01
Y Axis Title=Elevation
X Axis Title(PF)=Main Channel Distance
X Axis Title(XS)=Station
BEGIN DESCRIPTION:
WFSJR 094
END DESCRIPTION:
DSS Export Rating Curves= 0
DSS Export Rating Curve Sorted= 0
DSS Export Volume Flow Curves= 0
DXF OffsetX= 0
DXF OffsetY= 0
DXF ScaleX= 1
DXF ScaleY= 10

--- WFSJR 094.p01 (plan) ---

Plan Title=Multiple Run
Program Version=4.10
Short Identifier=Multiple
Geom File=g01
Flow File=f01
Subcritical Flow
K Sum by GR= 0
Std Step Tol= 0.01
Critical Tol= 0.01
Num of Std Step Trials= 20
Max Error Tol= 0.3
Flow Tol Ratio= 0.001
Split Flow NTrial= 30
Split Flow Tol= 0.02
Split Flow Ratio= 0.02
Log Output Level= 0
Friction Slope Method= 1
Unsteady Friction Slope Method= 2
Unsteady Bridges Friction Slope Method= 1
Parabolic Critical Depth
Global Vel Dist= 1 , 1 , 1
Global Log Level= 0
CheckData=True
Encroach Param=-1 ,0,0, 0
BEGIN DESCRIPTION:
Multiple Run
END DESCRIPTION:
Computation Interval=1HOUR
Output Interval=1HOUR
Run HTab= 0
Run UNet= 0
Run PostProcess= 0
Run WQNet= 0
UNET Theta= 1
UNET Theta Warmup= 1
UNET ZTol= 0.02
UNET ZSATol= 0.05
UNET MxIter= 20
UNET MaxInSteps= 0
UNET DtIC= 0
UNET DtMin= 0
UNET MaxCRTS= 20
UNET WFStab= 2
UNET SFStab= 1
UNET WFX= 1
UNET SFX= 1
UNET DSS MLevel= 4
UNET DZMax Abort= 100
UNET Convert EG Bridges= 0
UNET Use Existing IB Tables=-1
UNET Froude Reduction=False
UNET Froude Limit= 1
UNET Froude Power= 10
UNET Time Slicing=0,0, 5
UNET Junction Losses=0
Instantaneous Interval=1HOUR
Write IC File= 0
Write IC File at Sim End=0
Echo Input=False
Echo Parameters=False
Echo Output=False
Write Detailed= 0
WQ AD Non Conservative
WQ ULTIMATE=-1
WQ Max Comp Step=1HOUR
WQ Output Interval=15MIN
WQ Output Selected Increments= 0
WQ Output face flow=0
WQ Output face velocity=0
WQ Output face area=0
WQ Output face dispersion=0
WQ Output cell volume=0
WQ Output cell surface area=0
WQ Output cell continuity=0
WQ Output cumulative cell continuity=0
WQ Output face conc=0
WQ Output face dconc_dx=0
WQ Output face courant=0
WQ Output face peclet=0
WQ Output face adv mass=0
WQ Output face disp mass=0
WQ Output cell mass=0
WQ Output cell source sink temp=0
WQ Output cell source sink nsm=0
WQ Output MaxMinRange=-1
WQ Daily Max Min Mean=-1
WQ Daily Range=0
WQ Daily Time=0
WQ Create Restart=0
WQ Fixed Restart=0
WQ System Summary=0
WQ Use Fixed Temperature=0
Sorting and Armoring Iterations= 10
XS Update Threshold= 0.02
Hydraulics Update Threshold= 0.02
Energy Slope Method= 1
Volume Change Method= 0
XS Weighting Method= 0
Number of US Weighted Cross Sections= 1
Number of DS Weighted Cross Sections= 1
Upstream XS Weight=0.25
Main XS Weight=0.5
Downstream XS Weight=0.25
Number of DS XS's Weighted with US Boundary= 1
Upstream Boundary Weight= 1
Weight of XSs Associated with US Boundary= 0
Number of US XS's Weighted with DS Boundary= 1
Downstream Boundary Weight= 0.5
Weight of XSs Associated with DS Boundary= 0.5
Sediment Output Level= 4
Mass or Volume Output= 0
Output Increment Type= 1
Profile and TS Output Increment= 10
XS Output Flag= 0
XS Output Increment= 10
Disregard all LS=0
Disregard all Conn=0
Disregard all Breaches=0
Disregard all Pumps=0

--- WFSJR 094.f01 (steady flow) ---

Flow Title=Multiple
Program Version=4.10
Number of Profiles= 7
Profile Names=10-year,25-year,50-year,1pct_min,100-year,1pct_plu,500-year
River Rch & RM=WFSJR 094,Reach-1         ,5426
     918    1270    1743     787    2376    7175    4561
River Rch & RM=WFSJR 094,Reach-1         ,1644
    2047    2947    4150    1917    5789   17483   11653
Boundary for River Rch & Prof#=WFSJR 094,Reach-1         , 1
Up Type= 0
Dn Type= 3
Dn Slope=0.007
Boundary for River Rch & Prof#=WFSJR 094,Reach-1         , 2
Up Type= 0
Dn Type= 3
Dn Slope=0.007
Boundary for River Rch & Prof#=WFSJR 094,Reach-1         , 3
Up Type= 0
Dn Type= 3
Dn Slope=0.007
Boundary for River Rch & Prof#=WFSJR 094,Reach-1         , 4
Up Type= 0
Dn Type= 3
Dn Slope=0.007
Boundary for River Rch & Prof#=WFSJR 094,Reach-1         , 5
Up Type= 0
Dn Type= 3
Dn Slope=0.007
Boundary for River Rch & Prof#=WFSJR 094,Reach-1         , 6
Up Type= 0
Dn Type= 3
Dn Slope=0.007
Boundary for River Rch & Prof#=WFSJR 094,Reach-1         , 7
Up Type= 0
Dn Type= 3
Dn Slope=0.007
DSS Import GetInterval= 0
DSS Import GetPeak= 0
DSS Import FillOption= 0

--- WFSJR 094.g01 (geometry) ---

Geom Title=Existing Conditions
Program Version=4.10

River Reach=WFSJR 094       ,Reach-1
Reach XY= 30
      3792434.06     10252861.05      3792425.38     10252706.97
      3792499.17     10252586.52       3792518.7     10252418.34
      3792594.65     10252318.51      3792589.23     10252150.33
        3792497.     10251983.23       3792511.1      10251905.1
      3792708.58     10251671.81      3792841.66     10251388.91
      3792807.63     10251350.02      3792678.46     10251395.86
      3792664.57     10251347.94      3792827.07     10251262.52
      3792831.24     10251138.91       3792874.3     10251108.36
      3792872.21     10250896.55      3792940.27     10250854.88
       3792911.1     10250818.08      3792977.07      10250690.3
      3792851.73     10250596.55      3792918.39     10250428.84
      3793016.31      10250358.7      3793041.66     10250293.77
      3793002.77     10250190.65      3792834.37     10250088.22
      3792653.46     10249705.93      3792534.71     10249550.37
      3792602.77     10249495.16      3793187.64     10248576.26

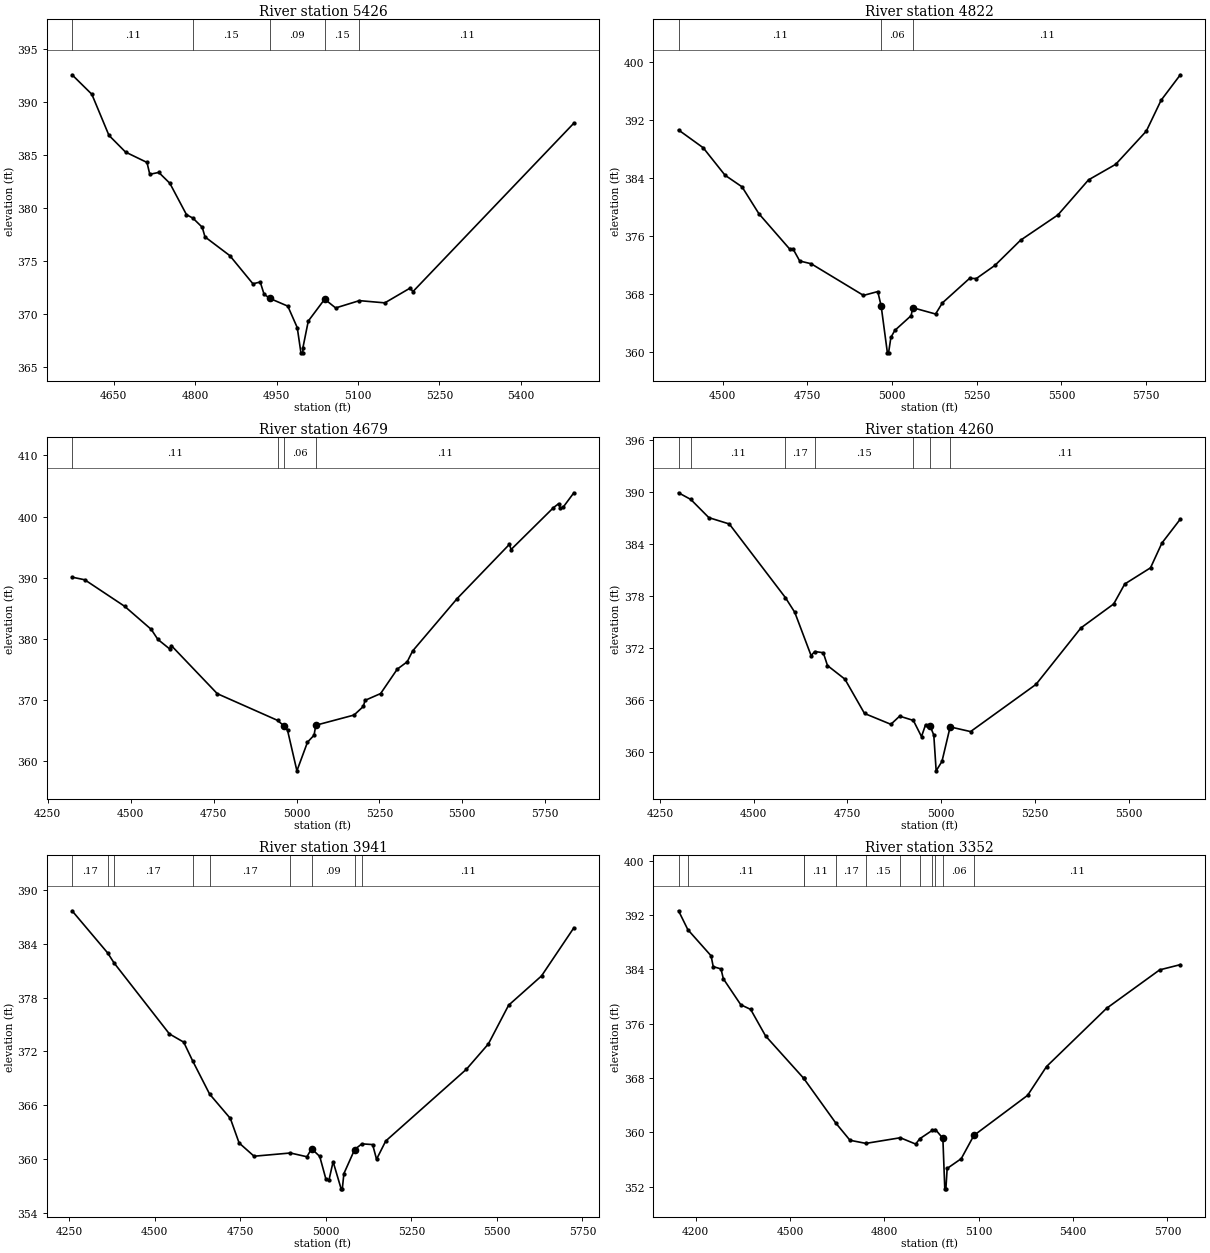
Type RM Length L Ch R = 1 ,5426    ,604,604,604
BEGIN DESCRIPTION:
WFSJR 094 11.0
END DESCRIPTION:
XS GIS Cut Line= 3
       3792844.4     10252884.08       3792426.2     10252799.87
      3791932.32     10252739.92
#Sta/Elev= 30
  4573.4  392.61  4609.8  390.77  4641.3  386.89  4671.9  385.31  4711.4  384.33
  4716.5  383.21  4733.1  383.39  4753.5  382.36  4784.1   379.4    4796  379.07
  4813.1  378.21  4818.2   377.3  4863.9  375.53  4906.5  372.87  4919.9  373.04
  4926.9   371.9  4937.1   371.5  4970.7  370.76  4988.1  368.73  4994.9  366.35
  4998.4  366.35  4998.6  366.85  5008.4  369.35  5038.6  371.42  5058.8  370.59
  5102.5  371.28  5149.4  371.07  5196.1  372.47  5201.1  372.13  5497.5  388.04
#Mann= 5 ,-1 , 0
  4573.4     .11       0    4796     .15       0  4937.1     .09       0
  5038.6     .15       0  5102.5     .11       0
Bank Sta=4937.1,5038.6
XS Rating Curve= 0 ,0
Exp/Cntr=0.3,0.1

Type RM Length L Ch R = 1 ,4822    ,143,143,143
BEGIN DESCRIPTION:
WFSJR 094 10.0
END DESCRIPTION:
XS GIS Cut Line= 3
      3793224.88     10252211.43      3792595.74     10252251.24
      3791747.79     10252320.84
#Sta/Elev= 30
  4369.6  390.66  4442.5   388.2  4506.9  384.41    4557  382.81  4607.1  379.08
  4697.3  374.24  4707.3  374.26  4727.3  372.57  4761.1  372.19  4915.5  367.82
  4957.8  368.35  4967.8  366.33  4986.1  359.89  4989.6  359.89  4996.4  362.01
  5007.9  362.98  5056.1  365.02  5061.1  366.12  5128.3  365.25  5148.4  366.78
  5228.7  370.17  5248.7  370.15  5303.7  371.97  5379.2  375.44  5489.5  378.93
  5579.8  383.77  5660.1  385.92  5750.4   390.5    5794  394.76  5850.8  398.28
#Mann= 3 , 0 , 0
  4369.6     .11       0  4967.8     .06       0  5061.1     .11       0
Bank Sta=4967.8,5061.1
XS Rating Curve= 0 ,0
Exp/Cntr=0.3,0.1

Type RM Length L Ch R = 1 ,4679    ,419,419,419
BEGIN DESCRIPTION:
WFSJR 094 9.0
END DESCRIPTION:
XS GIS Cut Line= 2
      3793245.95     10252065.96      3791736.58     10252169.15
#Sta/Elev= 30
  4323.3  390.08  4361.5  389.65  4481.8  385.31    4562  381.53    4582  379.89
  4617.6  378.33  4622.6  378.88  4761.1  371.01  4942.8  366.64  4962.9   365.7
  4972.9  365.03  5001.2  358.38  5033.1  363.07    5053  364.22    5058  365.84
  5173.4  367.51  5201.5  368.92  5206.5  369.91  5253.6  371.03  5303.7  375.02
  5333.8  376.23    5350  377.99  5484.1  386.56  5641.9  395.45  5646.9   394.6
  5774.8  401.46  5790.4  402.11  5795.4  401.34  5804.9   401.6  5836.2  403.89
#Mann= 4 ,-1 , 0
  4323.3     .11       0  4942.8     .11       0  4962.9     .06       0
    5058     .11       0
Bank Sta=4962.9,5058
XS Rating Curve= 0 ,0
Exp/Cntr=0.3,0.1

Type RM Length L Ch R = 1 ,4260    ,319,319,319
BEGIN DESCRIPTION:
Mapping XS 8ff145e6
END DESCRIPTION:
XS GIS Cut Line= 2
      3793272.05     10252042.32      3792044.95     10251507.72
#Sta/Elev= 30
  4299.5   389.9  4332.2  389.13  4380.4  387.03  4434.9   386.3  4584.4  377.81
  4609.5  376.11  4653.1  371.11  4662.8  371.58  4685.6  371.44  4696.8  369.96
  4743.3  368.39  4795.6  364.43  4865.9  363.18  4889.3  364.12  4925.8  363.63
  4947.6  361.76  4958.5  363.14  4970.5     363  4980.4  361.93  4986.7  357.81
  5002.2   358.9    5024  362.88  5078.5  362.34  5253.1  367.79    5373  374.31
  5460.3  377.07  5489.7  379.37  5558.5  381.24  5588.9   384.1    5638  386.86
#Mann= 7 ,-1 , 0
  4299.5     .17       0  4332.2     .11       0  4584.4     .17       0
  4662.8     .15       0  4925.8     .11       0  4970.5     .06       0
    5024     .11       0
Bank Sta=4970.5,5024
XS Rating Curve= 0 ,0
Exp/Cntr=0.3,0.1

Type RM Length L Ch R = 1 ,3941    ,589,589,589
BEGIN DESCRIPTION:
WFSJR 094 8.0
END DESCRIPTION:
XS GIS Cut Line= 3
      3793320.05     10251954.81      3793047.48     10251572.86
      3792097.83     10251269.04
#Sta/Elev= 30
  4258.6  387.69  4362.5  382.99  4381.3  381.87    4543  373.95  4584.8  373.03
  4610.7  370.96  4660.6  367.23  4721.2  364.51  4746.7  361.78  4790.4   360.3
  4896.6  360.66  4944.9  360.24  4958.4  361.14  4982.3  360.28  5000.4  357.74
  5009.2  357.62  5021.4  359.69  5044.8  356.66  5048.3  356.66  5052.9  358.36
  5084.4  361.05  5105.4  361.68  5136.9   361.6  5148.3  359.96  5175.2     362
  5410.8     370  5475.1  372.83  5534.2  377.15  5630.4  380.42  5724.9  385.79
#Mann= 9 ,-1 , 0
  4258.6     .17       0  4362.5     .15       0  4381.3     .17       0
  4610.7     .11       0  4660.6     .17       0  4896.6     .15       0
  4958.4     .09       0  5084.4     .15       0  5105.4     .11       0
Bank Sta=4958.4,5084.4
XS Rating Curve= 0 ,0
Exp/Cntr=0.3,0.1

Type RM Length L Ch R = 1 ,3352    ,330,330,330
BEGIN DESCRIPTION:
WFSJR 094 7.0
END DESCRIPTION:
XS GIS Cut Line= 3
      3793646.46     10251499.95      3792831.94     10251240.99
      3792094.34     10251170.08
#Sta/Elev= 30
  4145.3  392.63  4174.9  389.85  4248.8     386  4255.6  384.41  4280.3  384.07
  4287.8  382.62  4343.2   378.8  4374.7  378.11    4422  374.21  4543.5  367.96
  4543.6  367.95  4645.8  361.36  4690.5  358.85    4741  358.39  4850.6  359.22
  4899.4  358.29  4912.3  359.07  4952.9  360.33  4962.3  360.43  4985.9  359.13
    4992   351.7  4995.5   351.7  4999.5   354.7  5044.3  356.14  5084.5  359.56
  5255.3  365.46  5315.5   369.7  5506.4  378.27  5675.3  383.93    5741   384.7
#Mann= 12 ,-1 , 0
  4145.3     .17       0  4174.9     .11       0  4543.5     .17       0
  4543.6     .11       0  4645.8     .17       0    4741     .15       0
  4850.6     .11       0  4912.3     .17       0  4952.9     .11       0
  4962.3     .11       0  4985.9     .06       0  5084.5     .11       0
Bank Sta=4985.9,5084.5
XS Rating Curve= 0 ,0
Exp/Cntr=0.3,0.1

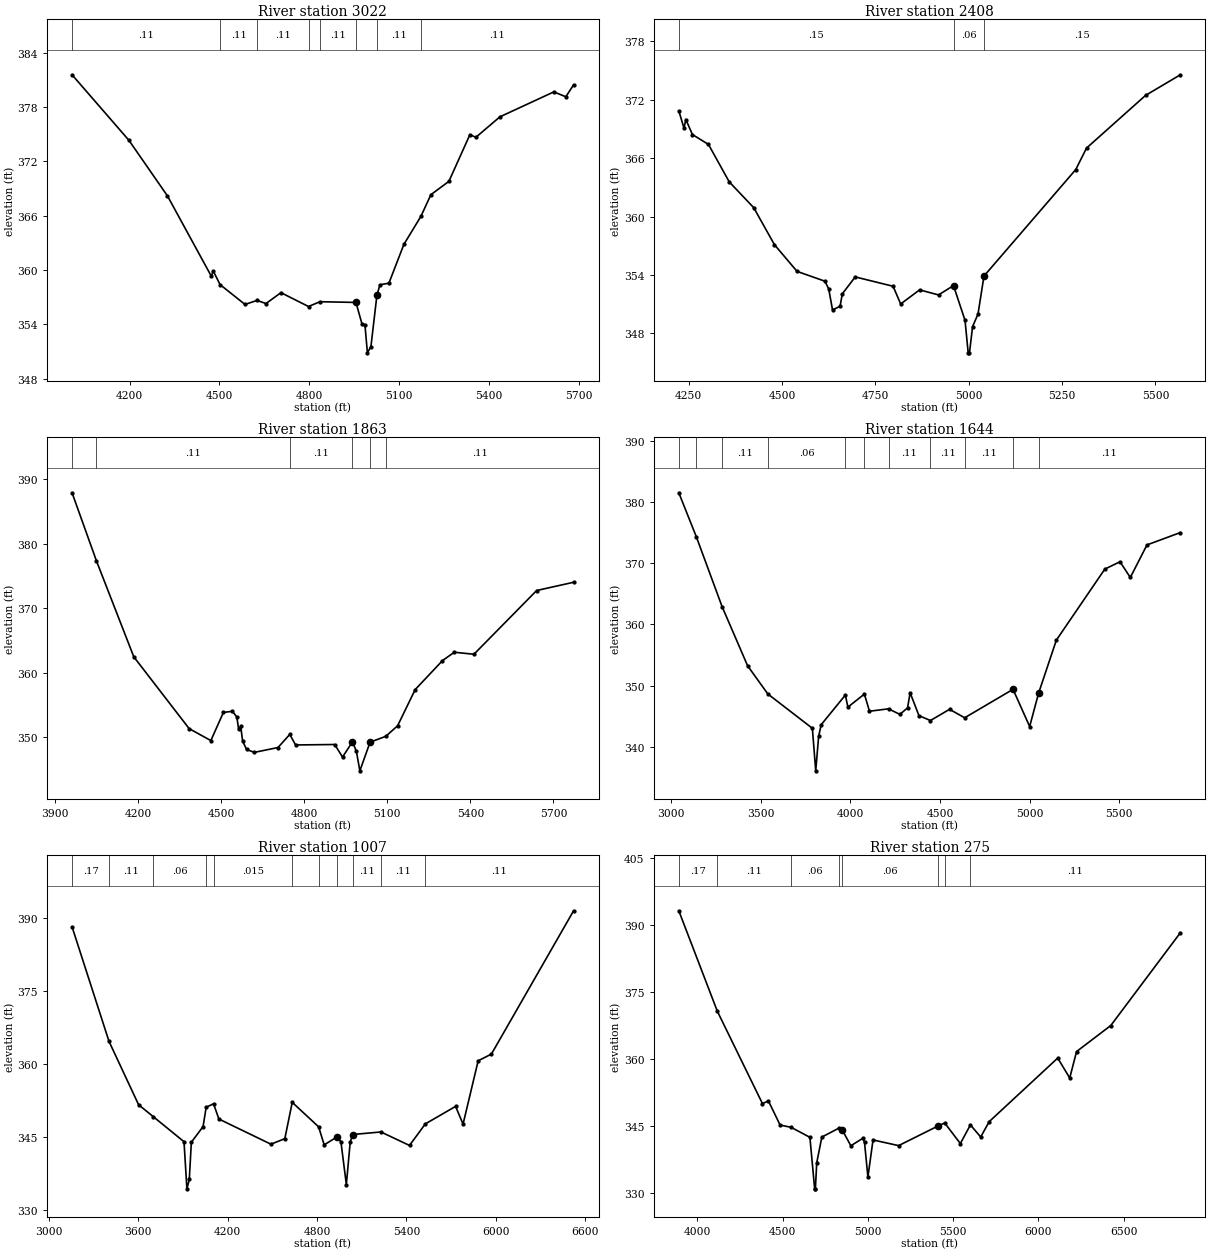
Type RM Length L Ch R = 1 ,3022    ,614,614,614
BEGIN DESCRIPTION:
WFSJR 094 6.0
END DESCRIPTION:
XS GIS Cut Line= 3
      3793780.15      10251227.4      3793339.14     10250960.01
      3792182.01     10250921.85
#Sta/Elev= 30
  4008.2  381.57  4197.9  374.33  4326.6  368.18  4473.2  359.29  4479.1   359.9
  4502.1  358.38  4585.3  356.19  4625.3  356.63  4655.3  356.29  4705.3  357.49
  4797.2  355.96  4835.4  356.49  4955.5  356.41  4975.5  354.05  4985.5  353.94
  4993.7  350.84  5005.5  351.54  5025.5  357.22  5035.5  358.36  5065.5  358.54
  5115.5  362.83    5172  365.91  5205.6  368.32  5265.6  369.79  5335.7  374.95
  5355.7  374.66  5435.7  376.92  5615.8  379.68  5655.8  379.14  5681.7  380.46
#Mann= 8 ,-1 , 0
  4008.2     .11       0  4502.1     .11       0  4625.3     .11       0
  4797.2     .11       0  4835.4     .11       0  4955.5     .06       0
  5025.5     .11       0    5172     .11       0
Bank Sta=4955.5,5025.5
XS Rating Curve= 0 ,0
Exp/Cntr=0.3,0.1

Type RM Length L Ch R = 1 ,2408    ,545,545,545
BEGIN DESCRIPTION:
WFSJR 094 5.0
END DESCRIPTION:
XS GIS Cut Line= 3
      3793663.81     10250638.83        3792794.     10250492.56
      3792385.22     10250706.07
#Sta/Elev= 30
  4223.4  370.87  4237.3   369.1  4242.3  369.98  4259.9  368.44  4302.9  367.42
  4358.4  363.58  4424.1  360.92  4479.6  357.12  4540.1  354.38  4614.8  353.37
  4624.9  352.57  4635.1  350.42  4655.3  350.79  4661.3  352.07  4695.9  353.81
  4797.3  352.85  4817.6  351.03  4868.3  352.48    4919  351.96  4959.1  352.92
    4990  349.34  4998.4  346.01  5001.9  346.01  5010.2  348.71  5024.7  349.99
  5040.7   353.9  5286.5  364.84  5315.4  367.05  5473.4  372.46  5566.6  374.58
#Mann= 3 , 0 , 0
  4223.4     .15       0  4959.1     .06       0  5040.7     .15       0
Bank Sta=4959.1,5040.7
XS Rating Curve= 0 ,0
Exp/Cntr=0.3,0.1

Type RM Length L Ch R = 1 ,1863    ,219,219,219
BEGIN DESCRIPTION:
WFSJR 094 4.0
END DESCRIPTION:
XS GIS Cut Line= 4
      3793643.88     10250120.38      3793338.28     10249851.94
       3793166.4     10249784.23      3792353.91     10250695.68
#Sta/Elev= 30
  3960.5  387.92  4048.4  377.37  4183.6  362.44  4383.6  351.29  4462.1  349.43
  4507.4   353.8  4539.7  353.98  4555.9  353.11  4562.6  351.19  4570.1  351.63
  4576.8  349.39    4591  348.05  4619.4   347.6  4704.7  348.35  4747.3  350.39
  4768.3  348.75  4909.6  348.82    4938  346.87  4973.9  349.24  4988.1  347.76
  5000.6  344.73  5037.5  349.18  5094.3  350.09    5137  351.73  5200.5  357.35
  5299.2  361.85  5341.8  363.15  5412.9  362.84  5639.5  372.74    5773  374.02
#Mann= 6 ,-1 , 0
  3960.5     .17       0  4048.4     .11       0  4747.3     .11       0
  4973.9     .06       0  5037.5     .11       0  5094.3     .11       0
Bank Sta=4973.9,5037.5
XS Rating Curve= 0 ,0
Exp/Cntr=0.3,0.1

Type RM Length L Ch R = 1 ,1644    ,637,637,637
BEGIN DESCRIPTION:
WFSJR 094 3.0
END DESCRIPTION:
XS GIS Cut Line= 3
      3794039.32     10248471.09      3792830.46     10249833.71
      3792218.51     10250594.09
#Sta/Elev= 30
  3042.6  381.49  3140.1  374.32  3284.3  362.87  3426.3  353.23  3539.2  348.62
  3787.6  343.01  3806.4  336.06  3822.7  341.72  3836.9   343.6  3971.6  348.44
  3985.8  346.47  4077.8   348.6  4106.2   345.8  4212.4  346.19    4276  345.28
  4318.7  346.36  4332.9  348.82  4382.2  345.08  4446.2  344.28  4552.8  346.11
  4637.3  344.73  4906.9  349.38  4999.7   343.3  5049.3  348.73  5148.5  357.41
  5418.9  369.02  5503.7  370.22  5561.2  367.65    5654  372.97  5840.2  374.99
#Mann= 11 ,-1 , 0
  3042.6     .11       0  3140.1     .13       0  3284.3     .11       0
  3539.2     .06       0  3971.6     .11       0  4077.8     .11       0
  4212.4     .11       0  4446.2     .11       0  4637.3     .11       0
  4906.9     .06       0  5049.3     .11       0
Bank Sta=4906.9,5049.3
XS Rating Curve= 0 ,0
Exp/Cntr=0.3,0.1

Type RM Length L Ch R = 1 ,1007    ,732,732,732
BEGIN DESCRIPTION:
WFSJR 094 2.0
END DESCRIPTION:
XS GIS Cut Line= 5
      3794031.38     10248434.68      3793356.89     10249189.89
      3792939.16     10249513.25      3792106.89     10249221.14
      3791166.79     10249236.77
#Sta/Elev= 30
  3157.4  388.28  3405.2  364.73  3603.6  351.71  3702.3  349.25    3908  344.11
  3927.6  334.42  3943.6  336.34  3957.3     344  4035.8  347.21  4056.8  351.19
  4106.1  351.91    4142  348.77  4490.8   343.6  4584.1  344.73  4633.9   352.2
  4810.7  347.17    4848  343.46  4934.7   345.1  4960.4  344.08  4996.7   335.3
  5022.4  343.99  5038.8  345.59  5228.7  346.11  5420.3  343.34  5526.3  347.77
  5729.3  351.37  5779.3  347.72  5880.6  360.74  5969.4  362.12  6520.5  391.58
#Mann= 11 ,-1 , 0
  3157.4     .17       0  3405.2     .11       0  3702.3     .06       0
  4056.8     .11       0  4106.1    .015       0  4633.9     .11       0
  4810.7     .11       0  4934.7     .06       0  5038.8     .11       0
  5228.7     .11       0  5526.3     .11       0
Bank Sta=4934.7,5038.8
XS Rating Curve= 0 ,0
Exp/Cntr=0.3,0.1

Type RM Length L Ch R = 1 ,275     ,0,0,0
BEGIN DESCRIPTION:
WFSJR 094 1.0
END DESCRIPTION:
XS GIS Cut Line= 4
      3794017.99     10248411.81      3793551.82     10248781.63
      3792689.84     10248818.08       3791211.8      10248958.6
#Sta/Elev= 30
  3890.7   393.2  4116.6  370.69  4381.3  349.98  4416.5  350.56  4485.1  345.16
  4549.8  344.65  4659.9  342.41  4687.8  330.86    4692  330.86  4699.9   336.7
  4729.9  342.47  4831.3  344.49    4850  344.03  4900.1  340.52  4970.1  342.19
  4980.2  341.29  5000.2   333.5  5030.2  341.82  5180.3  340.55  5410.8  344.94
  5450.9  345.62  5542.5  341.01  5601.6   345.2  5661.9  342.48  5712.1  345.94
  6113.9  360.18  6184.2  355.71  6224.4  361.64  6425.3  367.48  6833.2  388.27
#Mann= 8 ,-1 , 0
  3890.7     .17       0  4116.6     .11       0  4549.8     .06       0
  4831.3     .11       0    4850     .06       0  5410.8     .11       0
  5450.9     .11       0  5601.6     .11       0
Bank Sta=4850,5410.8
XS Rating Curve= 0 ,0
Exp/Cntr=0.3,0.1

Chan Stop Cuts=-1
Use User Specified Reach Order=0
Composite Channel Slope=5