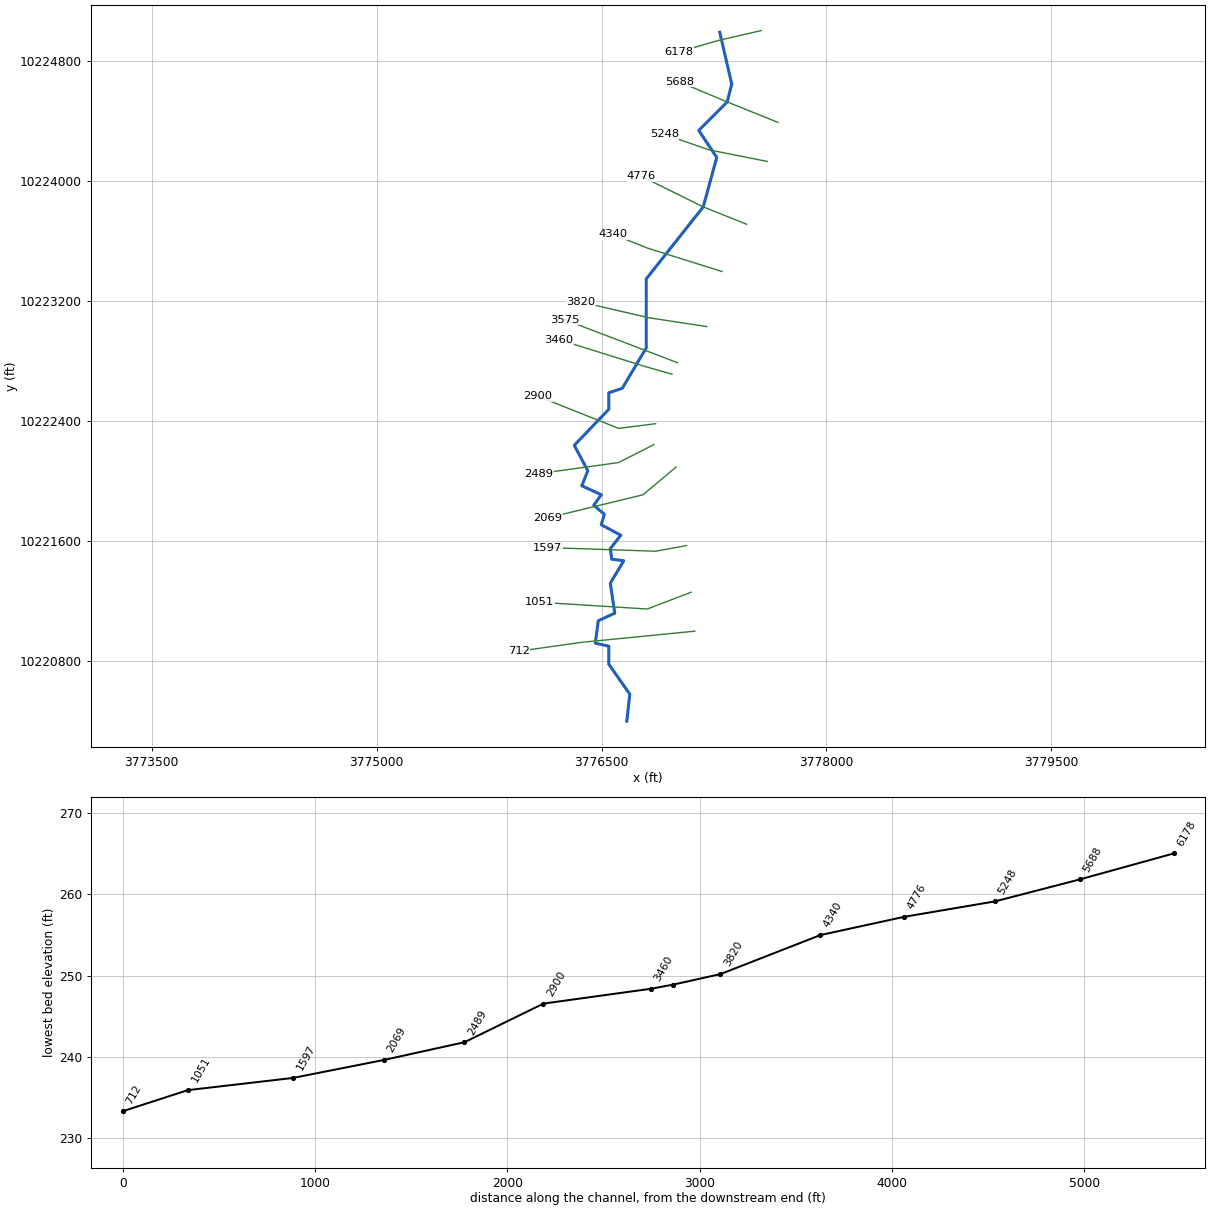
--- WFSJR 097.prj (project) ---

Proj Title=WFSJR 097 Base Level Engineering
Current Plan=p01
Default Exp/Contr=0.3,0.1
English Units
Geom File=g01
Flow File=f01
Plan File=p01
Y Axis Title=Elevation
X Axis Title(PF)=Main Channel Distance
X Axis Title(XS)=Station
BEGIN DESCRIPTION:
WFSJR 097
END DESCRIPTION:
DSS Export Rating Curves= 0
DSS Export Rating Curve Sorted= 0
DSS Export Volume Flow Curves= 0
DXF OffsetX= 0
DXF OffsetY= 0
DXF ScaleX= 1
DXF ScaleY= 10

--- WFSJR 097.p01 (plan) ---

Plan Title=Multiple Run
Program Version=4.10
Short Identifier=Multiple
Geom File=g01
Flow File=f01
Subcritical Flow
K Sum by GR= 0
Std Step Tol= 0.01
Critical Tol= 0.01
Num of Std Step Trials= 20
Max Error Tol= 0.3
Flow Tol Ratio= 0.001
Split Flow NTrial= 30
Split Flow Tol= 0.02
Split Flow Ratio= 0.02
Log Output Level= 0
Friction Slope Method= 1
Unsteady Friction Slope Method= 2
Unsteady Bridges Friction Slope Method= 1
Parabolic Critical Depth
Global Vel Dist= 1 , 1 , 1
Global Log Level= 0
CheckData=True
Encroach Param=-1 ,0,0, 0
BEGIN DESCRIPTION:
Multiple Run
END DESCRIPTION:
Computation Interval=1HOUR
Output Interval=1HOUR
Run HTab= 0
Run UNet= 0
Run PostProcess= 0
Run WQNet= 0
UNET Theta= 1
UNET Theta Warmup= 1
UNET ZTol= 0.02
UNET ZSATol= 0.05
UNET MxIter= 20
UNET MaxInSteps= 0
UNET DtIC= 0
UNET DtMin= 0
UNET MaxCRTS= 20
UNET WFStab= 2
UNET SFStab= 1
UNET WFX= 1
UNET SFX= 1
UNET DSS MLevel= 4
UNET DZMax Abort= 100
UNET Convert EG Bridges= 0
UNET Use Existing IB Tables=-1
UNET Froude Reduction=False
UNET Froude Limit= 1
UNET Froude Power= 10
UNET Time Slicing=0,0, 5
UNET Junction Losses=0
Instantaneous Interval=1HOUR
Write IC File= 0
Write IC File at Sim End=0
Echo Input=False
Echo Parameters=False
Echo Output=False
Write Detailed= 0
WQ AD Non Conservative
WQ ULTIMATE=-1
WQ Max Comp Step=1HOUR
WQ Output Interval=15MIN
WQ Output Selected Increments= 0
WQ Output face flow=0
WQ Output face velocity=0
WQ Output face area=0
WQ Output face dispersion=0
WQ Output cell volume=0
WQ Output cell surface area=0
WQ Output cell continuity=0
WQ Output cumulative cell continuity=0
WQ Output face conc=0
WQ Output face dconc_dx=0
WQ Output face courant=0
WQ Output face peclet=0
WQ Output face adv mass=0
WQ Output face disp mass=0
WQ Output cell mass=0
WQ Output cell source sink temp=0
WQ Output cell source sink nsm=0
WQ Output MaxMinRange=-1
WQ Daily Max Min Mean=-1
WQ Daily Range=0
WQ Daily Time=0
WQ Create Restart=0
WQ Fixed Restart=0
WQ System Summary=0
WQ Use Fixed Temperature=0
Sorting and Armoring Iterations= 10
XS Update Threshold= 0.02
Hydraulics Update Threshold= 0.02
Energy Slope Method= 1
Volume Change Method= 0
XS Weighting Method= 0
Number of US Weighted Cross Sections= 1
Number of DS Weighted Cross Sections= 1
Upstream XS Weight=0.25
Main XS Weight=0.5
Downstream XS Weight=0.25
Number of DS XS's Weighted with US Boundary= 1
Upstream Boundary Weight= 1
Weight of XSs Associated with US Boundary= 0
Number of US XS's Weighted with DS Boundary= 1
Downstream Boundary Weight= 0.5
Weight of XSs Associated with DS Boundary= 0.5
Sediment Output Level= 4
Mass or Volume Output= 0
Output Increment Type= 1
Profile and TS Output Increment= 10
XS Output Flag= 0
XS Output Increment= 10
Disregard all LS=0
Disregard all Conn=0
Disregard all Breaches=0
Disregard all Pumps=0

--- WFSJR 097.f01 (steady flow) ---

Flow Title=Multiple
Program Version=4.10
Number of Profiles= 7
Profile Names=10-year,25-year,50-year,1pct_min,100-year,1pct_plu,500-year
River Rch & RM=WFSJR 097,Reach-1         ,6178
     508     680     914     405    1222    3690    2255
River Rch & RM=WFSJR 097,Reach-1         ,5688
     642     870    1178     524    1583    4781    2960
Boundary for River Rch & Prof#=WFSJR 097,Reach-1         , 1
Up Type= 0
Dn Type= 3
Dn Slope=0.008
Boundary for River Rch & Prof#=WFSJR 097,Reach-1         , 2
Up Type= 0
Dn Type= 3
Dn Slope=0.008
Boundary for River Rch & Prof#=WFSJR 097,Reach-1         , 3
Up Type= 0
Dn Type= 3
Dn Slope=0.008
Boundary for River Rch & Prof#=WFSJR 097,Reach-1         , 4
Up Type= 0
Dn Type= 3
Dn Slope=0.008
Boundary for River Rch & Prof#=WFSJR 097,Reach-1         , 5
Up Type= 0
Dn Type= 3
Dn Slope=0.008
Boundary for River Rch & Prof#=WFSJR 097,Reach-1         , 6
Up Type= 0
Dn Type= 3
Dn Slope=0.008
Boundary for River Rch & Prof#=WFSJR 097,Reach-1         , 7
Up Type= 0
Dn Type= 3
Dn Slope=0.008
DSS Import GetInterval= 0
DSS Import GetPeak= 0
DSS Import FillOption= 0

--- WFSJR 097.g01 (geometry) ---

Geom Title=Existing Conditions
Program Version=4.10

River Reach=WFSJR 097       ,Reach-1
Reach XY= 30
      3777288.23     10224991.84      3777368.23     10224646.84
      3777338.23     10224526.84      3777148.23     10224336.84
      3777268.23     10224156.84      3777178.23     10223826.84
      3776798.23     10223346.84      3776798.23     10222886.84
      3776638.23     10222616.84      3776548.23     10222586.84
      3776548.23     10222476.84      3776318.23     10222236.84
      3776408.23     10222066.84      3776368.23     10221966.84
      3776498.23     10221906.84      3776448.23     10221836.84
      3776518.23     10221776.84      3776498.23     10221706.84
      3776628.23     10221636.84      3776558.23     10221546.84
      3776568.23     10221476.84      3776648.23     10221466.84
      3776558.23     10221316.84      3776588.23     10221116.84
      3776478.23     10221066.84      3776458.23     10220916.84
      3776548.23     10220896.84      3776548.23     10220776.84
      3776688.23     10220576.84      3776668.23     10220396.84

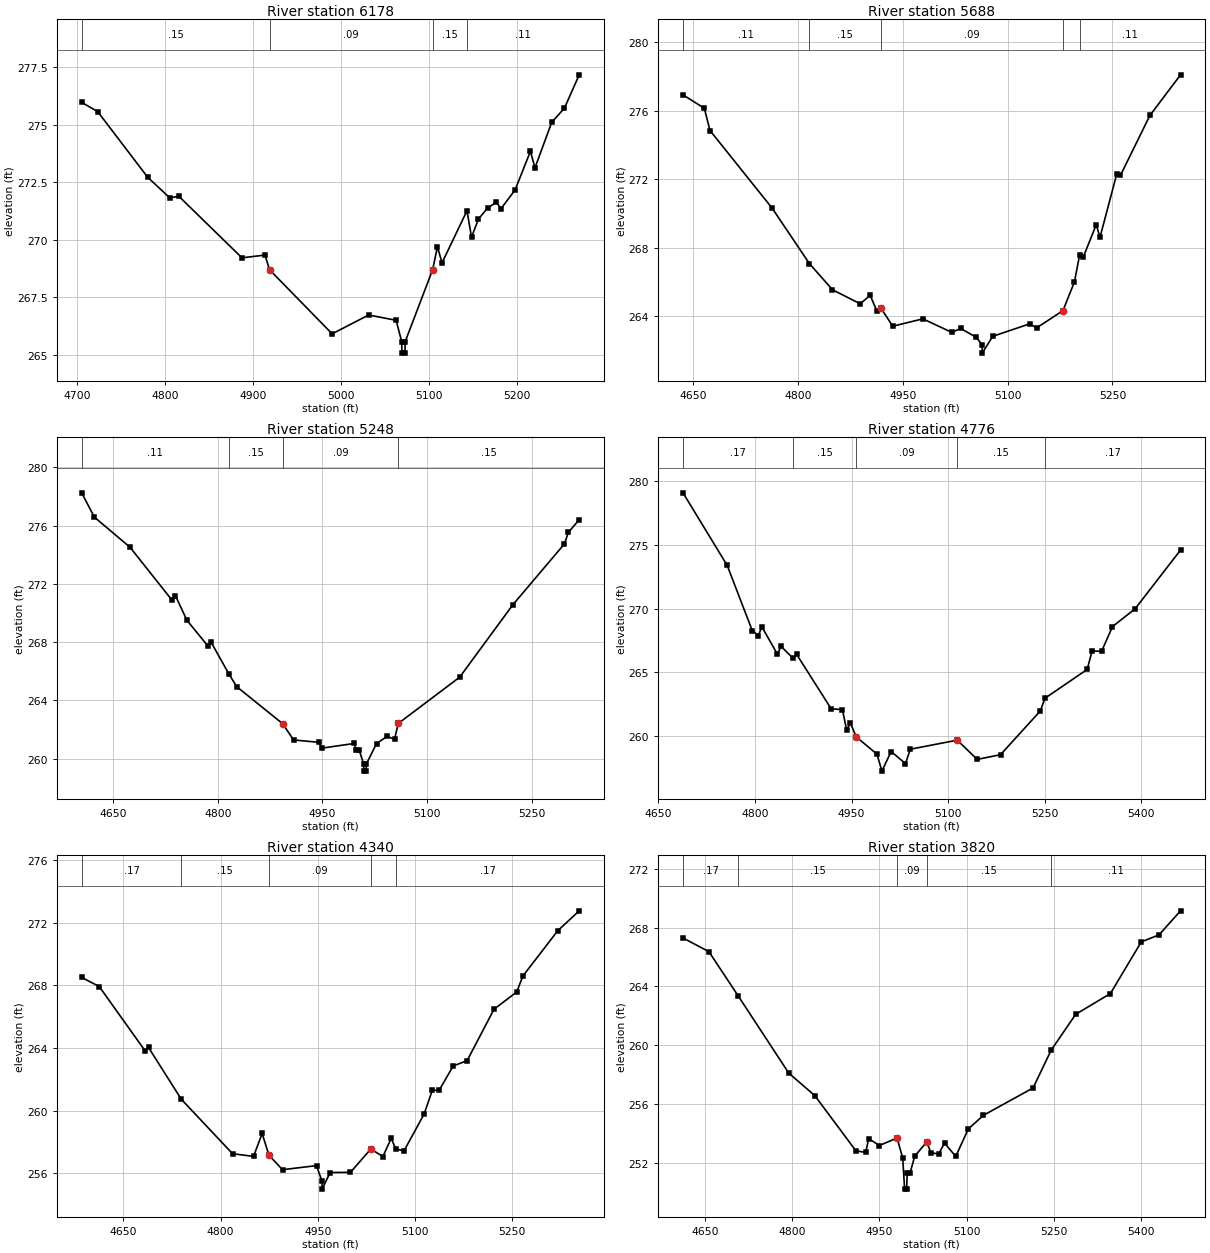
Type RM Length L Ch R = 1 ,6178    ,490,490,490
BEGIN DESCRIPTION:
WFSJR 097 13.0
END DESCRIPTION:
XS GIS Cut Line= 3
      3777565.61       10225003.      3777278.23     10224936.84
      3777017.83     10224861.07
#Sta/Elev= 30
  4705.1  275.98  4723.3  275.58  4780.2  272.72  4805.4  271.82  4815.7  271.89
  4887.5  269.21  4913.7  269.33  4918.9  268.69  4990.1   265.9  5031.6  266.72
  5062.9  266.49  5069.2  265.56  5069.5  265.06    5073  265.06  5073.2  265.56
  5104.5   268.7  5109.9   269.7  5115.1  268.99  5143.5  271.26  5148.7  270.11
  5156.6   270.9    5167  271.38    5177  271.63  5182.2  271.35  5198.3  272.17
  5215.7  273.85  5220.9  273.13  5239.9  275.11  5254.4  275.73  5271.2  277.18
#Mann= 4 ,-1 , 0
  4705.1     .15       0  4918.9     .09       0  5104.5     .15       0
  5143.5     .11       0
Bank Sta=4918.9,5104.5
XS Rating Curve= 0 ,0
Exp/Cntr=0.3,0.1

Type RM Length L Ch R = 1 ,5688    ,440,440,440
BEGIN DESCRIPTION:
WFSJR 097 12.0
END DESCRIPTION:
XS GIS Cut Line= 3
      3777676.11     10224390.64      3777338.23     10224526.84
      3777017.82     10224661.09
#Sta/Elev= 30
  4635.7  276.92  4666.2  276.14  4674.3  274.84  4763.2  270.31  4816.6  267.07
  4849.5  265.55  4889.1  264.73  4903.4  265.22  4913.2   264.3  4918.6  264.49
  4935.7  263.42  4978.8  263.85  5020.3  263.06  5032.9  263.29  5054.9  262.78
  5063.5  262.35  5063.7  261.85  5078.7  262.83  5131.7  263.56  5141.4  263.32
  5179.2  264.33  5195.6     266    5203  267.57  5208.4  267.47  5226.8  269.34
  5232.2  268.61    5256  272.28  5261.4  272.22  5303.6  275.72  5347.4  278.09
#Mann= 5 ,-1 , 0
  4635.7     .11       0  4816.6     .15       0  4918.6     .09       0
  5179.2     .15       0    5203     .11       0
Bank Sta=4918.6,5179.2
XS Rating Curve= 0 ,0
Exp/Cntr=0.3,0.1

Type RM Length L Ch R = 1 ,5248    ,472,472,472
BEGIN DESCRIPTION:
WFSJR 097 11.0
END DESCRIPTION:
XS GIS Cut Line= 3
      3777605.73     10224130.24      3777218.23     10224206.84
       3776917.9     10224311.06
#Sta/Elev= 30
    4605  278.25  4623.2  276.58  4674.2  274.52  4734.2   270.9  4739.3   271.2
  4755.7  269.51  4785.5  267.76  4790.6  267.99  4815.9  265.82  4827.1  264.95
  4893.1   262.4  4908.6  261.29  4944.4  261.13  4949.5  260.73  4995.7  261.05
    4998  260.57  5002.8  260.57    5009  259.65  5009.2  259.15  5012.7  259.15
    5013  259.65  5027.5  261.04  5042.7  261.54  5053.3  261.33  5058.6  262.42
  5146.7   265.6  5222.7  270.56  5296.8  274.75  5302.4  275.54  5317.9   276.4
#Mann= 4 ,-1 , 0
    4605     .11       0  4815.9     .15       0  4893.1     .09       0
  5058.6     .15       0
Bank Sta=4893.1,5058.6
XS Rating Curve= 0 ,0
Exp/Cntr=0.3,0.1

Type RM Length L Ch R = 1 ,4776    ,436,436,436
BEGIN DESCRIPTION:
WFSJR 097 10.0
END DESCRIPTION:
XS GIS Cut Line= 3
      3777467.85     10223711.07      3777178.23     10223826.84
       3776764.6     10224031.29
#Sta/Elev= 30
  4688.1  279.09  4756.8  273.39  4795.8  268.27  4805.3  267.89  4810.6  268.58
  4834.9  266.42  4840.3  267.05  4859.5  266.09  4864.5  266.43  4918.4  262.14
  4935.8  262.08  4942.6  260.44    4948  261.06  4957.3  259.94  4989.6  258.58
  4997.2  257.25  5011.6  258.79  5033.9  257.84  5041.4  258.97  5114.3  259.68
  5145.4  258.17  5181.6  258.54  5243.4  261.97  5250.7  262.97  5316.3  265.23
  5323.9  266.68  5338.7  266.65  5355.6  268.59  5390.8  269.99  5461.4   274.6
#Mann= 5 ,-1 , 0
  4688.1     .17       0  4859.5     .15       0  4957.3     .09       0
  5114.3     .15       0  5250.7     .17       0
Bank Sta=4957.3,5114.3
XS Rating Curve= 0 ,0
Exp/Cntr=0.3,0.1

Type RM Length L Ch R = 1 ,4340    ,520,520,520
BEGIN DESCRIPTION:
WFSJR 097 9.0
END DESCRIPTION:
XS GIS Cut Line= 3
      3777303.68     10223395.86      3776806.29     10223552.11
       3776577.1     10223643.26
#Sta/Elev= 30
  4585.5  268.51  4612.6  267.93  4683.5  263.82  4688.7  264.04  4739.2  260.74
  4818.4  257.26  4850.8  257.09  4864.1  258.55  4874.6  257.16  4895.6  256.24
    4948   256.5  4956.5   255.5  4956.7     255    4969  256.06  5000.4  256.07
  5031.8  257.56  5050.5  257.08  5063.3  258.24  5070.1  257.58  5082.9  257.43
  5114.1  259.79  5126.7   261.3  5137.5  261.32    5159  262.86  5180.5   263.2
    5222  266.48    5257  267.58  5266.6   268.6  5320.4  271.49  5353.5  272.76
#Mann= 5 ,-1 , 0
  4585.5     .17       0  4739.2     .15       0  4874.6     .09       0
  5031.8     .15       0  5070.1     .17       0
Bank Sta=4874.6,5031.8
XS Rating Curve= 0 ,0
Exp/Cntr=0.3,0.1

Type RM Length L Ch R = 1 ,3820    ,245,245,245
BEGIN DESCRIPTION:
WFSJR 097 8.0
END DESCRIPTION:
XS GIS Cut Line= 3
      3777202.15     10223028.67      3776818.23     10223086.84
      3776361.91     10223192.52
#Sta/Elev= 30
  4611.7  267.29  4656.3  266.36    4707  263.33  4793.8  258.09  4838.6  256.56
  4909.4   252.8  4926.3  252.69  4931.4  253.63  4949.8  253.16  4980.2  253.67
    4990  252.31  4993.3  250.19  4996.8  250.19  4997.7  251.31  5002.8  251.31
  5010.7  252.43  5031.2   253.4  5038.6  252.67  5051.7  252.58    5062  253.32
  5081.3  252.42    5103  254.29  5129.1  255.22  5214.5  257.08  5245.6  259.65
  5287.8  262.09  5347.7  263.51  5400.7  267.02  5431.5  267.51  5468.4  269.14
#Mann= 5 ,-1 , 0
  4611.7     .17       0    4707     .15       0  4980.2     .09       0
  5031.2     .15       0  5245.6     .11       0
Bank Sta=4980.2,5031.2
XS Rating Curve= 0 ,0
Exp/Cntr=0.3,0.1

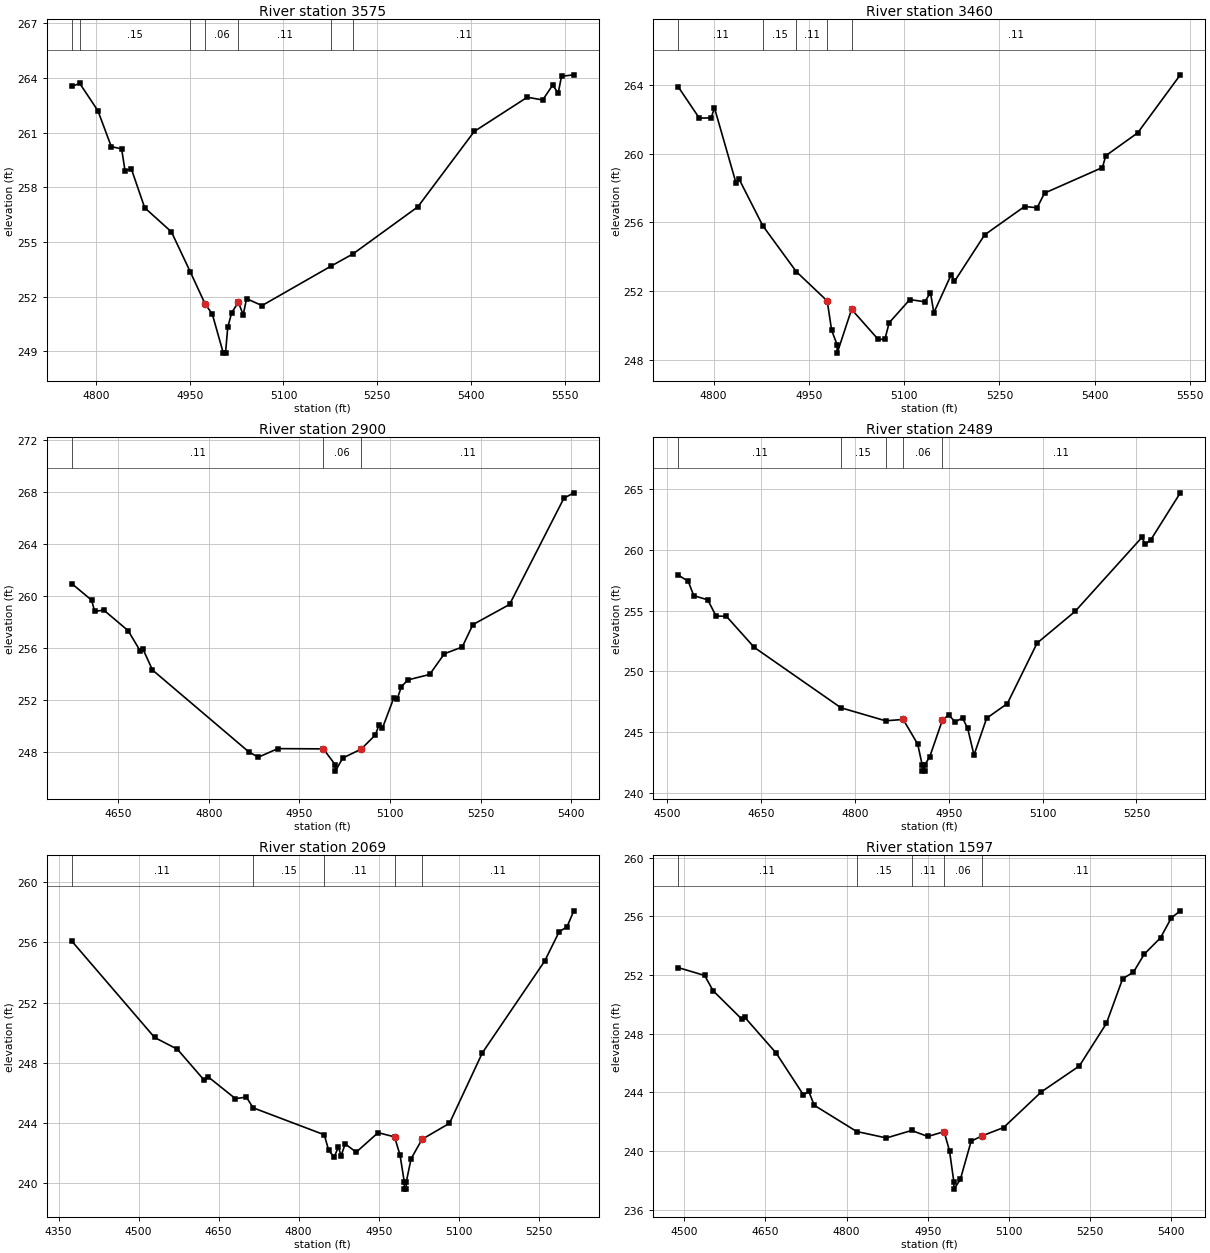
Type RM Length L Ch R = 1 ,3575    ,115,115,115
BEGIN DESCRIPTION:
Mapping XS 95bc1c57
END DESCRIPTION:
XS GIS Cut Line= 2
      3777007.11     10222787.36      3776256.29      10223073.8
#Sta/Elev= 30
  4761.1  263.54    4774  263.71  4803.1  262.21  4824.5  260.24  4841.1  260.11
  4846.5  258.91  4856.6  259.02    4878  256.88  4920.7  255.56  4950.7  253.38
  4974.4  251.62  4986.2  251.04  5003.8   248.9  5007.3   248.9  5010.9  250.32
  5017.2  251.12  5027.9   251.7  5035.6     251    5041  251.89  5065.7  251.51
  5176.8  253.69  5211.4  254.35    5315  256.93  5405.3  261.07  5490.2  262.95
  5514.9   262.8  5530.9  263.62  5539.6  263.17    5545   264.1  5564.7  264.18
#Mann= 7 ,-1 , 0
  4761.1     .17       0    4774     .15       0  4950.7     .11       0
  4974.4     .06       0  5027.9     .11       0  5176.8     .15       0
  5211.4     .11       0
Bank Sta=4974.4,5027.9
XS Rating Curve= 0 ,0
Exp/Cntr=0.3,0.1

Type RM Length L Ch R = 1 ,3460    ,560,560,560
BEGIN DESCRIPTION:
WFSJR 097 7.0
END DESCRIPTION:
XS GIS Cut Line= 3
      3776969.84     10222710.95      3776793.59     10222761.31
      3776213.76     10222941.86
#Sta/Elev= 30
  4744.1  263.91  4777.4  262.08  4796.1  262.09  4801.3  262.68  4835.1  258.32
  4840.3  258.51  4877.4  255.81  4930.1  253.14  4978.8  251.43  4985.8  249.72
  4994.3  248.89  4994.5  248.39  5017.2  250.94  5059.1  249.19  5069.6   249.2
  5076.4  250.16  5108.9  251.51  5132.4  251.38  5141.4  251.91  5146.7  250.74
    5174  252.96  5179.2  252.57  5226.7  255.28  5289.5  256.93  5309.3  256.86
  5320.9  257.71  5412.1   259.2  5417.4  259.89  5467.6  261.22  5534.7   264.6
#Mann= 5 ,-1 , 0
  4744.1     .11       0  4877.4     .15       0  4930.1     .11       0
  4978.8     .06       0  5017.2     .11       0
Bank Sta=4978.8,5017.2
XS Rating Curve= 0 ,0
Exp/Cntr=0.3,0.1

Type RM Length L Ch R = 1 ,2900    ,411,411,411
BEGIN DESCRIPTION:
WFSJR 097 6.0
END DESCRIPTION:
XS GIS Cut Line= 3
      3776860.54     10222380.89      3776614.01     10222349.64
      3776072.61     10222564.81
#Sta/Elev= 30
  4573.1  260.98  4606.1   259.7  4611.2  258.83  4626.2  258.94  4666.5  257.36
  4686.3  255.82  4691.3  255.92  4706.9  254.33    4866  248.05    4882  247.63
  4914.3  248.29  4989.6  248.27  5009.2  247.06  5009.4  246.56  5021.9  247.57
  5052.2  248.25  5075.7  249.34  5081.9  250.13  5087.3  249.85  5106.2  252.18
  5111.6  252.07  5118.8  253.05  5129.5  253.57  5165.6  253.99  5189.9  255.58
  5219.5   256.1  5237.1  257.82  5297.8  259.37  5387.8  267.54  5404.2  267.95
#Mann= 3 , 0 , 0
  4573.1     .11       0  4989.6     .06       0  5052.2     .11       0
Bank Sta=4989.6,5052.2
XS Rating Curve= 0 ,0
Exp/Cntr=0.3,0.1

Type RM Length L Ch R = 1 ,2489    ,420,420,420
BEGIN DESCRIPTION:
WFSJR 097 5.0
END DESCRIPTION:
XS GIS Cut Line= 3
      3776850.09     10222241.98       3776614.3     10222121.77
      3776081.07      10222047.8
#Sta/Elev= 30
  4517.2  257.93  4533.4  257.41  4542.2  256.23  4564.6  255.89  4577.8  254.56
  4594.5  254.53  4638.9  251.98  4777.6  247.01  4848.9  245.94  4877.1  246.05
  4900.3  244.02  4907.5   242.3  4907.8   241.8  4911.3   241.8  4911.5   242.3
  4919.6  242.99  4939.8     246  4949.9  246.43    4960  245.85    4972  246.17
  4980.2  245.32  4990.3  243.12  5010.5  246.15  5043.7  247.36  5091.2  252.33
  5151.8  254.93  5258.9  261.03    5264  260.45    5273  260.82  5320.2  264.69
#Mann= 5 ,-1 , 0
  4517.2     .11       0  4777.6     .15       0  4848.9     .11       0
  4877.1     .06       0  4939.8     .11       0
Bank Sta=4877.1,4939.8
XS Rating Curve= 0 ,0
Exp/Cntr=0.3,0.1

Type RM Length L Ch R = 1 ,2069    ,472,472,472
BEGIN DESCRIPTION:
WFSJR 097 4.0
END DESCRIPTION:
XS GIS Cut Line= 3
       3776996.7      10222091.9      3776777.39     10221906.88
      3776141.21     10221752.81
#Sta/Elev= 30
  4374.4  256.09  4529.9  249.68  4572.6   248.9    4622  246.88  4629.8  247.08
  4681.4  245.62    4702  245.72  4714.6  245.01    4848  243.22  4856.3  242.18
  4866.6  241.74  4874.5  242.41  4879.6  241.82  4887.2  242.62  4907.8  242.06
  4948.9  243.36  4979.8  243.08  4990.1  241.86  4997.9  240.11  4998.2  239.61
  5001.7  239.61  5001.9  240.11  5010.7  241.62  5031.3  242.92  5082.7  243.98
  5144.4  248.66  5261.2  254.75  5288.5  256.71    5303  257.02  5315.9  258.09
#Mann= 5 ,-1 , 0
  4374.4     .11       0  4714.6     .15       0    4848     .11       0
  4979.8     .06       0  5031.3     .11       0
Bank Sta=4979.8,5031.3
XS Rating Curve= 0 ,0
Exp/Cntr=0.3,0.1

Type RM Length L Ch R = 1 ,1597    ,546,546,546
BEGIN DESCRIPTION:
WFSJR 097 3.0
END DESCRIPTION:
XS GIS Cut Line= 3
      3777066.15     10221567.78      3776860.54     10221530.19
      3776141.27     10221554.44
#Sta/Elev= 30
  4488.5  252.51  4537.6  251.97  4553.2  250.93  4606.4  248.99  4611.5  249.13
  4669.8  246.68  4720.2  243.83  4730.2  244.06  4740.2  243.12  4818.7  241.33
  4873.7  240.89  4920.3   241.4  4950.3  240.99  4980.4  241.32  4990.4  240.01
  4998.4   237.9  4998.6   237.4  5010.4  238.06  5030.4  240.67  5050.4  241.03
  5090.4   241.6  5160.5  244.04  5230.5   245.8  5280.5   248.7  5310.6  251.75
  5330.6   252.2  5350.6  253.43  5380.6  254.54  5400.6   255.9  5417.2  256.38
#Mann= 5 ,-1 , 0
  4488.5     .11       0  4818.7     .15       0  4920.3     .11       0
  4980.4     .06       0  5050.4     .11       0
Bank Sta=4980.4,5050.4
XS Rating Curve= 0 ,0
Exp/Cntr=0.3,0.1

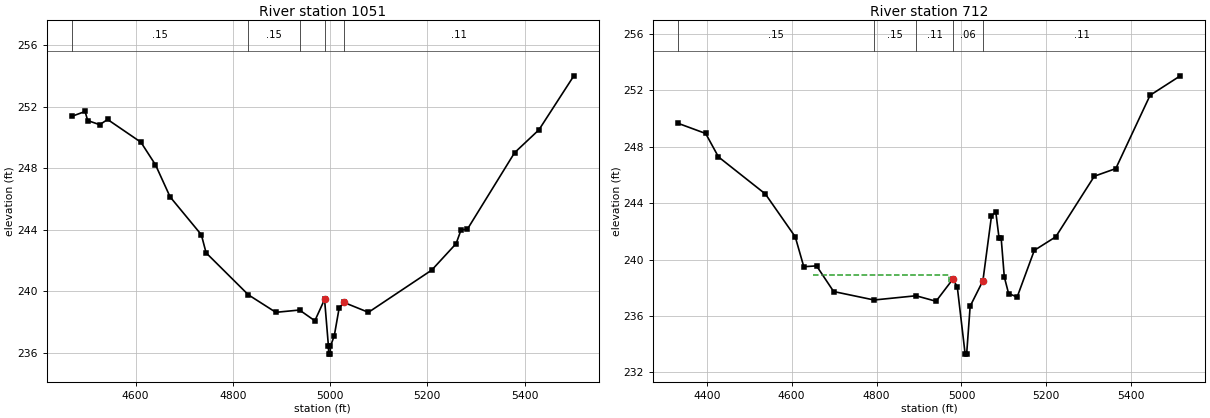
Type RM Length L Ch R = 1 ,1051    ,339,339,339
BEGIN DESCRIPTION:
WFSJR 097 2.0
END DESCRIPTION:
XS GIS Cut Line= 3
      3777096.85     10221256.65      3776804.98     10221144.78
      3776086.27     10221189.91
#Sta/Elev= 30
  4468.6  251.37  4496.2  251.69  4501.6   251.1  4526.3  250.83  4542.5  251.17
    4611  249.69    4641  248.22  4671.1  246.13  4735.3  243.67  4745.1  242.49
    4832  239.76  4888.5  238.62  4937.2  238.77  4968.7  238.07  4988.7  239.46
  4996.7   236.4    4997   235.9  5000.5   235.9  5000.7   236.4  5008.7   237.1
  5018.8  238.92  5028.8  239.26  5078.9  238.62  5209.1  241.37  5259.2  243.09
  5269.3  243.98  5282.4  244.03  5379.5  249.01  5429.6   250.5  5501.3  254.01
#Mann= 5 ,-1 , 0
  4468.6     .15       0    4832     .15       0  4937.2     .11       0
  4988.7     .06       0  5028.8     .11       0
Bank Sta=4988.7,5028.8
XS Rating Curve= 0 ,0
Exp/Cntr=0.3,0.1

Type RM Length L Ch R = 1 ,712     ,0,0,0
BEGIN DESCRIPTION:
WFSJR 097 1.0
END DESCRIPTION:
XS GIS Cut Line= 3
      3777122.41     10220997.03      3776367.48     10220922.55
       3775947.3     10220863.52
#Sta/Elev= 30
  4332.6  249.67  4397.5  248.95  4427.6  247.29  4538.1  244.66  4608.5  241.62
  4628.6   239.5  4658.7  239.56  4698.9  237.74  4794.2  237.14    4893  237.44
  4940.1  237.05  4980.3  238.64  4990.3  238.04  5008.7   233.3  5012.2   233.3
  5020.5   236.7  5050.5   238.5  5070.7  243.09  5080.8   243.4  5088.5  241.55
  5093.5  241.55  5100.9  238.78    5111   237.6  5131.2  237.35  5171.6  240.66
  5222.1  241.62    5313  245.92  5363.5  246.46  5444.3  251.66  5515.5  253.04
#Mann= 5 ,-1 , 0
  4332.6     .15       0  4794.2     .15       0    4893     .11       0
  4980.3     .06       0  5050.5     .11       0
#XS Ineff= 2 ,-1
    4650  4970.2  238.92  5080.8    5300   243.4
Permanent Ineff=
       T       F
Bank Sta=4980.3,5050.5
XS Rating Curve= 0 ,0
Exp/Cntr=0.3,0.1

Chan Stop Cuts=-1
Use User Specified Reach Order=0
Composite Channel Slope=5